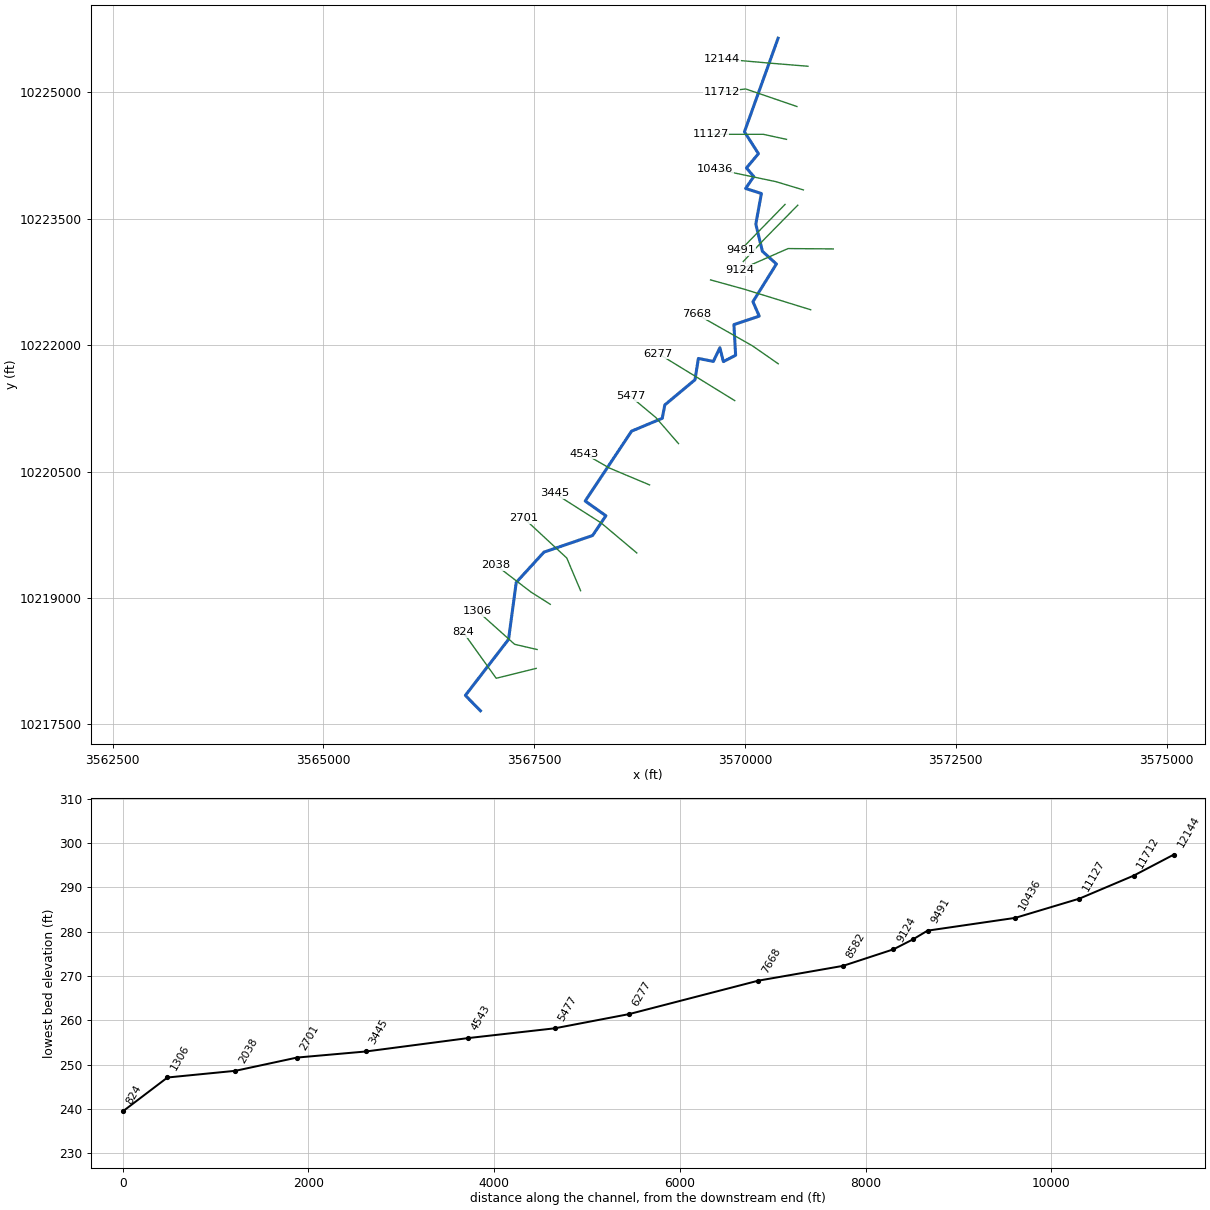
--- HARVEY HILLSIDES CREEK.prj (project) ---

Proj Title=HARVEY HILLSIDES CREEK Base Level Engineering
Current Plan=p01
Default Exp/Contr=0.3,0.1
English Units
Geom File=g01
Flow File=f01
Plan File=p01
Y Axis Title=Elevation
X Axis Title(PF)=Main Channel Distance
X Axis Title(XS)=Station
BEGIN DESCRIPTION:
HARVEY HILLSIDES CREEK
END DESCRIPTION:
DSS Export Rating Curves= 0
DSS Export Rating Curve Sorted= 0
DSS Export Volume Flow Curves= 0
DXF OffsetX= 0
DXF OffsetY= 0
DXF ScaleX= 1
DXF ScaleY= 10

--- HARVEY HILLSIDES CREEK.p01 (plan) ---

Plan Title=Multiple Run
Short Identifier=Multiple
Geom File=g01
Flow File=f01
Subcritical Flow
K Sum by GR= 0
Std Step Tol= 0.01
Critical Tol= 0.01
Num of Std Step Trials= 20
Max Error Tol= 0.3
Flow Tol Ratio= 0.001
Split Flow NTrial= 30
Split Flow Tol= 0.02
Split Flow Ratio= 0.02
Log Output Level= 0
Friction Slope Method= 1
Unsteady Friction Slope Method= 2
Unsteady Bridges Friction Slope Method= 1
Parabolic Critical Depth
Global Vel Dist=  1 , 1 , 1
Global Log Level= 0
CheckData=True
Encroach Param= -1, 0, 0, 0
BEGIN DESCRIPTION:
Multiple Run
END DESCRIPTION:

--- HARVEY HILLSIDES CREEK.f01 (steady flow) ---

Flow Title=Multiple
Number of Profiles=7
Profile Names=10-year,25-year,50-year,1pct_min,100-year,1pct_plu,500-year
River Rch & RM= HARVEY HILLSIDES,Reach-1,12144
     245     312     363     311     420     568     563
River Rch & RM= HARVEY HILLSIDES,Reach-1,9335
     590     793     958     848    1147    1551    1647
Boundary for River Rch & Prof#=HARVEY HILLSIDES,Reach-1,1
Up Type=0
Dn Type=3
Dn Slope=0.005
Boundary for River Rch & Prof#=HARVEY HILLSIDES,Reach-1,2
Up Type=0
Dn Type=3
Dn Slope=0.005
Boundary for River Rch & Prof#=HARVEY HILLSIDES,Reach-1,3
Up Type=0
Dn Type=3
Dn Slope=0.005
Boundary for River Rch & Prof#=HARVEY HILLSIDES,Reach-1,4
Up Type=0
Dn Type=3
Dn Slope=0.005
Boundary for River Rch & Prof#=HARVEY HILLSIDES,Reach-1,5
Up Type=0
Dn Type=3
Dn Slope=0.005
Boundary for River Rch & Prof#=HARVEY HILLSIDES,Reach-1,6
Up Type=0
Dn Type=3
Dn Slope=0.005
Boundary for River Rch & Prof#=HARVEY HILLSIDES,Reach-1,7
Up Type=0
Dn Type=3
Dn Slope=0.005

--- HARVEY HILLSIDES CREEK.g01 (geometry) ---

Geom Title=Existing Conditions
Program Version=4.10

River Reach=HARVEY HILLSIDES,Reach-1
Reach XY= 30
      3570392.34     10225641.65      3569993.31     10224531.35
      3570159.29     10224271.54      3570016.99     10224101.93
      3570103.79     10224000.37      3570007.44     10223858.87
      3570194.07     10223798.98       3570128.1     10223436.13
      3570206.03      10223113.8      3570372.21     10222962.63
      3570093.96     10222515.53      3570168.48     10222344.15
       3569868.4     10222243.81      3569888.73     10221879.47
      3569743.32     10221804.72      3569702.03     10221969.66
      3569624.45     10221806.79      3569447.02     10221841.82
      3569406.68     10221589.38      3569048.73     10221290.17
      3569018.35     10221131.75      3568654.84     10220979.57
       3568104.5     10220150.17      3568350.16     10219975.43
      3568192.27     10219741.02      3567615.61     10219543.95
      3567286.82     10219184.41      3567195.74     10218508.74
      3566683.76     10217844.02      3566862.11     10217661.64

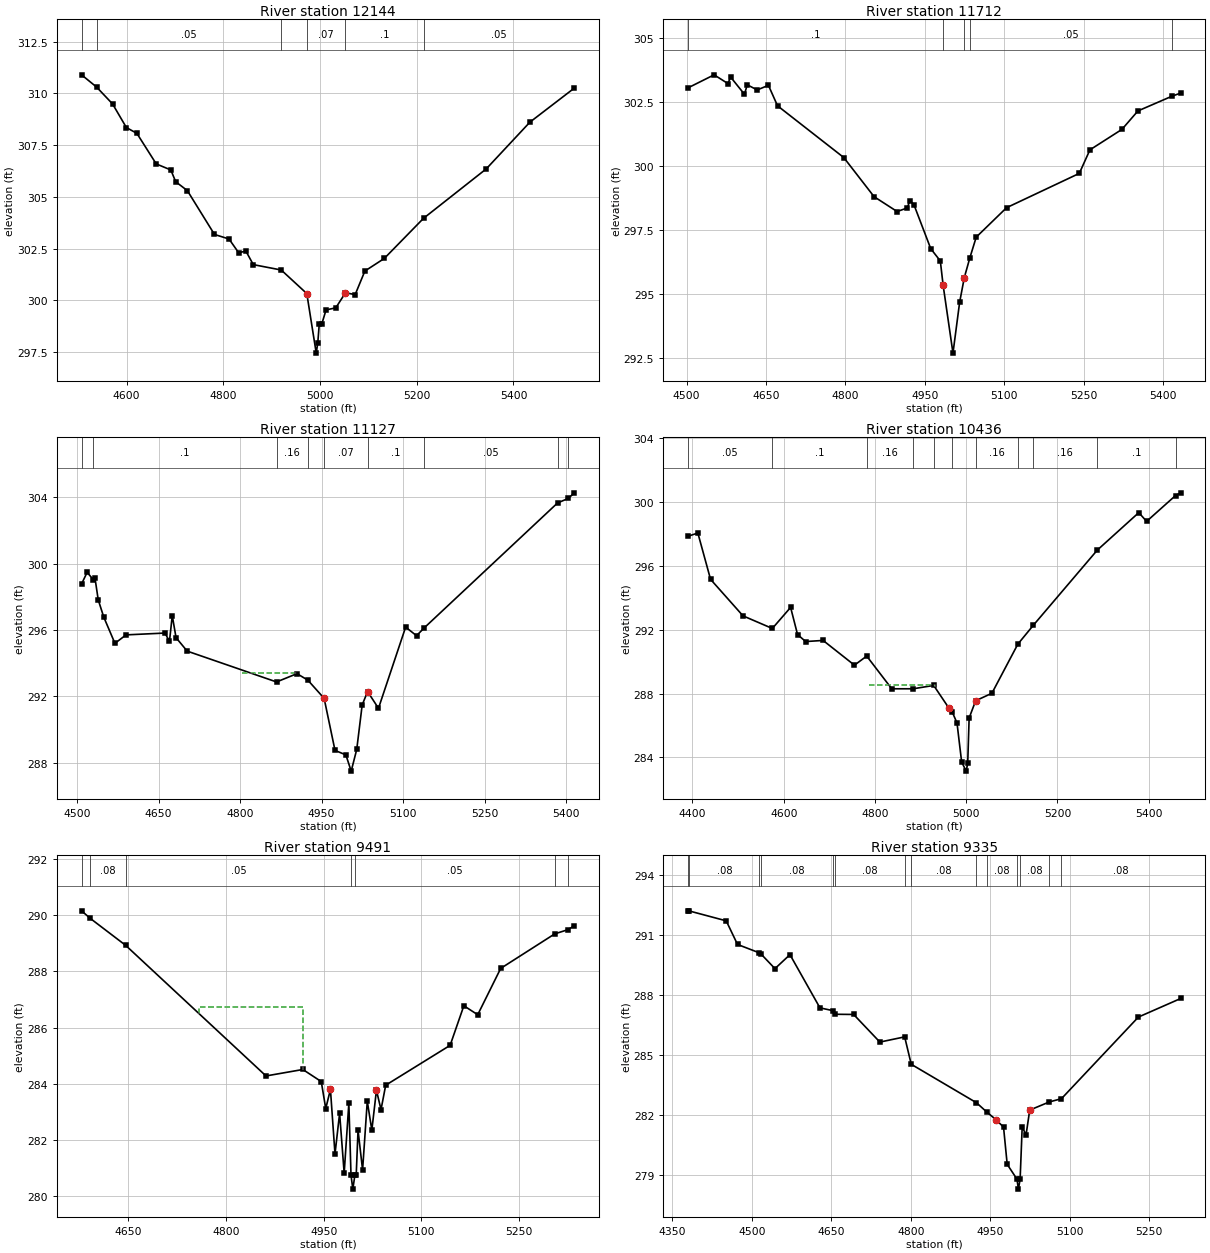
Type RM Length L Ch R = 1 ,12144   ,432,432,432
BEGIN DESCRIPTION:
HARVEY HILLSIDES CREEK 25.0
END DESCRIPTION:
XS GIS Cut Line= 3
       3570746.1     10225308.73      3570255.29     10225349.22
      3569730.51     10225395.54
#Sta/Elev= 30
  4506.7   310.9  4537.7  310.31  4570.9  309.49  4599.4  308.35  4621.1  308.07
  4661.2  306.59  4691.3   306.3  4701.4  305.73  4725.5   305.3  4781.6  303.18
  4811.7  302.96  4831.8  302.29  4846.5  302.38  4861.9  301.72  4919.7  301.46
  4972.6  300.32  4992.1  297.44  4995.3  297.94  4998.3  298.83  5003.3  298.83
  5012.4  299.53  5032.5  299.63  5052.6  300.36  5072.6  300.27  5092.7  301.41
  5132.9  302.02    5214  303.96  5343.7  306.35    5434  308.61    5526  310.26
#Mann= 6 ,-1 , 0
  4506.7      .1       0  4537.7     .05       0  4919.7      .1       0
  4972.6     .07       0  5052.6      .1       0    5214     .05       0
Bank Sta=4972.6,5052.6
XS Rating Curve= 0 ,0
Exp/Cntr=0.3,0.1

Type RM Length L Ch R = 1 ,11712   ,585,585,585
BEGIN DESCRIPTION:
HARVEY HILLSIDES CREEK 23.0
END DESCRIPTION:
XS GIS Cut Line= 3
      3570615.88     10224831.31      3570008.25     10225039.64
       3569721.8     10225004.92
#Sta/Elev= 30
  4502.5  303.05  4551.9  303.56  4577.9  303.22  4583.2  303.47  4609.2   302.8
  4614.5  303.17  4633.3  302.97  4654.5  303.15  4671.7  302.35  4796.8  300.33
  4854.1   298.8  4897.6  298.22  4916.6  298.36  4921.9  298.65  4929.3  298.49
  4961.1  296.77  4979.2  296.29  4984.5  295.34  5003.1  292.69  5015.7  294.68
  5024.5  295.64  5035.1  296.42    5047  297.22  5104.3  298.37  5241.7  299.71
  5261.8  300.63  5322.3  301.43  5352.5  302.15  5416.2  302.72  5433.4  302.85
#Mann= 5 ,-1 , 0
  4502.5      .1       0  4984.5     .07       0  5024.5      .1       0
  5035.1     .05       0  5416.2      .1       0
Bank Sta=4984.5,5024.5
XS Rating Curve= 0 ,0
Exp/Cntr=0.3,0.1

Type RM Length L Ch R = 1 ,11127   ,691,691,691
BEGIN DESCRIPTION:
HARVEY HILLSIDES CREEK 22.0
END DESCRIPTION:
XS GIS Cut Line= 3
       3570492.1     10224441.64      3570216.58     10224501.44
      3569591.61     10224501.44
#Sta/Elev= 30
  4508.3  298.78  4518.5  299.48  4530.1  299.04  4532.9  299.16    4539  297.82
  4549.2  296.78  4569.7   295.2  4590.2  295.71  4661.8  295.82  4670.1  295.32
  4675.2  296.87  4682.2  295.54  4702.7  294.73  4867.1  292.87  4904.7  293.37
  4924.7  292.98  4954.7  291.88  4974.7  288.74  4994.7  288.47  5004.5  287.49
  5014.7   288.8  5024.7  291.48  5034.7  292.29  5054.7  291.28  5104.7  296.18
  5124.7  295.66  5138.8  296.13  5384.3  303.67  5403.8  303.94  5415.2  304.28
#Mann= 9 ,-1 , 0
  4508.3     .16       0  4530.1      .1       0  4867.1     .16       0
  4924.7      .1       0  4954.7     .07       0  5034.7      .1       0
  5138.8     .05       0  5384.3      .1       0  5403.8     .05       0
#XS Ineff= 1 ,-1
 4804.32 4904.55  293.43
Permanent Ineff=
       F
Bank Sta=4954.7,5034.7
XS Rating Curve= 0 ,0
Exp/Cntr=0.3,0.1

Type RM Length L Ch R = 1 ,10436   ,945,945,945
BEGIN DESCRIPTION:
HARVEY HILLSIDES CREEK 21.0
END DESCRIPTION:
XS GIS Cut Line= 3
      3570692.07     10223841.65       3570365.6     10223939.94
      3569642.07     10224091.65
#Sta/Elev= 30
  4390.1  297.86  4411.8  298.06  4439.6  295.16  4510.8  292.87    4575  292.08
  4615.1   293.4  4630.3   291.7  4648.1  291.26  4686.3  291.33    4755  289.78
  4781.9  290.35  4836.8   288.3  4883.6   288.3  4928.7  288.51  4961.6  287.11
  4969.6  286.83  4979.8  286.16    4990  283.71    5000  283.14  5003.3  283.64
  5006.4  286.47  5020.7  287.55  5056.3  288.02  5113.2   291.1  5147.4  292.29
  5287.3  296.99  5378.3  299.34  5395.4  298.79  5458.8  300.41  5470.3  300.58
#Mann= 11 ,-1 , 0
  4390.1     .05       0    4575      .1       0  4781.9     .16       0
  4883.6      .1       0  4928.7     .16       0  4969.6     .07       0
  5020.7     .16       0  5113.2      .1       0  5147.4     .16       0
  5287.3      .1       0  5458.8     .05       0
#XS Ineff= 1 ,-1
 4786.25 4931.02  288.56
Permanent Ineff=
       F
Bank Sta=4961.6,5020.7
XS Rating Curve= 0 ,0
Exp/Cntr=0.3,0.1

Type RM Length L Ch R = 1 ,9491    ,156,156,156
BEGIN DESCRIPTION:
HARVEY HILLSIDES CREEK 20.0
END DESCRIPTION:
XS GIS Cut Line= 3
      3570474.87     10223669.62      3570180.18     10223367.55
      3569946.19     10223127.53
#Sta/Elev= 30
    4578  290.16  4591.4  289.89  4645.8  288.93  4861.4  284.28    4918  284.51
  4946.3  284.08  4953.2  283.12  4960.4   283.8  4967.4   281.5  4974.5  282.95
  4981.5  280.82  4988.7  283.31    4992  280.75  4994.8  280.25    4998  280.75
    5000  280.75  5002.8  282.35  5009.8  280.93    5017  283.38    5024  282.35
  5031.1  283.77  5038.1  283.08  5045.3  283.95  5144.3  285.37  5165.4  286.78
  5186.7  286.46    5222  288.11  5305.1  289.34  5325.4  289.49  5335.2  289.63
#Mann= 7 ,-1 , 0
    4578     .05       0  4591.4     .08       0  4645.8     .05       0
    4992     .04       0    4998     .05       0  5305.1     .08       0
  5325.4     .05       0
#XS Ineff= 1 ,-1
 4758.73 4917.91  286.73
Permanent Ineff=
       F
Bank Sta=4960.4,5031.1
XS Rating Curve= 0 ,0
Exp/Cntr=0.3,0.1

Type RM Length L Ch R = 1 ,9335    ,211,211,211
BEGIN DESCRIPTION:
HARVEY HILLSIDES CREEK 19.0
END DESCRIPTION:
XS GIS Cut Line= 3
      3570625.55     10223660.38      3570238.15      10223266.5
      3569978.84     10222991.97
#Sta/Elev= 30
  4379.2   292.2  4382.1  292.19  4451.4   291.7  4472.7  290.52  4513.9   290.1
  4517.5  290.03  4543.4  289.31  4571.7  290.01  4628.3  287.35  4652.9  287.21
  4657.3  287.03  4691.9  287.02  4741.4  285.64  4788.2   285.9  4800.6  284.53
  4923.6  282.61  4943.8  282.13  4960.6  281.76  4974.8  281.39  4981.7  279.53
  5000.1  278.79  5002.9  278.29  5006.1  278.79    5010   281.4  5017.3     281
  5024.2  282.24  5061.4  282.65  5084.1  282.81  5229.3  286.89  5309.3  287.82
#Mann= 14 ,-1 , 0
  4379.2     .05       0  4382.1     .08       0  4513.9     .05       0
  4517.5     .08       0  4652.9     .05       0  4657.3     .08       0
  4788.2     .05       0  4800.6     .08       0  4923.6     .05       0
  4943.8     .08       0  5000.1     .07       0  5006.1     .08       0
  5061.4     .05       0  5084.1     .08       0
Bank Sta=4960.6,5024.2
XS Rating Curve= 0 ,0
Exp/Cntr=0.3,0.1

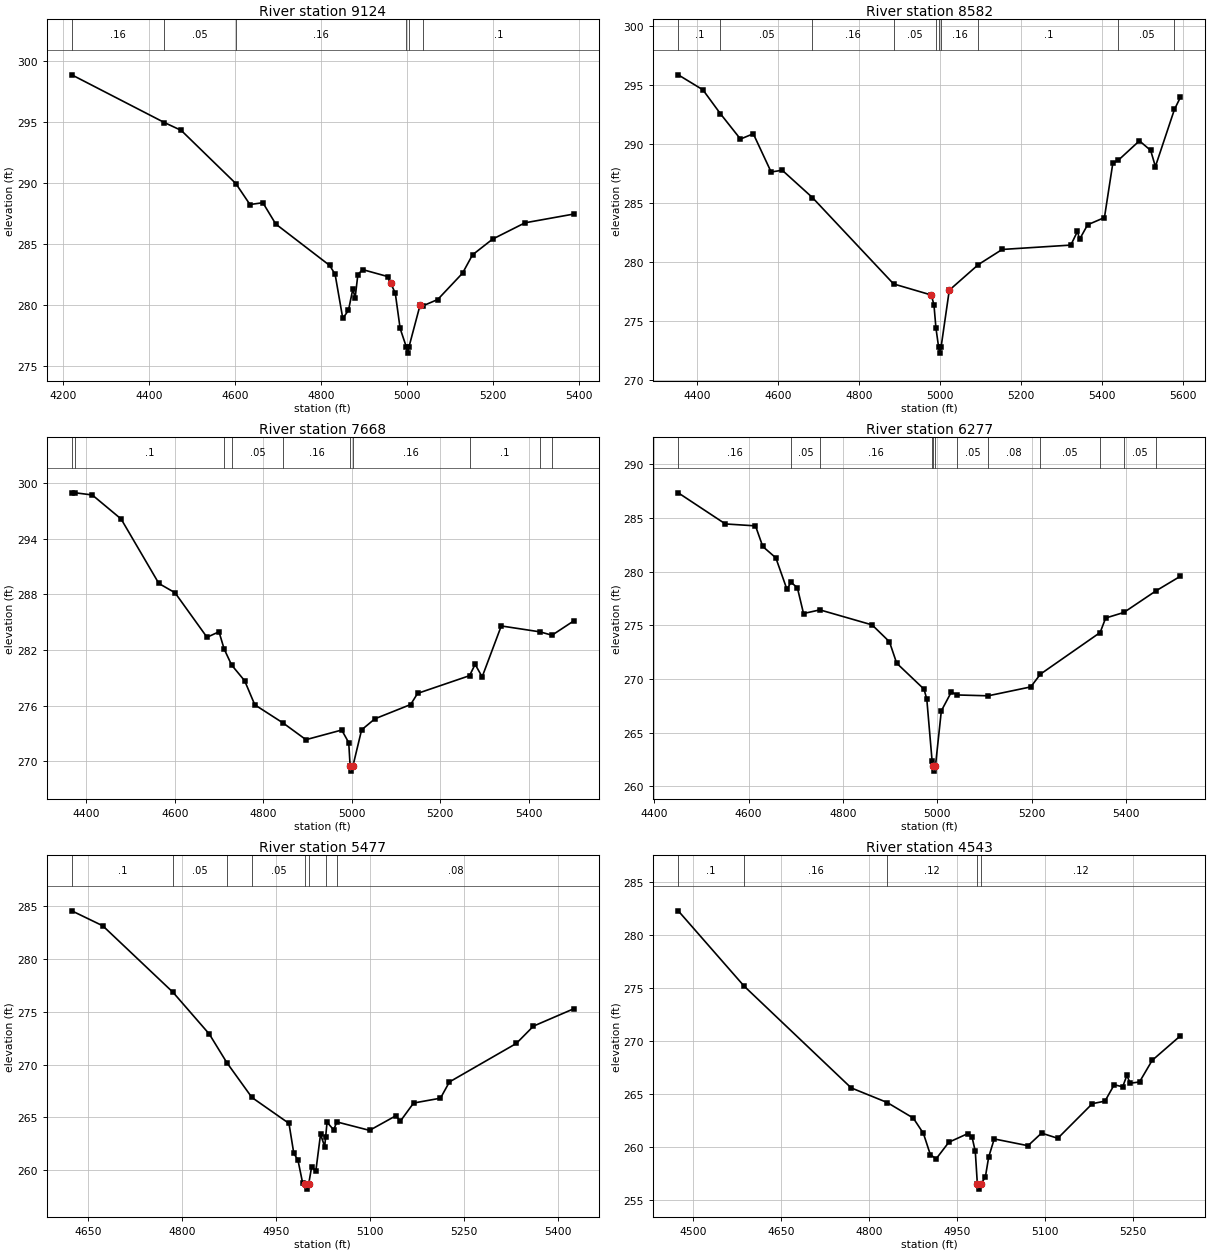
Type RM Length L Ch R = 1 ,9124    ,542,542,542
BEGIN DESCRIPTION:
HARVEY HILLSIDES CREEK 18.0
END DESCRIPTION:
XS GIS Cut Line= 3
       3571046.6     10223141.72       3570510.2     10223145.83
      3569932.32     10222891.21
#Sta/Elev= 30
  4220.7  298.88  4436.2  294.96  4475.2  294.32  4602.4  289.95  4635.2  288.23
  4665.2  288.38  4695.2  286.63  4820.6  283.23  4833.2  282.51  4851.1  278.88
  4864.3  279.54  4874.4  281.27  4879.9  280.58  4886.2  282.48  4897.1  282.89
  4955.4  282.32  4962.7  281.76  4973.2  280.96  4984.5  278.06    4999  276.53
  5001.8  276.03    5005  276.53  5030.8  279.96  5037.9  279.92  5071.9  280.43
  5129.6  282.59  5152.9   284.1  5199.6  285.39    5275  286.73  5388.6  287.45
#Mann= 6 ,-1 , 0
  4220.7     .16       0  4436.2     .05       0  4602.4     .16       0
    4999     .07       0    5005     .16       0  5037.9      .1       0
Bank Sta=4962.7,5030.8
XS Rating Curve= 0 ,0
Exp/Cntr=0.3,0.1

Type RM Length L Ch R = 1 ,8582    ,914,914,914
BEGIN DESCRIPTION:
HARVEY HILLSIDES CREEK 17.0
END DESCRIPTION:
XS GIS Cut Line= 3
      3570779.12     10222419.83      3569987.41     10222664.64
      3569591.54     10222774.02
#Sta/Elev= 30
  4354.3  295.87  4415.2   294.6  4458.3  292.58  4507.9  290.43  4539.6  290.88
  4583.6  287.64    4611  287.79  4685.4  285.48  4885.9  278.16  4979.2  277.22
  4985.6  276.37  4990.5  274.41  4997.1   272.8  4999.9   272.3  5003.1   272.8
  5023.4  277.63  5095.2   279.8  5153.9  281.08  5323.4  281.45  5339.8  282.61
    5345  281.94  5364.9  283.17  5406.4  283.78  5427.1  288.38  5441.1  288.65
  5492.7  290.28  5520.5  289.47  5532.2   288.1  5579.2  292.94  5593.7  293.95
#Mann= 10 ,-1 , 0
  4354.3      .1       0  4458.3     .05       0  4685.4     .16       0
  4885.9     .05       0  4990.5     .16       0  4997.1     .07       0
  5003.1     .16       0  5095.2      .1       0  5441.1     .05       0
  5579.2      .1       0
Bank Sta=4979.2,5023.4
XS Rating Curve= 0 ,0
Exp/Cntr=0.3,0.1

Type RM Length L Ch R = 1 ,7668    ,1391,1391,1391
BEGIN DESCRIPTION:
HARVEY HILLSIDES CREEK 15.0
END DESCRIPTION:
XS GIS Cut Line= 3
       3570393.7     10221779.19      3570086.37     10221992.76
      3569424.93     10222367.76
#Sta/Elev= 30
  4367.3  298.88  4375.6  298.95  4413.6  298.72  4478.8  296.13  4564.1  289.18
  4600.6  288.18  4672.9  283.38    4700  283.97  4711.6  282.12  4728.5  280.39
    4758  278.69  4780.9   276.1  4845.4  274.12  4896.5  272.34  4977.3  273.38
  4993.2  272.02  4996.4  269.45  4999.1  268.95  5002.4  269.45  5022.3   273.4
  5052.3  274.59  5133.1  276.13  5148.8  277.33  5266.2  279.24  5278.8  280.46
  5294.7  279.11  5337.9   284.6  5425.8  283.96  5452.5   283.6  5501.9  285.15
#Mann= 10 ,-1 , 0
  4367.3     .16       0  4375.6      .1       0  4711.6     .08       0
  4728.5     .05       0  4845.4     .16       0  4996.4     .07       0
  5002.4     .16       0  5266.2      .1       0  5425.8     .05       0
  5452.5      .1       0
Bank Sta=4996.4,5002.4
XS Rating Curve= 0 ,0
Exp/Cntr=0.3,0.1

Type RM Length L Ch R = 1 ,6277    ,800,800,800
BEGIN DESCRIPTION:
HARVEY HILLSIDES CREEK 13.0
END DESCRIPTION:
XS GIS Cut Line= 3
      3569878.07      10221341.7      3569392.11     10221641.64
      3568971.81       10221899.
#Sta/Elev= 30
  4450.8  287.34  4550.7  284.44  4614.5  284.26  4629.9  282.34  4657.6  281.28
  4681.1  278.35  4689.7     279  4703.2   278.5  4716.3  276.09    4751  276.43
  4861.6  275.03  4898.3  273.46  4913.7  271.46  4971.6  269.04  4977.5  268.11
  4988.8  262.31  4989.9   261.9  4992.7   261.4  4995.9   261.9  5008.3  267.02
  5029.6  268.78  5041.6   268.5  5107.5  268.42  5197.8  269.25  5218.3  270.44
  5344.8  274.32  5356.5  275.67  5395.1  276.19  5463.4  278.21  5514.7  279.56
#Mann= 12 ,-1 , 0
  4450.8     .16       0  4689.7     .05       0    4751     .16       0
  4988.8     .08       0  4989.9     .07       0  4995.9     .08       0
  5041.6     .05       0  5107.5     .08       0  5218.3     .05       0
  5344.8     .08       0  5395.1     .05       0  5463.4     .08       0
Bank Sta=4989.9,4995.9
XS Rating Curve= 0 ,0
Exp/Cntr=0.3,0.1

Type RM Length L Ch R = 1 ,5477    ,934,934,934
BEGIN DESCRIPTION:
HARVEY HILLSIDES CREEK 11.0
END DESCRIPTION:
XS GIS Cut Line= 3
      3569211.35     10220831.33      3568942.11     10221141.64
      3568642.07     10221391.67
#Sta/Elev= 30
  4623.8  284.57  4673.3  283.15  4785.5  276.84  4843.3  272.89  4871.2  270.19
  4911.3  266.88  4970.5  264.42  4978.2  261.58  4984.8  260.95  4992.4  258.74
    4996  258.69  4998.8  258.19    5002  258.69  5006.6  260.28  5013.3  259.87
  5020.9   263.4  5027.5  262.21    5029  263.13  5031.3  264.53  5041.8  263.81
  5046.9  264.56  5099.1  263.76  5140.7  265.13  5148.5  264.65  5169.4  266.35
  5212.3  266.81  5226.6  268.35  5333.4     272  5360.7  273.64  5425.2  275.29
#Mann= 8 ,-1 , 0
  4623.8      .1       0  4785.5     .05       0  4871.2     .12       0
  4911.3     .05       0    4996     .04       0    5002     .05       0
    5029     .12       0  5046.9     .08       0
Bank Sta=4996,5002
XS Rating Curve= 0 ,0
Exp/Cntr=0.3,0.1

Type RM Length L Ch R = 1 ,4543    ,1098,1098,1098
BEGIN DESCRIPTION:
HARVEY HILLSIDES CREEK 9.0
END DESCRIPTION:
XS GIS Cut Line= 3
      3568867.66      10220341.7      3568392.11     10220541.64
      3568096.93     10220711.43
#Sta/Elev= 30
  4474.8  282.26    4587  275.16  4769.8  265.54  4831.2  264.16  4875.7  262.69
    4893  261.24  4904.8  259.24  4914.7  258.84  4936.4  260.41    4969  261.23
  4976.1  260.86  4981.5  259.54    4985  256.48  4987.7  255.98    4991  256.48
  4998.6   257.1  5004.3     259  5013.8  260.72  5071.4  260.08  5094.5  261.27
  5122.2  260.78  5181.1  264.05  5202.7  264.29  5218.5  265.84  5232.9  265.64
    5240  266.71  5245.8  265.98  5261.6   266.1  5283.2  268.14  5331.2  270.45
#Mann= 5 ,-1 , 0
  4474.8      .1       0    4587     .16       0  4831.2     .12       0
    4985     .07       0    4991     .12       0
Bank Sta=4985,4991
XS Rating Curve= 0 ,0
Exp/Cntr=0.3,0.1

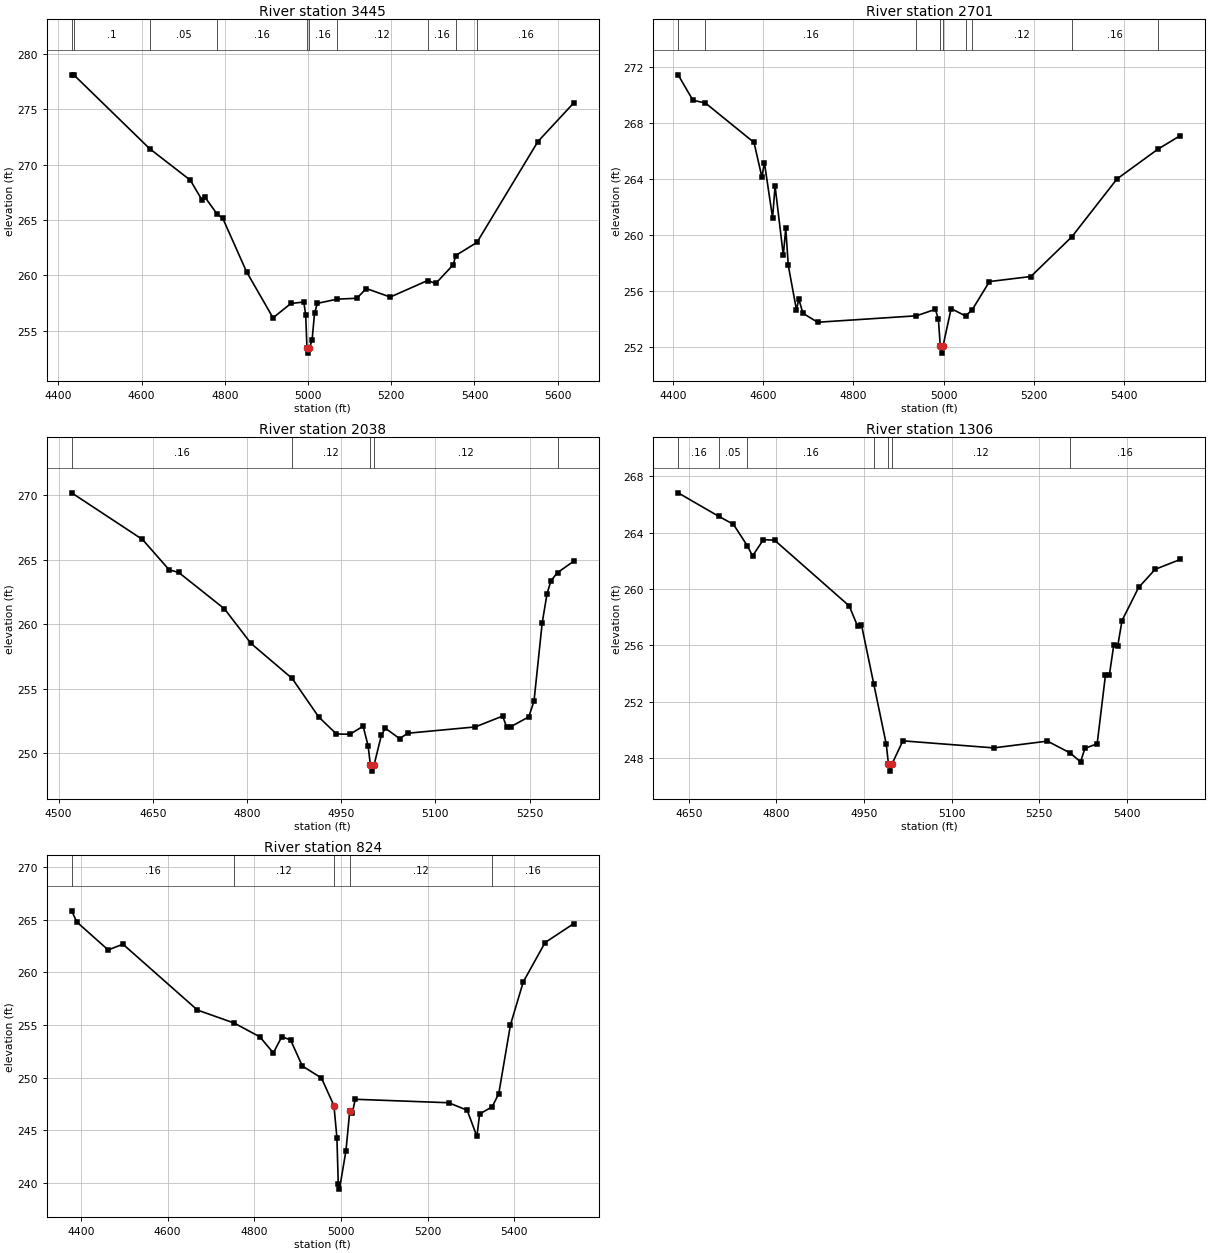
Type RM Length L Ch R = 1 ,3445    ,744,744,744
BEGIN DESCRIPTION:
HARVEY HILLSIDES CREEK 7.0
END DESCRIPTION:
XS GIS Cut Line= 3
      3568716.61      10219534.4      3568292.11     10219891.64
      3567742.14     10220241.62
#Sta/Elev= 30
  4432.1  278.06  4437.2  278.12  4619.6  271.44  4717.1   268.6  4745.7  266.78
  4752.2  267.07  4782.2   265.5  4795.1  265.16  4852.3  260.32    4916  256.15
  4958.9  257.45  4989.9  257.58  4994.5  256.41  4997.5  253.46  5000.2  252.96
  5003.5  253.46  5009.8  254.12  5015.7  256.55  5022.5  257.46  5070.1  257.84
  5117.3  257.92  5140.2   258.8  5197.7  258.03  5287.2  259.52    5307  259.26
  5349.3  260.96  5354.8  261.78    5406  262.97  5552.5  272.09  5638.8  275.59
#Mann= 10 ,-1 , 0
  4432.1     .16       0  4437.2      .1       0  4619.6     .05       0
  4782.2     .16       0  4997.5     .07       0  5003.5     .16       0
  5070.1     .12       0  5287.2     .16       0  5354.8     .12       0
    5406     .16       0
Bank Sta=4997.5,5003.5
XS Rating Curve= 0 ,0
Exp/Cntr=0.3,0.1

Type RM Length L Ch R = 1 ,2701    ,663,663,663
BEGIN DESCRIPTION:
HARVEY HILLSIDES CREEK 5.0
END DESCRIPTION:
XS GIS Cut Line= 3
      3568049.91     10219086.51       3567886.3     10219474.07
      3567378.02      10219945.9
#Sta/Elev= 30
    4411  271.41  4443.8   269.6  4471.6   269.4  4579.4  266.59  4596.9  264.12
  4602.4  265.16  4620.6  261.22  4626.1  263.49  4644.4  258.55  4649.8  260.48
  4655.4  257.83  4673.5  254.68  4678.9  255.42  4687.9  254.42  4720.5  253.78
  4939.8  254.24  4981.6   254.7  4988.4  254.02  4992.7  252.08  4995.5  251.58
  4998.7  252.08  5016.7  254.75  5048.8  254.23  5063.3  254.66  5101.8  256.68
  5193.6  257.04  5284.6  259.87  5384.7  263.99  5475.4  266.11  5525.2  267.08
#Mann= 9 ,-1 , 0
    4411     .05       0  4471.6     .16       0  4939.8     .12       0
  4992.7     .07       0  4998.7     .12       0  5048.8     .16       0
  5063.3     .12       0  5284.6     .16       0  5475.4     .08       0
Bank Sta=4992.7,4998.7
XS Rating Curve= 0 ,0
Exp/Cntr=0.3,0.1

Type RM Length L Ch R = 1 ,2038    ,732,732,732
BEGIN DESCRIPTION:
HARVEY HILLSIDES CREEK 4.0
END DESCRIPTION:
XS GIS Cut Line= 3
      3567690.55     10218925.05      3567461.75     10219070.09
      3567042.09     10219391.66
#Sta/Elev= 30
  4520.9  270.18  4633.7  266.56  4676.1  264.21  4691.4     264  4764.2  261.18
  4806.4   258.5    4872  255.78  4914.3  252.79  4942.5  251.47  4964.2  251.45
    4985  252.08  4992.9  250.56  4996.5  249.09  4999.3  248.59  5002.5  249.09
  5014.1  251.38  5020.4  251.92  5043.1  251.11  5055.9  251.53  5163.6  252.02
  5207.1  252.86  5213.5  252.02  5219.8  252.03  5248.8   252.8  5257.1  254.03
  5270.1  260.09  5277.9  262.37  5284.2  263.37  5294.5  263.99  5320.5  264.88
#Mann= 5 ,-1 , 0
  4520.9     .16       0    4872     .12       0  4996.5     .07       0
  5002.5     .12       0  5294.5      .1       0
Bank Sta=4996.5,5002.5
XS Rating Curve= 0 ,0
Exp/Cntr=0.3,0.1

Type RM Length L Ch R = 1 ,1306    ,482,482,482
BEGIN DESCRIPTION:
HARVEY HILLSIDES CREEK 2.0
END DESCRIPTION:
XS GIS Cut Line= 3
      3567534.29     10218388.59      3567268.09     10218450.12
      3566831.13     10218841.75
#Sta/Elev= 30
  4631.8  266.84  4701.8  265.16  4726.4  264.61  4750.2  263.09  4759.3  262.36
  4777.7  263.51  4796.9  263.48  4924.8  258.81    4939  257.39  4945.7  257.49
  4966.9  253.26  4988.3  248.98    4992  247.58  4994.8  247.08    4998  247.58
  5016.7  249.23  5172.2  248.73  5264.2  249.21  5302.7  248.38    5321  247.74
  5328.5   248.7  5349.4  249.02  5363.6  253.89  5370.3   253.9  5377.8  256.02
  5384.5  255.93    5392  257.77  5420.4  260.12  5448.8  261.41  5491.8  262.11
#Mann= 7 ,-1 , 0
  4631.8     .16       0  4701.8     .05       0  4750.2     .16       0
  4966.9     .12       0    4992     .07       0    4998     .12       0
  5302.7     .16       0
Bank Sta=4992,4998
XS Rating Curve= 0 ,0
Exp/Cntr=0.3,0.1

Type RM Length L Ch R = 1 ,824     ,0,0,0
BEGIN DESCRIPTION:
HARVEY HILLSIDES CREEK 1.0
END DESCRIPTION:
XS GIS Cut Line= 3
      3567523.83     10218164.63      3567049.17     10218047.24
      3566659.31     10218591.69
#Sta/Elev= 30
  4378.5  265.83  4390.6  264.76  4462.7  262.12  4496.9  262.66  4668.7  256.41
  4753.8  255.17  4812.9  253.86  4843.8  252.34  4863.4  253.88  4883.6  253.57
  4910.6   251.1  4954.8  249.96  4983.6  247.34  4990.5  244.28  4993.6  239.91
  4996.4  239.41  5011.4  243.07    5020  246.78  5026.1  246.65  5032.8  247.94
  5248.4  247.61    5291   246.9  5313.5  244.41  5319.7  246.54  5348.8  247.23
  5363.9  248.48  5390.9  255.01  5420.4  259.08  5470.8  262.82  5537.1  264.62
#Mann= 5 ,-1 , 0
  4378.5     .16       0  4753.8     .12       0  4983.6     .07       0
    5020     .12       0  5348.8     .16       0
Bank Sta=4983.6,5020
XS Rating Curve= 0 ,0
Exp/Cntr=0.3,0.1

Chan Stop Cuts=-1
Use User Specified Reach Order=0
Composite Channel Slope=5