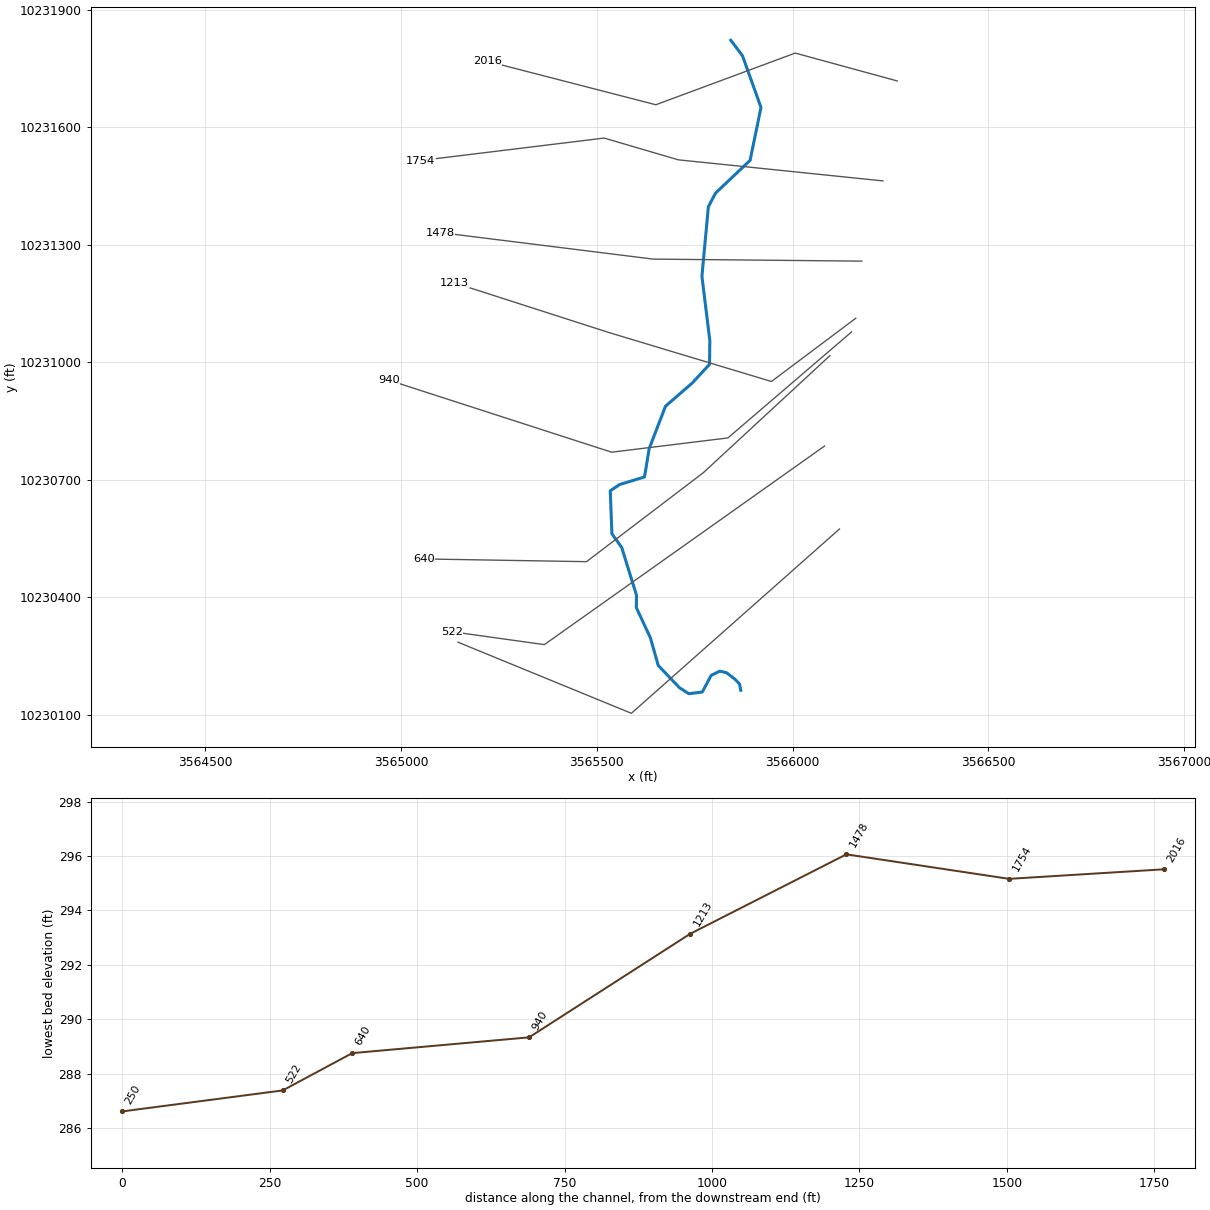
--- HUDSON CREEK TRIBUTARY 4 1.prj (project) ---

Proj Title=HUDSON CREEK TRIBUTARY 4 1 Base Level Engineering
Current Plan=p01
Default Exp/Contr=0.3,0.1
English Units
Geom File=g01
Flow File=f01
Plan File=p01
Y Axis Title=Elevation
X Axis Title(PF)=Main Channel Distance
X Axis Title(XS)=Station
BEGIN DESCRIPTION:
HUDSON CREEK TRIBUTARY 4 1
END DESCRIPTION:
DSS Export Rating Curves= 0
DSS Export Rating Curve Sorted= 0
DSS Export Volume Flow Curves= 0
DXF OffsetX= 0
DXF OffsetY= 0
DXF ScaleX= 1
DXF ScaleY= 10

--- HUDSON CREEK TRIBUTARY 4 1.p01 (plan) ---

Plan Title=Multiple Run
Short Identifier=Multiple
Geom File=g01
Flow File=f01
Subcritical Flow
K Sum by GR= 0
Std Step Tol= 0.01
Critical Tol= 0.01
Num of Std Step Trials= 20
Max Error Tol= 0.3
Flow Tol Ratio= 0.001
Split Flow NTrial= 30
Split Flow Tol= 0.02
Split Flow Ratio= 0.02
Log Output Level= 0
Friction Slope Method= 1
Unsteady Friction Slope Method= 2
Unsteady Bridges Friction Slope Method= 1
Parabolic Critical Depth
Global Vel Dist=  1 , 1 , 1
Global Log Level= 0
CheckData=True
Encroach Param= -1, 0, 0, 0
BEGIN DESCRIPTION:
Multiple Run
END DESCRIPTION:

--- HUDSON CREEK TRIBUTARY 4 1.f01 (steady flow) ---

Flow Title=Multiple
Number of Profiles=7
Profile Names=10-year,25-year,50-year,1pct_min,100-year,1pct_plu,500-year
River Rch & RM= HUDSON CREEK TRI,Reach-1,2016
     333     434     514     447     604     817     836
Boundary for River Rch & Prof#=HUDSON CREEK TRI,Reach-1,1
Up Type=0
Dn Type=3
Dn Slope=0.005
Boundary for River Rch & Prof#=HUDSON CREEK TRI,Reach-1,2
Up Type=0
Dn Type=3
Dn Slope=0.005
Boundary for River Rch & Prof#=HUDSON CREEK TRI,Reach-1,3
Up Type=0
Dn Type=3
Dn Slope=0.005
Boundary for River Rch & Prof#=HUDSON CREEK TRI,Reach-1,4
Up Type=0
Dn Type=3
Dn Slope=0.005
Boundary for River Rch & Prof#=HUDSON CREEK TRI,Reach-1,5
Up Type=0
Dn Type=3
Dn Slope=0.005
Boundary for River Rch & Prof#=HUDSON CREEK TRI,Reach-1,6
Up Type=0
Dn Type=3
Dn Slope=0.005
Boundary for River Rch & Prof#=HUDSON CREEK TRI,Reach-1,7
Up Type=0
Dn Type=3
Dn Slope=0.005

--- HUDSON CREEK TRIBUTARY 4 1.g01 (geometry) ---

Geom Title=Existing Conditions
Program Version=4.10

River Reach=HUDSON CREEK TRI,Reach-1
Reach XY= 30
      3565842.11     10231821.64      3565871.83     10231782.35
      3565919.16      10231650.2      3565891.38     10231515.13
      3565802.84     10231431.11      3565784.78     10231396.38
      3565768.36     10231219.16       3565788.5     10231055.27
       3565787.8     10230994.16      3565743.36     10230946.24
       3565675.3     10230887.21      3565633.63     10230778.88
      3565621.83     10230706.66      3565557.94     10230687.21
      3565534.33     10230671.24       3565538.5     10230561.52
       3565563.5      10230526.8       3565601.4     10230404.32
       3565600.9     10230373.05      3565636.82     10230295.91
       3565656.9     10230225.16      3565711.25     10230168.38
      3565734.88     10230153.17      3565769.33     10230157.59
      3565791.94     10230200.07      3565813.88     10230210.76
      3565831.27     10230206.79      3565852.71     10230190.15
      3565864.35     10230178.19      3565867.48     10230162.02

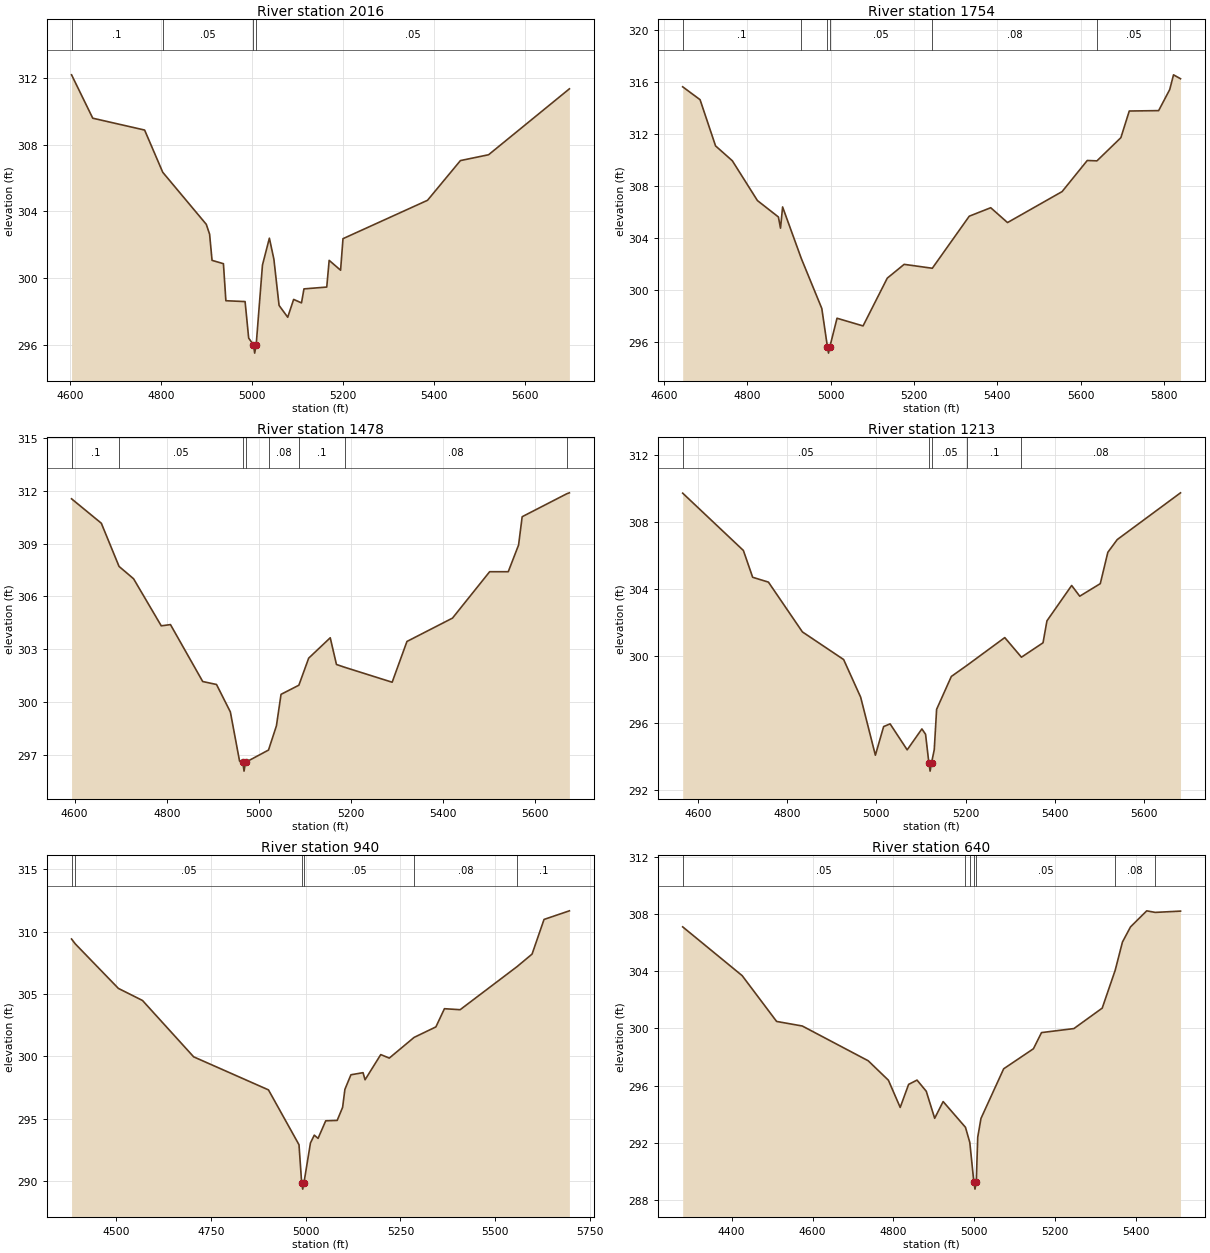
Type RM Length L Ch R = 1 ,2016    ,262,262,262
BEGIN DESCRIPTION:
HUDSON CREEK TRIB 4 1 38.0
END DESCRIPTION:
XS GIS Cut Line= 4
      3566267.04     10231717.78      3566006.61     10231788.97
      3565650.71     10231657.02      3565220.16     10231768.13
#Sta/Elev= 30
  4602.7  312.19  4649.3  309.59  4763.3  308.88  4803.1  306.35  4898.8  303.23
  4906.1  302.64  4911.5  301.07  4936.5  300.87  4941.9  298.65  4984.1   298.6
    4992  296.41  5002.5  296.01  5005.2  295.51  5008.5  296.01  5022.3  300.79
  5037.5   302.4  5047.4  301.14  5058.8  298.37  5077.8  297.66  5090.8  298.73
  5108.1  298.52  5113.5  299.36  5163.6  299.47  5168.9  301.07    5194  300.48
  5199.3  302.37  5385.1  304.67  5457.4  307.05  5519.3   307.4  5696.9  311.35
#Mann= 4 ,-1 , 0
  4602.7      .1       0  4803.1     .05       0  5002.5     .04       0
  5008.5     .05       0
Bank Sta=5002.5,5008.5
XS Rating Curve= 0 ,0
Exp/Cntr=0.3,0.1

Type RM Length L Ch R = 1 ,1754    ,276,276,276
BEGIN DESCRIPTION:
Mapping XS 9c778345
END DESCRIPTION:
XS GIS Cut Line= 4
      3566230.56     10231462.58        3565708.      10231516.4
      3565518.76     10231571.95        3565050.     10231514.66
#Sta/Elev= 30
  4644.7  315.62  4686.4  314.63  4723.6  311.08  4763.8  309.94  4824.1  306.88
  4874.4  305.62  4879.5  304.76  4884.5  306.39  4929.4  302.43  4978.6  298.59
    4992  295.66  4994.7  295.16    4998  295.66  5015.1  297.84  5077.6  297.25
  5135.7  300.92  5176.2  301.98  5243.8  301.68  5332.5  305.68    5384  306.33
  5424.3  305.19  5555.3  307.57  5615.7  309.96  5638.9  309.93  5696.3  311.71
  5716.5  313.76    5787  313.79  5813.6  315.41  5822.7  316.54  5839.5  316.24
#Mann= 7 ,-1 , 0
  4644.7      .1       0  4929.4     .05       0    4992     .04       0
    4998     .05       0  5243.8     .08       0  5638.9     .05       0
  5813.6     .08       0
Bank Sta=4992,4998
XS Rating Curve= 0 ,0
Exp/Cntr=0.3,0.1

Type RM Length L Ch R = 1 ,1478    ,265,265,265
BEGIN DESCRIPTION:
Mapping XS 6661310d
END DESCRIPTION:
XS GIS Cut Line= 3
      3566176.75     10231257.72      3565643.76     10231262.92
      3565100.37     10231330.63
#Sta/Elev= 30
  4593.4  311.56    4658  310.17  4696.5  307.71    4728  307.01  4788.1  304.33
  4808.1   304.4  4878.1  301.16  4908.1  300.99  4938.1  299.43  4958.1  296.63
  4965.1  296.56  4967.8  296.06  4971.1  296.56  5020.9  297.26  5038.1  298.64
  5048.1  300.43  5086.8  300.95  5108.1  302.49  5154.9  303.65  5168.4  302.13
  5186.3  301.97  5289.3  301.12  5321.4  303.44  5420.3  304.77  5500.9  307.41
  5541.3  307.41  5563.7  308.93  5571.5  310.54  5668.6  311.85    5674   311.9
#Mann= 8 ,-1 , 0
  4593.4      .1       0  4696.5     .05       0  4965.1     .04       0
  4971.1     .05       0  5020.9     .08       0  5086.8      .1       0
  5186.3     .08       0  5668.6      .1       0
Bank Sta=4965.1,4971.1
XS Rating Curve= 0 ,0
Exp/Cntr=0.3,0.1

Type RM Length L Ch R = 1 ,1213    ,273,273,273
BEGIN DESCRIPTION:
Mapping XS 61c339a5
END DESCRIPTION:
XS GIS Cut Line= 4
      3566161.16     10231111.91      3565945.84     10230950.42
      3565530.91     10231075.42      3565136.97     10231202.11
#Sta/Elev= 30
  4565.8  309.73  4701.9  306.31  4722.7  304.71  4758.1  304.42  4834.2  301.45
  4926.7   299.8  4964.9  297.55  4997.9  294.09  5016.4   295.8  5030.9  295.96
  5069.2  294.41  5102.2  295.66  5110.4  295.34  5117.8  293.64  5120.6  293.14
  5123.8  293.64  5129.9  294.42  5135.2  296.83  5168.2  298.79  5203.7  299.46
    5288  301.11  5325.4  299.94  5373.8   300.8  5382.6  302.11    5438  304.22
  5456.1  303.58  5502.2  304.33  5519.1   306.2  5540.2  306.96  5682.1  309.75
#Mann= 5 ,-1 , 0
  4565.8     .05       0  5117.8     .04       0  5123.8     .05       0
  5203.7      .1       0  5325.4     .08       0
Bank Sta=5117.8,5123.8
XS Rating Curve= 0 ,0
Exp/Cntr=0.3,0.1

Type RM Length L Ch R = 1 ,940     ,300,300,300
BEGIN DESCRIPTION:
Mapping XS 7a2158bf
END DESCRIPTION:
XS GIS Cut Line= 4
      3566150.71     10231077.16      3565834.73     10230806.33
      3565537.86     10230769.87      3564968.42     10230953.89
#Sta/Elev= 30
  4382.3   309.4  4392.1  309.01  4505.8  305.44  4569.5  304.47  4704.5  299.95
  4901.9   297.3  4982.5   292.9  4989.5  289.84  4992.3  289.34  4995.5  289.84
  5012.7  293.04  5022.8  293.67  5032.8  293.41    5053  294.82  5083.2  294.85
  5097.6   295.9  5103.6  297.34  5119.5  298.51  5151.5  298.68  5156.8  298.11
  5198.2  300.13  5220.8  299.85  5286.3  301.51  5343.7  302.35  5366.3  303.81
  5407.7  303.73  5558.1  307.19  5597.5  308.19  5629.1  310.97    5696  311.66
#Mann= 6 ,-1 , 0
  4382.3     .08       0  4392.1     .05       0  4989.5     .04       0
  4995.5     .05       0  5286.3     .08       0  5558.1      .1       0
Bank Sta=4989.5,4995.5
XS Rating Curve= 0 ,0
Exp/Cntr=0.3,0.1

Type RM Length L Ch R = 1 ,640     ,118,118,118
BEGIN DESCRIPTION:
Mapping XS e795c9a2
END DESCRIPTION:
XS GIS Cut Line= 4
      3566095.14     10231016.38      3565772.23     10230717.79
      3565473.62     10230490.35      3565058.64      10230497.3
#Sta/Elev= 30
  4279.1  307.09  4426.1  303.68  4511.2  300.48  4574.7  300.16  4737.6  297.73
  4787.5  296.37  4816.6  294.47  4837.4  296.08  4858.2  296.38    4881   295.6
  4901.8  293.71  4922.7  294.88  4977.9  293.08  4988.6  292.02  4998.6  289.26
  5001.4  288.76  5004.6  289.26  5008.2  292.39  5016.2   293.7  5072.3  297.17
  5145.8  298.57  5165.8   299.7  5245.8  299.98  5315.8  301.41  5347.9  304.06
  5365.8  306.03  5385.8  307.09  5425.8  308.21  5446.7   308.1  5509.3  308.19
#Mann= 7 ,-1 , 0
  4279.1     .05       0  4977.9     .08       0  4988.6     .05       0
  4998.6     .04       0  5004.6     .05       0  5347.9     .08       0
  5446.7     .15       0
Bank Sta=4998.6,5004.6
XS Rating Curve= 0 ,0
Exp/Cntr=0.3,0.1

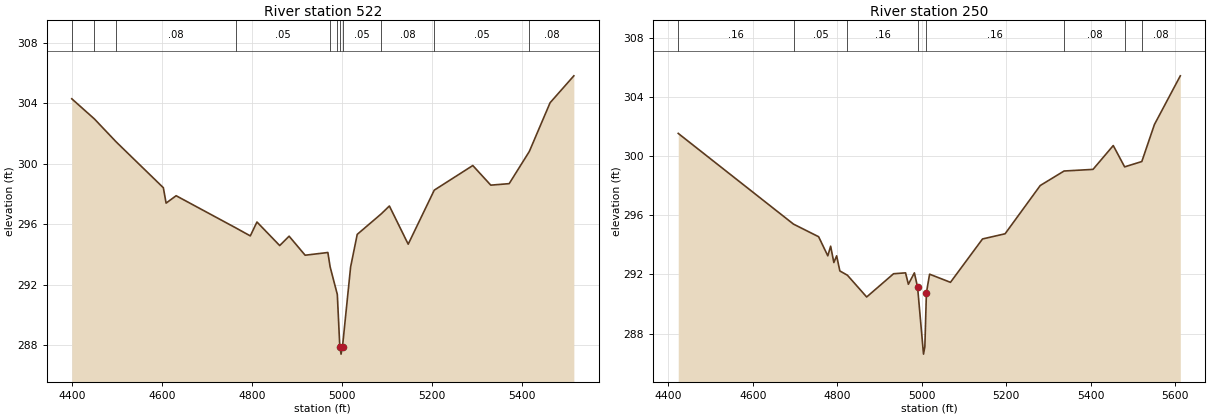
Type RM Length L Ch R = 1 ,522     ,272,272,272
BEGIN DESCRIPTION:
Mapping XS 9f4b3651
END DESCRIPTION:
XS GIS Cut Line= 3
      3566081.25     10230785.48      3565365.98     10230278.55
      3565129.87     10230311.54
#Sta/Elev= 30
  4399.7   304.3  4449.8  302.97  4498.5  301.44  4603.1  298.41  4609.2  297.39
  4631.5  297.88    4764  295.75  4796.2  295.22    4811  296.14  4861.5  294.58
  4882.4   295.2    4918  293.94  4968.5  294.12  4973.5  293.17  4989.5  291.34
    4995  287.89  4997.8  287.39    5001  287.89    5019  293.16  5033.7  295.32
  5087.1  296.68  5105.1   297.2  5146.9  294.67  5204.8  298.25  5290.4  299.88
  5330.3  298.58  5371.2  298.68  5415.9  300.81  5462.1  304.04  5514.8  305.82
#Mann= 11 ,-1 , 0
  4399.7     .08       0  4449.8     .05       0  4498.5     .08       0
    4764     .05       0  4973.5     .08       0  4989.5     .05       0
    4995     .04       0    5001     .05       0  5087.1     .08       0
  5204.8     .05       0  5415.9     .08       0
Bank Sta=4995,5001
XS Rating Curve= 0 ,0
Exp/Cntr=0.3,0.1

Type RM Length L Ch R = 1 ,250     ,0,0,0
BEGIN DESCRIPTION:
HUDSON CREEK TRIBUTARY 4 1 1.0
END DESCRIPTION:
XS GIS Cut Line= 3
      3566119.49     10230573.72      3565588.21      10230103.2
      3565145.39     10230284.83
#Sta/Elev= 30
  4423.4  301.53  4696.3   295.4  4755.7  294.55  4777.4  293.26  4784.1  293.91
  4791.7  292.81  4798.3  293.26  4805.9  292.24  4823.8  291.95  4869.4  290.48
    4933  292.05  4961.4  292.11  4968.1  291.34  4982.3  292.11  4989.9  291.14
  5003.9  286.62  5007.1  287.12  5010.8  290.77  5018.3  292.02  5067.7  291.47
  5143.6   294.4    5197  294.75  5280.2  298.01  5336.6  298.99  5405.1   299.1
    5453  300.71  5479.9  299.27  5520.6  299.63  5550.4  302.13  5611.7  305.42
#Mann= 8 ,-1 , 0
  4423.4     .16       0  4696.3     .05       0  4823.8     .16       0
  4989.9     .07       0  5010.8     .16       0  5336.6     .08       0
  5479.9     .05       0  5520.6     .08       0
Bank Sta=4989.9,5010.8
XS Rating Curve= 0 ,0
Exp/Cntr=0.3,0.1

Chan Stop Cuts=-1
Use User Specified Reach Order=0
Composite Channel Slope=5