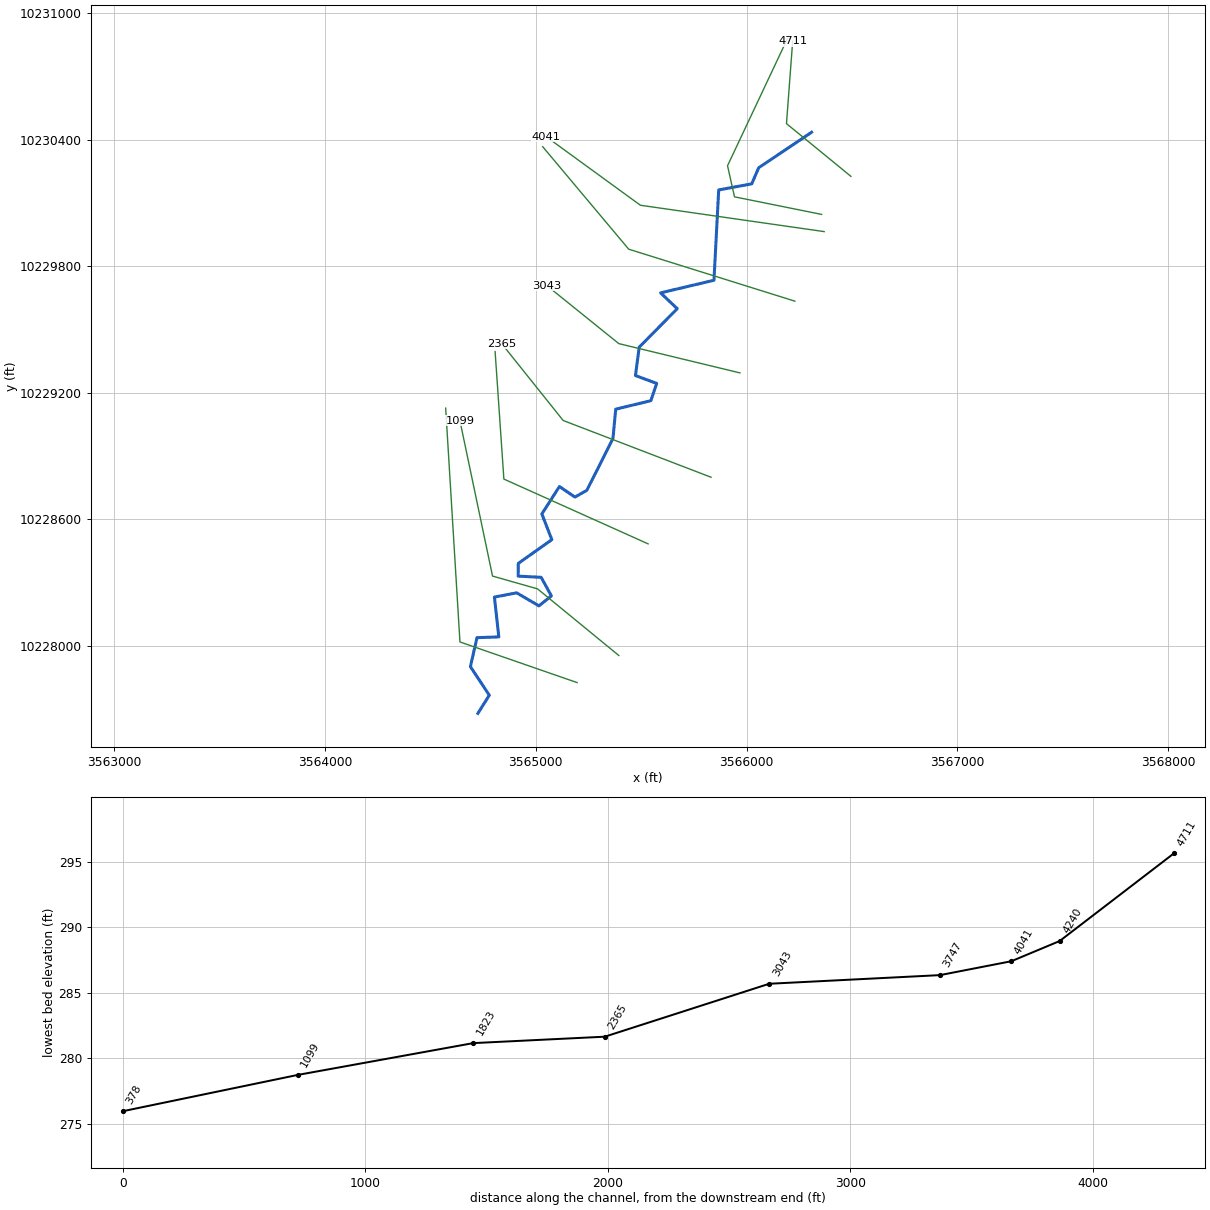
--- HUDSON CREEK TRIBUTARY 4.prj (project) ---

Proj Title=HUDSON CREEK TRIBUTARY 4 Base Level Engineering
Current Plan=p01
Default Exp/Contr=0.3,0.1
English Units
Geom File=g01
Flow File=f01
Plan File=p01
Y Axis Title=Elevation
X Axis Title(PF)=Main Channel Distance
X Axis Title(XS)=Station
BEGIN DESCRIPTION:
HUDSON CREEK TRIBUTARY 4
END DESCRIPTION:
DSS Export Rating Curves= 0
DSS Export Rating Curve Sorted= 0
DSS Export Volume Flow Curves= 0
DXF OffsetX= 0
DXF OffsetY= 0
DXF ScaleX= 1
DXF ScaleY= 10

--- HUDSON CREEK TRIBUTARY 4.p01 (plan) ---

Plan Title=Multiple Run
Short Identifier=Multiple
Geom File=g01
Flow File=f01
Subcritical Flow
K Sum by GR= 0
Std Step Tol= 0.01
Critical Tol= 0.01
Num of Std Step Trials= 20
Max Error Tol= 0.3
Flow Tol Ratio= 0.001
Split Flow NTrial= 30
Split Flow Tol= 0.02
Split Flow Ratio= 0.02
Log Output Level= 0
Friction Slope Method= 1
Unsteady Friction Slope Method= 2
Unsteady Bridges Friction Slope Method= 1
Parabolic Critical Depth
Global Vel Dist=  1 , 1 , 1
Global Log Level= 0
CheckData=True
Encroach Param= -1, 0, 0, 0
BEGIN DESCRIPTION:
Multiple Run
END DESCRIPTION:

--- HUDSON CREEK TRIBUTARY 4.f01 (steady flow) ---

Flow Title=Multiple
Number of Profiles=7
Profile Names=10-year,25-year,50-year,1pct_min,100-year,1pct_plu,500-year
River Rch & RM= HUDSON CREEK TRI,Reach-1,4711
      95     113     126     104     141     190     174
River Rch & RM= HUDSON CREEK TRI,Reach-1,4041
     455     606     726     639     865    1169    1227
Boundary for River Rch & Prof#=HUDSON CREEK TRI,Reach-1,1
Up Type=0
Dn Type=3
Dn Slope=0.005
Boundary for River Rch & Prof#=HUDSON CREEK TRI,Reach-1,2
Up Type=0
Dn Type=3
Dn Slope=0.005
Boundary for River Rch & Prof#=HUDSON CREEK TRI,Reach-1,3
Up Type=0
Dn Type=3
Dn Slope=0.005
Boundary for River Rch & Prof#=HUDSON CREEK TRI,Reach-1,4
Up Type=0
Dn Type=3
Dn Slope=0.005
Boundary for River Rch & Prof#=HUDSON CREEK TRI,Reach-1,5
Up Type=0
Dn Type=3
Dn Slope=0.005
Boundary for River Rch & Prof#=HUDSON CREEK TRI,Reach-1,6
Up Type=0
Dn Type=3
Dn Slope=0.005
Boundary for River Rch & Prof#=HUDSON CREEK TRI,Reach-1,7
Up Type=0
Dn Type=3
Dn Slope=0.005

--- HUDSON CREEK TRIBUTARY 4.g01 (geometry) ---

Geom Title=Existing Conditions
Program Version=4.10

River Reach=HUDSON CREEK TRI,Reach-1
Reach XY= 30
      3566307.96     10230435.53      3566057.09     10230267.13
      3566024.11     10230190.74      3565867.48     10230162.02
      3565844.96     10229733.52      3565591.87     10229673.76
       3565670.9     10229598.72       3565490.4     10229416.09
      3565472.64     10229281.59      3565573.22     10229244.37
      3565545.59     10229162.58      3565378.99     10229121.91
      3565365.89      10228982.6      3565241.97     10228737.21
      3565185.72     10228705.27      3565112.11     10228755.27
      3565028.77     10228625.41        3565076.     10228503.18
      3564916.97     10228390.68      3564916.27     10228330.27
       3565025.3     10228324.71      3565073.91     10228236.52
      3565014.88      10228189.3      3564909.33      10228251.1
      3564803.77     10228230.96      3564824.61     10228042.07
      3564721.13      10228038.6      3564689.88      10227901.1
      3564779.47     10227765.68      3564725.41     10227679.42

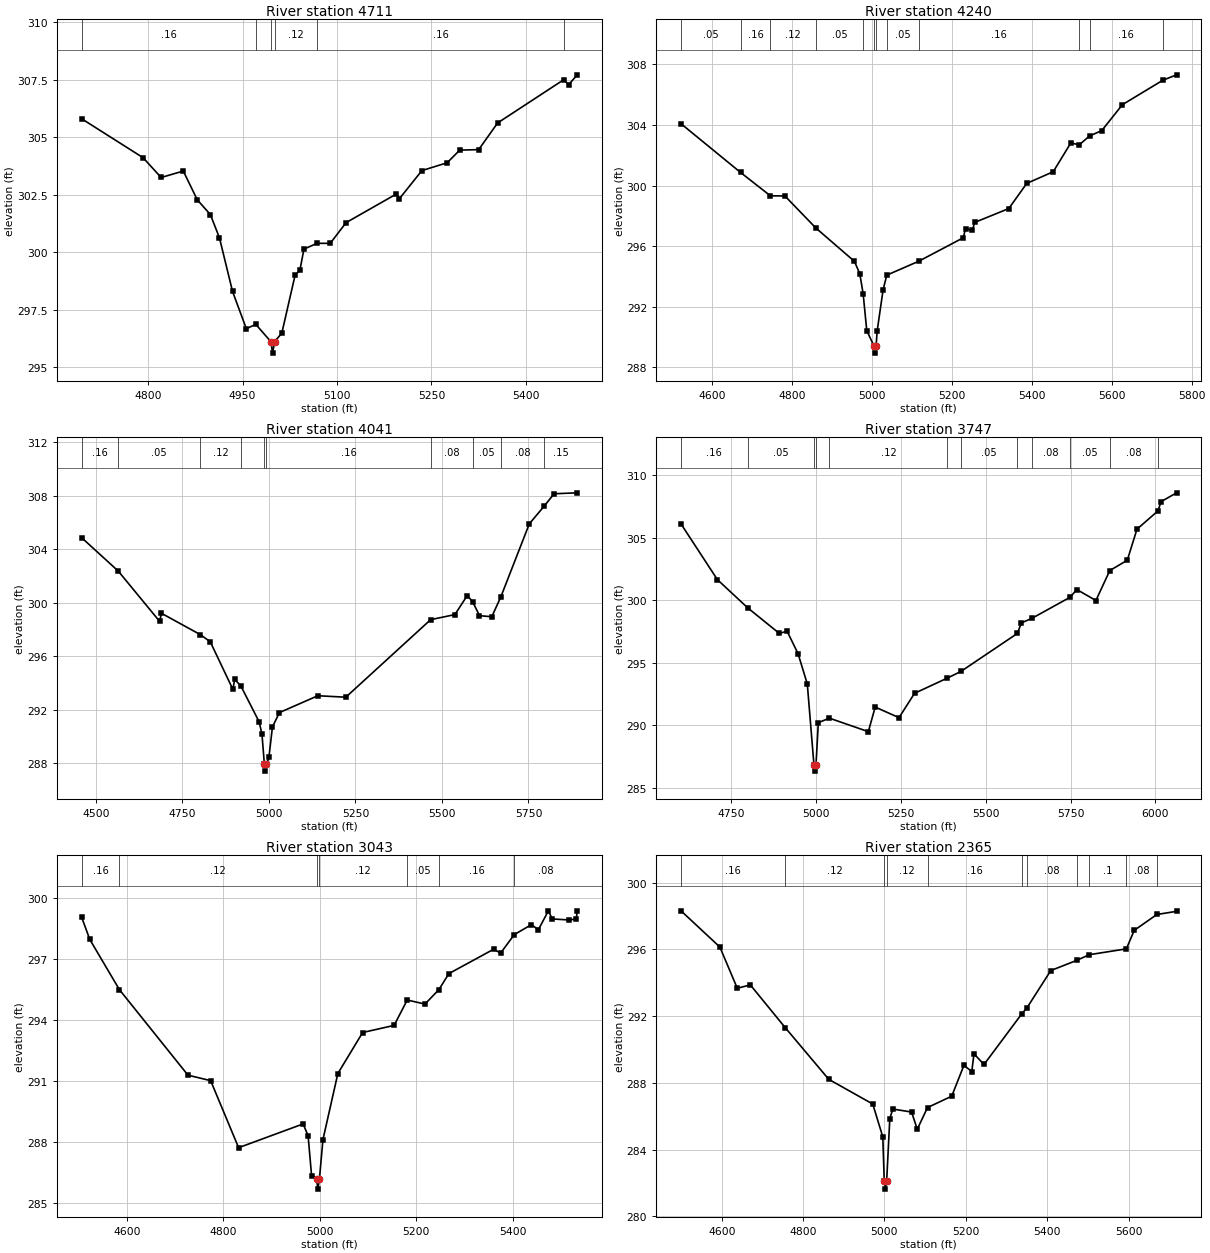
Type RM Length L Ch R = 1 ,4711    ,471,471,471
BEGIN DESCRIPTION:
HUDSON CREEK 38.
END DESCRIPTION:
XS GIS Cut Line= 3
      3566494.46     10230226.47       3566188.9     10230476.47
      3566218.33     10230867.76
#Sta/Elev= 30
  4694.5   305.8    4792  304.11  4820.7  303.25  4855.9  303.53  4878.1  302.28
  4898.9  301.64  4913.3  300.63  4934.1   298.3    4956  296.68    4971  296.87
    4995  296.12  4997.7  295.62    5001  296.12  5012.4  296.49  5033.5  299.01
  5041.1  299.22  5047.5  300.14  5068.4  300.39  5089.3  300.39  5114.5  301.29
  5194.2  302.53  5199.2  302.33  5234.9  303.55    5275  303.89  5295.1  304.44
  5325.1  304.46  5355.2  305.62  5460.3   307.5  5467.9  307.28  5481.7  307.71
#Mann= 6 ,-1 , 0
  4694.5     .16       0    4971     .12       0    4995     .07       0
    5001     .12       0  5068.4     .16       0  5460.3     .05       0
Bank Sta=4995,5001
XS Rating Curve= 0 ,0
Exp/Cntr=0.3,0.1

Type RM Length L Ch R = 1 ,4240    ,199,199,199
BEGIN DESCRIPTION:
Mapping XS 001b8c9c
END DESCRIPTION:
XS GIS Cut Line= 4
      3566355.57     10230045.91      3565942.37     10230129.24
      3565909.39     10230276.81       3566194.1     10230880.96
#Sta/Elev= 30
  4521.7  304.08  4670.9  300.86  4745.4  299.32  4781.8  299.31    4859   297.2
  4955.9  294.99  4969.3  294.17  4977.7  292.84  4986.7  290.42  5004.2  289.43
  5006.9  288.93  5010.2  289.43  5012.7  290.39  5027.6  293.11  5036.8  294.08
  5116.9     295  5228.4  296.55  5233.9  297.16  5251.1  297.04  5256.7  297.56
  5342.3  298.48  5387.2  300.14  5453.5  300.91  5497.7  302.82  5518.3  302.68
  5544.3  303.27  5575.1  303.63  5626.7  305.34  5727.7  306.95  5762.3  307.31
#Mann= 12 ,-1 , 0
  4521.7     .05       0  4670.9     .16       0  4745.4     .12       0
    4859     .05       0  4977.7     .16       0  5004.2     .07       0
  5010.2     .16       0  5036.8     .05       0  5116.9     .16       0
  5518.3     .05       0  5544.3     .16       0  5727.7     .05       0
Bank Sta=5004.2,5010.2
XS Rating Curve= 0 ,0
Exp/Cntr=0.3,0.1

Type RM Length L Ch R = 1 ,4041    ,294,294,294
BEGIN DESCRIPTION:
Mapping XS bcfbd126
END DESCRIPTION:
XS GIS Cut Line= 3
      3566367.72     10229964.31      3565496.19     10230089.31
      3565050.04     10230413.94
#Sta/Elev= 30
  4458.8  304.85  4564.3  302.36  4684.1  298.59  4689.1   299.2  4801.1  297.61
  4830.3  297.07  4895.8   293.5  4900.9  294.26    4919  293.75  4971.4  291.09
  4979.7  290.18  4986.8  287.89  4989.5  287.39  4992.8  287.89  4999.9  288.43
    5010  290.69  5030.2  291.77  5141.3  293.03  5222.1  292.92  5467.2  298.72
  5537.3   299.1  5572.9  300.52  5588.4  300.08  5608.4  299.02    5644  298.94
  5670.5  300.45  5752.4  305.89  5796.2  307.24    5824  308.14    5891  308.21
#Mann= 10 ,-1 , 0
  4458.8     .16       0  4564.3     .05       0  4801.1     .12       0
    4919     .16       0  4986.8     .07       0  4992.8     .16       0
  5467.2     .08       0  5588.4     .05       0  5670.5     .08       0
  5796.2     .15       0
Bank Sta=4986.8,4992.8
XS Rating Curve= 0 ,0
Exp/Cntr=0.3,0.1

Type RM Length L Ch R = 1 ,3747    ,704,704,704
BEGIN DESCRIPTION:
Mapping XS 1a861323
END DESCRIPTION:
XS GIS Cut Line= 3
       3566228.8     10229634.46      3565440.64     10229880.98
      3565032.81      10230366.9
#Sta/Elev= 30
  4602.2  306.12  4709.4  301.66  4798.4  299.41  4892.1  297.35  4914.6  297.54
  4947.1  295.73  4974.3  293.31  4993.9  286.83  4996.6  286.33  4999.9  286.83
  5006.8  290.21  5039.4  290.57  5154.1  289.49  5174.4  291.46  5244.5  290.61
  5290.3  292.56    5387  293.78  5426.9  294.31  5593.6  297.36  5604.9   298.2
  5635.4  298.55  5748.6  300.25  5768.3  300.87  5824.7  299.99  5865.6  302.39
  5917.1  303.21  5945.7   305.7  6007.9  307.17  6016.4   307.9  6062.4  308.61
#Mann= 12 ,-1 , 0
  4602.2     .16       0  4798.4     .05       0  4993.9     .04       0
  4999.9     .05       0  5039.4     .12       0    5387     .16       0
  5426.9     .05       0  5593.6     .16       0  5635.4     .08       0
  5748.6     .05       0  5865.6     .08       0  6007.9     .15       0
Bank Sta=4993.9,4999.9
XS Rating Curve= 0 ,0
Exp/Cntr=0.3,0.1

Type RM Length L Ch R = 1 ,3043    ,678,678,678
BEGIN DESCRIPTION:
Mapping XS dcf16133
END DESCRIPTION:
XS GIS Cut Line= 3
      3565968.44     10229294.17      3565393.76     10229433.06
      3565053.95       10229707.
#Sta/Elev= 30
  4506.6  299.05  4523.4  297.96  4584.8  295.49    4727  291.28    4774  291.01
    4832  287.71  4965.8  288.88  4976.1   288.3  4983.3  286.34  4993.6  286.17
  4996.4  285.67  4999.6  286.17  5006.9  288.11  5037.8  291.36  5089.2  293.38
  5154.5  293.73  5181.7  294.98  5218.5  294.78  5247.3  295.49  5268.1  296.28
  5360.9  297.48  5375.3  297.29  5403.7   298.2  5439.2  298.69  5453.6  298.44
  5474.4  299.37  5482.4  298.97  5517.6  298.92    5532  298.97  5534.3  299.34
#Mann= 7 ,-1 , 0
  4506.6     .16       0  4584.8     .12       0  4993.6     .07       0
  4999.6     .12       0  5181.7     .05       0  5247.3     .16       0
  5403.7     .08       0
Bank Sta=4993.6,4999.6
XS Rating Curve= 0 ,0
Exp/Cntr=0.3,0.1

Type RM Length L Ch R = 1 ,2365    ,542,542,542
BEGIN DESCRIPTION:
Mapping XS c7fd01cc
END DESCRIPTION:
XS GIS Cut Line= 3
      3565831.22      10228799.4      3565129.87     10229068.48
       3564838.2     10229433.07
#Sta/Elev= 30
    4500  298.31  4595.5  296.14  4638.3  293.67  4670.4  293.87  4756.1  291.31
  4863.2  288.21  4971.3  286.73    4996  284.76  4999.5  282.13  5002.2  281.63
  5005.5  282.13  5013.2  285.86  5020.6  286.43  5066.7  286.25  5080.7  285.22
  5105.9  286.52  5165.4   287.2  5195.4  289.05  5214.7  288.68  5220.1  289.74
  5244.8   289.1  5337.1  292.12  5350.7  292.51  5408.9  294.73  5472.6  295.34
  5503.4  295.68  5594.6  296.03    5614  297.14  5669.6  298.09  5718.1  298.28
#Mann= 11 ,-1 , 0
    4500     .16       0  4756.1     .12       0  4999.5     .07       0
  5005.5     .12       0  5105.9     .16       0  5337.1     .05       0
  5350.7     .08       0  5472.6     .05       0  5503.4      .1       0
  5594.6     .08       0  5669.6      .1       0
Bank Sta=4999.5,5005.5
XS Rating Curve= 0 ,0
Exp/Cntr=0.3,0.1

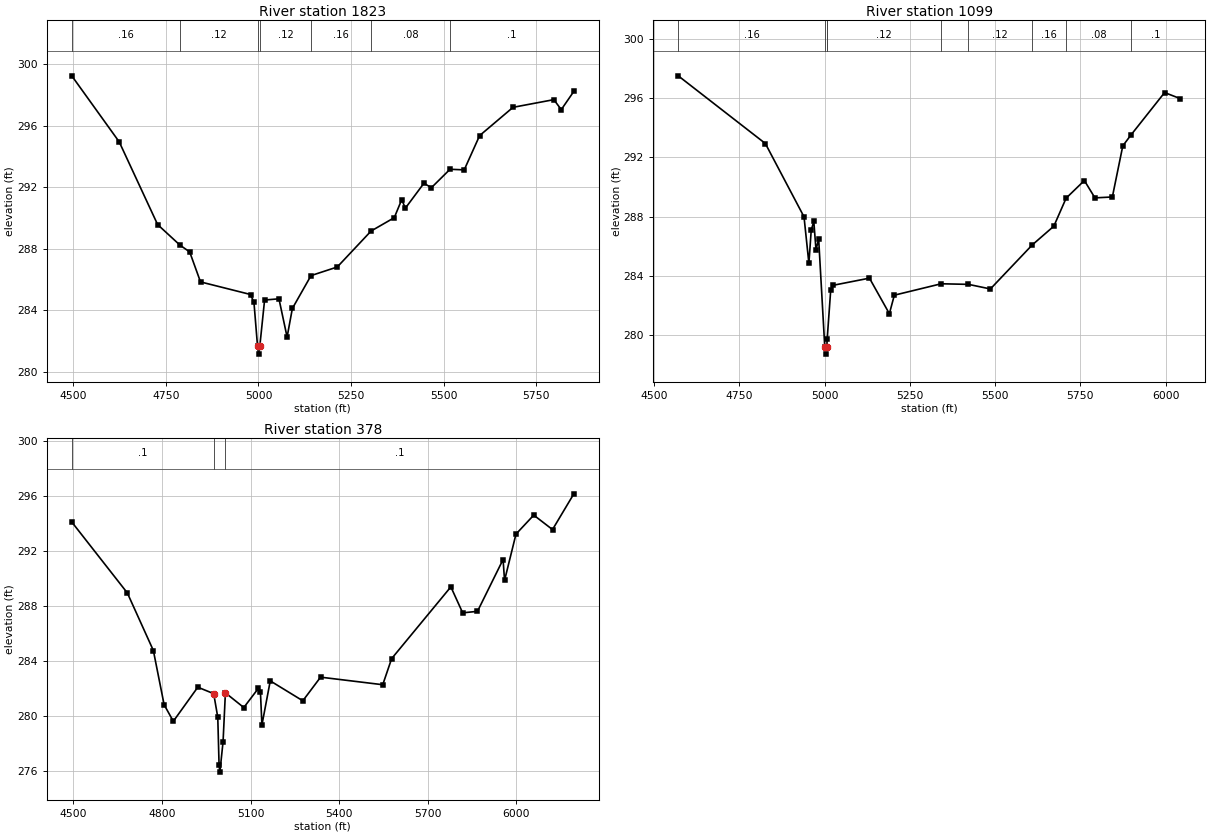
Type RM Length L Ch R = 1 ,1823    ,724,724,724
BEGIN DESCRIPTION:
Mapping XS a10e1965
END DESCRIPTION:
XS GIS Cut Line= 3
      3565532.61     10228483.43      3564848.62      10228790.7
      3564807.03     10229395.54
#Sta/Elev= 30
  4495.8  299.25    4624  294.95  4727.7  289.57  4787.7  288.24  4814.3  287.79
  4843.5  285.84  4978.7  285.02  4987.9   284.5  4997.6  281.64  5000.4  281.14
  5003.6  281.64  5016.6  284.66  5055.4  284.74  5077.4  282.25  5091.6  284.11
    5142  286.25  5212.9  286.81  5304.2  289.15  5366.9  290.02  5386.9  291.19
  5396.9  290.64    5447  292.26  5467.1  291.97  5517.5  293.17  5555.8  293.13
  5597.4  295.36  5687.6   297.2  5797.9   297.7  5817.9  297.05  5851.9  298.24
#Mann= 7 ,-1 , 0
  4495.8     .16       0  4787.7     .12       0  4997.6     .07       0
  5003.6     .12       0    5142     .16       0  5304.2     .08       0
  5517.5      .1       0
Bank Sta=4997.6,5003.6
XS Rating Curve= 0 ,0
Exp/Cntr=0.3,0.1

Type RM Length L Ch R = 1 ,1099    ,721,721,721
BEGIN DESCRIPTION:
Mapping XS 72851e7c
END DESCRIPTION:
XS GIS Cut Line= 4
      3565393.74     10227953.91      3565008.34     10228269.87
       3564794.8     10228330.63      3564640.29     10229066.72
#Sta/Elev= 30
  4570.7   297.5  4826.2  292.93  4939.6  287.98  4953.9  284.84  4960.7  287.07
  4968.3  287.67  4974.7  285.76  4982.6  286.47  5000.4  279.21  5003.2  278.71
  5006.4  279.21  5007.5  279.72  5017.8  283.01  5025.4  283.36  5131.5  283.84
  5189.9  281.44  5204.5  282.69  5341.9  283.46  5421.9  283.42  5486.2  283.11
  5608.8  286.08  5672.3  287.35  5708.3  289.24  5761.8  290.43  5792.8  289.26
  5843.9  289.32  5874.5  292.77  5897.6  293.48  5997.1  296.37  6043.2  295.96
#Mann= 9 ,-1 , 0
  4570.7     .16       0  5000.4     .07       0  5006.4     .16       0
  5007.5     .12       0  5341.9     .16       0  5421.9     .12       0
  5608.8     .16       0  5708.3     .08       0  5897.6      .1       0
Bank Sta=5000.4,5006.4
XS Rating Curve= 0 ,0
Exp/Cntr=0.3,0.1

Type RM Length L Ch R = 1 ,378     ,0,0,0
BEGIN DESCRIPTION:
SEWER CREEK 1.7
END DESCRIPTION:
XS GIS Cut Line= 3
      3565195.87     10227825.42      3564640.29     10228018.13
       3564572.6     10229127.11
#Sta/Elev= 30
    4495  294.14    4683  288.98  4771.1  284.79  4807.6  280.84  4838.7  279.64
  4921.5  282.12  4975.3  281.65  4989.1  279.93  4993.5  276.44  4996.2  275.94
    5007  278.15  5014.9  281.71  5077.2  280.64  5126.6  282.04  5133.5  281.75
  5138.5  279.37  5166.7  282.58  5276.9  281.13    5337  282.85  5547.4   282.3
  5577.5   284.2  5777.9  289.42  5817.9  287.53    5868  287.64  5954.6  291.41
  5959.6  289.89  5998.3  293.26  6058.4  294.64  6121.9  293.59  6194.1  296.19
#Mann= 3 , 0 , 0
    4495      .1       0  4975.3     .05       0  5014.9      .1       0
Bank Sta=4975.3,5014.9
XS Rating Curve= 0 ,0
Exp/Cntr=0.3,0.1

Chan Stop Cuts=-1
Use User Specified Reach Order=0
Composite Channel Slope=5