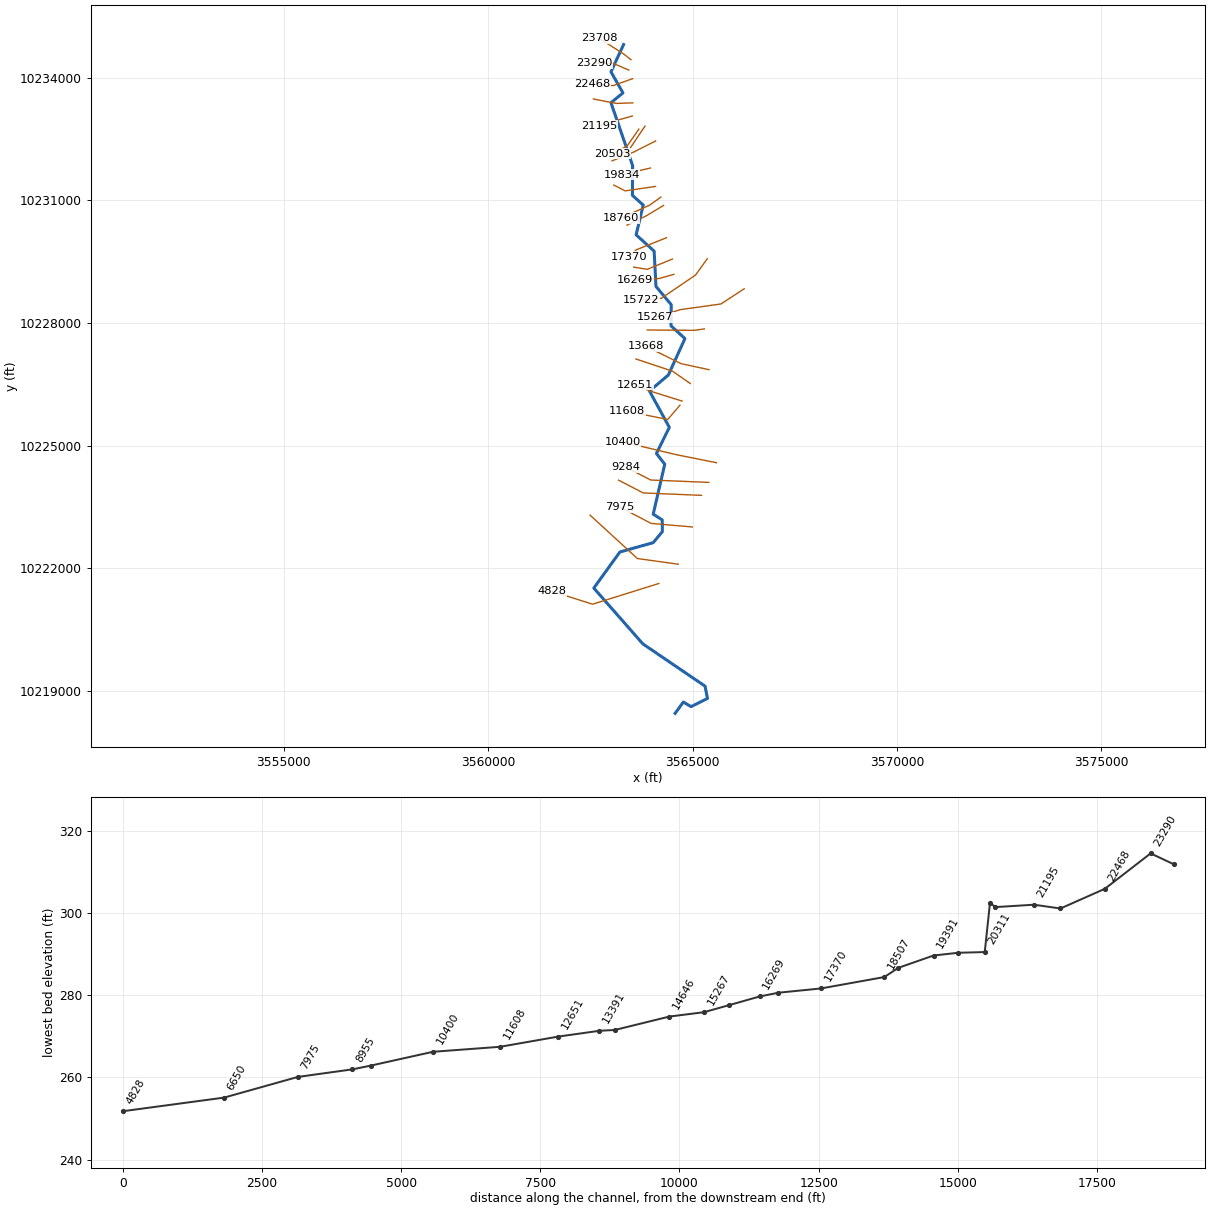
--- HUDSON CREEK.prj (project) ---

Proj Title=HUDSON CREEK Base Level Engineering
Current Plan=p01
Default Exp/Contr=0.3,0.1
English Units
Geom File=g01
Flow File=f01
Plan File=p01
Y Axis Title=Elevation
X Axis Title(PF)=Main Channel Distance
X Axis Title(XS)=Station
BEGIN DESCRIPTION:
HUDSON CREEK
END DESCRIPTION:
DSS Export Rating Curves= 0
DSS Export Rating Curve Sorted= 0
DSS Export Volume Flow Curves= 0
DXF OffsetX= 0
DXF OffsetY= 0
DXF ScaleX= 1
DXF ScaleY= 10

--- HUDSON CREEK.p01 (plan) ---

Plan Title=Multiple Run
Short Identifier=Multiple
Geom File=g01
Flow File=f01
Subcritical Flow
K Sum by GR= 0
Std Step Tol= 0.01
Critical Tol= 0.01
Num of Std Step Trials= 20
Max Error Tol= 0.3
Flow Tol Ratio= 0.001
Split Flow NTrial= 30
Split Flow Tol= 0.02
Split Flow Ratio= 0.02
Log Output Level= 0
Friction Slope Method= 1
Unsteady Friction Slope Method= 2
Unsteady Bridges Friction Slope Method= 1
Parabolic Critical Depth
Global Vel Dist=  1 , 1 , 1
Global Log Level= 0
CheckData=True
Encroach Param= -1, 0, 0, 0
BEGIN DESCRIPTION:
Multiple Run
END DESCRIPTION:

--- HUDSON CREEK.f01 (steady flow) ---

Flow Title=Multiple
Number of Profiles=7
Profile Names=10-year,25-year,50-year,1pct_min,100-year,1pct_plu,500-year
River Rch & RM= HUDSON CREEK,Reach-1,23708
     484     644     772     679     918    1241    1300
River Rch & RM= HUDSON CREEK,Reach-1,14646
     821    1121    1367    1220    1650    2231    2410
River Rch & RM= HUDSON CREEK,Reach-1,9284
    1019    1405    1724    1546    2091    2828    3087
Boundary for River Rch & Prof#=HUDSON CREEK,Reach-1,1
Up Type=0
Dn Type=3
Dn Slope=0.005
Boundary for River Rch & Prof#=HUDSON CREEK,Reach-1,2
Up Type=0
Dn Type=3
Dn Slope=0.005
Boundary for River Rch & Prof#=HUDSON CREEK,Reach-1,3
Up Type=0
Dn Type=3
Dn Slope=0.005
Boundary for River Rch & Prof#=HUDSON CREEK,Reach-1,4
Up Type=0
Dn Type=3
Dn Slope=0.005
Boundary for River Rch & Prof#=HUDSON CREEK,Reach-1,5
Up Type=0
Dn Type=3
Dn Slope=0.005
Boundary for River Rch & Prof#=HUDSON CREEK,Reach-1,6
Up Type=0
Dn Type=3
Dn Slope=0.005
Boundary for River Rch & Prof#=HUDSON CREEK,Reach-1,7
Up Type=0
Dn Type=3
Dn Slope=0.005

--- HUDSON CREEK.g01 (geometry) ---

Geom Title=Existing Conditions
Program Version=4.10

River Reach=HUDSON CREEK    ,Reach-1
Reach XY= 30
      3563311.24       10234812.      3563003.03     10234145.75
      3563295.85     10233628.89      3563002.88     10233389.74
      3563531.96     10231854.59      3563527.73     10231124.71
      3563791.62     10230885.13      3563617.92     10230157.98
      3564058.31     10229759.83      3564103.69     10228895.37
      3564476.95     10228449.19      3564470.87      10227932.7
      3564812.13     10227619.53      3564406.51     10226729.38
       3563944.7     10226336.02      3564430.55     10225448.19
      3564114.15     10224808.87      3564318.57     10224547.15
      3564036.15     10223324.84      3564256.83     10223184.22
      3564259.92      10222897.4      3564035.02     10222627.88
      3563220.49      10222398.7      3562582.87      10221516.8
      3563782.11     10220152.12      3565303.72     10219118.11
      3565363.73     10218816.71      3564961.23      10218616.2
      3564773.68     10218728.66      3564572.11     10218451.64

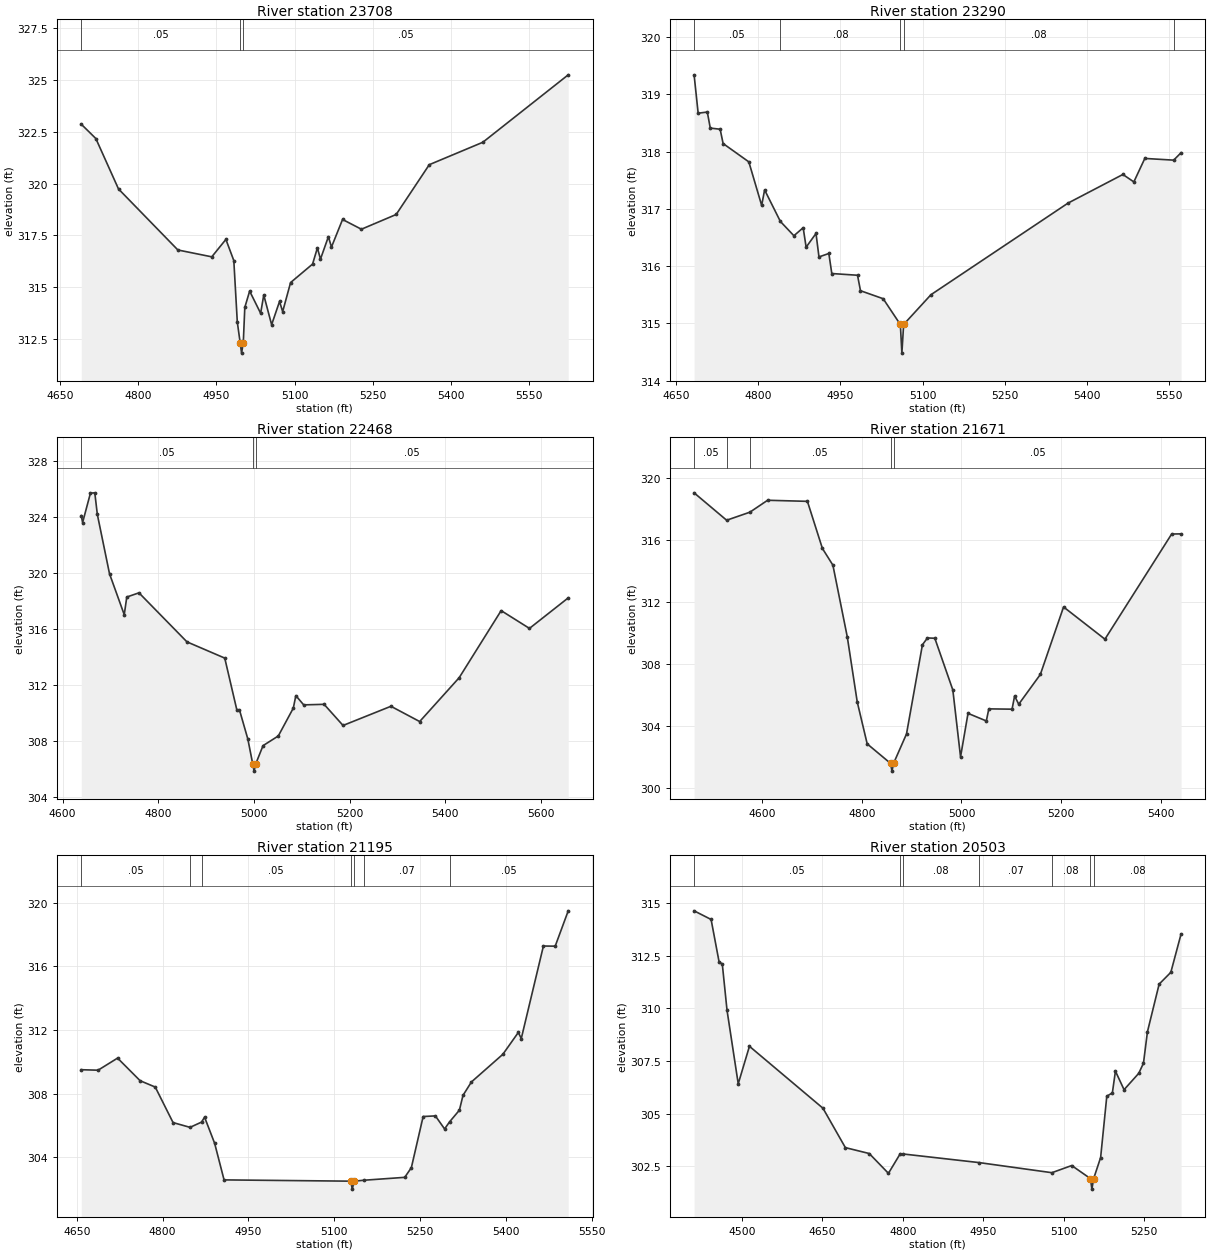
Type RM Length L Ch R = 1 ,23708   ,418,418,418
BEGIN DESCRIPTION:
HUDSON CREEK 38.0
END DESCRIPTION:
XS GIS Cut Line= 3
      3563492.08     10234441.66      3563308.81      10234584.2
       3562717.7     10234964.39
#Sta/Elev= 30
  4690.4  322.86  4718.4  322.17  4761.9  319.74  4875.9   316.8    4941  316.47
  4968.1  317.31  4983.3  316.29    4990  313.33  4995.5  312.33  4998.2  311.83
  5001.5  312.33  5004.4  314.03  5013.7  314.82  5034.8  313.75  5040.8  314.63
  5055.9   313.2  5071.1  314.32  5077.1  313.83  5092.3  315.23  5134.5  316.12
  5143.8   316.9  5149.7  316.36  5164.9  317.44  5170.8  316.94  5192.1  318.27
  5228.3   317.8    5295  318.51  5358.6  320.91  5461.4  321.99  5625.4  325.24
#Mann= 3 ,-1 , 0
  4690.4     .05       0  4995.5     .03       0  5001.5     .05       0
Bank Sta=4995.5,5001.5
XS Rating Curve= 0 ,0
Exp/Cntr=0.3,0.1

Type RM Length L Ch R = 1 ,23290   ,822,822,822
BEGIN DESCRIPTION:
HUDSON CREEK 37.0
END DESCRIPTION:
XS GIS Cut Line= 3
      3563438.89     10234186.89      3563053.61     10234355.03
      3562585.98     10234355.03
#Sta/Elev= 30
  4683.4  319.34  4690.8  318.67  4707.5  318.69  4712.9  318.41  4730.9  318.39
  4736.3  318.14  4783.2  317.82  4806.6  317.06    4812  317.33  4840.7  316.78
  4865.4  316.53  4882.3  316.67  4887.7  316.33  4905.7  316.57  4911.1  316.16
  4929.1  316.22  4934.5  315.87  4981.4  315.84  4986.8  315.57  5028.2  315.43
  5059.5  314.98  5062.3  314.48  5065.5  314.98  5115.3   315.5  5365.3   317.1
  5465.3   317.6  5485.3  317.47  5505.3  317.88  5557.9  317.85  5571.4  317.98
#Mann= 5 ,-1 , 0
  4683.4     .05       0  4840.7     .08       0  5059.5     .07       0
  5065.5     .08       0  5557.9     .05       0
Bank Sta=5059.5,5065.5
XS Rating Curve= 0 ,0
Exp/Cntr=0.3,0.1

Type RM Length L Ch R = 1 ,22468   ,797,797,797
BEGIN DESCRIPTION:
HUDSON CREEK 36.0
END DESCRIPTION:
XS GIS Cut Line= 3
      3563530.18     10233977.44      3563056.21     10233808.16
      3562542.09     10233841.64
#Sta/Elev= 30
  4638.9  324.11  4641.7  323.62  4658.1  325.72  4667.2  325.74  4672.5   324.2
    4698  319.96  4728.8  317.04  4734.1   318.3  4759.6   318.6  4859.9   315.1
    4939  313.94  4964.5  310.21  4969.8  310.24  4987.3  308.16  4997.6  306.37
  5000.4  305.87  5003.6  306.37  5019.1  307.69    5051  308.38  5082.4  310.37
  5087.7  311.26  5104.1   310.6  5146.8  310.64  5186.4  309.13  5286.6   310.5
  5346.7  309.41  5429.3  312.54  5517.1  317.33  5576.3  316.06  5657.4  318.24
#Mann= 3 ,-1 , 0
  4638.9     .05       0  4997.6     .04       0  5003.6     .05       0
Bank Sta=4997.6,5003.6
XS Rating Curve= 0 ,0
Exp/Cntr=0.3,0.1

Type RM Length L Ch R = 1 ,21671   ,476,476,476
BEGIN DESCRIPTION:
HUDSON CREEK 34.0
END DESCRIPTION:
XS GIS Cut Line= 3
      3563539.74     10233385.42      3563131.73      10233372.4
      3562571.86      10233480.9
#Sta/Elev= 30
  4462.7  319.05  4528.1  317.28  4574.8   317.8  4610.4  318.57  4690.4   318.5
  4720.5  315.46  4741.6  314.38  4770.5  309.75  4790.5  305.55  4810.5  302.84
  4857.5  301.58  4860.3  301.08  4863.5  301.58  4889.5  303.48  4921.5  309.24
  4931.6  309.68  4946.4  309.66  4982.6  306.32  4998.1     302  5013.1  304.81
  5049.9  304.32  5054.9   305.1  5101.6  305.08  5106.7  305.93    5115   305.4
  5158.4  307.32  5205.1  311.68  5288.2   309.6  5422.3  316.39  5441.2   316.4
#Mann= 5 ,-1 , 0
  4462.7     .05       0  4528.1     .08       0  4574.8     .05       0
  4857.5     .04       0  4863.5     .05       0
Bank Sta=4857.5,4863.5
XS Rating Curve= 0 ,0
Exp/Cntr=0.3,0.1

Type RM Length L Ch R = 1 ,21195   ,692,692,692
BEGIN DESCRIPTION:
HUDSON CREEK 33.0
END DESCRIPTION:
XS GIS Cut Line= 3
      3563526.68     10233064.23      3563092.67     10232942.71
      3562710.74     10232821.18
#Sta/Elev= 30
  4657.7   309.5  4687.1  309.47  4721.2  310.23  4760.6  308.81  4787.1  308.41
  4818.2  306.18  4847.9  305.88    4868  306.21  4873.3  306.52  4890.9  304.88
  4907.4  302.58  5128.8   302.5  5131.6     302  5134.8   302.5  5152.5  302.56
  5223.3  302.74  5234.9  303.35  5255.5  306.56  5276.9   306.6    5293  305.78
  5301.6  306.22  5318.9  306.96  5325.2  307.89  5339.9  308.73  5394.9  310.47
  5421.9  311.84  5427.1  311.46  5465.8  317.27  5486.4  317.26  5509.2  319.48
#Mann= 7 ,-1 , 0
  4657.7     .05       0  4847.9     .08       0    4868     .05       0
  5128.8     .04       0  5134.8     .05       0  5152.5     .07       0
  5301.6     .05       0
Bank Sta=5128.8,5134.8
XS Rating Curve= 0 ,0
Exp/Cntr=0.3,0.1

Type RM Length L Ch R = 1 ,20503   ,98,98,98
BEGIN DESCRIPTION:
HUDSON CREEK 32.0
END DESCRIPTION:
XS GIS Cut Line= 3
      3563685.09     10232742.85      3563400.82      10232334.8
       3563040.6     10232137.33
#Sta/Elev= 30
  4410.7  314.63  4442.4  314.22  4457.2  312.22  4463.3   312.1  4472.1  309.91
    4493  306.42  4513.9   308.2    4651  305.26  4692.8  303.39  4737.3  303.11
  4773.1  302.17  4795.1   303.1  4799.9  303.09  4942.1  302.68  5077.9   302.2
  5114.9  302.54  5149.8  301.92  5152.5  301.42  5155.8  301.92  5168.8  302.92
  5180.3  305.83  5190.7  305.99  5196.4  307.02  5212.5  306.14    5240  306.92
  5248.7   307.4  5256.1  308.89  5277.9  311.15  5299.7  311.71  5318.8  313.53
#Mann= 7 ,-1 , 0
  4410.7     .05       0  4795.1     .07       0  4799.9     .08       0
  4942.1     .07       0  5077.9     .08       0  5149.8     .07       0
  5155.8     .08       0
Bank Sta=5149.8,5155.8
XS Rating Curve= 0 ,0
Exp/Cntr=0.3,0.1

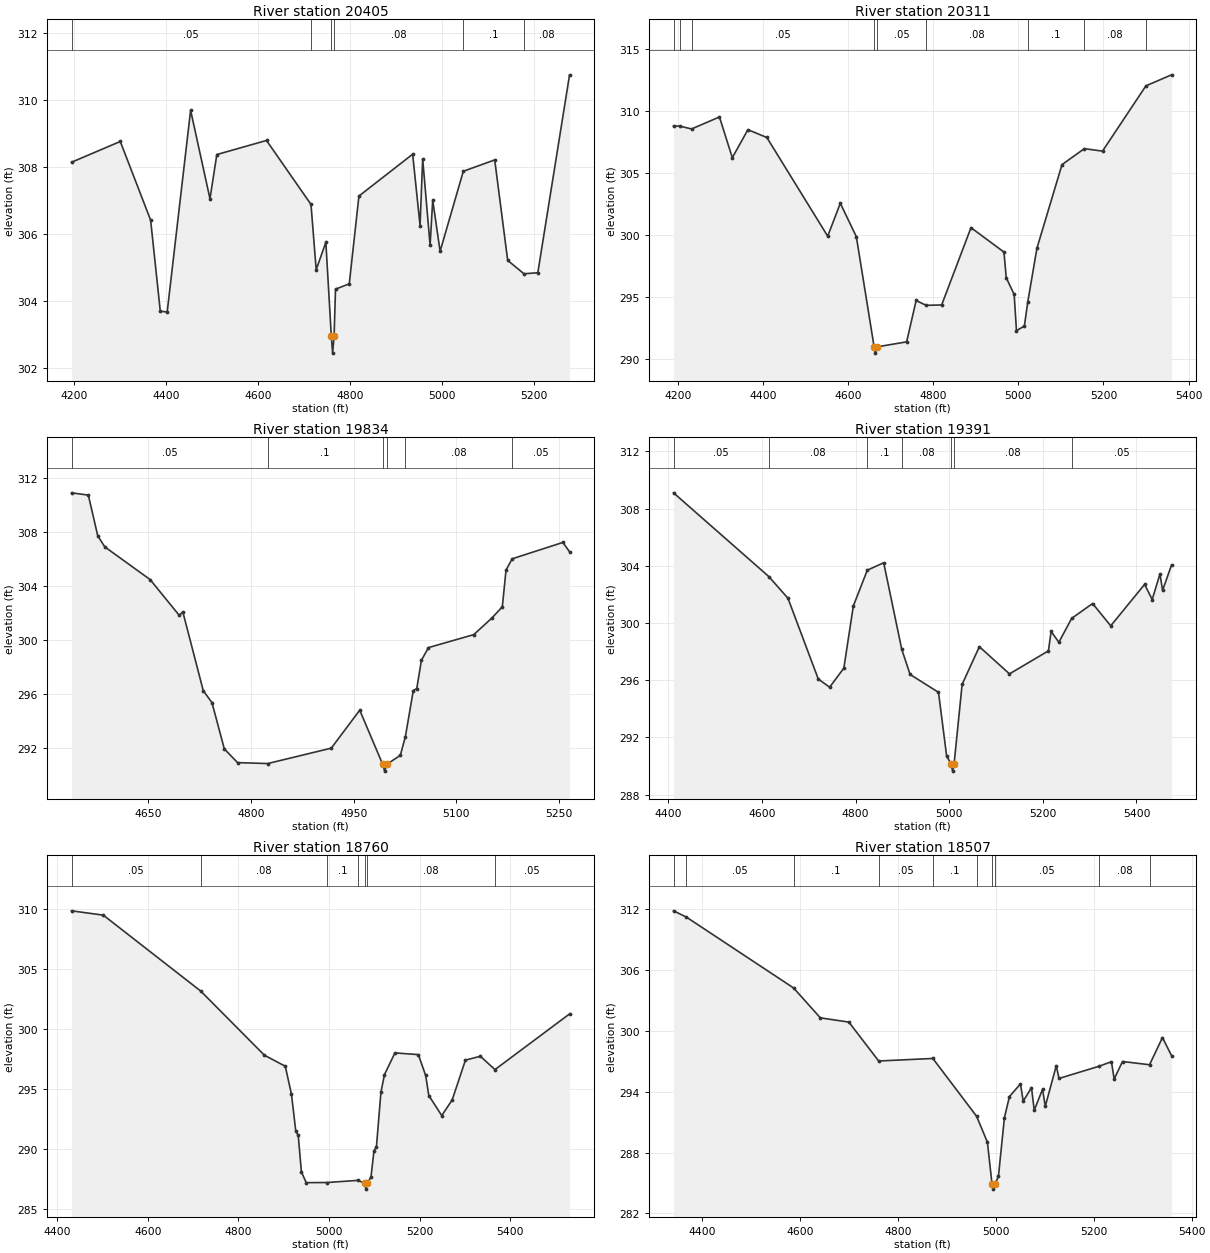
Type RM Length L Ch R = 1 ,20405   ,94,94,94
BEGIN DESCRIPTION:
HUDSON CREEK 32.1
END DESCRIPTION:
XS GIS Cut Line= 3
      3563834.87     10232816.61       3563459.6     10232259.37
      3563099.39     10232061.91
#Sta/Elev= 30
  4195.3  308.14  4301.2  308.76  4367.2  306.41  4388.2  303.69  4403.2  303.67
  4454.1  309.69  4496.2  307.05  4511.1  308.37  4619.1  308.79  4715.8  306.88
  4727.1  304.93  4748.1  305.75    4760  302.94  4762.8  302.44    4766  302.94
  4769.1  304.35    4799  304.51    4820  307.13  4936.8  308.38  4952.9  306.25
  4958.6  308.24  4974.7  305.66  4980.4  307.01  4996.5  305.48  5046.9  307.87
  5115.2  308.21  5143.4  305.21  5178.7  304.81  5208.9  304.84  5277.9  310.75
#Mann= 6 ,-1 , 0
  4195.3     .05       0  4715.8     .08       0    4760     .07       0
    4766     .08       0  5046.9      .1       0  5178.7     .08       0
Bank Sta=4760,4766
XS Rating Curve= 0 ,0
Exp/Cntr=0.3,0.1

Type RM Length L Ch R = 1 ,20311   ,477,477,477
BEGIN DESCRIPTION:
HUDSON CREEK 31.0
END DESCRIPTION:
XS GIS Cut Line= 3
      3564095.31     10232454.44      3563563.58     10232185.06
      3563031.93     10231968.06
#Sta/Elev= 30
  4189.8  308.82  4204.3  308.81  4232.2  308.58  4297.7  309.55  4327.9  306.26
  4364.6  308.52  4409.1  307.89  4552.1  299.92  4581.7  302.58  4619.4  299.88
  4661.2  290.98    4664  290.48  4667.2  290.98  4737.6  291.39  4759.9  294.73
  4783.1  294.34  4819.9  294.37  4888.8  300.61  4966.3  298.64  4971.7  296.56
  4990.3  295.22  4995.7  292.29  5014.3  292.67  5022.4  294.64  5043.8  298.95
  5102.7   305.7  5155.2  306.99  5197.9  306.79  5299.9  312.06  5360.1  312.95
#Mann= 9 ,-1 , 0
  4189.8     .05       0  4204.3     .08       0  4232.2     .05       0
  4661.2     .07       0  4667.2     .05       0  4783.1     .08       0
  5022.4      .1       0  5155.2     .08       0  5299.9      .1       0
Bank Sta=4661.2,4667.2
XS Rating Curve= 0 ,0
Exp/Cntr=0.3,0.1

Type RM Length L Ch R = 1 ,19834   ,443,443,443
BEGIN DESCRIPTION:
HUDSON CREEK 30.0
END DESCRIPTION:
XS GIS Cut Line= 3
      3563969.45     10231792.54      3563652.56     10231718.75
      3563261.93     10231623.26
#Sta/Elev= 30
  4537.9   310.9  4562.4  310.73  4576.2  307.71  4586.5   306.9  4652.7  304.48
  4695.3  301.83  4700.4   302.1  4730.3  296.26    4743  295.38  4761.1  291.95
  4780.4  290.94  4824.4  290.87  4917.3  292.01  4958.9  294.82  4992.4  290.81
  4995.2  290.31  4998.4  290.81  5018.2  291.48  5025.6  292.87  5037.1  296.27
  5042.2  296.42    5049  298.51  5059.3  299.45  5125.5  300.41    5152  301.64
  5167.2  302.47  5172.6  305.19  5181.6  306.02  5255.6  307.23  5265.4  306.54
#Mann= 6 ,-1 , 0
  4537.9     .05       0  4824.4      .1       0  4992.4     .07       0
  4998.4      .1       0  5025.6     .08       0  5181.6     .05       0
Bank Sta=4992.4,4998.4
XS Rating Curve= 0 ,0
Exp/Cntr=0.3,0.1

Type RM Length L Ch R = 1 ,19391   ,631,631,631
BEGIN DESCRIPTION:
HUDSON CREEK 29.0
END DESCRIPTION:
XS GIS Cut Line= 3
       3564092.1     10231341.64      3563348.74     10231232.64
        3563071.     10231375.85
#Sta/Elev= 30
  4411.1   309.1  4614.8  303.24  4655.5  301.73  4720.3  296.08  4744.6  295.51
  4774.9  296.84  4795.2  301.19    4825  303.69    4860  304.21  4898.6  298.16
  4916.4   296.4  4977.1  295.15  4994.6  290.67  5004.4  290.14  5007.2  289.64
  5010.4  290.14  5027.6  295.71  5064.4  298.34  5128.7  296.44    5212  298.05
  5217.6  299.41  5234.2  298.65  5261.6  300.32  5306.3  301.36    5345   299.8
  5417.4   302.7  5433.6  301.64  5450.2  303.43  5455.8  302.28  5474.9  304.05
#Mann= 7 ,-1 , 0
  4411.1     .05       0  4614.8     .08       0    4825      .1       0
  4898.6     .08       0  5004.4     .07       0  5010.4     .08       0
  5261.6     .05       0
Bank Sta=5004.4,5010.4
XS Rating Curve= 0 ,0
Exp/Cntr=0.3,0.1

Type RM Length L Ch R = 1 ,18760   ,253,253,253
BEGIN DESCRIPTION:
HUDSON CREEK 28.0
END DESCRIPTION:
XS GIS Cut Line= 3
      3564221.35     10231079.57      3563952.04     10230885.42
      3563252.61     10230569.17
#Sta/Elev= 30
  4431.6  309.84  4501.7  309.48  4716.9  303.15  4857.3  297.81  4903.5  296.89
  4917.2  294.55  4926.6  291.51  4932.1  291.12  4939.1  288.09  4949.7  287.19
  4995.8   287.2  5063.9  287.38  5078.8  287.15  5081.5  286.65  5084.8  287.15
  5092.8  287.67  5099.3  289.83  5104.8  290.19  5114.7  294.72  5122.5  296.19
  5145.6     298  5197.3  297.86  5213.5  296.12  5220.4  294.45    5249  292.78
  5272.1  294.09  5301.3   297.4  5334.2  297.72  5366.5  296.61  5531.2  301.25
#Mann= 7 ,-1 , 0
  4431.6     .05       0  4716.9     .08       0  4995.8      .1       0
  5063.9     .08       0  5078.8     .07       0  5084.8     .08       0
  5366.5     .05       0
Bank Sta=5078.8,5084.8
XS Rating Curve= 0 ,0
Exp/Cntr=0.3,0.1

Type RM Length L Ch R = 1 ,18507   ,1137,1137,1137
BEGIN DESCRIPTION:
HUDSON CREEK 27.0
END DESCRIPTION:
XS GIS Cut Line= 3
      3564289.09     10230876.47      3563872.42     10230626.47
       3563395.5     10230393.48
#Sta/Elev= 30
  4342.2  311.81  4368.5  311.19  4587.4  304.21  4641.9  301.27  4700.2  300.85
    4761  297.02  4871.6  297.27    4961  291.57    4983  289.02  4992.4   284.9
  4995.2   284.4  4998.4   284.9  5005.5  285.66  5017.7  291.42    5028  293.52
  5050.5  294.76  5056.1  293.07    5073  294.39  5078.6  292.16  5095.6  294.24
  5101.1  292.55  5123.6  296.55  5129.2   295.3  5211.4  296.51  5236.2  296.95
  5241.8  295.24  5258.8  296.97    5314  296.65  5340.4  299.33  5358.9  297.55
#Mann= 10 ,-1 , 0
  4342.2     .08       0  4368.5     .05       0  4587.4      .1       0
    4761     .05       0  4871.6      .1       0    4961     .05       0
  4992.4     .04       0  4998.4     .05       0  5211.4     .08       0
    5314     .05       0
Bank Sta=4992.4,4998.4
XS Rating Curve= 0 ,0
Exp/Cntr=0.3,0.1

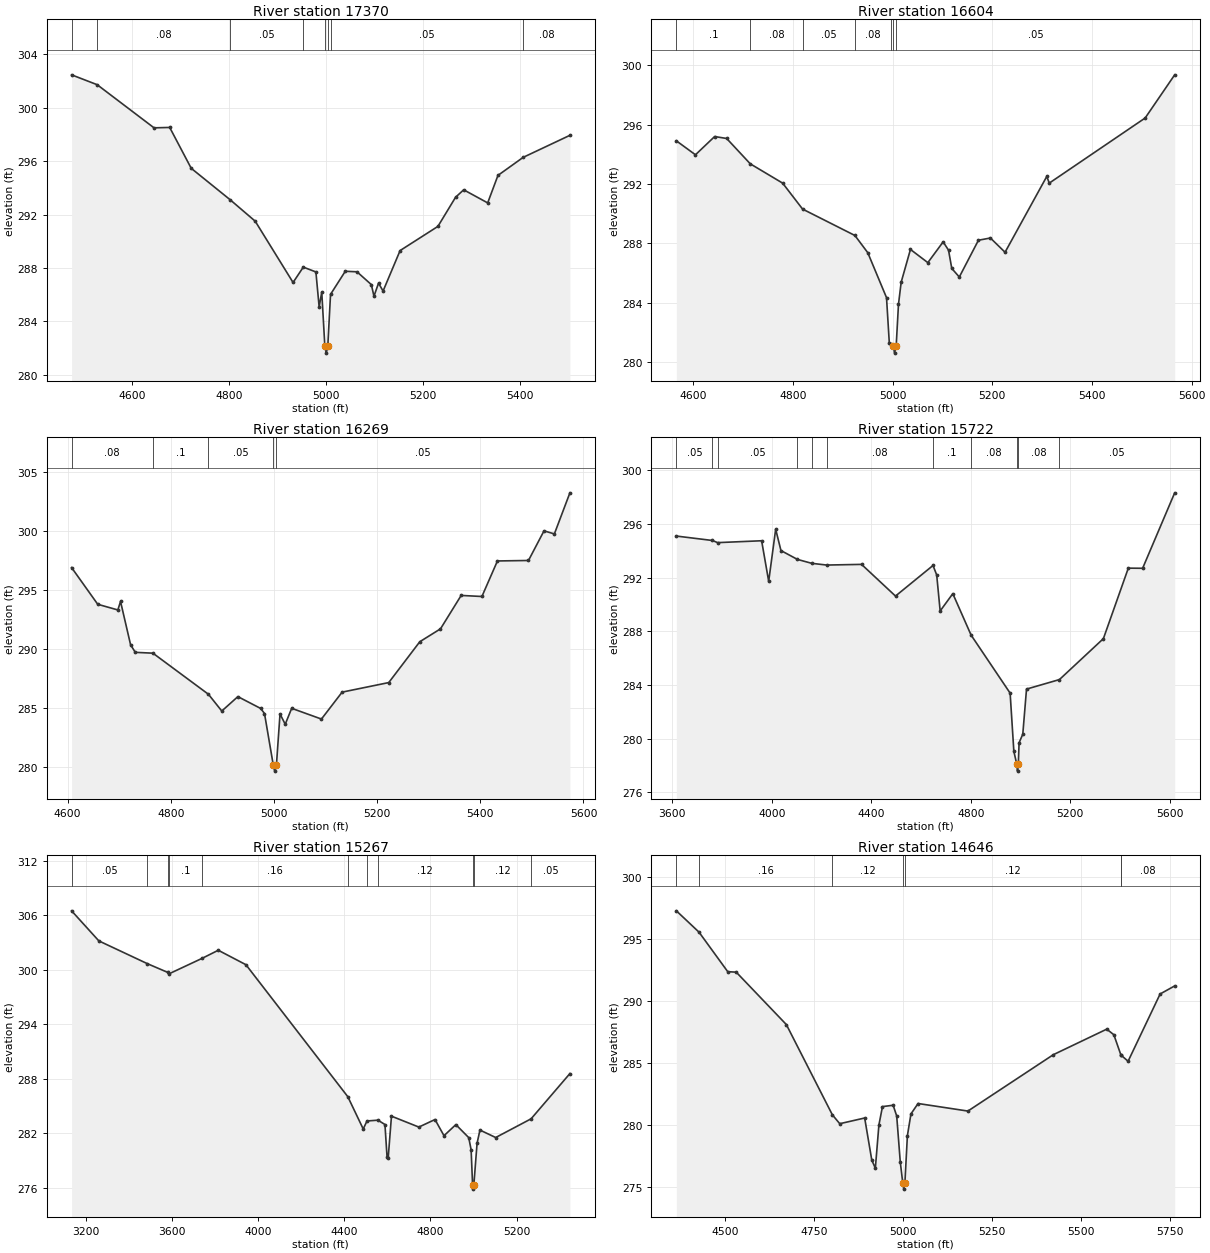
Type RM Length L Ch R = 1 ,17370   ,766,766,766
BEGIN DESCRIPTION:
HUDSON CREEK 25.0
END DESCRIPTION:
XS GIS Cut Line= 3
      3564360.05     10230086.81      3563622.18     10229791.67
      3563457.22      10229626.7
#Sta/Elev= 30
  4474.9  302.47  4527.7  301.73    4645   298.5  4677.3  298.53  4721.7  295.47
  4802.2  293.11  4853.7  291.51  4931.8  286.92  4952.9  288.07  4978.9  287.71
  4985.6  285.09    4991   286.2  4997.4  282.13  5000.2  281.63  5003.4  282.13
  5009.1  286.03  5039.5  287.76  5063.7  287.72  5093.3  286.76  5098.7  285.89
  5108.1  286.87  5117.5  286.28  5152.6  289.31  5230.6  291.12    5267   293.3
  5283.8  293.86  5333.3  292.88  5354.5  294.94  5406.5  296.29  5502.9  297.94
#Mann= 8 ,-1 , 0
  4474.9      .1       0  4527.7     .08       0  4802.2     .05       0
  4952.9     .08       0  4997.4     .07       0  5003.4     .08       0
  5009.1     .05       0  5406.5     .08       0
Bank Sta=4997.4,5003.4
XS Rating Curve= 0 ,0
Exp/Cntr=0.3,0.1

Type RM Length L Ch R = 1 ,16604   ,335,335,335
BEGIN DESCRIPTION:
HUDSON CREEK 24.0
END DESCRIPTION:
XS GIS Cut Line= 3
      3564507.58     10229565.97      3563891.28     10229314.24
       3563561.4     10229366.32
#Sta/Elev= 30
  4566.3   294.9  4604.6  293.96  4643.1  295.19  4667.2  295.06  4714.6  293.35
  4779.5  292.05  4819.5   290.3  4924.5  288.52  4950.3  287.36  4987.9  284.33
  4993.5  281.27    4997  281.19  5001.3  281.09    5004  280.59  5007.3  281.09
  5011.9  283.88  5017.3  285.37  5035.9  287.58  5070.8  286.69  5101.5  288.09
  5112.3  287.53  5118.8   286.3  5133.9  285.72  5172.3   288.2  5196.3  288.35
  5225.7  287.39  5309.4   292.5  5314.4  292.05  5506.8  296.44    5566  299.35
#Mann= 7 ,-1 , 0
  4566.3      .1       0  4714.6     .08       0  4819.5     .05       0
  4924.5     .08       0    4997     .05       0  5001.3     .04       0
  5007.3     .05       0
Bank Sta=5001.3,5007.3
XS Rating Curve= 0 ,0
Exp/Cntr=0.3,0.1

Type RM Length L Ch R = 1 ,16269   ,547,547,547
BEGIN DESCRIPTION:
HUDSON CREEK 23.0
END DESCRIPTION:
XS GIS Cut Line= 3
      3564542.09     10229191.64      3564192.11     10229091.64
      3563592.08     10229041.64
#Sta/Elev= 30
  4607.6  296.92  4658.3  293.81  4697.3  293.33  4702.5  294.05    4722  290.38
  4731.1  289.74  4765.3  289.67  4872.9  286.19  4898.8  284.77    4930  285.99
  4974.1  284.99  4981.6  284.56  4998.7  280.18  5001.4  279.68  5004.7  280.18
  5011.7  284.52  5021.8  283.65  5034.3     285    5092  284.09  5132.1  286.37
  5222.5  287.18  5282.7  290.64  5322.8  291.73  5362.9  294.56  5403.1  294.47
  5433.2  297.48  5493.4  297.52  5523.5  300.03  5543.6  299.77  5573.7  303.25
#Mann= 5 ,-1 , 0
  4607.6     .08       0  4765.3      .1       0  4872.9     .05       0
  4998.7     .04       0  5004.7     .05       0
Bank Sta=4998.7,5004.7
XS Rating Curve= 0 ,0
Exp/Cntr=0.3,0.1

Type RM Length L Ch R = 1 ,15722   ,455,455,455
BEGIN DESCRIPTION:
HUDSON CREEK 21.0
END DESCRIPTION:
XS GIS Cut Line= 4
      3565358.54     10229573.25      3565072.21     10229174.56
      3564229.82     10228602.43       3563736.1     10228567.78
#Sta/Elev= 30
  3615.9  295.09  3760.8  294.76  3781.9   294.6  3958.8  294.74  3987.2  291.72
  4015.3   295.6  4036.5  294.01  4102.8  293.35  4160.1  293.06  4220.1  292.93
  4360.7  292.98  4497.2  290.62  4648.1   292.9  4662.9  292.19  4676.8  289.51
  4727.7   290.8  4801.3  287.71  4958.2  283.39  4973.2  279.05  4985.1  278.08
  4987.9  277.58  4991.1  278.08  4994.2  279.69  5009.1  280.33  5024.1  283.69
  5156.5   284.4  5333.3  287.45  5433.5   292.7  5491.1  292.69    5620  298.31
#Mann= 11 ,-1 , 0
  3615.9     .05       0  3760.8     .16       0  3781.9     .05       0
  4102.8     .08       0  4160.1     .05       0  4220.1     .08       0
  4648.1      .1       0  4801.3     .08       0  4985.1     .07       0
  4991.1     .08       0  5156.5     .05       0
Bank Sta=4985.1,4991.1
XS Rating Curve= 0 ,0
Exp/Cntr=0.3,0.1

Type RM Length L Ch R = 1 ,15267   ,621,621,621
BEGIN DESCRIPTION:
HUDSON CREEK 20.0
END DESCRIPTION:
XS GIS Cut Line= 4
      3566261.37     10228837.19      3565693.18     10228466.83
      3564705.65     10228328.34      3564092.06     10228141.63
#Sta/Elev= 30
  3131.4  306.48  3258.2  303.17  3484.1  300.66  3577.8  299.71  3586.6  299.57
  3738.2  301.25  3813.4  302.14    3942  300.55  4415.7  286.02  4487.3  282.47
  4504.8  283.35  4555.8  283.44  4588.3  282.96  4598.2  279.35  4603.2  279.23
  4618.6  283.88  4745.9  282.68    4821  283.51  4862.8  281.73    4918  282.95
  4977.8  281.52  4988.9  280.19  4995.7  276.35  4998.4  275.85  5001.7  276.35
  5016.6   280.9    5030  282.35  5103.2  281.53  5267.8  283.59  5448.2  288.57
#Mann= 11 ,-1 , 0
  3131.4     .05       0  3484.1      .1       0  3577.8     .16       0
  3586.6      .1       0  3738.2     .16       0  4415.7     .12       0
  4504.8     .16       0  4555.8     .12       0  4995.7     .07       0
  5001.7     .12       0  5267.8     .05       0
Bank Sta=4995.7,5001.7
XS Rating Curve= 0 ,0
Exp/Cntr=0.3,0.1

Type RM Length L Ch R = 1 ,14646   ,978,978,978
BEGIN DESCRIPTION:
HUDSON CREEK 19.0
END DESCRIPTION:
XS GIS Cut Line= 3
      3565288.82      10227855.9      3565028.43     10227821.18
      3563891.26     10227829.86
#Sta/Elev= 30
  4362.9  297.25  4426.5  295.53  4507.2  292.34  4531.1   292.3  4671.9  288.07
  4801.1  280.79  4821.9  280.07  4891.9  280.53  4911.9  277.13  4921.9  276.48
  4931.9  279.97  4941.9  281.45  4971.9  281.56  4981.9  280.69  4991.9  276.99
  4998.9  275.29  5001.7  274.79  5004.9  275.29  5011.9   279.1  5021.9  280.86
  5041.9   281.7  5181.9  281.09  5421.9  285.64  5571.9   287.7  5591.9  287.25
  5611.3  285.65  5612.3   285.6  5631.9  285.11  5721.9  290.54  5762.8  291.19
#Mann= 7 ,-1 , 0
  4362.9      .1       0  4426.5     .16       0  4801.1     .12       0
  4998.9     .07       0  5004.9     .12       0  5611.3     .05       0
  5612.3     .08       0
Bank Sta=4998.9,5004.9
XS Rating Curve= 0 ,0
Exp/Cntr=0.3,0.1

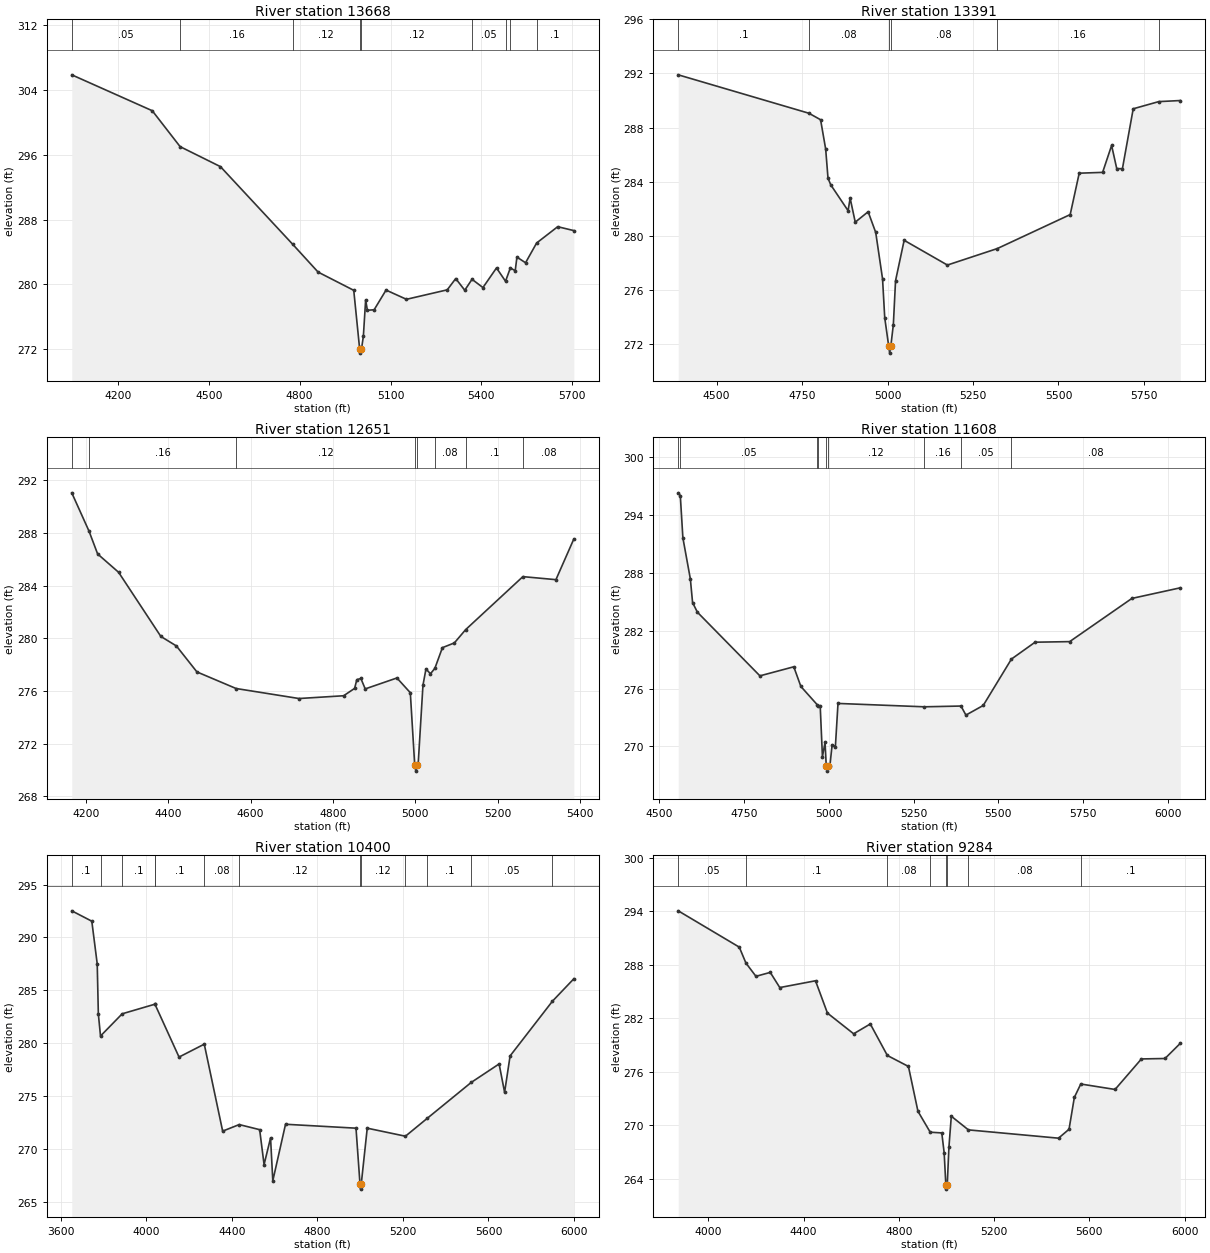
Type RM Length L Ch R = 1 ,13668   ,277,277,277
BEGIN DESCRIPTION:
HUDSON CREEK 18.0
END DESCRIPTION:
XS GIS Cut Line= 3
      3565401.89     10226859.12      3564716.17     10227006.68
      3563859.24     10227430.22
#Sta/Elev= 30
  4047.8  305.87  4313.5  301.44  4405.4  297.01  4538.6  294.54  4777.3  284.95
  4860.9  281.53  4978.6  279.28  4998.1  272.03  5000.8  271.53  5004.1  272.03
  5010.3   273.6  5017.9  278.11  5023.5  276.82  5045.9  276.88  5085.2  279.31
  5152.6  278.17  5287.2  279.34  5315.2  280.73    5345  279.29    5369  280.64
    5405  279.62  5449.8  282.04  5479.6   280.4  5495.5  282.04  5511.6   281.7
  5517.2  283.38  5545.7  282.68  5582.3  285.12  5651.8  287.13  5705.1  286.65
#Mann= 9 ,-1 , 0
  4047.8     .05       0  4405.4     .16       0  4777.3     .12       0
  4998.1     .07       0  5004.1     .12       0    5369     .05       0
  5479.6     .08       0  5495.5     .05       0  5582.3      .1       0
Bank Sta=4998.1,5004.1
XS Rating Curve= 0 ,0
Exp/Cntr=0.3,0.1

Type RM Length L Ch R = 1 ,13391   ,740,740,740
BEGIN DESCRIPTION:
HUDSON CREEK 17.0
END DESCRIPTION:
XS GIS Cut Line= 3
      3564942.37     10226521.52      3564507.73     10226822.38
      3563615.68     10227120.01
#Sta/Elev= 30
  4387.5   291.9  4769.9  289.06    4804  288.58  4818.9  286.41  4825.7  284.26
  4833.7  283.77  4884.4  281.86  4890.5  282.78  4905.4  281.01  4943.1  281.78
  4965.3  280.25  4985.3  276.82  4991.7  273.94  5003.4  271.83  5006.1  271.33
  5009.4  271.83  5016.9  273.44  5023.3  276.68  5048.5  279.67    5175  277.84
  5321.2  279.06  5534.3  281.57  5560.7  284.63  5629.2  284.69  5655.5  286.68
  5670.5  284.97  5687.1  284.96  5718.7  289.39  5793.4  289.92  5856.5     290
#Mann= 6 ,-1 , 0
  4387.5      .1       0  4769.9     .08       0  5003.4     .07       0
  5009.4     .08       0  5321.2     .16       0  5793.4      .1       0
Bank Sta=5003.4,5009.4
XS Rating Curve= 0 ,0
Exp/Cntr=0.3,0.1

Type RM Length L Ch R = 1 ,12651   ,1043,1043,1043
BEGIN DESCRIPTION:
HUDSON CREEK 16.0
END DESCRIPTION:
XS GIS Cut Line= 3
      3564742.09     10226091.65      3563942.11     10226341.64
      3563592.13     10226491.63
#Sta/Elev= 30
  4165.8  291.04  4207.7  288.13  4228.6   286.4  4279.5  285.01  4382.1  280.14
  4419.8  279.42  4469.6  277.45  4564.7  276.19  4717.4  275.43  4825.8  275.64
  4852.5   276.2  4857.8  276.86  4867.7  276.95  4878.2  276.16  4955.2  276.99
  4987.7  275.87  4998.3  270.42  5001.1  269.92  5004.3  270.42  5006.7  270.42
  5018.4  276.44  5025.7  277.67  5036.6  277.31  5047.3  277.72  5065.6  279.29
  5094.6  279.65  5122.1  280.66    5261  284.68  5341.2  284.45  5384.7  287.54
#Mann= 8 ,-1 , 0
  4165.8     .05       0  4207.7     .16       0  4564.7     .12       0
  4998.3     .07       0  5004.3     .12       0  5047.3     .08       0
  5122.1      .1       0    5261     .08       0
Bank Sta=4998.3,5004.3
XS Rating Curve= 0 ,0
Exp/Cntr=0.3,0.1

Type RM Length L Ch R = 1 ,11608   ,1208,1208,1208
BEGIN DESCRIPTION:
HUDSON CREEK 14.0
END DESCRIPTION:
XS GIS Cut Line= 3
      3564692.11     10225991.65      3564392.11     10225641.64
       3563392.1     10225841.64
#Sta/Elev= 30
  4555.8   296.3  4561.9  296.01  4569.5  291.63  4591.5  287.38  4598.1  284.92
  4612.3  283.92  4796.7  277.32  4896.6  278.26  4917.5  276.22  4965.6  274.33
  4968.8  274.21  4974.5  274.22  4981.1  268.94  4988.8  270.43  4992.4  267.94
  4995.1  267.44  4998.4  267.94  5003.1  267.99  5009.7  270.18  5019.3  269.98
    5027  274.46  5281.6  274.11  5389.7  274.19  5404.3  273.25  5455.3  274.25
  5538.5  279.06  5608.3  280.81  5710.3  280.87  5893.8  285.35  6036.6  286.45
#Mann= 9 ,-1 , 0
  4555.8     .16       0  4561.9     .05       0  4965.6      .1       0
  4968.8     .12       0  4992.4     .07       0  4998.4     .12       0
  5281.6     .16       0  5389.7     .05       0  5538.5     .08       0
Bank Sta=4992.4,4998.4
XS Rating Curve= 0 ,0
Exp/Cntr=0.3,0.1

Type RM Length L Ch R = 1 ,10400   ,1116,1116,1116
BEGIN DESCRIPTION:
HUDSON CREEK 12.0
END DESCRIPTION:
XS GIS Cut Line= 3
      3565583.95     10224583.34      3564600.45     10224780.12
      3563292.12     10225091.64
#Sta/Elev= 30
  3651.5  292.52  3745.2  291.54  3770.5  287.51  3775.8  282.77  3785.9  280.69
  3887.4  282.79  4039.2  283.69  4040.1  283.71  4153.1   278.7  4271.1  279.92
  4357.1   271.7  4434.5  272.32  4530.1  271.84  4550.8  268.54  4581.1  271.06
  4591.6  267.01  4651.1  272.35  4980.7  271.98  4999.3  266.72    5002  266.22
  5005.3  266.72  5033.2  271.98  5211.9  271.22  5314.4  272.92  5519.3   276.3
  5649.9  278.05  5675.6  275.37  5701.3  278.81  5899.3  283.98  5999.4   286.1
#Mann= 13 ,-1 , 0
  3651.5      .1       0  3785.9     .08       0  3887.4      .1       0
  4039.2     .08       0  4040.1      .1       0  4271.1     .08       0
  4434.5     .12       0  4999.3     .07       0  5005.3     .12       0
  5211.9     .05       0  5314.4      .1       0  5519.3     .05       0
  5899.3     .08       0
Bank Sta=4999.3,5005.3
XS Rating Curve= 0 ,0
Exp/Cntr=0.3,0.1

Type RM Length L Ch R = 1 ,9284    ,329,329,329
BEGIN DESCRIPTION:
HUDSON CREEK 10.1
END DESCRIPTION:
XS GIS Cut Line= 3
      3565398.34     10224101.46      3563971.96     10224160.32
      3563367.09     10224474.73
#Sta/Elev= 30
  3873.1  294.05  4129.6  289.98  4157.4   288.2  4199.6  286.71  4259.7  287.15
  4299.7  285.45  4449.8  286.21  4499.9  282.59    4610  280.27    4680  281.37
  4751.6  277.84  4840.2  276.61  4880.2  271.58  4931.7  269.24  4980.3  269.16
  4990.3  266.94  4997.3  263.36    5000  262.86  5003.3  263.36  5010.3  267.55
  5020.3  271.03  5092.2   269.5  5470.7  268.57  5514.9  269.57  5537.2  273.14
  5564.2  274.64  5708.3  274.03    5819  277.45  5918.1   277.5  5982.4   279.2
#Mann= 8 ,-1 , 0
  3873.1     .05       0  4157.4      .1       0  4751.6     .08       0
  4931.7     .12       0  4997.3     .07       0  5003.3     .12       0
  5092.2     .08       0  5564.2      .1       0
Bank Sta=4997.3,5003.3
XS Rating Curve= 0 ,0
Exp/Cntr=0.3,0.1

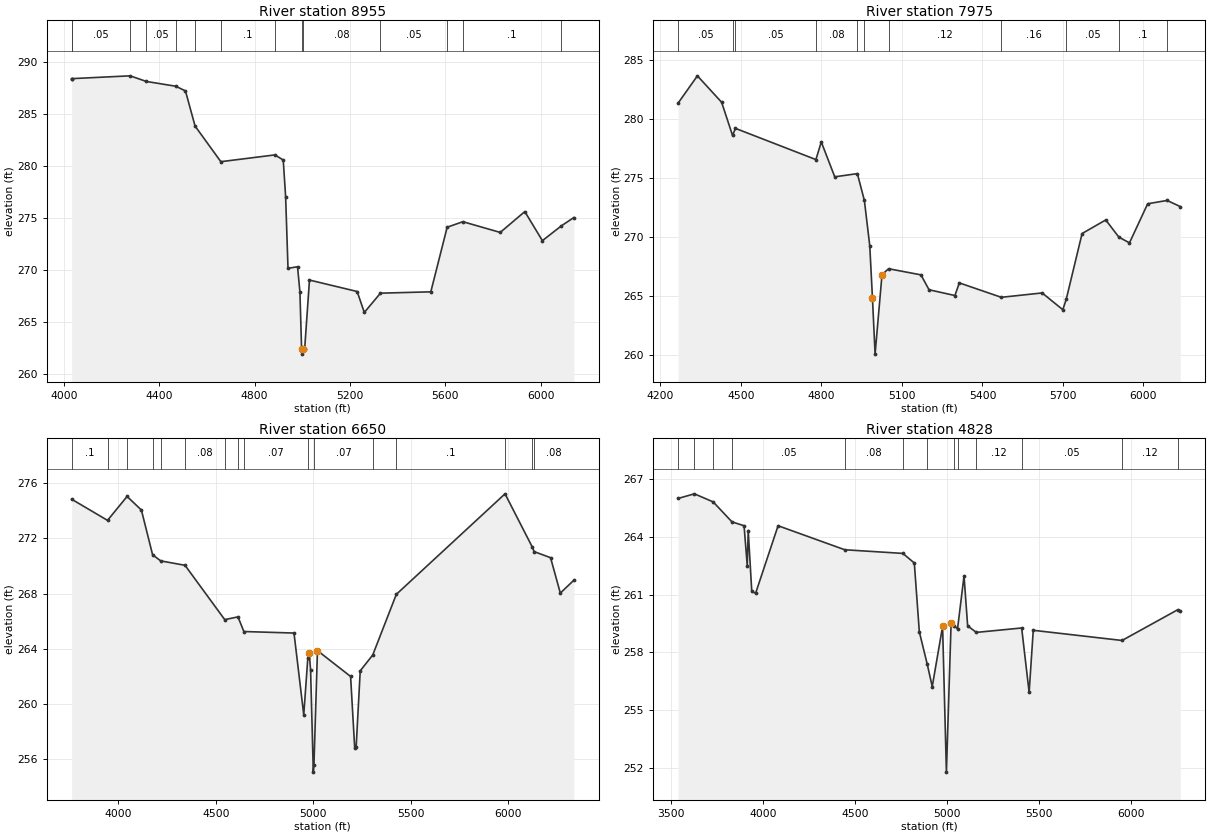
Type RM Length L Ch R = 1 ,8955    ,980,980,980
BEGIN DESCRIPTION:
HUDSON CREEK 10.0
END DESCRIPTION:
XS GIS Cut Line= 3
      3565219.41     10223784.72        3563793.     10223843.58
      3563189.49     10224157.29
#Sta/Elev= 30
  4032.1  288.39  4032.9  288.39  4277.4  288.66  4345.7  288.12  4469.3  287.66
  4509.8  287.21  4550.1  283.84  4658.3  280.42  4885.3  281.07  4920.2  280.58
  4930.2  277.07  4940.2  270.18  4980.2  270.34  4990.2  267.92  4997.2  262.45
    5000  261.95  5003.2  262.45  5010.2  262.47  5030.3  269.06  5230.4  267.96
  5260.5  265.95  5328.2   267.8  5539.6  267.93  5608.2  274.13  5674.2  274.66
    5831  273.63  5934.1  275.63  6007.9  272.84  6087.5  274.26  6139.9  275.06
#Mann= 14 ,-1 , 0
  4032.1      .1       0  4032.9     .05       0  4277.4     .08       0
  4345.7     .05       0  4469.3     .08       0  4550.1     .05       0
  4658.3      .1       0  4885.3     .08       0  4997.2     .07       0
  5003.2     .08       0  5328.2     .05       0  5608.2     .08       0
  5674.2      .1       0  6087.5     .08       0
Bank Sta=4997.2,5003.2
XS Rating Curve= 0 ,0
Exp/Cntr=0.3,0.1

Type RM Length L Ch R = 1 ,7975    ,1325,1325,1325
BEGIN DESCRIPTION:
HUDSON CREEK 8.0
END DESCRIPTION:
XS GIS Cut Line= 3
      3564993.72     10223012.15      3563985.78     10223097.97
      3563224.41     10223497.46
#Sta/Elev= 30
  4265.8  281.36  4337.7  283.67    4428  281.43  4468.5  278.63  4479.6  279.22
  4779.3  276.58  4799.3  278.07  4849.5  275.12  4933.7  275.39  4959.9  273.12
    4980  269.28    4990  264.86  4999.8  260.11  5025.6  266.84  5050.2  267.34
  5170.7  266.82  5200.8  265.56  5297.3  265.07  5313.7  266.14  5470.2  264.92
  5622.4  265.29  5699.4  263.87  5712.2  264.76  5771.2  270.32  5859.4  271.47
  5908.4  270.01  5947.8  269.53  6015.6  272.84  6088.1  273.12  6137.2   272.6
#Mann= 11 ,-1 , 0
  4265.8     .05       0  4468.5      .1       0  4479.6     .05       0
  4779.3     .08       0  4933.7     .12       0  4959.9     .07       0
  5050.2     .12       0  5470.2     .16       0  5712.2     .05       0
  5908.4      .1       0  6088.1     .05       0
Bank Sta=4990,5025.6
XS Rating Curve= 0 ,0
Exp/Cntr=0.3,0.1

Type RM Length L Ch R = 1 ,6650    ,1822,1822,1822
BEGIN DESCRIPTION:
HUDSON CREEK 5.0
END DESCRIPTION:
XS GIS Cut Line= 3
      3564646.53     10222100.69      3563648.22     10222239.58
       3562492.4     10223300.31
#Sta/Elev= 30
  3759.7  274.82  3943.8  273.29  4044.1  275.02  4117.5  274.04  4175.1   270.8
  4216.6  270.36  4341.4  270.04  4545.2  266.11  4613.2  266.31  4643.3  265.25
  4900.6  265.14  4950.6  259.22  4971.5  263.34  4978.9  263.67  4985.7  262.47
  4999.6  255.08  5002.9  255.58  5020.9  263.87    5191     262    5212  256.82
  5219.4  256.88  5240.4  262.41  5304.5  263.55  5425.6  267.94  5983.3  275.21
  6122.2  271.39  6132.7  271.03    6217  270.59    6267  268.03  6336.4  268.96
#Mann= 16 ,-1 , 0
  3759.7      .1       0  3943.8     .08       0  4044.1     .05       0
  4175.1     .08       0  4216.6     .05       0  4341.4     .08       0
  4545.2     .07       0  4613.2     .08       0  4643.3     .07       0
  4971.5     .07       0  5002.9     .07       0  5304.5     .16       0
  5425.6      .1       0  5983.3     .08       0  6122.2     .05       0
  6132.7     .08       0
Bank Sta=4978.9,5020.9
XS Rating Curve= 0 ,0
Exp/Cntr=0.3,0.1

Type RM Length L Ch R = 1 ,4828    ,0,0,0
BEGIN DESCRIPTION:
HUDSON CREEK 1.0
END DESCRIPTION:
XS GIS Cut Line= 3
       3564174.3     10221629.29      3562552.72     10221122.23
      3561570.09     10221433.98
#Sta/Elev= 30
  3536.9     266  3625.3  266.24  3727.5  265.82  3829.7  264.78  3895.4  264.58
  3912.7   262.5    3918  264.33  3937.3  261.16  3958.3  261.07  4080.3  264.58
  4442.8  263.33  4758.7  263.14  4820.9  262.64  4848.1  259.06    4891  257.38
  4918.3  256.21  4974.6  259.34  4995.3  251.76  5020.9  259.52  5037.5  259.38
  5055.8  259.21  5091.1  261.97  5110.8  259.37    5158  259.03  5404.4  259.26
    5445  255.91  5467.4  259.14  5950.1  258.61  6252.9  260.21  6266.8  260.15
#Mann= 13 ,-1 , 0
  3536.9     .08       0  3625.3     .05       0  3727.5      .1       0
  3829.7     .05       0  4442.8     .08       0  4758.7     .12       0
    4891     .05       0  5037.5     .12       0  5055.8     .05       0
    5158     .12       0  5404.4     .05       0  5950.1     .12       0
  6252.9     .16       0
Bank Sta=4974.6,5020.9
XS Rating Curve= 0 ,0
Exp/Cntr=0.3,0.1

Chan Stop Cuts=-1
Use User Specified Reach Order=0
Composite Channel Slope=5