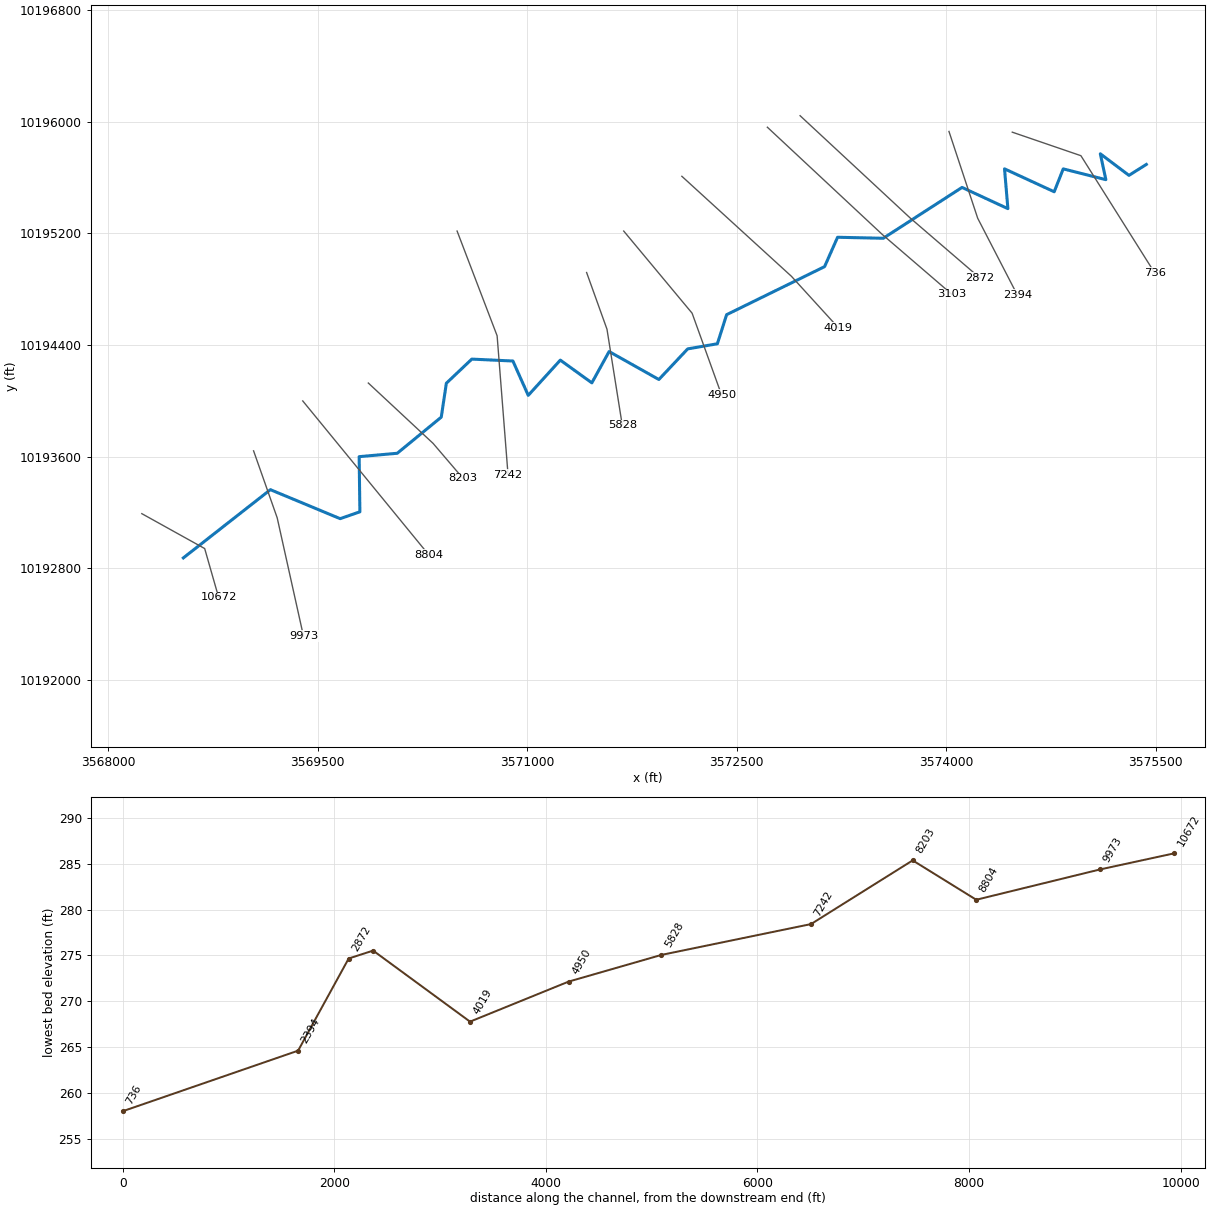
--- LICK CREEK TRIBUTARY 13.prj (project) ---

Proj Title=LICK CREEK TRIBUTARY 13 Base Level Engineering
Current Plan=p01
Default Exp/Contr=0.3,0.1
English Units
Geom File=g01
Flow File=f01
Plan File=p01
BEGIN DESCRIPTION:
LICK CREEK TRIBUTARY 13
END DESCRIPTION:

--- LICK CREEK TRIBUTARY 13.p01 (plan) ---

Plan Title=Multiple Run
Short Identifier=Multiple
Geom File=g01
Flow File=f01
Subcritical Flow
K Sum by GR= 0
Std Step Tol= 0.01
Critical Tol= 0.01
Num of Std Step Trials= 20
Max Error Tol= 0.3
Flow Tol Ratio= 0.001
Split Flow NTrial= 30
Split Flow Tol= 0.02
Split Flow Ratio= 0.02
Log Output Level= 0
Friction Slope Method= 1
Unsteady Friction Slope Method= 2
Unsteady Bridges Friction Slope Method= 1
Parabolic Critical Depth
Global Vel Dist=  1 , 1 , 1
Global Log Level= 0
CheckData=True
Encroach Param= -1, 0, 0, 0
BEGIN DESCRIPTION:
Multiple Run
END DESCRIPTION:

--- LICK CREEK TRIBUTARY 13.f01 (steady flow) ---

Flow Title=Multiple
Number of Profiles=7
Profile Names=10-year,25-year,50-year,1pct_min,100-year,1pct_plu,500-year
River Rch & RM= LICK CREEK TRIBU,Reach-1,10672
     535     715     860     759    1027    1389    1464
River Rch & RM= LICK CREEK TRIBU,Reach-1,4950
     548     727     870     763    1032    1395    1453
River Rch & RM= LICK CREEK TRIBU,Reach-1,2872
     665     899    1090     967    1308    1769    1888
Boundary for River Rch & Prof#=LICK CREEK TRIBU,Reach-1,1
Up Type=0
Dn Type=3
Dn Slope=0.005
Boundary for River Rch & Prof#=LICK CREEK TRIBU,Reach-1,2
Up Type=0
Dn Type=3
Dn Slope=0.005
Boundary for River Rch & Prof#=LICK CREEK TRIBU,Reach-1,3
Up Type=0
Dn Type=3
Dn Slope=0.005
Boundary for River Rch & Prof#=LICK CREEK TRIBU,Reach-1,4
Up Type=0
Dn Type=3
Dn Slope=0.005
Boundary for River Rch & Prof#=LICK CREEK TRIBU,Reach-1,5
Up Type=0
Dn Type=3
Dn Slope=0.005
Boundary for River Rch & Prof#=LICK CREEK TRIBU,Reach-1,6
Up Type=0
Dn Type=3
Dn Slope=0.005
Boundary for River Rch & Prof#=LICK CREEK TRIBU,Reach-1,7
Up Type=0
Dn Type=3
Dn Slope=0.005

--- LICK CREEK TRIBUTARY 13.g01 (geometry) ---

Geom Title=Existing Conditions

River Reach=LICK CREEK TRIBU,Reach-1
Reach XY= 30
      3568539.39     10192874.72      3569162.58     10193363.40
      3569661.95     10193155.74      3569803.04     10193204.89
      3569797.83     10193599.85      3570070.40     10193624.16
      3570385.50     10193882.84      3570421.96     10194125.90
      3570604.25     10194298.64      3570898.44     10194284.95
      3571008.06     10194038.95      3571237.77     10194291.47
      3571463.37     10194128.56      3571586.97     10194352.87
      3571943.12     10194152.55      3572149.28     10194371.74
      3572361.96     10194408.63      3572428.15     10194616.96
      3573129.10     10194960.93      3573222.42     10195171.43
      3573549.30     10195164.18      3574113.26     10195528.42
      3574441.40     10195376.29      3574417.23     10195661.51
      3574772.90     10195497.31      3574837.53     10195661.32
      3575142.68     10195583.90      3575102.98     10195769.28
      3575308.02     10195614.79      3575432.11     10195692.96

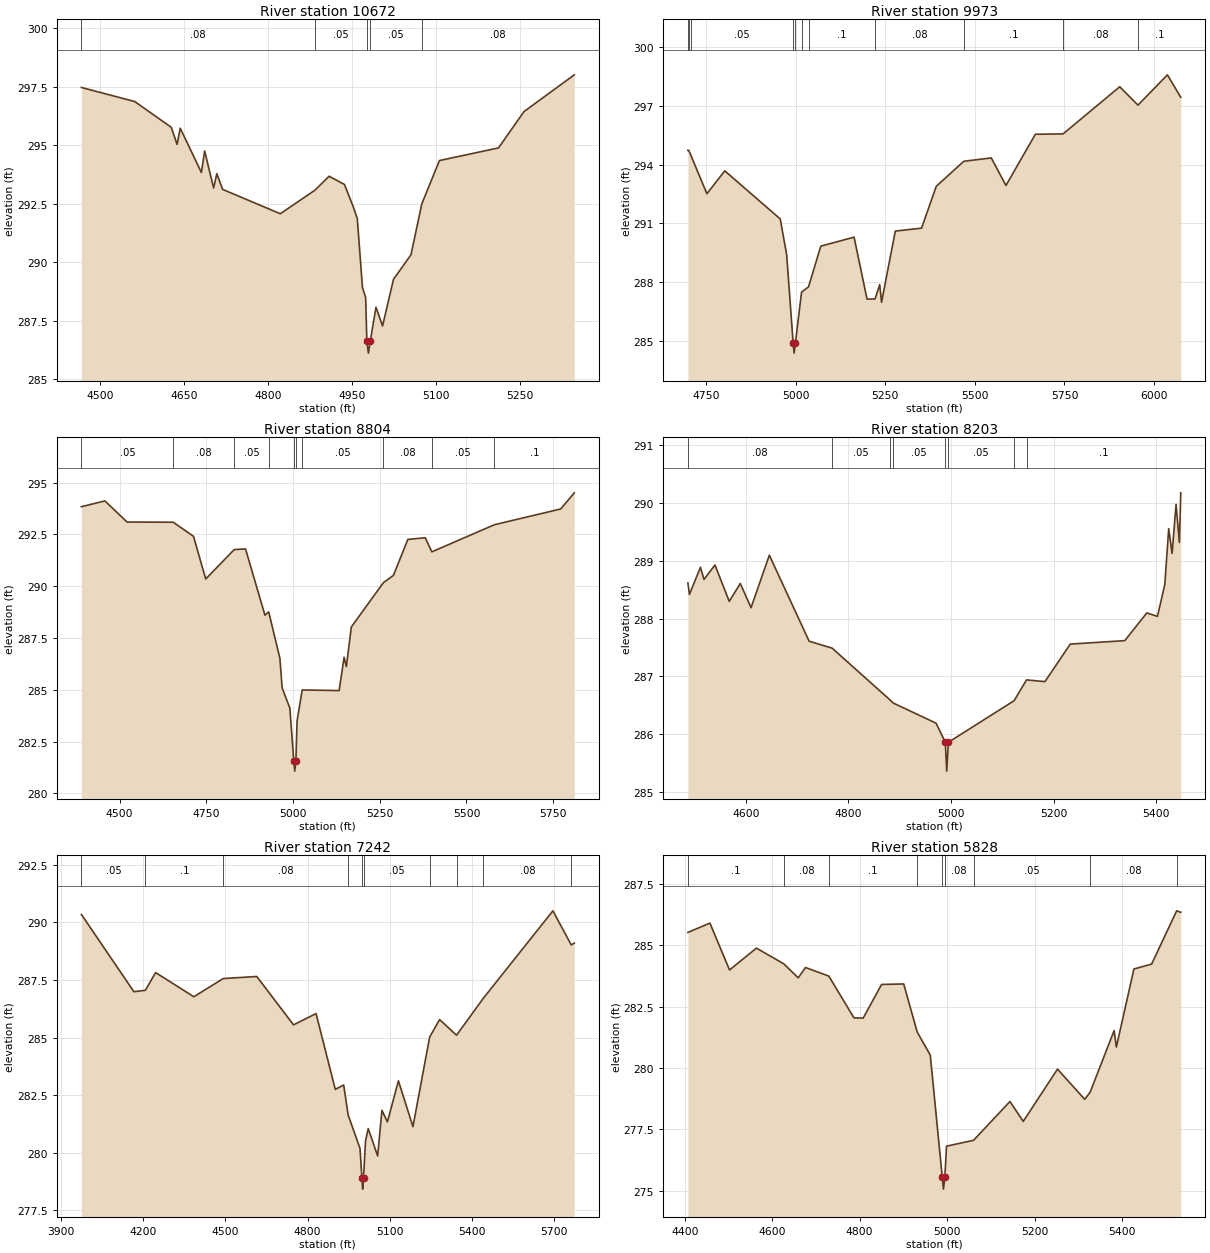
Type RM Length L Ch R = 1,10672,699,699,699
BEGIN DESCRIPTION:
LICK CREEK TRIBUTARY 13 20.0
END DESCRIPTION:
XS GIS Cut Line= 3
      3568242.09     10193191.65      3568692.11     10192941.64
      3568792.10     10192591.65
#Sta/Elev= 30
  4467.4  297.46  4562.4  296.86  4627.6  295.76  4637.9  295.03  4643.6  295.72
  4681.3  293.83  4687.1  294.75  4703.1  293.17  4708.8  293.78  4719.1  293.11
  4822.0  292.07  4883.4  293.07  4909.0  293.67  4936.4  293.32  4952.5  292.34
  4959.3  291.86  4968.5  288.92  4974.2  288.49  4976.3  286.62  4979.1  286.12
  4982.3  286.62  4992.6  288.08  5004.3  287.28  5023.8  289.27  5055.0  290.32
  5074.3  292.49  5105.7  294.34  5211.0  294.88  5256.5  296.43  5346.2  298.00
#Mann=5,-1,0
  4467.4    0.08       0  4883.4    0.05       0  4976.3    0.04       0
  4982.3    0.05       0  5074.3    0.08       0
Bank Sta=4976.3,4982.3
Exp/Cntr=0.3,0.1

Type RM Length L Ch R = 1,9973,1169,1169,1169
BEGIN DESCRIPTION:
LICK CREEK TRIBUTARY 13 18.0
END DESCRIPTION:
XS GIS Cut Line= 3
      3569042.10     10193641.65      3569211.07     10193161.99
      3569399.08     10192315.27
#Sta/Elev= 30
  4698.8  294.74  4701.1  294.74  4707.3  294.48  4751.8  292.52  4801.8  293.69
  4956.6  291.23  4974.5  289.40  4992.7  284.87  4995.4  284.37  4998.7  284.87
  5016.1  287.49  5035.6  287.76  5069.8  289.84  5162.7  290.30  5198.9  287.13
  5221.3  287.14  5234.3  287.87  5239.4  286.97  5277.8  290.61  5351.1  290.76
  5392.1  292.90  5469.1  294.18  5545.7  294.35  5586.7  292.94  5668.7  295.56
  5746.2  295.58  5904.3  297.99  5955.2  297.05  6037.4  298.60  6074.7  297.45
#Mann=11,-1,0
  4698.8    0.08       0  4701.1     0.1       0  4707.3    0.05       0
  4992.7    0.04       0  4998.7    0.05       0  5016.1    0.08       0
  5035.6     0.1       0  5221.3    0.08       0  5469.1     0.1       0
  5746.2    0.08       0  5955.2     0.1       0
Bank Sta=4992.7,4998.7
Exp/Cntr=0.3,0.1

Type RM Length L Ch R = 1,8804,601,601,601
BEGIN DESCRIPTION:
LICK CREEK TRIBUTARY 13 16.0
END DESCRIPTION:
XS GIS Cut Line= 3
      3569394.18     10193998.95      3569844.19     10193448.93
      3570294.20     10192898.92
#Sta/Elev= 30
  4389.7  293.84  4457.4  294.12  4521.3  293.10  4654.4  293.09  4712.9  292.41
  4748.1  290.35  4830.4  291.77  4862.9  291.80  4918.9  288.60  4929.7  288.76
  4962.0  286.52  4968.5  285.09  4990.7  284.11  5002.1  281.57  5004.8  281.07
  5008.1  281.57  5011.5  283.49  5026.3  284.99  5132.8  284.96  5147.2  286.57
  5153.7  286.12  5168.0  288.03  5260.4  290.17  5289.3  290.52  5331.0  292.26
  5381.1  292.34  5400.2  291.66  5580.7  292.97  5771.7  293.73  5811.0  294.51
#Mann=10,-1,0
  4389.7    0.05       0  4654.4    0.08       0  4830.4    0.05       0
  4929.7    0.08       0  5002.1    0.07       0  5008.1    0.08       0
  5026.3    0.05       0  5260.4    0.08       0  5400.2    0.05       0
  5580.7     0.1       0
Bank Sta=5002.1,5008.1
Exp/Cntr=0.3,0.1

Type RM Length L Ch R = 1,8203,961,961,961
BEGIN DESCRIPTION:
LICK CREEK TRIBUTARY 13 14.0
END DESCRIPTION:
XS GIS Cut Line= 3
      3569863.42     10194127.32      3570326.96     10193695.03
      3570539.84     10193445.80
#Sta/Elev= 30
  4486.7  288.62  4489.7  288.42  4511.2  288.89  4518.1  288.68  4539.5  288.93
  4567.4  288.30  4588.9  288.61  4609.9  288.19  4645.6  289.10  4723.2  287.61
  4768.1  287.49  4881.4  286.59  4887.2  286.54  4970.9  286.19  4988.9  285.86
  4991.7  285.36  4994.9  285.86  5123.2  286.58  5147.4  286.94  5183.3  286.91
  5232.7  287.56  5339.1  287.62  5382.0  288.10  5402.8  288.04  5417.1  288.59
  5424.8  289.56  5431.4  289.13  5439.1  289.98  5445.6  289.32  5448.3  290.18
#Mann=8,-1,0
  4486.7    0.08       0  4768.1    0.05       0  4881.4    0.08       0
  4887.2    0.05       0  4988.9    0.04       0  4994.9    0.05       0
  5123.2    0.08       0  5147.4     0.1       0
Bank Sta=4988.9,4994.9
Exp/Cntr=0.3,0.1

Type RM Length L Ch R = 1,7242,1414,1414,1414
BEGIN DESCRIPTION:
LICK CREEK TRIBUTARY 13 13.0
END DESCRIPTION:
XS GIS Cut Line= 3
      3570498.84     10195215.84      3570785.29     10194465.86
      3570863.42     10193471.05
#Sta/Elev= 30
  3973.8  290.34  4165.4  286.99  4207.3  287.05  4244.9  287.82  4384.5  286.77
  4491.8  287.56  4614.4  287.65  4748.7  285.55  4831.0  286.04  4901.2  282.75
  4931.9  282.94  4948.2  281.64  4991.5  280.19  4998.5  278.92  5001.3  278.42
  5004.5  278.92  5011.6  280.50  5021.6  281.05  5056.0  279.86  5071.7  281.84
  5091.8  281.34  5131.9  283.12  5185.0  281.13  5246.0  285.02  5282.4  285.78
  5344.2  285.10  5442.5  286.71  5696.3  290.50  5763.3  289.02  5774.5  289.10
#Mann=10,-1,0
  3973.8    0.05       0  4207.3     0.1       0  4491.8    0.08       0
  4948.2    0.05       0  4998.5    0.04       0  5004.5    0.05       0
  5246.0    0.08       0  5344.2     0.1       0  5442.5    0.08       0
  5763.3     0.1       0
Bank Sta=4998.5,5004.5
Exp/Cntr=0.3,0.1

Type RM Length L Ch R = 1,5828,878,878,878
BEGIN DESCRIPTION:
LICK CREEK TRIBUTARY 13 11.0
END DESCRIPTION:
XS GIS Cut Line= 3
      3571425.91     10194919.00      3571571.75     10194512.74
      3571681.02     10193825.92
#Sta/Elev= 30
  4407.2  285.52  4457.5  285.90  4502.4  283.99  4563.9  284.88  4626.5  284.24
  4659.4  283.67  4676.2  284.09  4729.5  283.74  4786.9  282.04  4808.1  282.03
  4850.1  283.40  4900.7  283.42  4931.6  281.46  4961.5  280.52  4988.8  275.56
  4991.6  275.06  4994.8  275.56  4998.6  276.81  5060.4  277.05  5143.7  278.63
  5174.1  277.82  5252.4  279.95  5314.6  278.72  5327.1  279.01  5381.9  281.52
  5387.0  280.85  5427.2  284.03  5467.7  284.23  5524.9  286.40  5534.3  286.34
#Mann=9,-1,0
  4407.2     0.1       0  4626.5    0.08       0  4729.5     0.1       0
  4931.6    0.08       0  4988.8    0.07       0  4994.8    0.08       0
  5060.4    0.05       0  5327.1    0.08       0  5524.9     0.1       0
Bank Sta=4988.8,4994.8
Exp/Cntr=0.3,0.1

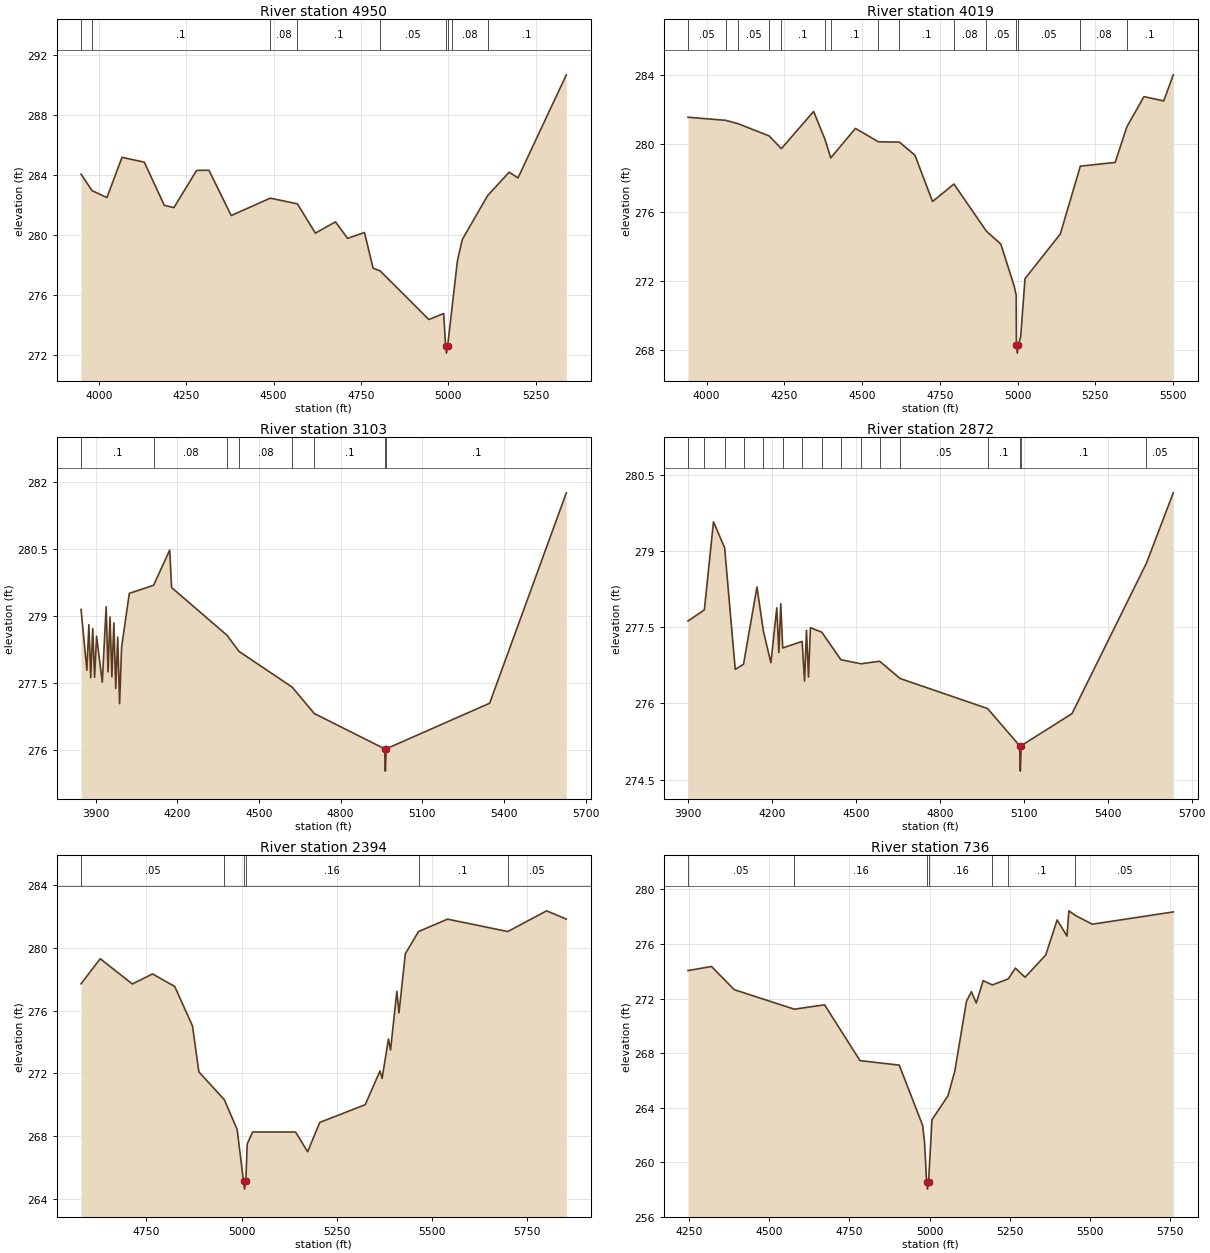
Type RM Length L Ch R = 1,4950,931,931,931
BEGIN DESCRIPTION:
LICK CREEK TRIBUTARY 13 9.0
END DESCRIPTION:
XS GIS Cut Line= 3
      3571691.55     10195215.85      3572181.13     10194627.32
      3572392.12     10194041.61
#Sta/Elev= 30
  3949.4  284.08  3980.9  282.98  4023.5  282.52  4066.5  285.20  4130.3  284.88
  4187.6  282.00  4215.0  281.85  4280.0  284.33  4315.2  284.34  4379.0  281.32
  4490.8  282.48  4568.3  282.10  4619.8  280.15  4677.1  280.90  4711.8  279.80
  4760.1  280.19  4784.8  277.81  4805.1  277.63  4944.3  274.39  4986.7  274.79
  4992.1  272.65  4994.8  272.15  4998.1  272.65  5009.4  274.94  5025.8  278.28
  5039.8  279.72  5112.4  282.65  5173.9  284.21  5199.3  283.83  5337.5  290.70
#Mann=9,-1,0
  3949.4    0.08       0  3980.9     0.1       0  4490.8    0.08       0
  4568.3     0.1       0  4805.1    0.05       0  4992.1    0.04       0
  4998.1    0.05       0  5009.4    0.08       0  5112.4     0.1       0
Bank Sta=4992.1,4998.1
Exp/Cntr=0.3,0.1

Type RM Length L Ch R = 1,4019,916,916,916
BEGIN DESCRIPTION:
LICK CREEK TRIBUTARY 13 7.0
END DESCRIPTION:
XS GIS Cut Line= 3
      3572107.76     10195608.06      3572892.11     10194891.64
      3573227.53     10194523.67
#Sta/Elev= 30
  3940.3  281.53  4061.6  281.35  4101.9  281.15  4201.3  280.44  4240.6  279.70
  4344.2  281.87  4380.6  280.25  4399.3  279.16  4478.7  280.88  4552.3  280.10
  4620.2  280.08  4669.9  279.32  4726.6  276.62  4795.3  277.64  4899.8  274.89
  4946.2  274.14  4988.7  271.71  4995.5  271.17  4996.2  268.29  4999.0  267.79
  5002.2  268.29  5009.7  268.72  5023.9  272.13  5137.4  274.73  5201.7  278.68
  5313.8  278.90  5351.3  280.97  5406.3  282.73  5469.8  282.48  5500.5  284.00
#Mann=15,-1,0
  3940.3    0.05       0  4061.6    0.08       0  4101.9    0.05       0
  4201.3    0.08       0  4240.6     0.1       0  4380.6    0.08       0
  4399.3     0.1       0  4552.3    0.08       0  4620.2     0.1       0
  4795.3    0.08       0  4899.8    0.05       0  4996.2    0.04       0
  5002.2    0.05       0  5201.7    0.08       0  5351.3     0.1       0
Bank Sta=4996.2,5002.2
Exp/Cntr=0.3,0.1

Type RM Length L Ch R = 1,3103,231,231,231
BEGIN DESCRIPTION:
LICK CREEK TRIBUTARY 13 5.0
END DESCRIPTION:
XS GIS Cut Line= 3
      3572719.75     10195959.62      3573542.11     10195191.64
      3574040.48     10194762.76
#Sta/Elev= 30
  3846.3  279.15  3867.7  277.79  3875.0  278.81  3881.8  277.62  3889.2  278.72
  3896.0  277.63  3903.3  278.55  3924.3  277.52  3938.5  279.21  3945.4  277.75
  3952.7  278.98  3959.5  277.64  3966.8  278.85  3973.7  277.38  3981.0  278.53
  3987.9  277.04  3995.2  278.30  4023.5  279.51  4112.8  279.69  4172.0  280.48
  4178.9  279.64  4382.7  278.57  4426.6  278.21  4622.0  277.41  4703.0  276.82
  4961.4  276.03  4964.2  275.53  4967.4  276.03  5347.3  277.05  5629.0  281.76
#Mann=8,-1,0
  3846.3     0.1       0  4112.8    0.08       0  4382.7     0.1       0
  4426.6    0.08       0  4622.0    0.15       0  4703.0     0.1       0
  4961.4    0.07       0  4967.4     0.1       0
Bank Sta=4961.4,4967.4
Exp/Cntr=0.3,0.1

Type RM Length L Ch R = 1,2872,478,478,478
BEGIN DESCRIPTION:
LICK CREEK TRIBUTARY 13 5.1
END DESCRIPTION:
XS GIS Cut Line= 3
      3572954.07     10196042.13      3573742.47     10195309.03
      3574240.85     10194880.13
#Sta/Elev= 30
  3900.2  277.62  3958.7  277.84  3991.3  279.57  4031.2  279.06  4069.0  276.67
  4098.6  276.77  4146.7  278.29  4169.7  277.42  4196.5  276.80  4217.5  277.88
  4224.9  277.00  4231.7  277.96  4238.6  277.09  4308.1  277.22  4316.7  276.44
  4323.6  277.44  4330.9  276.52  4337.7  277.49  4378.5  277.40  4446.6  276.86
  4518.4  276.78  4585.0  276.83  4658.3  276.49  4970.8  275.90  5085.1  275.17
  5087.8  274.67  5091.1  275.17  5272.4  275.80  5538.6  278.76  5634.3  280.14
#Mann=16,-1,0
  3900.2    0.08       0  3958.7     0.1       0  4031.2    0.08       0
  4098.6    0.05       0  4169.7     0.1       0  4238.6    0.05       0
  4308.1     0.1       0  4378.5    0.05       0  4446.6     0.1       0
  4518.4    0.05       0  4585.0     0.1       0  4658.3    0.05       0
  4970.8     0.1       0  5085.1    0.07       0  5091.1     0.1       0
  5538.6    0.05       0
Bank Sta=5085.1,5091.1
Exp/Cntr=0.3,0.1

Type RM Length L Ch R = 1,2394,1658,1658,1658
BEGIN DESCRIPTION:
LICK CREEK TRIBUTARY 13 3.0
END DESCRIPTION:
XS GIS Cut Line= 3
      3574019.67     10195929.39      3574225.24     10195307.78
      3574509.23     10194757.57
#Sta/Elev= 30
  4578.8  277.71  4629.1  279.31  4713.4  277.70  4766.5  278.34  4824.7  277.54
  4871.3  275.03  4888.1  272.10  4954.8  270.33  4988.6  268.43  5005.3  265.13
  5008.0  264.63  5011.3  265.13  5015.0  267.51  5029.3  268.27  5141.9  268.27
  5173.6  267.01  5205.4  268.88  5324.8  270.01  5363.5  272.16  5369.1  271.68
  5385.7  274.19  5391.3  273.50  5407.8  277.24  5413.4  275.86  5430.0  279.62
  5464.7  281.04  5540.7  281.83  5699.1  281.04  5801.0  282.36  5852.7  281.83
#Mann=6,-1,0
  4578.8    0.05       0  4954.8    0.16       0  5005.3    0.07       0
  5011.3    0.16       0  5464.7     0.1       0  5699.1    0.05       0
Bank Sta=5005.3,5011.3
Exp/Cntr=0.3,0.1

Type RM Length L Ch R = 1,736,0,0,0
BEGIN DESCRIPTION:
LICK CREEK TRIBUTARY 13 1.0
END DESCRIPTION:
XS GIS Cut Line= 3
      3574472.77     10195924.20      3574964.05     10195755.67
      3575492.73     10194915.21
#Sta/Elev= 30
  4247.2  274.05  4320.5  274.35  4391.5  272.65  4578.5  271.22  4672.9  271.54
  4783.2  267.45  4905.5  267.12  4978.5  262.70  4984.4  261.45  4990.8  258.53
  4993.5  258.03  4996.8  258.53  5007.6  263.12  5057.4  264.87  5078.6  266.67
  5115.1  271.80  5130.4  272.50  5145.7  271.67  5166.9  273.31  5195.9  273.00
  5245.3  273.44  5267.5  274.23  5297.6  273.56  5362.0  275.19  5397.7  277.76
  5428.3  276.58  5434.2  278.43  5454.4  278.09  5507.2  277.45  5759.5  278.35
#Mann=7,-1,0
  4247.2    0.05       0  4578.5    0.16       0  4990.8    0.07       0
  4996.8    0.16       0  5195.9    0.05       0  5245.3     0.1       0
  5454.4    0.05       0
Bank Sta=4990.8,4996.8
Exp/Cntr=0.3,0.1

Chan Stop Cuts=-1