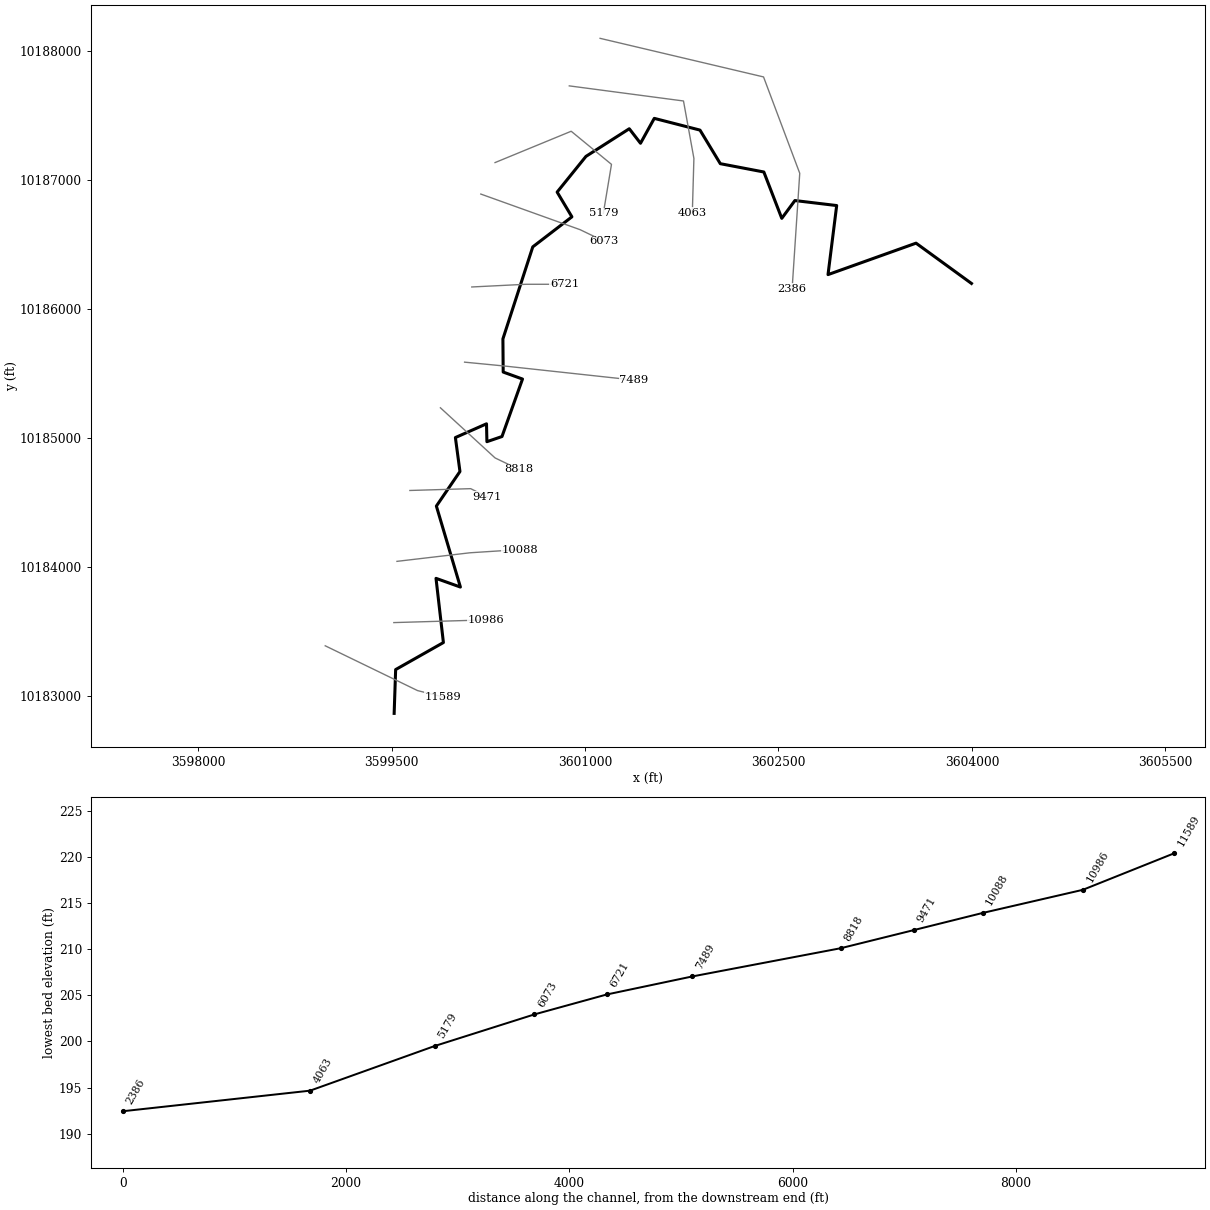
--- LICK CREEK TRIBUTARY 2.prj (project) ---

Proj Title=LICK CREEK TRIBUTARY 2 Base Level Engineering
Current Plan=p01
Default Exp/Contr=0.3,0.1
English Units
Geom File=g01
Flow File=f01
Plan File=p01
Y Axis Title=Elevation
X Axis Title(PF)=Main Channel Distance
X Axis Title(XS)=Station
BEGIN DESCRIPTION:
LICK CREEK TRIBUTARY 2
END DESCRIPTION:
DSS Export Rating Curves= 0
DSS Export Rating Curve Sorted= 0
DSS Export Volume Flow Curves= 0
DXF OffsetX= 0
DXF OffsetY= 0
DXF ScaleX= 1
DXF ScaleY= 10

--- LICK CREEK TRIBUTARY 2.p01 (plan) ---

Plan Title=Multiple Run
Short Identifier=Multiple
Geom File=g01
Flow File=f01
Subcritical Flow
K Sum by GR= 0
Std Step Tol= 0.01
Critical Tol= 0.01
Num of Std Step Trials= 20
Max Error Tol= 0.3
Flow Tol Ratio= 0.001
Split Flow NTrial= 30
Split Flow Tol= 0.02
Split Flow Ratio= 0.02
Log Output Level= 0
Friction Slope Method= 1
Unsteady Friction Slope Method= 2
Unsteady Bridges Friction Slope Method= 1
Parabolic Critical Depth
Global Vel Dist=  1 , 1 , 1
Global Log Level= 0
CheckData=True
Encroach Param= -1, 0, 0, 0
BEGIN DESCRIPTION:
Multiple Run
END DESCRIPTION:

--- LICK CREEK TRIBUTARY 2.f01 (steady flow) ---

Flow Title=Multiple
Program Version=4.10
Number of Profiles= 7
Profile Names=10-year,25-year,50-year,1pct_min,100-year,1pct_plu,500-year
River Rch & RM=LICK CREEK TRIBU,Reach-1         ,11589
     458     604     720     630     852    1152    1193
Boundary for River Rch & Prof#=LICK CREEK TRIBU,Reach-1         , 1
Up Type= 0
Dn Type= 3
Dn Slope=0.005
Boundary for River Rch & Prof#=LICK CREEK TRIBU,Reach-1         , 2
Up Type= 0
Dn Type= 3
Dn Slope=0.005
Boundary for River Rch & Prof#=LICK CREEK TRIBU,Reach-1         , 3
Up Type= 0
Dn Type= 3
Dn Slope=0.005
Boundary for River Rch & Prof#=LICK CREEK TRIBU,Reach-1         , 4
Up Type= 0
Dn Type= 3
Dn Slope=0.005
Boundary for River Rch & Prof#=LICK CREEK TRIBU,Reach-1         , 5
Up Type= 0
Dn Type= 3
Dn Slope=0.005
Boundary for River Rch & Prof#=LICK CREEK TRIBU,Reach-1         , 6
Up Type= 0
Dn Type= 3
Dn Slope=0.005
Boundary for River Rch & Prof#=LICK CREEK TRIBU,Reach-1         , 7
Up Type= 0
Dn Type= 3
Dn Slope=0.005
DSS Import GetInterval= 0
DSS Import GetPeak= 0
DSS Import FillOption= 0

--- LICK CREEK TRIBUTARY 2.g01 (geometry) ---

Geom Title=Existing Conditions
Program Version=4.10

River Reach=LICK CREEK TRIBU,Reach-1
Reach XY= 30
      3599520.27     10182862.08      3599531.86     10183201.94
       3599902.1     10183411.67      3599844.81     10183909.82
      3600034.04     10183842.11      3599847.64      10184470.5
      3600030.48      10184738.9       3599995.1     10185002.29
      3600236.31     10185108.94      3600239.46     10184970.19
      3600356.41     10185010.26      3600515.43     10185456.24
      3600365.69      10185510.5      3600363.52     10185767.66
      3600595.07     10186481.85       3600898.5     10186714.92
        3600784.     10186906.96      3601007.42     10187183.92
       3601343.3     10187398.47      3601430.45     10187285.77
      3601537.18     10187478.96      3601891.59     10187387.99
      3602049.13     10187127.35      3602386.75     10187062.89
      3602525.73     10186703.14      3602627.46      10186841.3
      3602951.42     10186802.47      3602884.24     10186266.57
      3603566.76     10186510.68      3603996.62     10186198.03

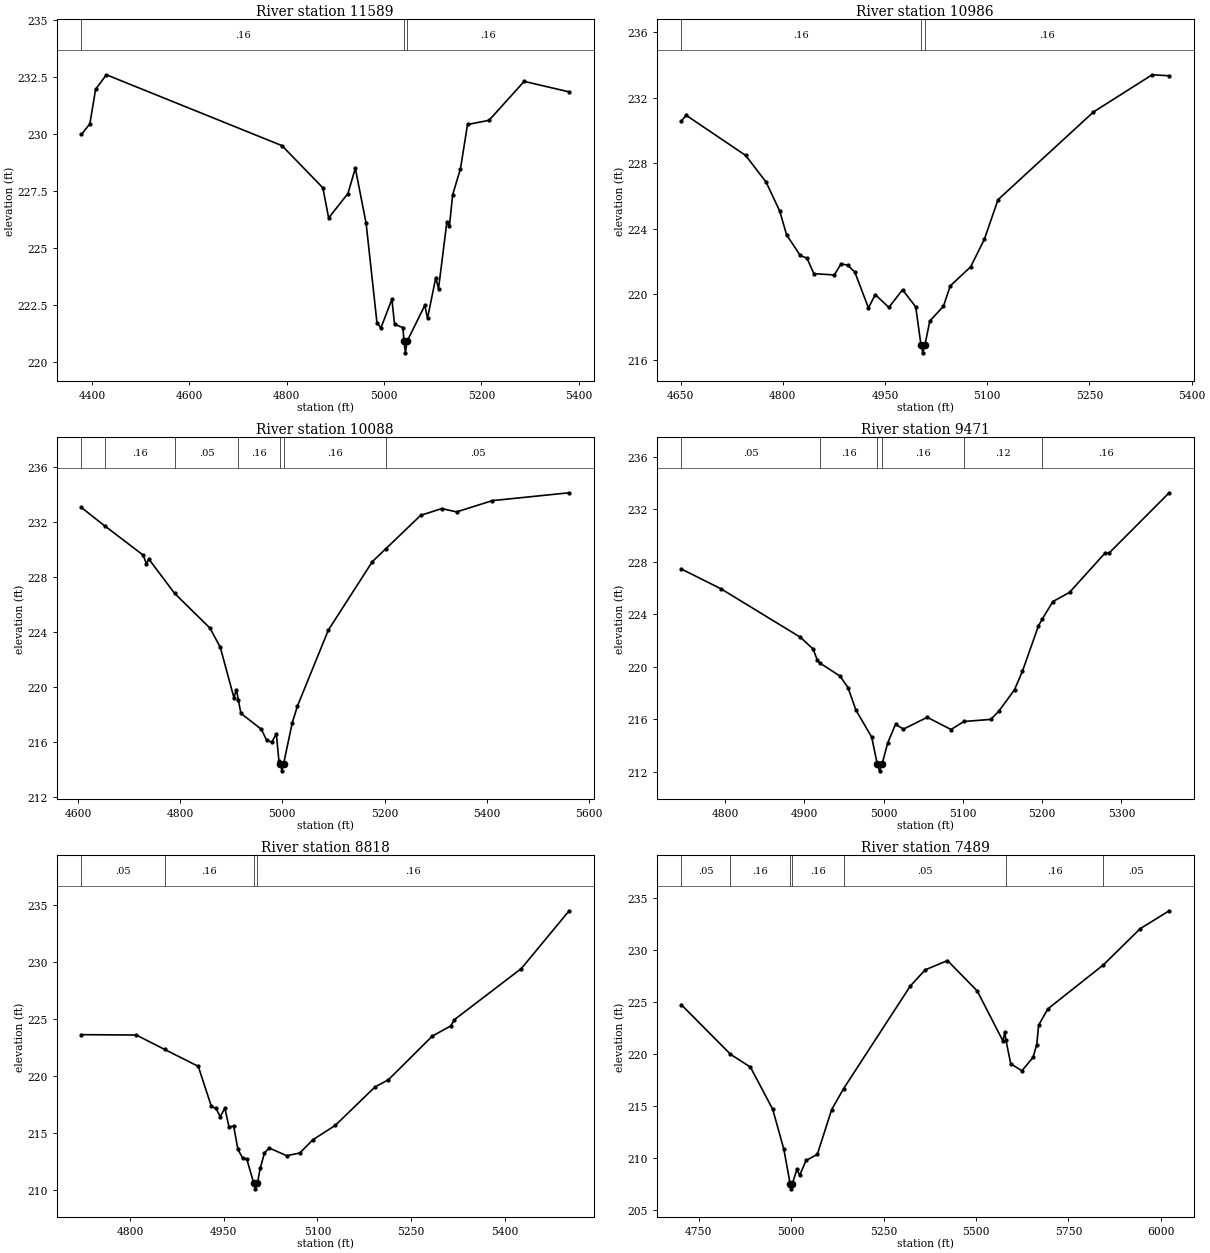
Type RM Length L Ch R = 1 ,11589   ,816,816,816
BEGIN DESCRIPTION:
LICK CREEK TRIBUTARY 2 19.0
END DESCRIPTION:
XS GIS Cut Line= 3
      3598985.85     10183386.45      3599701.83     10183038.86
      3599901.79     10182988.87
#Sta/Elev= 30
  4378.3  229.97  4395.8  230.44  4407.5  231.95  4429.7  232.59  4790.5  229.48
  4874.4  227.63  4886.3  226.31  4925.9  227.38  4941.1  228.49  4963.3  226.07
  4985.5  221.72  4993.6  221.48  5016.2  222.74  5021.7  221.64  5038.7   221.5
  5041.3  220.89    5044  220.39  5047.3  220.89  5083.8  222.47  5089.4  221.91
  5106.4  223.69    5112   223.2    5129  226.11  5134.5  225.97  5141.1  227.33
  5157.1  228.47  5171.6  230.41  5215.7  230.59  5287.9   232.3  5380.3  231.84
#Mann= 3 ,-1 , 0
  4378.3     .16       0  5041.3     .07       0  5047.3     .16       0
Bank Sta=5041.3,5047.3
XS Rating Curve= 0 ,0
Exp/Cntr=0.3,0.1

Type RM Length L Ch R = 1 ,10986   ,898,898,898
BEGIN DESCRIPTION:
LICK CREEK TRIBUTARY 2 17.0
END DESCRIPTION:
XS GIS Cut Line= 2
      3599517.85     10183566.51      3600233.15     10183587.34
#Sta/Elev= 30
  4651.3  230.58  4658.3  230.93  4745.6  228.48  4775.6  226.85  4795.6  225.08
  4805.6  223.64  4825.6  222.38  4835.6  222.21  4845.6  221.27  4875.6  221.19
  4885.7  221.88  4895.7  221.77  4905.7  221.37  4925.7  219.18  4935.7  219.99
  4955.7  219.21  4975.7  220.29  4995.1  219.24  5002.7  216.94  5005.5  216.44
  5008.7  216.94  5015.7  218.38  5035.7  219.28  5045.7  220.52  5075.7  221.69
  5095.7  223.36  5115.8  225.78  5255.8  231.13  5341.9   233.4  5366.9  233.34
#Mann= 3 ,-1 , 0
  4651.3     .16       0  5002.7     .07       0  5008.7     .16       0
Bank Sta=5002.7,5008.7
XS Rating Curve= 0 ,0
Exp/Cntr=0.3,0.1

Type RM Length L Ch R = 1 ,10088   ,617,617,617
BEGIN DESCRIPTION:
LICK CREEK TRIBUTARY 2 16.0
END DESCRIPTION:
XS GIS Cut Line= 3
      3599542.09     10184041.64      3600108.18     10184108.17
      3600491.99     10184132.96
#Sta/Elev= 30
  4606.7  233.08  4652.6  231.74  4727.5  229.62  4733.9     229  4738.9  229.32
  4789.3  226.83  4858.4  224.31  4878.6  222.91  4905.2  219.26  4910.2  219.83
    4914  219.08  4918.9  218.11  4959.1  216.95  4969.2  216.15  4979.3  216.02
  4988.3  216.61  4993.3  214.67  4996.4  214.43  4999.2  213.93  5002.4  214.43
  5019.5  217.43  5029.6  218.64    5090  224.16  5176.1  229.14  5202.2  230.07
  5270.8  232.51    5312     233    5341  232.76  5411.1  233.58  5561.3  234.15
#Mann= 7 ,-1 , 0
  4606.7     .05       0  4652.6     .16       0  4789.3     .05       0
    4914     .16       0  4996.4     .07       0  5002.4     .16       0
  5202.2     .05       0
Bank Sta=4996.4,5002.4
XS Rating Curve= 0 ,0
Exp/Cntr=0.3,0.1

Type RM Length L Ch R = 1 ,9471    ,653,653,653
BEGIN DESCRIPTION:
LICK CREEK TRIBUTARY 2 14.0
END DESCRIPTION:
XS GIS Cut Line= 3
      3599642.12     10184591.64      3600113.91     10184605.74
      3600242.08     10184541.66
#Sta/Elev= 30
  4744.9  227.45  4794.9  225.94    4895  222.25  4911.1  221.35  4916.1  220.54
  4919.7  220.28    4945  219.29    4955  218.42    4965  216.71    4985  214.63
    4992  212.57  4994.8  212.07    4998  212.57    5005  214.17    5015  215.62
    5025  215.25    5055  216.15    5085  215.22  5101.3  215.83  5135.1  215.99
  5145.1   216.6  5165.1  218.25  5175.1  219.66  5195.1  223.08  5199.9  223.62
  5213.5  224.97  5234.5  225.67  5279.2  228.66  5284.8  228.69  5360.2  233.26
#Mann= 6 ,-1 , 0
  4744.9     .05       0  4919.7     .16       0    4992     .07       0
    4998     .16       0  5101.3     .12       0  5199.9     .16       0
Bank Sta=4992,4998
XS Rating Curve= 0 ,0
Exp/Cntr=0.3,0.1

Type RM Length L Ch R = 1 ,8818    ,1329,1329,1329
BEGIN DESCRIPTION:
LICK CREEK TRIBUTARY 2 13.0
END DESCRIPTION:
XS GIS Cut Line= 3
      3599878.99     10185233.19      3600302.62     10184844.28
      3600488.61     10184754.73
#Sta/Elev= 30
  4721.8  223.65  4809.8  223.62    4855  222.36  4909.1  220.87  4930.1  217.35
  4937.5  217.17  4944.3  216.45  4951.7  217.19  4958.4  215.54  4965.8  215.63
  4972.6  213.58    4980  212.83  4986.8  212.73    4998  210.61  5000.7  210.11
    5004  210.61  5008.4  211.94  5015.2  213.26  5022.6   213.7  5050.9  213.02
  5071.9  213.26  5092.9  214.43  5128.6  215.68  5192.1  219.05  5213.7  219.69
    5284  223.52  5313.7  224.42  5319.3  224.96  5426.8  229.46  5503.3  234.53
#Mann= 4 ,-1 , 0
  4721.8     .05       0    4855     .16       0    4998     .07       0
    5004     .16       0
Bank Sta=4998,5004
XS Rating Curve= 0 ,0
Exp/Cntr=0.3,0.1

Type RM Length L Ch R = 1 ,7489    ,768,768,768
BEGIN DESCRIPTION:
LICK CREEK TRIBUTARY 2 11.0
END DESCRIPTION:
XS GIS Cut Line= 3
      3600066.48     10185587.34      3600377.46     10185557.17
      3601378.04     10185448.56
#Sta/Elev= 30
  4703.4  224.75  4836.1  219.99  4889.9  218.76  4950.2  214.71  4980.3  210.87
  4997.4  207.55  5000.2  207.05  5003.4  207.55  5015.7  208.91  5023.2  208.36
  5040.6  209.78  5070.8  210.36  5109.7  214.67    5142  216.69  5322.3  226.55
  5362.5  228.11  5422.9     229  5503.3  226.08  5572.7  221.28  5577.8  222.12
  5580.6   221.4  5593.9  219.08    5624   218.4  5654.2  219.69  5664.3  220.93
  5669.3  222.79  5694.4  224.36  5843.9  228.57  5944.1  232.07  6022.3  233.79
#Mann= 7 ,-1 , 0
  4703.4     .05       0  4836.1     .16       0  4997.4     .07       0
  5003.4     .16       0    5142     .05       0  5580.6     .16       0
  5843.9     .05       0
Bank Sta=4997.4,5003.4
XS Rating Curve= 0 ,0
Exp/Cntr=0.3,0.1

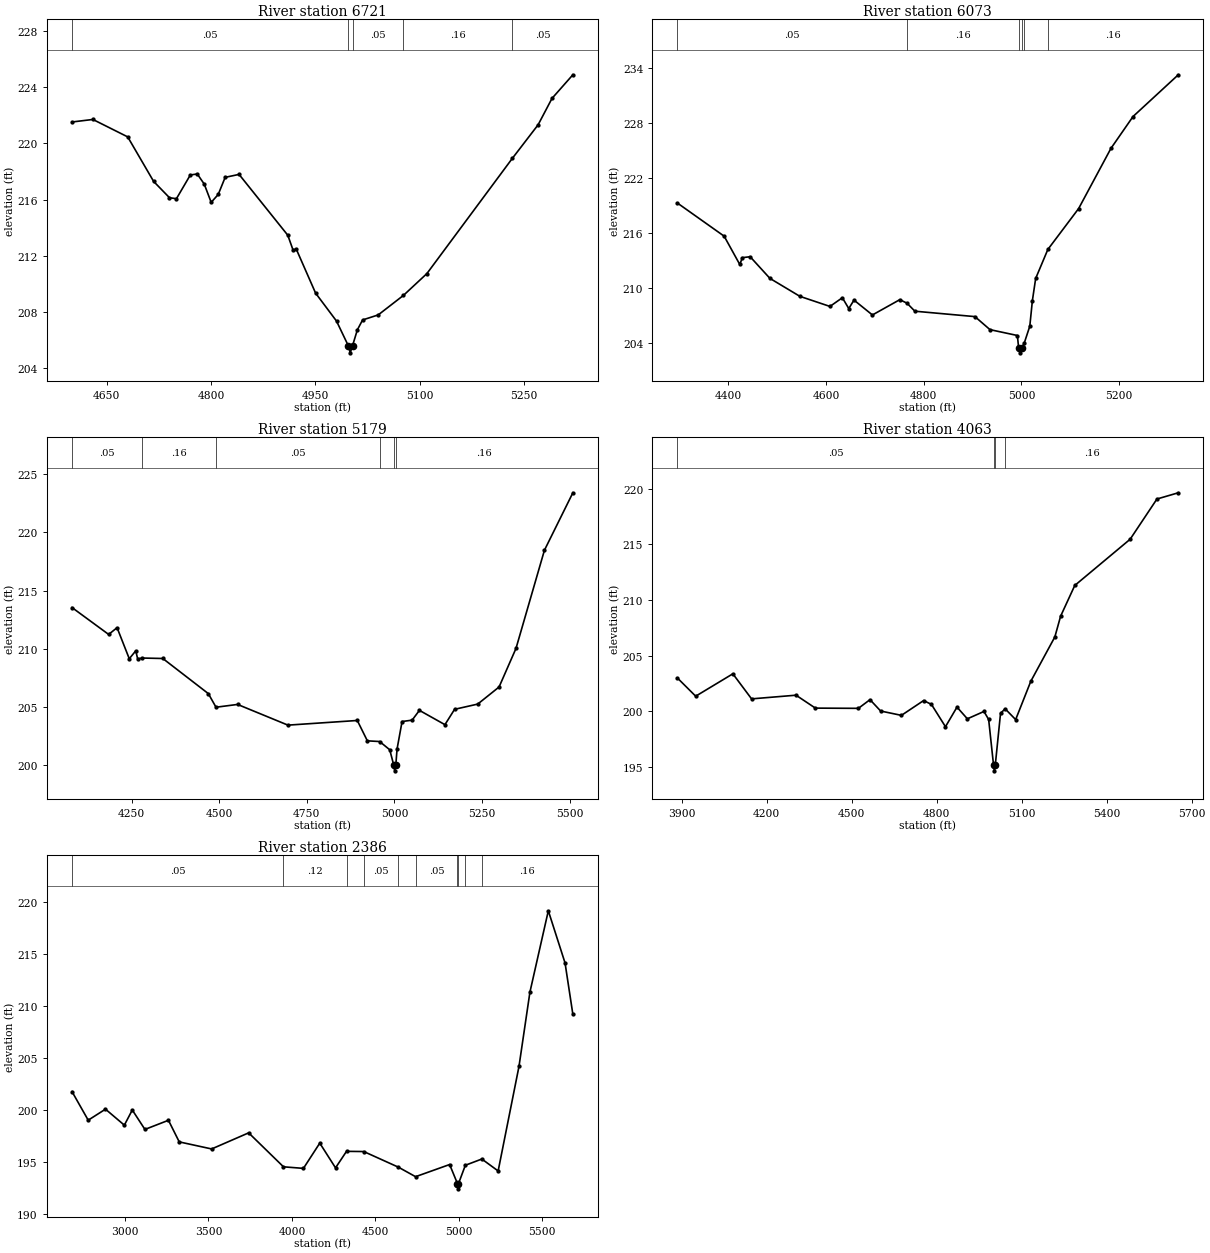
Type RM Length L Ch R = 1 ,6721    ,648,648,648
BEGIN DESCRIPTION:
LICK CREEK TRIBUTARY 2 9.0
END DESCRIPTION:
XS GIS Cut Line= 3
      3600122.11     10186170.68      3600542.11     10186191.64
      3600842.08     10186191.64
#Sta/Elev= 30
  4599.9  221.52  4629.9   221.7    4680  220.46  4717.3  217.29  4740.1  216.13
  4750.1  216.06  4770.1  217.75  4780.1  217.82  4790.1   217.1  4800.1   215.8
  4810.2  216.36  4820.2  217.58  4840.2  217.79  4910.3  213.46  4917.7  212.43
  4922.7  212.45  4950.3  209.34  4980.4  207.35  4997.4  205.59  5000.1  205.09
  5003.4  205.59  5010.4  206.73  5017.9  207.43  5040.4  207.79  5076.7  209.18
  5110.4  210.73  5233.3  218.93  5270.4  221.32  5290.4   223.2  5320.4  224.88
#Mann= 5 ,-1 , 0
  4599.9     .05       0  4997.4     .03       0  5003.4     .05       0
  5076.7     .16       0  5233.3     .05       0
Bank Sta=4997.4,5003.4
XS Rating Curve= 0 ,0
Exp/Cntr=0.3,0.1

Type RM Length L Ch R = 1 ,6073    ,894,894,894
BEGIN DESCRIPTION:
LICK CREEK TRIBUTARY 2 7.0
END DESCRIPTION:
XS GIS Cut Line= 3
       3600192.1     10186891.64      3600962.35     10186615.12
      3601148.51     10186525.48
#Sta/Elev= 30
  4296.1  219.26  4391.7  215.65  4423.6  212.57  4429.1  213.31  4444.9  213.41
  4485.3  211.05  4546.7  209.09  4608.2  207.99  4633.6  208.94  4646.7  207.76
  4657.4  208.68  4695.1  207.06  4751.2  208.73    4766  208.34    4782  207.47
  4904.9  206.88  4935.7  205.46  4991.8  204.82  4994.4  203.43  4997.1  202.93
  5000.4  203.43  5005.7  203.97  5017.2  205.84  5022.5  208.63  5029.2  211.04
  5054.1   214.2  5117.1  218.66  5183.2  225.22  5228.5   228.7  5321.1  233.25
#Mann= 6 ,-1 , 0
  4296.1     .05       0    4766     .16       0  4994.4     .07       0
  5000.4     .16       0  5005.7     .05       0  5054.1     .16       0
Bank Sta=4994.4,5000.4
XS Rating Curve= 0 ,0
Exp/Cntr=0.3,0.1

Type RM Length L Ch R = 1 ,5179    ,1116,1116,1116
BEGIN DESCRIPTION:
LICK CREEK TRIBUTARY 2 6.0
END DESCRIPTION:
XS GIS Cut Line= 4
       3600302.6     10187135.94       3600892.9     10187379.01
       3601205.4     10187122.06      3601142.11     10186741.64
#Sta/Elev= 30
  4080.2  213.54  4184.7  211.23  4208.7  211.81  4243.5  209.14    4262  209.82
  4267.4  209.13  4280.8   209.2  4339.2  209.16    4469  206.14  4490.9  204.97
  4552.4  205.21  4696.1  203.43  4893.9  203.83  4922.6  202.08  4957.7  202.02
  4986.5  201.31  4997.8     200  5000.6   199.5  5003.8     200  5007.3  201.37
  5021.6  203.74  5050.3  203.86  5071.1   204.7  5143.9  203.47  5171.4  204.79
  5237.4  205.24  5298.3  206.71  5346.6  210.03  5427.7  218.47  5508.8  223.41
#Mann= 6 ,-1 , 0
  4080.2     .05       0  4280.8     .16       0  4490.9     .05       0
  4957.7     .16       0  4997.8     .07       0  5003.8     .16       0
Bank Sta=4997.8,5003.8
XS Rating Curve= 0 ,0
Exp/Cntr=0.3,0.1

Type RM Length L Ch R = 1 ,4063    ,1677,1677,1677
BEGIN DESCRIPTION:
LICK CREEK TRIBUTARY 2 6.1
END DESCRIPTION:
XS GIS Cut Line= 4
      3600878.22     10187731.05      3601763.68     10187613.86
      3601844.39     10187168.43      3601832.22     10186746.27
#Sta/Elev= 30
  3884.7  202.99  3949.1  201.36  4080.3  203.37  4146.4  201.12  4303.3  201.45
  4371.7  200.29  4523.5  200.27  4564.5  201.05    4602  200.03  4675.4  199.64
  4753.9  200.97  4781.5  200.62  4830.9  198.62  4871.6  200.38  4908.2  199.33
  4966.8  199.99  4983.4  199.27  5000.7  195.16  5003.5  194.66  5006.7  195.16
  5025.3  199.82  5041.5  200.23  5078.7  199.26  5132.2   202.7  5217.1  206.68
  5237.4  208.54  5287.4   211.3  5482.9  215.45  5577.5  219.06  5652.9  219.62
#Mann= 4 ,-1 , 0
  3884.7     .05       0  5000.7     .03       0  5006.7     .05       0
  5041.5     .16       0
Bank Sta=5000.7,5006.7
XS Rating Curve= 0 ,0
Exp/Cntr=0.3,0.1

Type RM Length L Ch R = 1 ,2386    ,0,0,0
BEGIN DESCRIPTION:
LICK CREEK TRIBUTARY 2 1.0
END DESCRIPTION:
XS GIS Cut Line= 4
      3601116.97     10188099.97      3602384.34     10187800.49
      3602665.08      10187052.7      3602605.83     10186154.88
#Sta/Elev= 30
  2682.5  201.79  2779.5  199.04    2883   200.1    2996  198.56  3043.6  200.02
  3119.3  198.15  3260.2  199.03  3324.9  196.95  3519.1  196.27  3740.8  197.82
  3949.5  194.55    4069   194.4  4166.9  196.83  4261.3  194.45  4327.1  196.04
  4430.5  196.02  4637.4  194.52  4740.9   193.6  4944.9  194.77    4992  192.93
  4994.8  192.43    4998  192.93  5039.1   194.7  5137.8   195.3  5235.6  194.15
  5360.5  204.22    5426  211.37  5536.2   219.2  5636.4  214.18  5683.3  209.23
#Mann= 10 ,-1 , 0
  2682.5     .05       0  3949.5     .12       0  4327.1      .1       0
  4430.5     .05       0  4637.4      .1       0  4740.9     .05       0
    4992    .035       0    4998     .05       0  5039.1     .12       0
  5137.8     .16       0
Bank Sta=4992,4998
XS Rating Curve= 0 ,0
Exp/Cntr=0.3,0.1
Stream Node=LICK CREEK TRIBU,Reach-1         , 0 , 0 ,Upstream end
Stream Node=LICK CREEK TRIBU,Reach-1         , 0 , 1 ,Downstream end

Chan Stop Cuts=-1
Use User Specified Reach Order=0
Composite Channel Slope=5