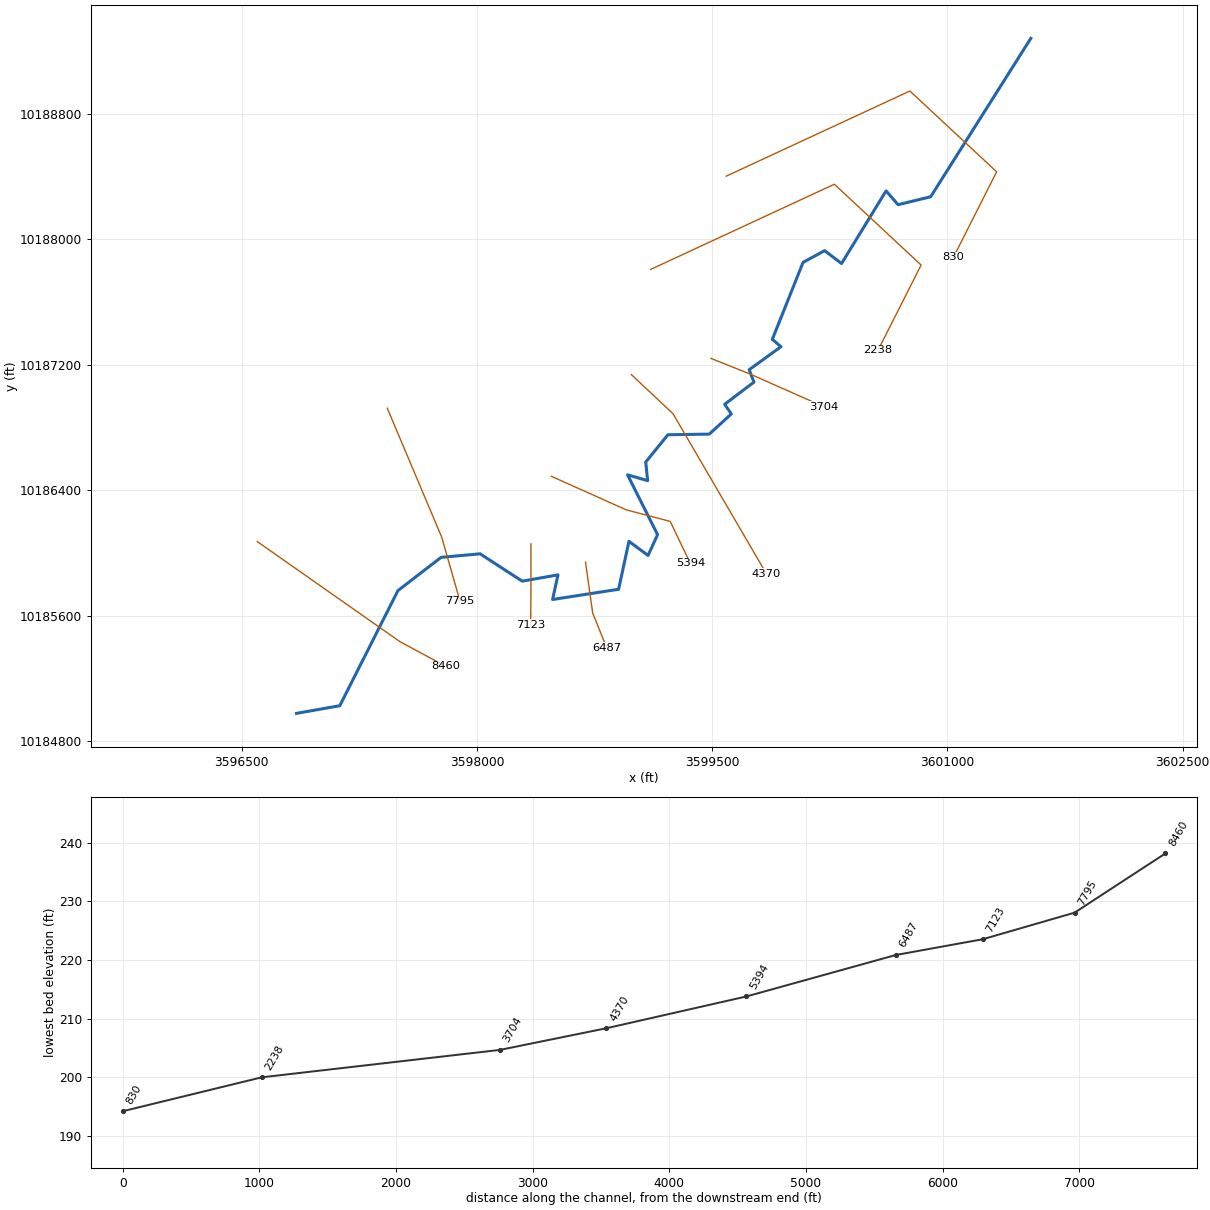
--- LICK CREEK TRIBUTARY 3.prj (project) ---

Proj Title=LICK CREEK TRIBUTARY 3 Base Level Engineering
Current Plan=p01
Default Exp/Contr=0.3,0.1
English Units
Geom File=g01
Flow File=f01
Plan File=p01
Y Axis Title=Elevation
X Axis Title(PF)=Main Channel Distance
X Axis Title(XS)=Station
BEGIN DESCRIPTION:
LICK CREEK TRIBUTARY 3
END DESCRIPTION:
DSS Export Rating Curves= 0
DSS Export Rating Curve Sorted= 0
DSS Export Volume Flow Curves= 0
DXF OffsetX= 0
DXF OffsetY= 0
DXF ScaleX= 1
DXF ScaleY= 10

--- LICK CREEK TRIBUTARY 3.p01 (plan) ---

Plan Title=Multiple Run
Short Identifier=Multiple
Geom File=g01
Flow File=f01
Subcritical Flow
K Sum by GR= 0
Std Step Tol= 0.01
Critical Tol= 0.01
Num of Std Step Trials= 20
Max Error Tol= 0.3
Flow Tol Ratio= 0.001
Split Flow NTrial= 30
Split Flow Tol= 0.02
Split Flow Ratio= 0.02
Log Output Level= 0
Friction Slope Method= 1
Unsteady Friction Slope Method= 2
Unsteady Bridges Friction Slope Method= 1
Parabolic Critical Depth
Global Vel Dist=  1 , 1 , 1
Global Log Level= 0
CheckData=True
Encroach Param= -1, 0, 0, 0
BEGIN DESCRIPTION:
Multiple Run
END DESCRIPTION:

--- LICK CREEK TRIBUTARY 3.f01 (steady flow) ---

Flow Title=Multiple
Program Version=4.10
Number of Profiles= 7
Profile Names=10-year,25-year,50-year,1pct_min,100-year,1pct_plu,500-year
River Rch & RM=LICK CREEK TRIBU,Reach-1         ,8460
     436     575     686     601     812    1098    1139
Boundary for River Rch & Prof#=LICK CREEK TRIBU,Reach-1         , 1
Up Type= 0
Dn Type= 3
Dn Slope=0.005
Boundary for River Rch & Prof#=LICK CREEK TRIBU,Reach-1         , 2
Up Type= 0
Dn Type= 3
Dn Slope=0.005
Boundary for River Rch & Prof#=LICK CREEK TRIBU,Reach-1         , 3
Up Type= 0
Dn Type= 3
Dn Slope=0.005
Boundary for River Rch & Prof#=LICK CREEK TRIBU,Reach-1         , 4
Up Type= 0
Dn Type= 3
Dn Slope=0.005
Boundary for River Rch & Prof#=LICK CREEK TRIBU,Reach-1         , 5
Up Type= 0
Dn Type= 3
Dn Slope=0.005
Boundary for River Rch & Prof#=LICK CREEK TRIBU,Reach-1         , 6
Up Type= 0
Dn Type= 3
Dn Slope=0.005
Boundary for River Rch & Prof#=LICK CREEK TRIBU,Reach-1         , 7
Up Type= 0
Dn Type= 3
Dn Slope=0.005
DSS Import GetInterval= 0
DSS Import GetPeak= 0
DSS Import FillOption= 0

--- LICK CREEK TRIBUTARY 3.g01 (geometry) ---

Geom Title=Existing Conditions
Program Version=4.10

River Reach=LICK CREEK TRIBU,Reach-1
Reach XY= 30
       3596848.5      10184977.6      3597124.85     10185026.47
      3597495.65     10185760.65      3597770.76     10185972.56
      3598019.47     10185995.34      3598288.16     10185820.91
      3598516.37      10185860.9      3598481.98       10185704.
      3598903.06     10185769.16      3598969.02     10186074.82
      3599090.69     10185984.85      3599151.66     10186117.31
      3598959.93     10186499.24      3599088.35     10186461.74
      3599075.99     10186580.46      3599217.57     10186754.65
      3599481.29     10186758.68      3599621.89     10186887.28
      3599579.57     10186949.12      3599766.21     10187090.18
      3599735.82     10187169.39      3599938.58      10187316.1
      3599883.49     10187363.34      3600079.67     10187854.23
      3600217.05     10187928.91      3600325.06      10187846.7
      3600608.75     10188309.95      3600685.57     10188221.85
      3600893.47     10188272.63      3601532.11     10189282.96

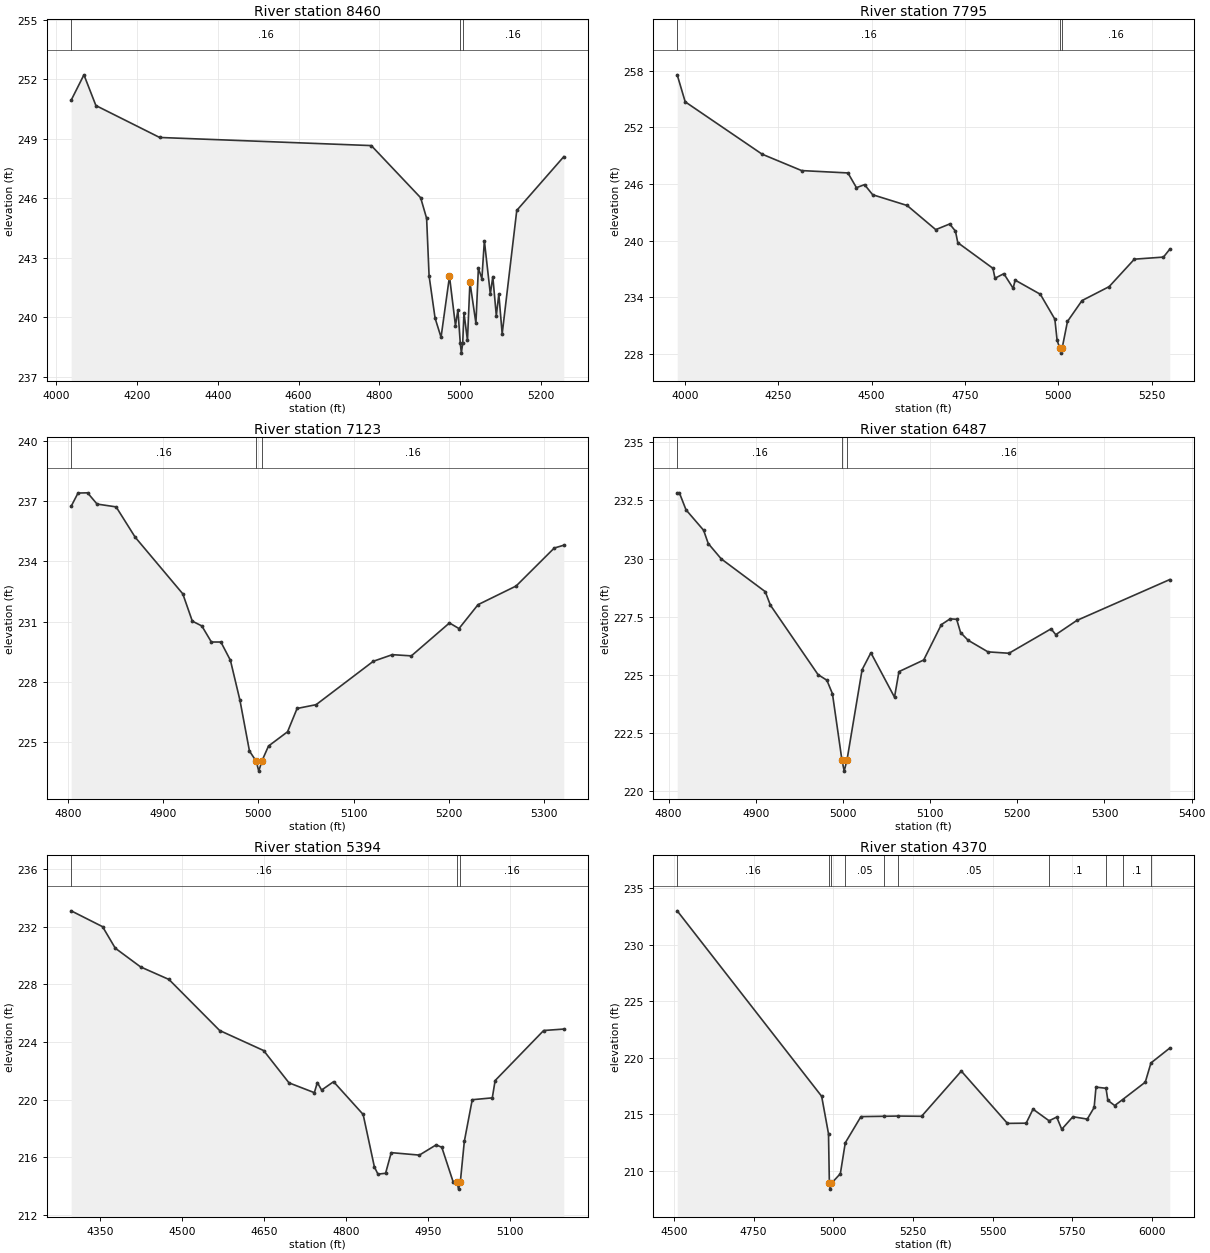
Type RM Length L Ch R = 1 ,8460    ,665,665,665
BEGIN DESCRIPTION:
LICK CREEK TRIBUTARY 3 9.0
END DESCRIPTION:
XS GIS Cut Line= 3
      3596598.78     10186073.04      3597508.57     10185435.02
        3597798.       10185279.
#Sta/Elev= 30
  4037.1  250.95  4068.7  252.23  4098.3  250.68  4256.1  249.07  4779.9  248.66
    4902  246.03  4916.8  244.99  4922.9  242.09  4937.7  239.96  4952.5  238.99
  4973.4  242.06  4988.2  239.58  4994.3  240.37  5000.1  238.69  5002.8  238.19
  5006.1  238.69  5009.2  240.23  5017.9  238.83    5024  241.77  5038.8   239.7
  5044.9  242.47  5053.6  241.95  5059.7  243.86  5074.5  241.17  5080.6  242.05
  5089.3  240.08  5095.5  241.17  5103.8  239.16  5139.9  245.39  5256.2   248.1
#Mann= 3 ,-1 , 0
  4037.1     .16       0  5000.1     .07       0  5006.1     .16       0
Bank Sta=4973.4,5024
XS Rating Curve= 0 ,0
Exp/Cntr=0.3,0.1

Type RM Length L Ch R = 1 ,7795    ,672,672,672
BEGIN DESCRIPTION:
LICK CREEK TRIBUTARY 3 7.0
END DESCRIPTION:
XS GIS Cut Line= 3
      3597427.73     10186923.77      3597774.39     10186102.29
       3597892.1     10185691.66
#Sta/Elev= 30
  3979.5  257.58  4000.9  254.72  4206.8  249.17  4312.6  247.43  4436.6  247.18
  4459.4  245.62  4481.1  245.94  4502.8  244.87  4595.1  243.73  4671.7  241.17
    4709  241.77  4724.5  241.01  4730.7  239.79  4824.8  237.07  4830.3  236.02
    4854   236.5    4879  234.95  4884.2  235.82  4951.7  234.32  4990.6  231.68
  4996.6  229.45    5004  228.58  5006.8  228.08    5010  228.58  5024.4  231.44
  5063.3  233.65    5136  235.13  5203.5  238.04  5281.4  238.26  5298.3   239.1
#Mann= 3 ,-1 , 0
  3979.5     .16       0    5004     .07       0    5010     .16       0
Bank Sta=5004,5010
XS Rating Curve= 0 ,0
Exp/Cntr=0.3,0.1

Type RM Length L Ch R = 1 ,7123    ,636,636,636
BEGIN DESCRIPTION:
LICK CREEK TRIBUTARY 3 6.0
END DESCRIPTION:
XS GIS Cut Line= 3
      3598344.01     10186058.85      3598344.01     10185733.39
      3598342.11     10185541.66
#Sta/Elev= 30
  4803.4  236.74  4810.6   237.4  4820.6  237.41  4830.6  236.85  4850.6  236.71
  4870.6   235.2  4920.6  232.38  4930.6  231.02  4940.6  230.78  4950.6  229.98
  4960.6  229.98  4970.6  229.07  4980.6  227.08  4990.6  224.55  4997.6  224.05
  5000.4  223.55  5003.6  224.05  5010.6   224.8  5030.6  225.51  5040.6  226.67
  5060.6  226.86  5120.6  229.02  5140.6  229.35  5160.6  229.29  5200.6  230.93
  5210.6  230.65  5230.6  231.84  5270.6  232.77  5310.6  234.66  5320.6   234.8
#Mann= 3 ,-1 , 0
  4803.4     .16       0  4997.6     .07       0  5003.6     .16       0
Bank Sta=4997.6,5003.6
XS Rating Curve= 0 ,0
Exp/Cntr=0.3,0.1

Type RM Length L Ch R = 1 ,6487    ,1093,1093,1093
BEGIN DESCRIPTION:
LICK CREEK TRIBUTARY 3 5.0
END DESCRIPTION:
XS GIS Cut Line= 3
       3598692.1     10185941.67      3598737.69     10185617.62
      3598826.81     10185397.09
#Sta/Elev= 30
  4809.8  232.83  4812.3  232.83  4819.9   232.1  4840.1  231.22  4845.4  230.65
  4860.3  229.99  4910.8  228.58  4916.7     228  4971.4  225.01  4981.5  224.77
  4987.9  224.19  4998.7  221.36  5001.4  220.86  5004.7  221.36  5021.9  225.22
    5032  225.95  5059.1  224.04  5064.2  225.14  5092.6  225.64  5112.8  227.16
  5122.9  227.41  5130.4  227.39  5134.9  226.82  5143.5  226.49  5166.3  225.99
  5190.4  225.93  5238.7  226.98  5244.1  226.73  5268.2  227.34  5374.9   229.1
#Mann= 3 ,-1 , 0
  4809.8     .16       0  4998.7     .07       0  5004.7     .16       0
Bank Sta=4998.7,5004.7
XS Rating Curve= 0 ,0
Exp/Cntr=0.3,0.1

Type RM Length L Ch R = 1 ,5394    ,1024,1024,1024
BEGIN DESCRIPTION:
LICK CREEK TRIBUTARY 3 4.0
END DESCRIPTION:
XS GIS Cut Line= 4
       3598473.7     10186489.75      3598951.61     10186275.88
        3599232.       10186202.        3599360.       10185935.
#Sta/Elev= 30
  4297.4  233.09  4354.9  231.99  4378.1   230.5  4424.5   229.2  4476.4  228.33
  4569.2  224.79  4649.7   223.4  4696.1  221.16  4742.5  220.48    4748  221.18
  4755.8  220.66  4777.7  221.24  4831.8  218.97  4852.4  215.33  4858.9  214.83
  4872.9  214.89  4883.2  216.32  4934.7  216.15  4965.5  216.86  4975.8  216.69
  4996.4  214.31  5003.7  214.29  5006.4  213.79  5009.7  214.29    5017   217.1
  5031.5  219.99  5068.2  220.12  5073.4  221.32  5162.2  224.79    5199  224.89
#Mann= 3 ,-1 , 0
  4297.4     .16       0  5003.7     .07       0  5009.7     .16       0
Bank Sta=5003.7,5009.7
XS Rating Curve= 0 ,0
Exp/Cntr=0.3,0.1

Type RM Length L Ch R = 1 ,4370    ,780,780,780
BEGIN DESCRIPTION:
LICK CREEK TRIBUTARY 3 3.0
END DESCRIPTION:
XS GIS Cut Line= 3
      3598984.17     10187138.44      3599249.98      10186888.9
      3599845.25     10185869.11
#Sta/Elev= 30
  4510.5  233.01  4963.7  216.59  4985.2  213.27  4987.9  208.87  4990.7  208.37
  4993.9  208.87  5022.4  209.74  5037.8  212.47  5086.9  214.79  5158.8  214.82
  5202.1  214.84  5277.2  214.82  5401.9  218.82  5546.6  214.19  5605.3  214.21
  5626.8  215.45  5677.3  214.42  5701.2  214.75  5716.9  213.67  5751.9  214.78
  5797.1  214.57  5818.6   215.6  5824.4   217.4  5855.8   217.3  5861.6  216.23
  5883.1  215.77    5908   216.3    5979  217.84  5996.8  219.54  6055.9  220.86
#Mann= 10 ,-1 , 0
  4510.5     .16       0  4987.9     .07       0  4993.9     .16       0
  5037.8     .05       0  5158.8     .16       0  5202.1     .05       0
  5677.3      .1       0  5855.8     .05       0    5908      .1       0
  5996.8     .05       0
Bank Sta=4987.9,4993.9
XS Rating Curve= 0 ,0
Exp/Cntr=0.3,0.1

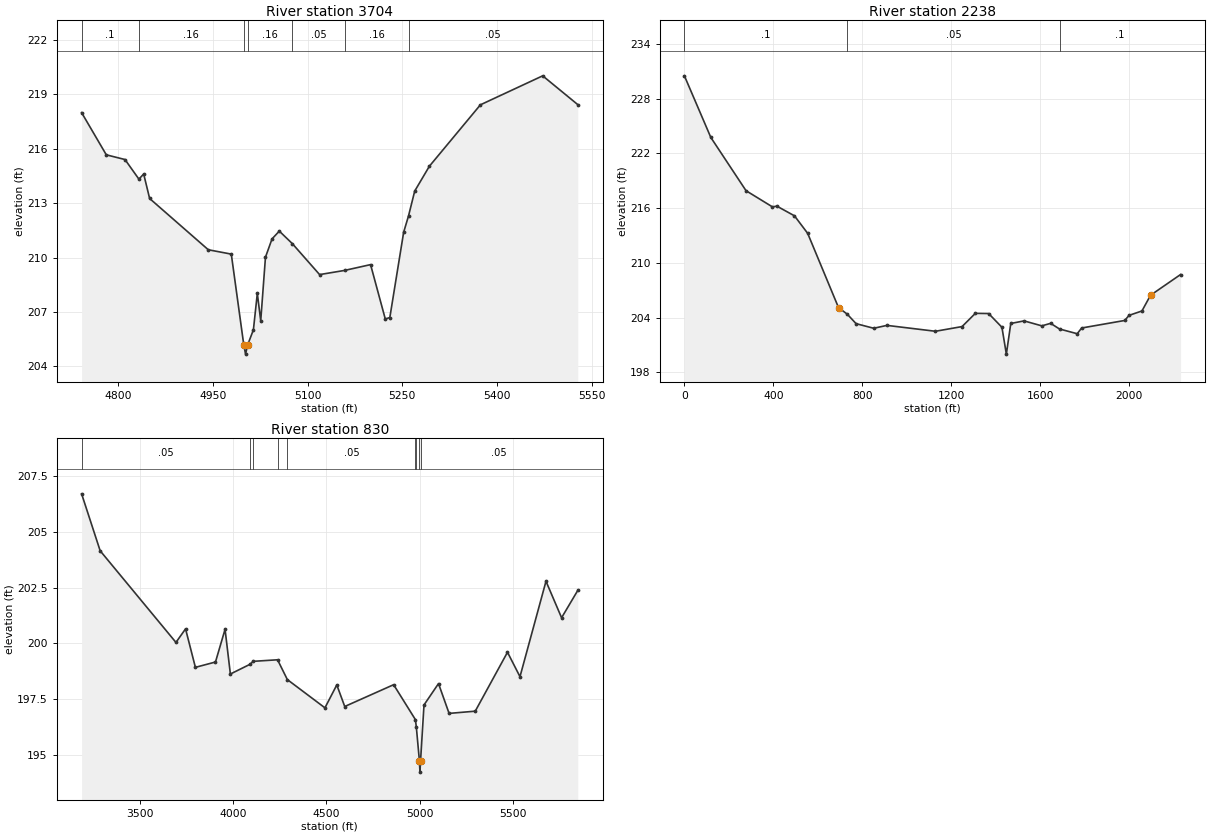
Type RM Length L Ch R = 1 ,3704    ,1742,1742,1742
BEGIN DESCRIPTION:
LICK CREEK TRIBUTARY 3 2.0
END DESCRIPTION:
XS GIS Cut Line= 3
       3599492.1     10187241.65      3599742.11     10187141.64
      3600214.16     10186932.45
#Sta/Elev= 30
  4742.3     218  4781.4  215.67    4811  215.41    4833  214.33  4840.6  214.61
    4850  213.26  4942.9  210.43  4979.3  210.19  4999.1  205.17  5001.9  204.67
  5005.1  205.17  5014.3  206.01  5020.5  208.02  5025.9  206.51  5033.4  210.02
  5043.8  211.03  5055.3  211.46  5075.9  210.77  5119.1  209.06  5158.7  209.29
  5199.8  209.61  5223.1  206.61  5230.3  206.69  5252.2   211.4  5259.9   212.3
  5269.7  213.67  5292.9  215.04  5373.7  218.43  5472.3  220.03  5527.9  218.44
#Mann= 7 ,-1 , 0
  4742.3      .1       0    4833     .16       0  4999.1     .07       0
  5005.1     .16       0  5075.9     .05       0  5158.7     .16       0
  5259.9     .05       0
Bank Sta=4999.1,5005.1
XS Rating Curve= 0 ,0
Exp/Cntr=0.3,0.1

Type RM Length L Ch R = 1 ,2238    ,1018,1018,1018
BEGIN DESCRIPTION:
LICK CREEK TRIBUTARY 3 1.1
END DESCRIPTION:
XS GIS Cut Line= 4
      3599107.42     10187809.17      3600279.08     10188352.43
      3600832.42     10187837.06      3600557.08     10187292.68
#Sta/Elev= 30
       0230.5081118.7727223.7539277.1362217.9148395.9089216.1395415.7043216.2233
494.8861215.1599554.2725 213.239692.8406205.1048732.4315204.3739772.0223203.3377
851.2042202.8341910.5905203.14951128.928202.50431248.407203.01971308.146204.4704
1367.885204.44931427.624 202.9431447.537199.9988 1467.45203.3599 1527.19203.6418
1606.842203.09891646.668203.37321686.494202.75431766.146202.23611786.059 202.863
1979.841203.6897 1999.16204.24922057.116204.72912095.754 206.4532230.986 208.728
#Mann= 3 ,-1 , 0
       0      .1       0732.4315     .05       01686.494      .1       0
Bank Sta=692.8406,2095.754
XS Rating Curve= 0 ,0
Exp/Cntr=0.3,0.1

Type RM Length L Ch R = 1 ,830     ,0,0,0
BEGIN DESCRIPTION:
LICK CREEK TRIBUTARY 3 1.0
END DESCRIPTION:
XS GIS Cut Line= 4
      3599589.15     10188403.77      3600760.85     10188947.05
      3601314.19     10188431.68      3601038.83     10187887.25
#Sta/Elev= 30
  3189.3  206.72  3288.7  204.16  3694.7  200.04  3746.1  200.65  3798.8  198.92
  3906.4  199.16  3957.7  200.63  3986.2  198.62  4092.1  199.06    4108  199.19
  4238.9  199.26  4291.3  198.37  4492.7   197.1  4556.2  198.13  4598.7  197.16
  4860.6  198.14  4977.3  196.57  4982.3  196.23  4998.8  194.71  5001.6  194.21
  5004.8  194.71  5023.3  197.23    5101  198.19  5157.7  196.85  5297.8  196.95
  5470.5   199.6  5537.4   198.5  5676.7  202.79  5760.2  201.15  5847.1  202.38
#Mann= 9 ,-1 , 0
  3189.3     .05       0  4092.1      .1       0    4108     .05       0
  4238.9      .1       0  4291.3     .05       0  4977.3      .1       0
  4982.3     .05       0  4998.8     .03       0  5004.8     .05       0
Bank Sta=4998.8,5004.8
XS Rating Curve= 0 ,0
Exp/Cntr=0.3,0.1

Chan Stop Cuts=-1
Use User Specified Reach Order=0
Composite Channel Slope=5