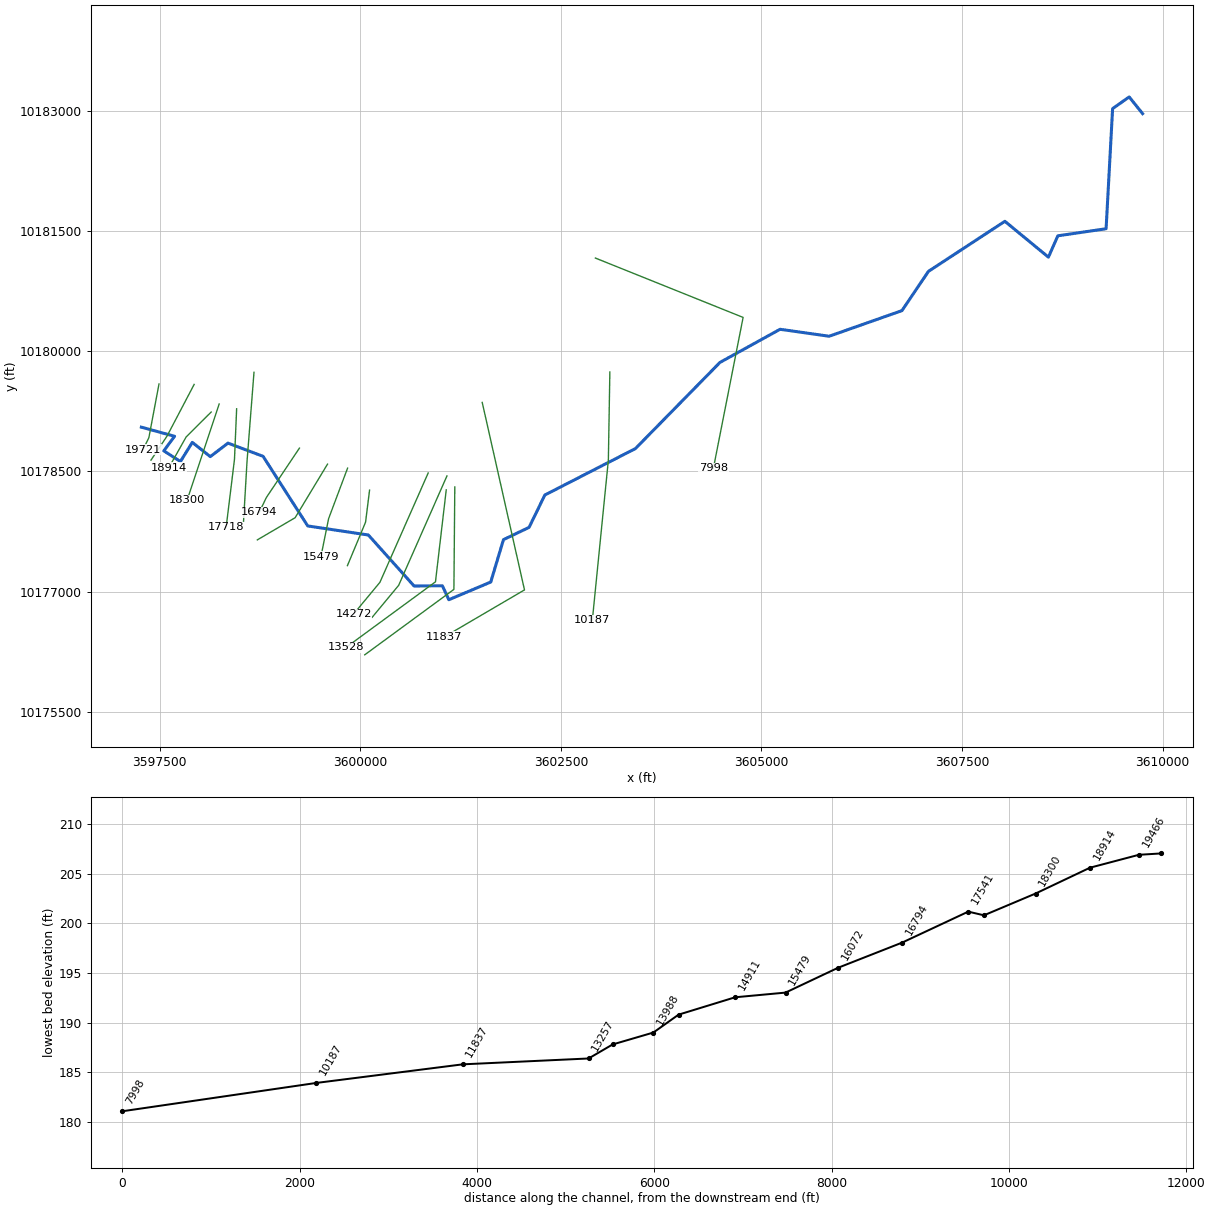
--- NAVASOTA TRIB 29.prj (project) ---

Proj Title=NAVASOTA TRIB 29 Base Level Engineering
Current Plan=p01
Default Exp/Contr=0.3,0.1
English Units
Geom File=g01
Flow File=f01
Plan File=p01
Y Axis Title=Elevation
X Axis Title(PF)=Main Channel Distance
X Axis Title(XS)=Station
BEGIN DESCRIPTION:
NAVASOTA TRIB 29
END DESCRIPTION:
DSS Export Rating Curves= 0
DSS Export Rating Curve Sorted= 0
DSS Export Volume Flow Curves= 0
DXF OffsetX= 0
DXF OffsetY= 0
DXF ScaleX= 1
DXF ScaleY= 10

--- NAVASOTA TRIB 29.p01 (plan) ---

Plan Title=Multiple Run
Short Identifier=Multiple
Geom File=g01
Flow File=f01
Subcritical Flow
K Sum by GR= 0
Std Step Tol= 0.01
Critical Tol= 0.01
Num of Std Step Trials= 20
Max Error Tol= 0.3
Flow Tol Ratio= 0.001
Split Flow NTrial= 30
Split Flow Tol= 0.02
Split Flow Ratio= 0.02
Log Output Level= 0
Friction Slope Method= 1
Unsteady Friction Slope Method= 2
Unsteady Bridges Friction Slope Method= 1
Parabolic Critical Depth
Global Vel Dist=  1 , 1 , 1
Global Log Level= 0
CheckData=True
Encroach Param= -1, 0, 0, 0
BEGIN DESCRIPTION:
Multiple Run
END DESCRIPTION:

--- NAVASOTA TRIB 29.f01 (steady flow) ---

Flow Title=Multiple
Number of Profiles=7
Profile Names=10-year,25-year,50-year,1pct_min,100-year,1pct_plu,500-year
River Rch & RM= NAVASOTA TRIB 29,Reach-1,19721
     602     812     983     873    1181    1597    1704
River Rch & RM= NAVASOTA TRIB 29,Reach-1,16072
    1009    1391    1708    1535    2076    2807    3072
Boundary for River Rch & Prof#=NAVASOTA TRIB 29,Reach-1,1
Up Type=0
Dn Type=3
Dn Slope=0.005
Boundary for River Rch & Prof#=NAVASOTA TRIB 29,Reach-1,2
Up Type=0
Dn Type=3
Dn Slope=0.005
Boundary for River Rch & Prof#=NAVASOTA TRIB 29,Reach-1,3
Up Type=0
Dn Type=3
Dn Slope=0.005
Boundary for River Rch & Prof#=NAVASOTA TRIB 29,Reach-1,4
Up Type=0
Dn Type=3
Dn Slope=0.005
Boundary for River Rch & Prof#=NAVASOTA TRIB 29,Reach-1,5
Up Type=0
Dn Type=3
Dn Slope=0.005
Boundary for River Rch & Prof#=NAVASOTA TRIB 29,Reach-1,6
Up Type=0
Dn Type=3
Dn Slope=0.005
Boundary for River Rch & Prof#=NAVASOTA TRIB 29,Reach-1,7
Up Type=0
Dn Type=3
Dn Slope=0.005

--- NAVASOTA TRIB 29.g01 (geometry) ---

Geom Title=Existing Conditions
Program Version=4.10

River Reach=NAVASOTA TRIB 29,Reach-1
Reach XY= 30
      3597272.11     10179052.96      3597685.77     10178939.52
      3597552.04     10178757.31      3597759.07     10178624.07
      3597907.08     10178862.78      3598131.47     10178685.27
      3598351.52     10178853.67      3598789.02     10178689.17
       3599345.6     10177820.66      3600101.02     10177707.75
      3600670.81     10177071.72      3601023.67     10177074.33
      3601103.62     10176900.37      3601626.28     10177120.94
      3601784.87     10177649.59       3602104.4      10177803.5
       3602300.5     10178206.36      3603429.66     10178785.96
      3604483.12      10179860.5      3605231.81     10180273.74
      3605843.79     10180186.94      3606750.69      10180506.4
       3607081.4     10180996.45      3608033.55     10181620.71
      3608576.05     10181173.47      3608693.72     10181439.77
      3609295.02     10181527.79      3609376.13     10183026.03
      3609582.73     10183171.95      3609749.81      10182963.7

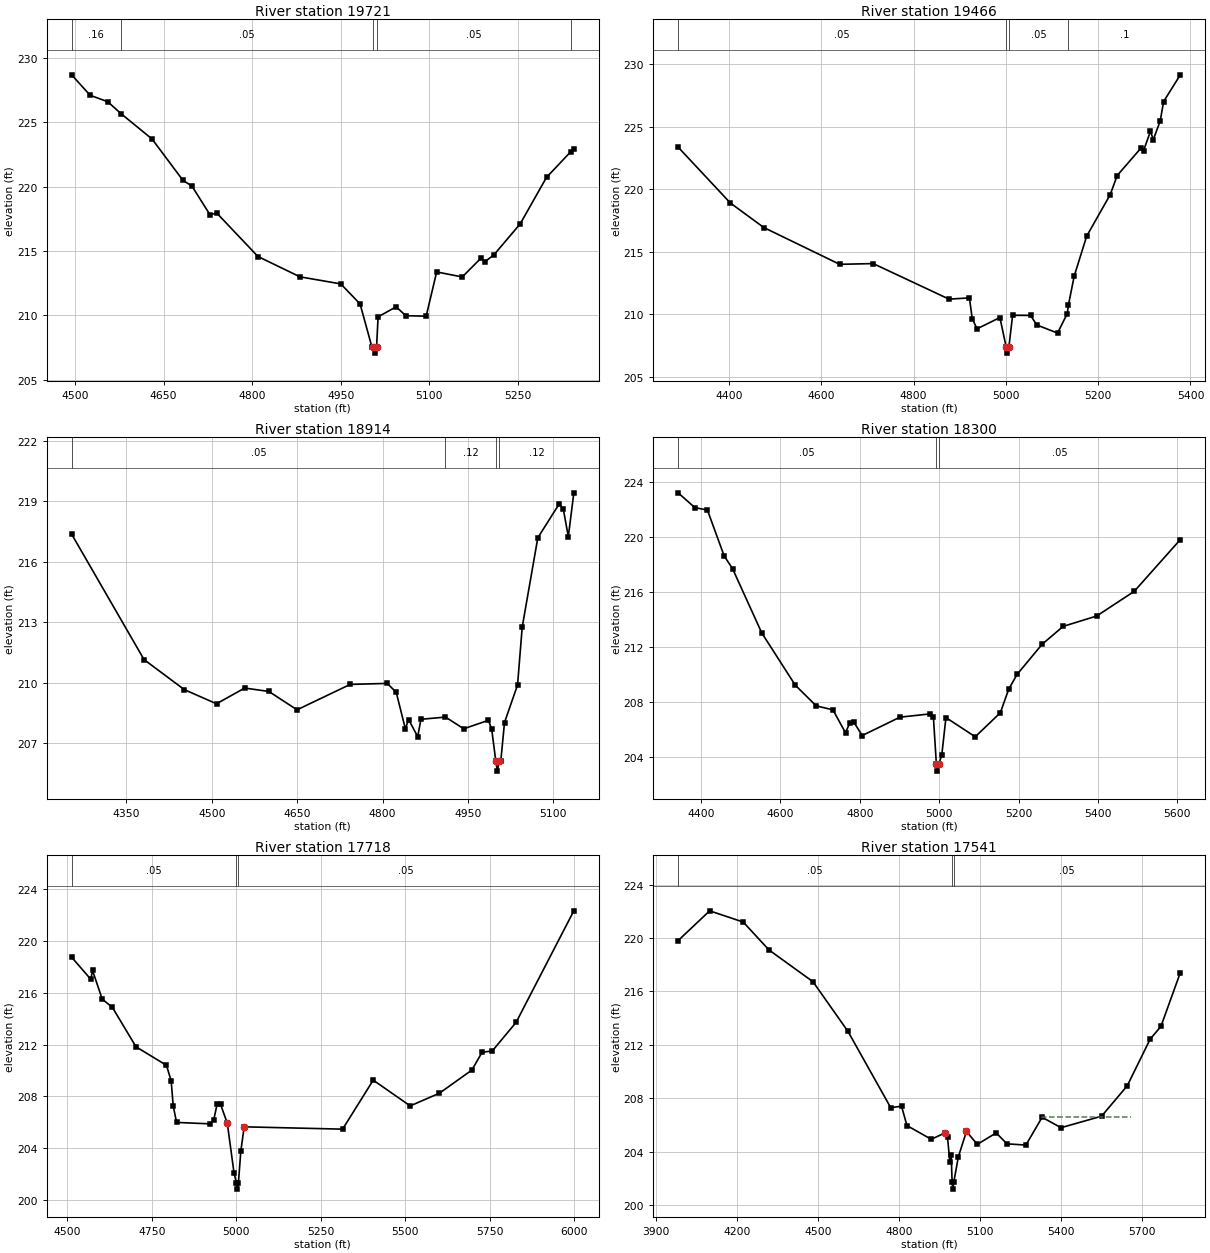
Type RM Length L Ch R = 1 ,19721   ,255,255,255
BEGIN DESCRIPTION:
NAVASOTA TRIB 29 33.0
END DESCRIPTION:
XS GIS Cut Line= 3
      3597492.11     10179591.68      3597365.83      10178921.9
      3597292.03     10178769.96
#Sta/Elev= 30
  4494.4  228.68  4525.7  227.09  4555.5  226.59  4577.8  225.67  4630.6  223.69
    4683  220.47    4698  220.04  4728.5  217.82  4740.5  217.92  4809.9  214.56
  4881.1  212.98  4950.2  212.43  4982.9  210.87  5002.7  207.56  5004.8  207.55
  5007.5  207.05  5010.8  207.55  5013.4  209.87    5044  210.65  5060.2  209.96
  5094.8  209.92  5112.6  213.36  5155.9  212.97  5187.4  214.42  5194.4  214.16
  5209.6  214.69  5254.1   217.1  5298.6  220.71  5339.4  222.69  5344.9  222.88
#Mann= 5 ,-1 , 0
  4494.4     .16       0  4577.8     .05       0  5004.8     .03       0
  5010.8     .05       0  5339.4      .1       0
Bank Sta=5004.8,5010.8
XS Rating Curve= 0 ,0
Exp/Cntr=0.3,0.1

Type RM Length L Ch R = 1 ,19466   ,552,552,552
BEGIN DESCRIPTION:
NAVASOTA TRIB 29 32.0
END DESCRIPTION:
XS GIS Cut Line= 3
      3597930.08     10179585.99      3597592.11     10178941.64
      3597392.08     10178641.61
#Sta/Elev= 30
  4289.8  223.36  4402.9   218.9  4475.4  216.94  4639.9     214  4712.5  214.06
  4876.9  211.22    4921  211.32  4927.1  209.67  4937.4  208.85  4987.1  209.75
  5000.6  207.41  5003.3  206.91  5006.6  207.41  5014.6  209.93  5053.5  209.92
    5067  209.16    5112  208.51  5133.1  210.07  5135.6  210.76  5148.1  213.06
  5175.1  216.25  5226.2  219.57  5241.2  221.09  5292.3  223.26  5298.3  223.07
  5313.4  224.63  5319.4  223.95  5334.4  225.44  5341.9     227    5378  229.13
#Mann= 4 ,-1 , 0
  4289.8     .05       0  5000.6     .03       0  5006.6     .05       0
  5135.6      .1       0
Bank Sta=5000.6,5006.6
XS Rating Curve= 0 ,0
Exp/Cntr=0.3,0.1

Type RM Length L Ch R = 1 ,18914   ,614,614,614
BEGIN DESCRIPTION:
NAVASOTA TRIB 29 31.0
END DESCRIPTION:
XS GIS Cut Line= 3
      3598142.08     10179241.62      3597830.24     10178930.58
      3597613.87     10178545.45
#Sta/Elev= 30
  4253.9  217.36  4381.1  211.14  4451.9  209.65  4508.4  208.95  4557.9  209.73
  4600.4  209.56  4649.8  208.65  4743.2  209.91  4808.2  209.96  4824.1  209.52
  4840.1  207.71  4845.8  208.17  4861.8  207.32  4867.5  208.18  4910.6  208.29
  4942.7  207.71  4986.1  208.13  4991.8  207.69    4999  206.11  5001.8  205.61
    5005  206.11  5007.8  206.12  5014.3  208.02  5037.2  209.88  5045.4  212.75
  5072.8  217.18  5110.4  218.86  5117.5  218.62  5126.4  217.24  5136.1  219.41
#Mann= 4 ,-1 , 0
  4253.9     .05       0  4910.6     .12       0    4999     .07       0
    5005     .12       0
Bank Sta=4999,5005
XS Rating Curve= 0 ,0
Exp/Cntr=0.3,0.1

Type RM Length L Ch R = 1 ,18300   ,582,582,582
BEGIN DESCRIPTION:
NAVASOTA TRIB 29 30.0
END DESCRIPTION:
XS GIS Cut Line= 3
       3598242.1     10179341.63      3598042.11     10178741.64
       3597842.1     10178141.64
#Sta/Elev= 30
  4342.4  223.18  4384.5  222.11  4416.2  221.93  4458.3  218.61  4479.4  217.69
  4553.2  213.02  4637.5  209.24  4690.2  207.74  4732.4  207.45    4764  205.79
  4774.6  206.49  4785.1  206.55  4806.2  205.59  4901.1  206.92  4977.5  207.16
  4985.4  206.93  4992.9  203.51  4995.7  203.01  4998.9  203.51  5006.5  204.18
    5017  206.89  5090.8   205.5    5154  207.24  5175.1  208.95  5196.2  210.02
  5259.4  212.21  5312.2   213.5  5396.5  214.25  5491.3  216.04  5607.3  219.79
#Mann= 3 ,-1 , 0
  4342.4     .05       0  4992.9     .03       0  4998.9     .05       0
Bank Sta=4992.9,4998.9
XS Rating Curve= 0 ,0
Exp/Cntr=0.3,0.1

Type RM Length L Ch R = 1 ,17718   ,177,177,177
BEGIN DESCRIPTION:
NAVASOTA TRIB 29 29.0
END DESCRIPTION:
XS GIS Cut Line= 3
      3598459.57      10179282.1      3598432.82     10178652.59
      3598328.66     10177801.92
#Sta/Elev= 30
  4512.5  218.76  4569.3  217.05  4574.3  217.74    4603  215.52  4633.1  214.88
  4703.1  211.83  4793.2   210.4  4807.2   209.2  4813.2  207.26  4823.2  205.98
  4923.3  205.87  4933.3  206.18  4943.3   207.4  4953.4  207.38  4973.4  205.92
  4993.4  202.06  5000.4  201.32  5003.2  200.82  5006.4  201.32  5013.4  203.75
  5023.4  205.64  5314.8  205.46  5405.5  209.25    5515  207.26  5601.5  208.24
  5697.6  210.03  5727.9  211.41  5758.1  211.51  5828.6  213.72  5999.6  222.35
#Mann= 3 ,-1 , 0
  4512.5     .05       0  5000.4     .03       0  5006.4     .05       0
Bank Sta=4973.4,5023.4
XS Rating Curve= 0 ,0
Exp/Cntr=0.3,0.1

Type RM Length L Ch R = 1 ,17541   ,747,747,747
BEGIN DESCRIPTION:
NAVASOTA TRIB 29 28.0
END DESCRIPTION:
XS GIS Cut Line= 3
      3598675.88     10179737.65      3598589.07     10178626.55
      3598545.67       10177880.
#Sta/Elev= 30
  3981.2   219.8  4098.2  222.03  4222.6  221.19  4318.2   219.1  4481.4  216.72
  4610.8  213.01  4769.6  207.29  4809.7   207.4  4829.8  205.95  4920.1  204.92
  4970.2   205.4  4980.2  205.07  4988.9  203.23  4993.9  203.73  4997.3  201.69
  5000.1  201.19  5003.3  201.69  5020.4  203.61  5050.5  205.51  5090.6  204.54
  5160.7   205.4  5200.8  204.58  5270.9  204.49    5331  206.57  5401.1  205.79
  5551.4  206.65  5646.5  208.92  5731.7  212.42  5771.7  213.38  5843.5   217.4
#Mann= 3 ,-1 , 0
  3981.2     .05       0  4997.3     .03       0  5003.3     .05       0
#XS Ineff= 1 ,-1
 5329.55 5660.51   206.6
Permanent Ineff=
       F
Bank Sta=4970.2,5050.5
XS Rating Curve= 0 ,0
Exp/Cntr=0.3,0.1

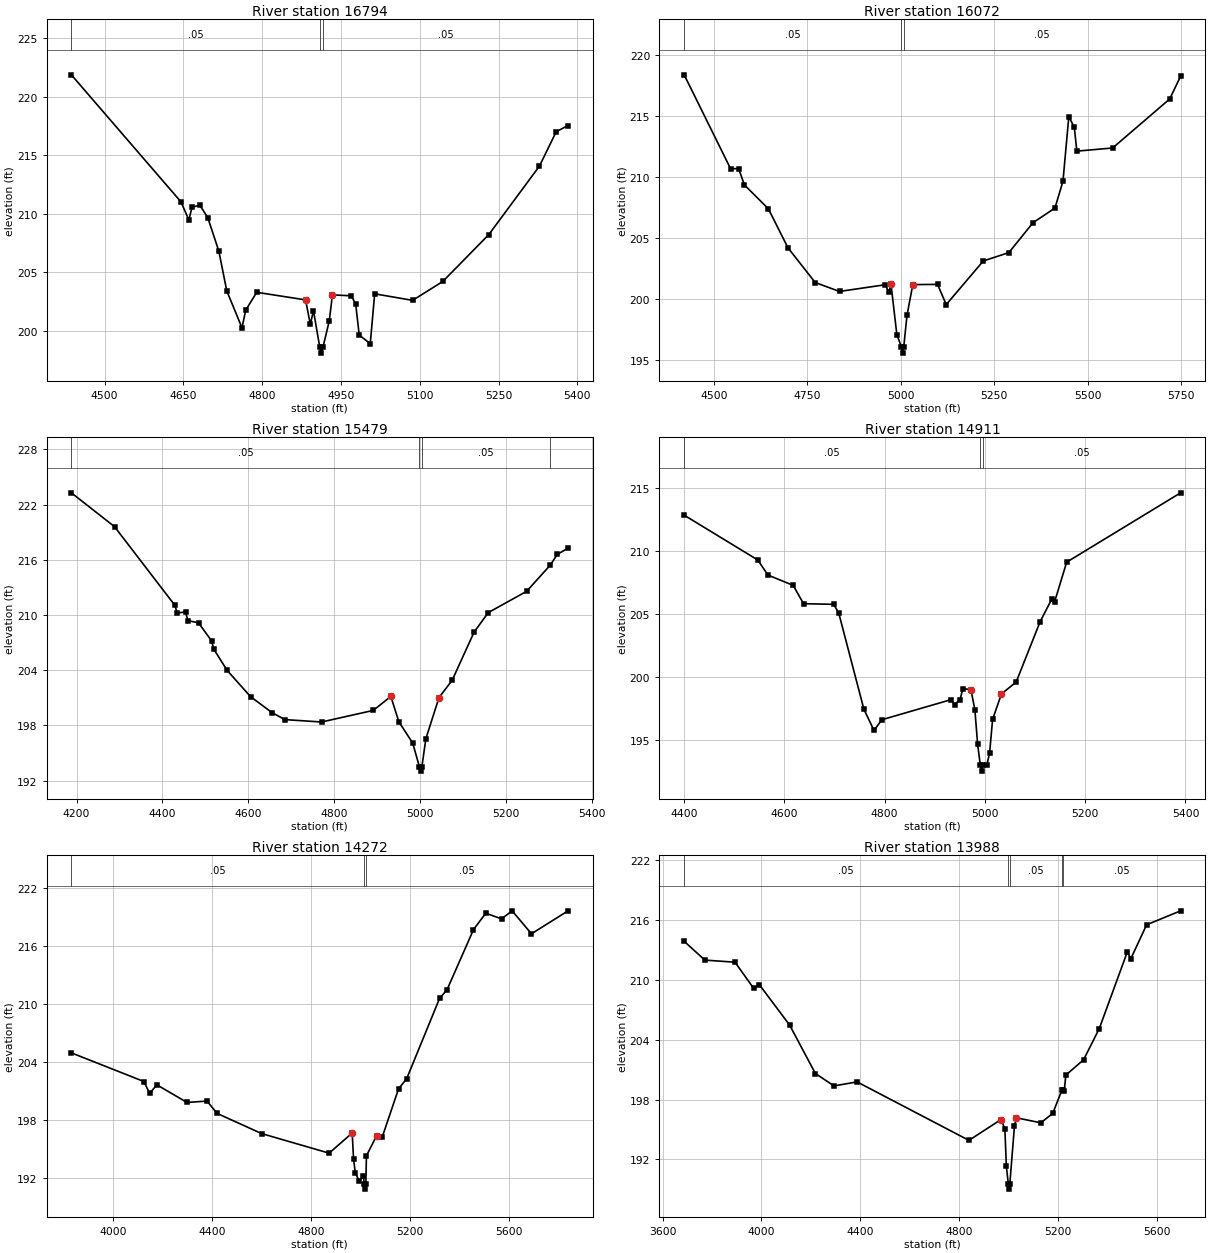
Type RM Length L Ch R = 1 ,16794   ,722,722,722
BEGIN DESCRIPTION:
NAVASOTA TRIB 29 27.0
END DESCRIPTION:
XS GIS Cut Line= 3
      3599242.09     10178791.62      3598829.23     10178174.14
      3598742.11     10177991.66
#Sta/Elev= 30
  4436.8  221.86  4645.5     211  4660.5  209.45  4666.5  210.55  4681.5  210.71
  4696.5  209.65  4717.6  206.78  4732.6   203.4  4761.6  200.23  4768.6  201.73
  4789.6  203.27  4882.7  202.62  4891.7  200.53  4897.7   201.7  4909.7  198.57
  4912.5  198.07  4915.7  198.57  4927.7  200.81  4933.8  203.05  4969.8  202.97
  4978.1  202.25  4984.8  199.61  5005.8  198.88  5014.2  203.14  5086.4  202.58
    5144   204.2  5231.6  208.21  5327.9  214.06  5359.7  216.99  5381.8  217.52
#Mann= 3 ,-1 , 0
  4436.8     .05       0  4909.7     .03       0  4915.7     .05       0
Bank Sta=4882.7,4933.8
XS Rating Curve= 0 ,0
Exp/Cntr=0.3,0.1

Type RM Length L Ch R = 1 ,16072   ,593,593,593
BEGIN DESCRIPTION:
NAVASOTA TRIB 29 26.0
END DESCRIPTION:
XS GIS Cut Line= 3
      3599592.09     10178591.61      3599188.74     10177923.63
      3598717.05     10177646.68
#Sta/Elev= 30
  4420.9  218.37  4545.1  210.66  4566.4  210.68  4581.9  209.34    4646  207.38
  4698.4  204.18  4771.3  201.33  4836.2   200.6  4958.5  201.15  4968.1  200.54
    4974  201.17  4989.5  197.06  5001.9  196.04  5004.7  195.54  5007.9  196.04
  5016.7  198.65  5032.2  201.16  5098.4  201.18  5121.5  199.52  5220.7   203.1
  5289.2  203.79  5353.6  206.24  5412.2  207.44  5433.7  209.64  5449.3  214.94
    5464  214.06  5470.8  212.11  5566.6  212.37  5719.1  216.39  5748.2  218.25
#Mann= 3 ,-1 , 0
  4420.9     .05       0  5001.9     .03       0  5007.9     .05       0
Bank Sta=4974,5032.2
XS Rating Curve= 0 ,0
Exp/Cntr=0.3,0.1

Type RM Length L Ch R = 1 ,15479   ,568,568,568
BEGIN DESCRIPTION:
NAVASOTA TRIB 29 24.0
END DESCRIPTION:
XS GIS Cut Line= 3
      3599842.11     10178541.65      3599605.41     10177910.61
      3599509.92     10177437.52
#Sta/Elev= 30
    4188  223.29  4288.6  219.61  4429.2  211.06  4434.5  210.22  4454.1  210.35
  4459.4  209.41  4484.4  209.15  4514.6  207.21  4519.9  206.29  4551.1  203.98
  4605.4  201.14  4655.2  199.41  4685.5  198.64  4770.9  198.38  4891.5  199.64
  4932.3  201.16  4951.1   198.4  4983.3  196.09  4998.8  193.54  5001.6  193.04
  5004.8  193.54  5013.9  196.55  5044.6  201.04  5075.2  202.91  5126.2  208.14
  5159.3  210.27  5248.6  212.58  5304.2  215.45    5320  216.59  5344.6  217.26
#Mann= 4 ,-1 , 0
    4188     .05       0  4998.8     .03       0  5004.8     .05       0
  5304.2     .16       0
Bank Sta=4932.3,5044.6
XS Rating Curve= 0 ,0
Exp/Cntr=0.3,0.1

Type RM Length L Ch R = 1 ,14911   ,639,639,639
BEGIN DESCRIPTION:
NAVASOTA TRIB 29 23.0
END DESCRIPTION:
XS GIS Cut Line= 3
      3600116.06     10178267.32      3600066.06     10177867.34
      3599840.19     10177325.64
#Sta/Elev= 30
  4400.3  212.84  4547.1  209.29  4567.3   208.1  4617.7  207.28  4638.3  205.83
  4698.3  205.78  4708.4  205.11  4758.7  197.47  4778.9  195.79  4794.5  196.64
  4932.4  198.23  4939.6  197.84  4950.4  198.23  4956.2  199.11  4972.1  199.02
    4980  197.45  4985.5   194.7  4990.8  193.07  4993.5  192.57  4996.8  193.07
  5003.9  193.07  5009.3  193.97  5015.4  196.67  5033.1  198.69  5062.3  199.62
    5110  204.39  5133.8  206.23  5139.2     206  5163.1  209.12  5390.3  214.61
#Mann= 3 ,-1 , 0
  4400.3     .05       0  4990.8     .03       0  4996.8     .05       0
Bank Sta=4972.1,5033.1
XS Rating Curve= 0 ,0
Exp/Cntr=0.3,0.1

Type RM Length L Ch R = 1 ,14272   ,284,284,284
BEGIN DESCRIPTION:
NAVASOTA TRIB 29 22.1
END DESCRIPTION:
XS GIS Cut Line= 3
      3600846.83     10178481.84      3600245.13     10177117.51
      3599916.15      10176720.4
#Sta/Elev= 30
  3832.4  204.95  4125.7  201.98    4149  200.74  4177.8  201.64  4299.8  199.81
  4380.7  199.95  4421.9  198.67  4601.5  196.58  4874.5  194.55  4967.7  196.64
  4973.2  193.95  4980.2   192.5  4996.5  191.66    5013  192.18  5016.8  191.32
  5019.6  190.82  5022.8  191.32  5025.3  194.28  5066.5  196.36  5089.5  196.25
  5155.1  201.22  5187.9  202.27  5321.1  210.61  5351.2   211.5    5458  217.73
  5507.5  219.43  5571.3  218.85  5614.3  219.68  5692.4   217.3  5839.2  219.66
#Mann= 3 ,-1 , 0
  3832.4     .05       0  5016.8     .03       0  5022.8     .05       0
Bank Sta=4967.7,5066.5
XS Rating Curve= 0 ,0
Exp/Cntr=0.3,0.1

Type RM Length L Ch R = 1 ,13988   ,460,460,460
BEGIN DESCRIPTION:
NAVASOTA TRIB 29 22.0
END DESCRIPTION:
XS GIS Cut Line= 3
       3601080.4     10178444.27      3600478.67     10177079.88
      3600148.71     10176681.59
#Sta/Elev= 30
  3687.6  213.86  3771.3  211.98  3893.3  211.77  3968.8  209.14  3992.1   209.5
  4114.2  205.47  4218.4  200.61  4293.8  199.37  4387.1  199.77  4839.6  193.91
  4969.2  195.99    4985  195.07  4991.1  191.31    4999  189.52  5001.7  189.02
    5005  189.52  5023.8  195.34  5031.6  196.17  5130.4  195.67  5178.8  196.61
  5216.2  198.98  5220.4     199  5225.1  198.81  5231.6  200.45  5303.3  201.98
  5367.1  205.12  5480.4   212.8  5494.7  212.12  5558.5  215.52    5696  216.92
#Mann= 5 ,-1 , 0
  3687.6     .05       0    4999    .035       0    5005     .05       0
  5216.2     .12       0  5220.4     .05       0
Bank Sta=4969.2,5031.6
XS Rating Curve= 0 ,0
Exp/Cntr=0.3,0.1

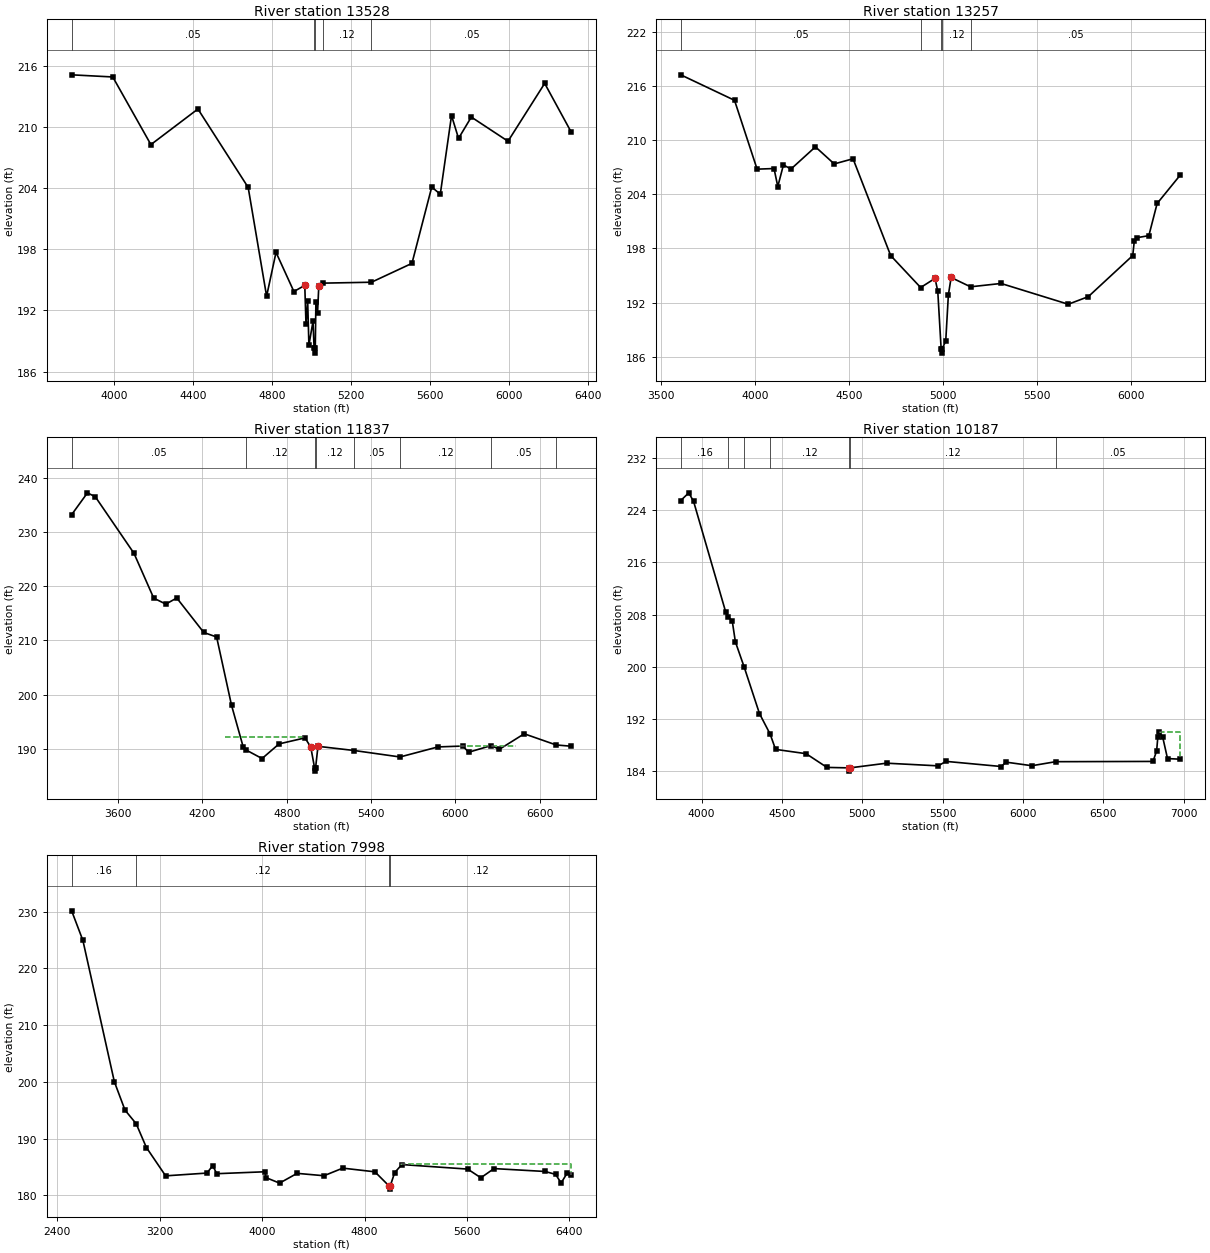
Type RM Length L Ch R = 1 ,13528   ,271,271,271
BEGIN DESCRIPTION:
NAVASOTA TRIB 29 21.1
END DESCRIPTION:
XS GIS Cut Line= 3
      3601071.71     10178270.63      3600937.47     10177123.62
      3599826.74     10176307.93
#Sta/Elev= 30
  3783.3   215.1  3991.8  214.89    4185  208.26  4423.4  211.75  4678.2  204.06
  4771.6   193.4  4819.3   197.7  4909.9  193.86  4965.1  194.46  4971.3  190.63
  4979.8   192.9    4986   188.6  5006.8  190.94  5012.3  188.32    5015  187.82
  5018.3  188.32  5021.5  192.88  5029.9   191.8  5036.1  194.39  5055.3  194.68
  5303.1  194.77  5508.4  196.62  5608.7   204.1    5652   203.4    5709  211.11
  5744.5  208.87  5809.3  210.96  5995.3  208.59  6181.2  214.26  6316.2  209.47
#Mann= 5 ,-1 , 0
  3783.3     .05       0  5012.3     .03       0  5018.3     .05       0
  5055.3     .12       0  5303.1     .05       0
#XS Ineff= 1 ,-1
 4686.36 4822.73  197.44
Permanent Ineff=
       F
Bank Sta=4965.1,5036.1
XS Rating Curve= 0 ,0
Exp/Cntr=0.3,0.1

Type RM Length L Ch R = 1 ,13257   ,1420,1420,1420
BEGIN DESCRIPTION:
NAVASOTA TRIB 29 21.0
END DESCRIPTION:
XS GIS Cut Line= 3
      3601178.33     10178307.29       3601167.2     10177029.32
      3600056.62     10176213.74
#Sta/Elev= 30
  3606.2  217.21  3891.9  214.39  4011.9  206.77  4101.9  206.84  4121.9  204.85
  4151.9  207.24  4191.9  206.78  4321.9  209.24  4421.9  207.35  4521.9  207.92
  4721.9  197.21  4881.2  193.67  4957.5  194.68  4972.2  193.28  4990.1  186.91
  4992.8  186.41  4996.1  186.91  5014.6  187.75  5028.6  192.85  5043.2  194.78
  5146.5  193.75  5308.6  194.12  5665.9  191.82  5772.4  192.66  6008.6  197.21
    6017  198.84  6031.7  199.19  6094.2  199.41  6138.2  202.97  6262.1  206.14
#Mann= 5 ,-1 , 0
  3606.2     .05       0  4881.2     .12       0  4990.1     .07       0
  4996.1     .12       0  5146.5     .05       0
Bank Sta=4957.5,5043.2
XS Rating Curve= 0 ,0
Exp/Cntr=0.3,0.1

Type RM Length L Ch R = 1 ,11837   ,1650,1650,1650
BEGIN DESCRIPTION:
NAVASOTA TRIB 29 17.0
END DESCRIPTION:
XS GIS Cut Line= 3
      3601520.07     10179361.39      3602046.87      10177022.8
      3601047.97     10176437.16
#Sta/Elev= 30
    3270  233.28  3382.5  237.32  3438.7  236.58  3713.6  226.12    3854  217.83
  3940.1  216.73    4018  217.86  4209.9  211.48  4301.5  210.64  4407.6     198
  4489.9  190.36  4509.1  189.76  4624.8  188.15  4745.8  190.86  4930.3  191.97
  4971.3  190.27  4999.1  186.32  5001.8  185.82  5005.1  186.32  5022.6  190.41
  5281.8  189.63  5606.4  188.44  5876.3   190.3  6052.2  190.46  6095.2  189.32
  6253.6  190.54  6314.1  189.87    6490  192.73  6717.6  190.66  6825.1  190.43
#Mann= 8 ,-1 , 0
    3270     .05       0  4509.1     .12       0  4999.1     .07       0
  5005.1     .12       0  5281.8     .05       0  5606.4     .12       0
  6253.6     .05       0  6717.6     .12       0
#XS Ineff= 2 ,-1
 4363.64 4922.73  192.17 6029.55 6429.55  190.51
Permanent Ineff=
       F       F
Bank Sta=4971.3,5022.6
XS Rating Curve= 0 ,0
Exp/Cntr=0.3,0.1

Type RM Length L Ch R = 1 ,10187   ,2189,2189,2189
BEGIN DESCRIPTION:
NAVASOTA TRIB 29 16.0
END DESCRIPTION:
XS GIS Cut Line= 3
      3603110.73     10179741.54      3603092.11     10178641.64
      3602892.11     10176641.67
#Sta/Elev= 30
  3870.8  225.52  3920.7   226.7  3950.7  225.37  4150.7  208.37  4167.7   207.6
  4190.7  207.08  4210.7  203.81  4266.1  199.89  4360.8  192.78    4427  189.64
  4460.8  187.29  4650.8  186.63  4780.8  184.52  4917.8  184.45  4920.6  183.95
  4923.8  184.45  5151.8  185.17  5473.3  184.76  5521.1  185.45  5865.3  184.66
  5895.4  185.33  6056.2  184.78  6204.5   185.4    6810  185.44  6832.6  187.05
  6840.1  189.17  6850.2  189.93  6870.3  189.19  6900.4  185.88  6980.8  185.78
#Mann= 7 ,-1 , 0
  3870.8     .16       0  4167.7     .05       0  4266.1     .16       0
    4427     .12       0  4917.8     .07       0  4923.8     .12       0
  6204.5     .05       0
#XS Ineff= 1 ,-1
 6852.84 7013.92  190.01
Permanent Ineff=
       F
Bank Sta=4917.8,4923.8
XS Rating Curve= 0 ,0
Exp/Cntr=0.3,0.1

Type RM Length L Ch R = 1 ,7998    ,0,0,0
BEGIN DESCRIPTION:
NAVASOTA TRIB 29 1.0
END DESCRIPTION:
XS GIS Cut Line= 3
      3602930.61      10181162.1      3604771.41     10180421.78
      3604401.26     10178541.04
#Sta/Elev= 30
  2513.4  230.14  2601.2  224.92  2846.7  200.03    2930  195.02  3017.3  192.62
    3097  188.43  3247.1  183.44  3569.6  183.93  3614.4  185.23  3646.7  183.82
  4023.7  184.16  4029.1  183.14  4136.6  182.16  4273.7  183.88  4483.3  183.46
  4630.1   184.8    4881  184.15    4994   181.6  4996.8   181.1    5000   181.6
  5035.2  184.01  5091.6  185.43  5605.4  184.63  5708.1   183.1  5810.8  184.72
  6209.9  184.21  6291.4   183.7  6334.8  182.19    6381  183.89  6414.3  183.55
#Mann= 4 ,-1 , 0
  2513.4     .16       0  3017.3     .12       0    4994     .07       0
    5000     .12       0
#XS Ineff= 1 ,-1
 5085.23 6426.14  185.56
Permanent Ineff=
       F
Bank Sta=4994,5000
XS Rating Curve= 0 ,0
Exp/Cntr=0.3,0.1

Chan Stop Cuts=-1
Use User Specified Reach Order=0
Composite Channel Slope=5