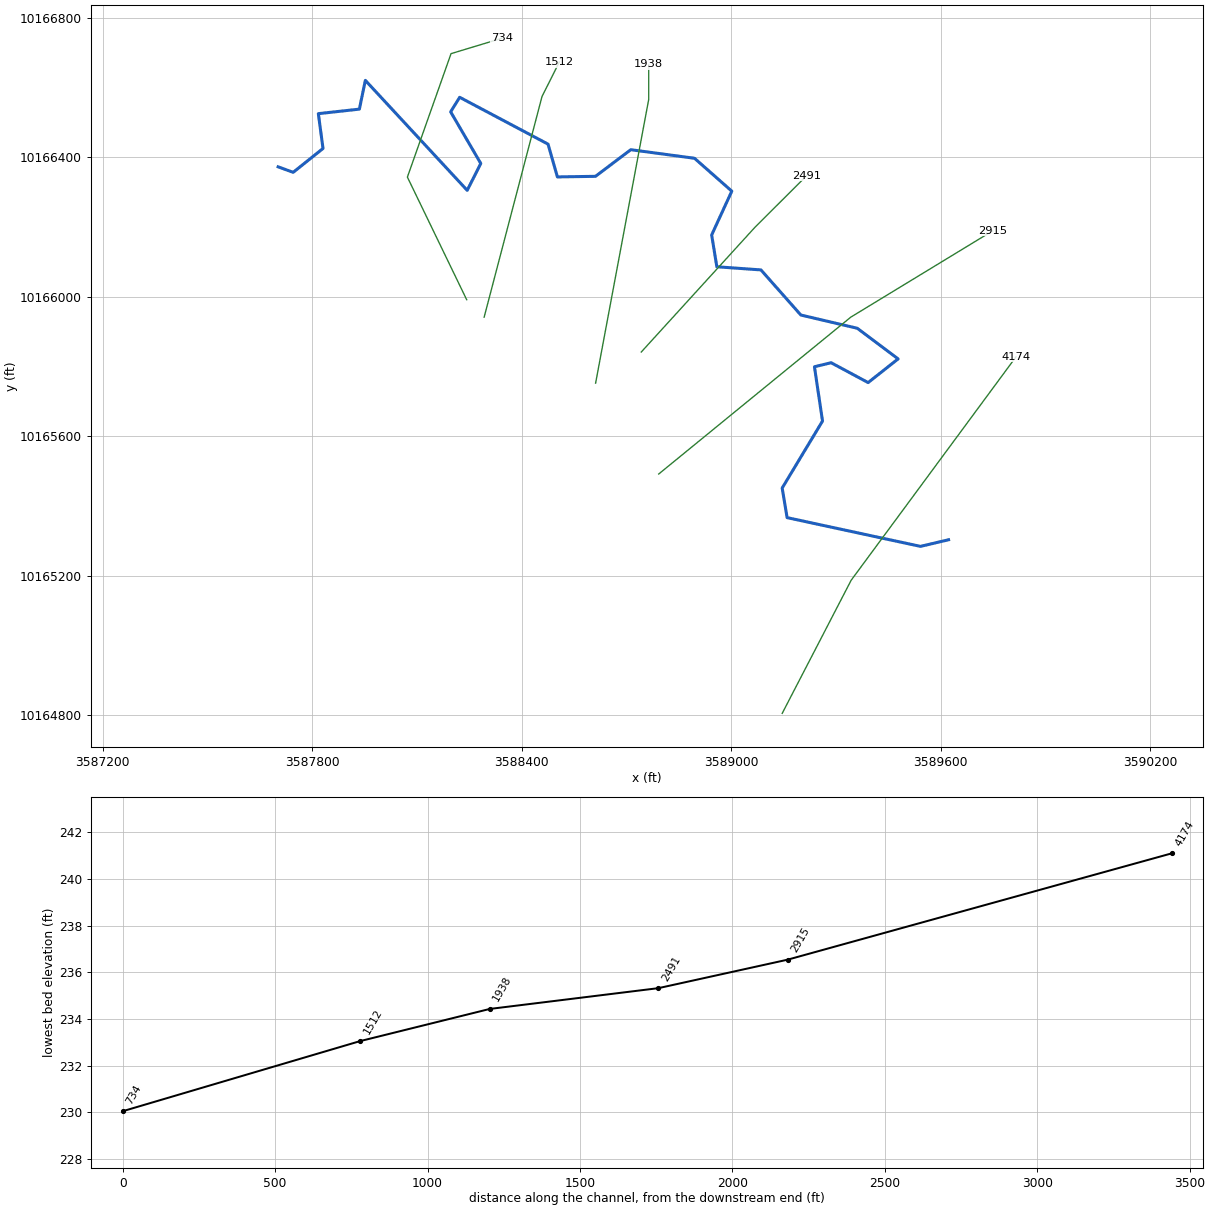
--- PANTHER BRANCH TRIB 2.prj (project) ---

Proj Title=PANTHER BRANCH TRIB 2 Base Level Engineering
Current Plan=p01
Default Exp/Contr=0.3,0.1
English Units
Geom File=g01
Flow File=f01
Plan File=p01
Y Axis Title=Elevation
X Axis Title(PF)=Main Channel Distance
X Axis Title(XS)=Station
BEGIN DESCRIPTION:
PANTHER BRANCH TRIB 2
END DESCRIPTION:
DSS Export Rating Curves= 0
DSS Export Rating Curve Sorted= 0
DSS Export Volume Flow Curves= 0
DXF OffsetX= 0
DXF OffsetY= 0
DXF ScaleX= 1
DXF ScaleY= 10

--- PANTHER BRANCH TRIB 2.p01 (plan) ---

Plan Title=Multiple Run
Short Identifier=Multiple
Geom File=g01
Flow File=f01
Subcritical Flow
K Sum by GR= 0
Std Step Tol= 0.01
Critical Tol= 0.01
Num of Std Step Trials= 20
Max Error Tol= 0.3
Flow Tol Ratio= 0.001
Split Flow NTrial= 30
Split Flow Tol= 0.02
Split Flow Ratio= 0.02
Log Output Level= 0
Friction Slope Method= 1
Unsteady Friction Slope Method= 2
Unsteady Bridges Friction Slope Method= 1
Parabolic Critical Depth
Global Vel Dist=  1 , 1 , 1
Global Log Level= 0
CheckData=True
Encroach Param= -1, 0, 0, 0
BEGIN DESCRIPTION:
Multiple Run
END DESCRIPTION:

--- PANTHER BRANCH TRIB 2.f01 (steady flow) ---

Flow Title=Multiple
Number of Profiles=7
Profile Names=10-year,25-year,50-year,1pct_min,100-year,1pct_plu,500-year
River Rch & RM= PANTHER BRANCH T,Reach-1,4174
     537     721     871     771    1043    1411    1499
Boundary for River Rch & Prof#=PANTHER BRANCH T,Reach-1,1
Up Type=0
Dn Type=3
Dn Slope=0.005
Boundary for River Rch & Prof#=PANTHER BRANCH T,Reach-1,2
Up Type=0
Dn Type=3
Dn Slope=0.005
Boundary for River Rch & Prof#=PANTHER BRANCH T,Reach-1,3
Up Type=0
Dn Type=3
Dn Slope=0.005
Boundary for River Rch & Prof#=PANTHER BRANCH T,Reach-1,4
Up Type=0
Dn Type=3
Dn Slope=0.005
Boundary for River Rch & Prof#=PANTHER BRANCH T,Reach-1,5
Up Type=0
Dn Type=3
Dn Slope=0.005
Boundary for River Rch & Prof#=PANTHER BRANCH T,Reach-1,6
Up Type=0
Dn Type=3
Dn Slope=0.005
Boundary for River Rch & Prof#=PANTHER BRANCH T,Reach-1,7
Up Type=0
Dn Type=3
Dn Slope=0.005

--- PANTHER BRANCH TRIB 2.g01 (geometry) ---

Geom Title=Existing Conditions
Program Version=4.10

River Reach=PANTHER BRANCH T,Reach-1
Reach XY= 30
      3589622.11     10165302.96      3589541.74     10165283.95
      3589159.76     10165366.46      3589145.63     10165451.27
      3589261.18     10165643.62      3589238.07     10165799.28
      3589285.74     10165810.95      3589391.82     10165753.94
      3589477.64     10165821.88      3589360.79     10165909.76
      3589199.15     10165947.77       3589084.8     10166077.24
      3588958.52     10166086.24      3588943.67     10166177.47
      3589001.35     10166303.16      3588894.57     10166397.51
      3588712.03     10166422.11      3588610.99     10166345.72
      3588501.91     10166344.03      3588475.07     10166438.11
      3588222.02     10166572.46      3588196.16     10166530.73
      3588282.46     10166382.64      3588243.58     10166305.46
      3587951.83     10166621.02      3587934.77     10166538.53
      3587817.25     10166525.52      3587830.63     10166425.61
      3587745.16     10166357.16      3587702.11     10166372.96

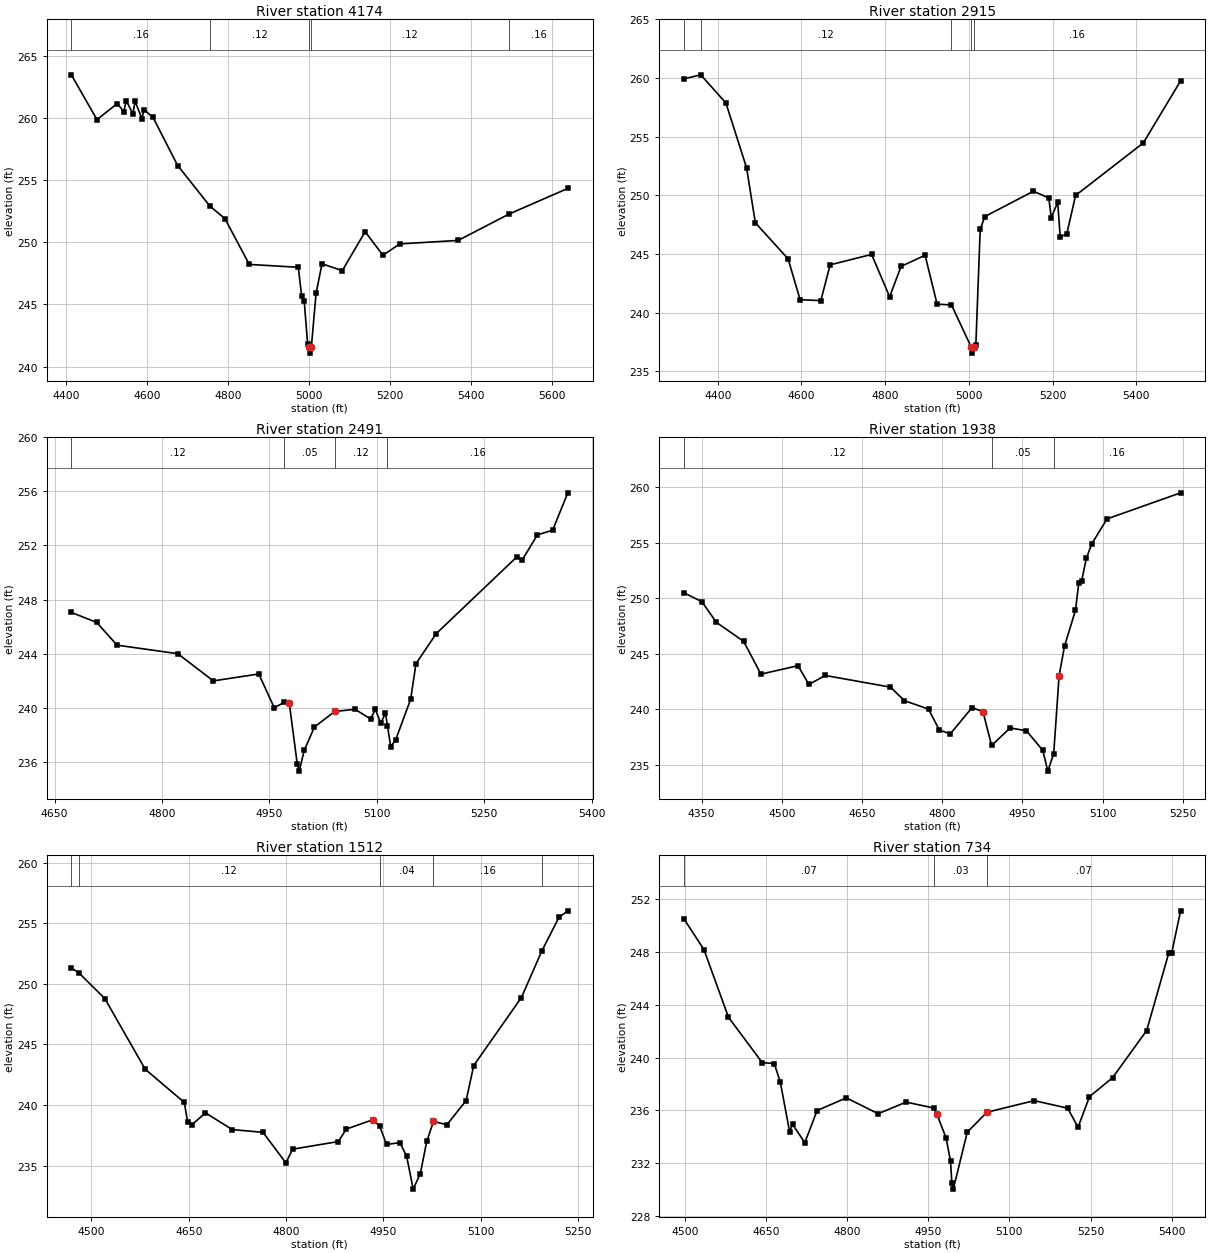
Type RM Length L Ch R = 1 ,4174    ,1259,1259,1259
BEGIN DESCRIPTION:
PANTHER BRANCH TRIB 2 6.0
END DESCRIPTION:
XS GIS Cut Line= 3
      3589145.71     10164804.83       3589343.2     10165186.78
      3589815.37     10165827.89
#Sta/Elev= 30
  4413.1  263.46  4476.4  259.86  4526.4  261.15  4542.9   260.5  4548.5  261.39
    4565  260.33  4570.6  261.33  4587.2  259.94  4592.8  260.66  4614.9  260.03
  4675.7  256.17    4756  252.88  4792.3  251.91  4852.5  248.22  4973.6  247.99
    4982  245.66  4988.3  245.25  4996.7  241.81  4999.9  241.59  5002.7  241.09
  5005.9  241.59  5017.5  245.89  5032.2  248.27  5082.3  247.72  5138.7  250.85
  5182.6  248.96  5224.3  249.87  5368.5  250.15  5494.9  252.28  5639.3  254.33
#Mann= 5 ,-1 , 0
  4413.1     .16       0    4756     .12       0  4999.9     .07       0
  5005.9     .12       0  5494.9     .16       0
Bank Sta=4999.9,5005.9
XS Rating Curve= 0 ,0
Exp/Cntr=0.3,0.1

Type RM Length L Ch R = 1 ,2915    ,424,424,424
BEGIN DESCRIPTION:
PANTHER BRANCH TRIB 2 5.0
END DESCRIPTION:
XS GIS Cut Line= 3
      3588792.11     10165491.65      3589342.11     10165941.64
      3589748.18     10166189.18
#Sta/Elev= 30
  4319.7  259.94  4359.3  260.28  4419.5  257.88    4469  252.33  4489.8  247.66
  4568.1  244.58  4596.8   241.1  4646.3  241.02  4668.5  244.07  4767.6  244.96
  4810.7  241.35    4838  243.94  4895.4  244.89  4924.1  240.72  4958.5  240.65
  5005.8  237.04  5008.5  236.54  5011.8  237.04  5016.7  237.26  5027.1  247.09
  5038.1  248.19  5154.3  250.35    5191  249.78  5196.9  248.09  5212.3  249.41
  5218.2  246.48  5233.7  246.67    5255  249.99  5416.8  254.47  5505.9  259.76
#Mann= 5 ,-1 , 0
  4319.7     .16       0  4359.3     .12       0  4958.5     .16       0
  5005.8     .07       0  5011.8     .16       0
Bank Sta=5005.8,5011.8
XS Rating Curve= 0 ,0
Exp/Cntr=0.3,0.1

Type RM Length L Ch R = 1 ,2491    ,553,553,553
BEGIN DESCRIPTION:
PANTHER BRANCH TRIB 2 4.0
END DESCRIPTION:
XS GIS Cut Line= 3
      3588742.13     10165841.67      3589067.11     10166198.93
      3589215.98     10166347.81
#Sta/Elev= 30
  4673.4  247.05  4708.8  246.31  4737.2  244.63  4822.1     244  4871.7  241.99
  4935.2   242.5  4956.8  240.01  4970.8   240.4  4977.8  240.35    4989  235.82
  4991.7  235.32  4998.7  236.85  5012.9  238.58  5041.3  239.73  5069.7  239.89
  5091.3  239.18  5098.1  239.88  5105.5  238.86  5112.2   239.6  5114.9  238.69
  5119.5  237.13  5126.4  237.63  5147.4  240.64  5154.8  243.26    5183  245.48
  5296.2  251.18  5303.2  250.93  5324.4  252.78  5345.7  253.13  5366.9  255.89
#Mann= 4 ,-1 , 0
  4673.4     .12       0  4970.8     .05       0  5041.3     .12       0
  5114.9     .16       0
Bank Sta=4977.8,5041.3
XS Rating Curve= 0 ,0
Exp/Cntr=0.3,0.1

Type RM Length L Ch R = 1 ,1938    ,426,426,426
BEGIN DESCRIPTION:
PANTHER BRANCH TRIB 2 3.0
END DESCRIPTION:
XS GIS Cut Line= 3
      3588611.31     10165752.34      3588763.46     10166566.64
      3588763.46     10166666.65
#Sta/Elev= 30
  4317.3  250.47  4350.5  249.68  4377.6  247.82  4428.5  246.11  4460.9  243.16
  4530.2  243.92  4550.6  242.23  4581.1  243.04  4703.2  241.99  4729.3  240.77
  4774.4  240.01  4794.7  238.11  4815.1  237.79  4855.8  240.15  4876.1  239.78
  4892.3  236.74    4927  238.32  4957.5  238.06    4988   236.3  4997.4  234.43
  5008.4     236  5018.5  243.02  5028.7   245.7  5049.1   248.9  5055.4   251.4
  5060.5  251.51  5069.4  253.58  5079.6  254.89  5108.1  257.13  5245.7  259.48
#Mann= 3 ,-1 , 0
  4317.3     .12       0  4892.3     .05       0  5008.4     .16       0
Bank Sta=4876.1,5018.5
XS Rating Curve= 0 ,0
Exp/Cntr=0.3,0.1

Type RM Length L Ch R = 1 ,1512    ,778,778,778
BEGIN DESCRIPTION:
PANTHER BRANCH TRIB 2 2.0
END DESCRIPTION:
XS GIS Cut Line= 3
      3588292.12     10165941.69      3588457.73     10166574.45
      3588507.42     10166673.84
#Sta/Elev= 30
    4469  251.32  4480.3  250.93  4520.6  248.79  4582.7  242.96  4643.1  240.21
  4648.3  238.57    4655  238.38  4675.7  239.35    4717  237.97  4764.4  237.74
  4799.6  235.22  4810.1  236.35  4880.5  236.98  4892.8  238.01  4934.1  238.79
  4944.4  238.23  4954.8  236.74  4975.5  236.89  4985.8  235.75  4995.9  233.05
  5006.9  234.34  5016.8     237  5027.1  238.64  5047.8  238.37  5077.4  240.36
  5089.2  243.26  5162.7  248.88  5194.3  252.74  5220.6  255.51  5234.2  256.04
#Mann= 5 ,-1 , 0
    4469     .16       0  4480.3     .12       0  4944.4     .04       0
  5027.1     .16       0  5194.3      .1       0
Bank Sta=4934.1,5027.1
XS Rating Curve= 0 ,0
Exp/Cntr=0.3,0.1

Type RM Length L Ch R = 1 ,734     ,0,0,0
BEGIN DESCRIPTION:
PANTHER BRANCH TRIB 2 1.0
END DESCRIPTION:
XS GIS Cut Line= 4
       3588242.1     10165991.64      3588072.26     10166343.53
      3588197.26     10166697.69      3588342.13     10166741.65
#Sta/Elev= 30
  4498.7  250.46  4535.4  248.15  4580.6  243.05  4642.9  239.62  4665.3  239.54
  4676.6  238.12  4693.6   234.4  4699.2  234.94  4721.8  233.56  4744.4  235.99
  4798.5  236.95  4857.4  235.75    4909  236.63  4960.2  236.18  4965.5  235.76
  4982.9  233.92  4991.2  232.14  4993.5  230.55  4996.2  230.05  5022.1  234.36
  5058.3  235.86  5145.8  236.74  5207.7  236.17  5226.8  234.73    5248  237.04
  5290.8  238.48  5353.7  242.04  5394.7  247.92  5399.9   247.9  5416.4  251.09
#Mann= 3 ,-1 , 0
  4498.7     .07       0  4960.2     .03       0  5058.3     .07       0
Bank Sta=4965.5,5058.3
XS Rating Curve= 0 ,0
Exp/Cntr=0.3,0.1

Chan Stop Cuts=-1
Use User Specified Reach Order=0
Composite Channel Slope=5