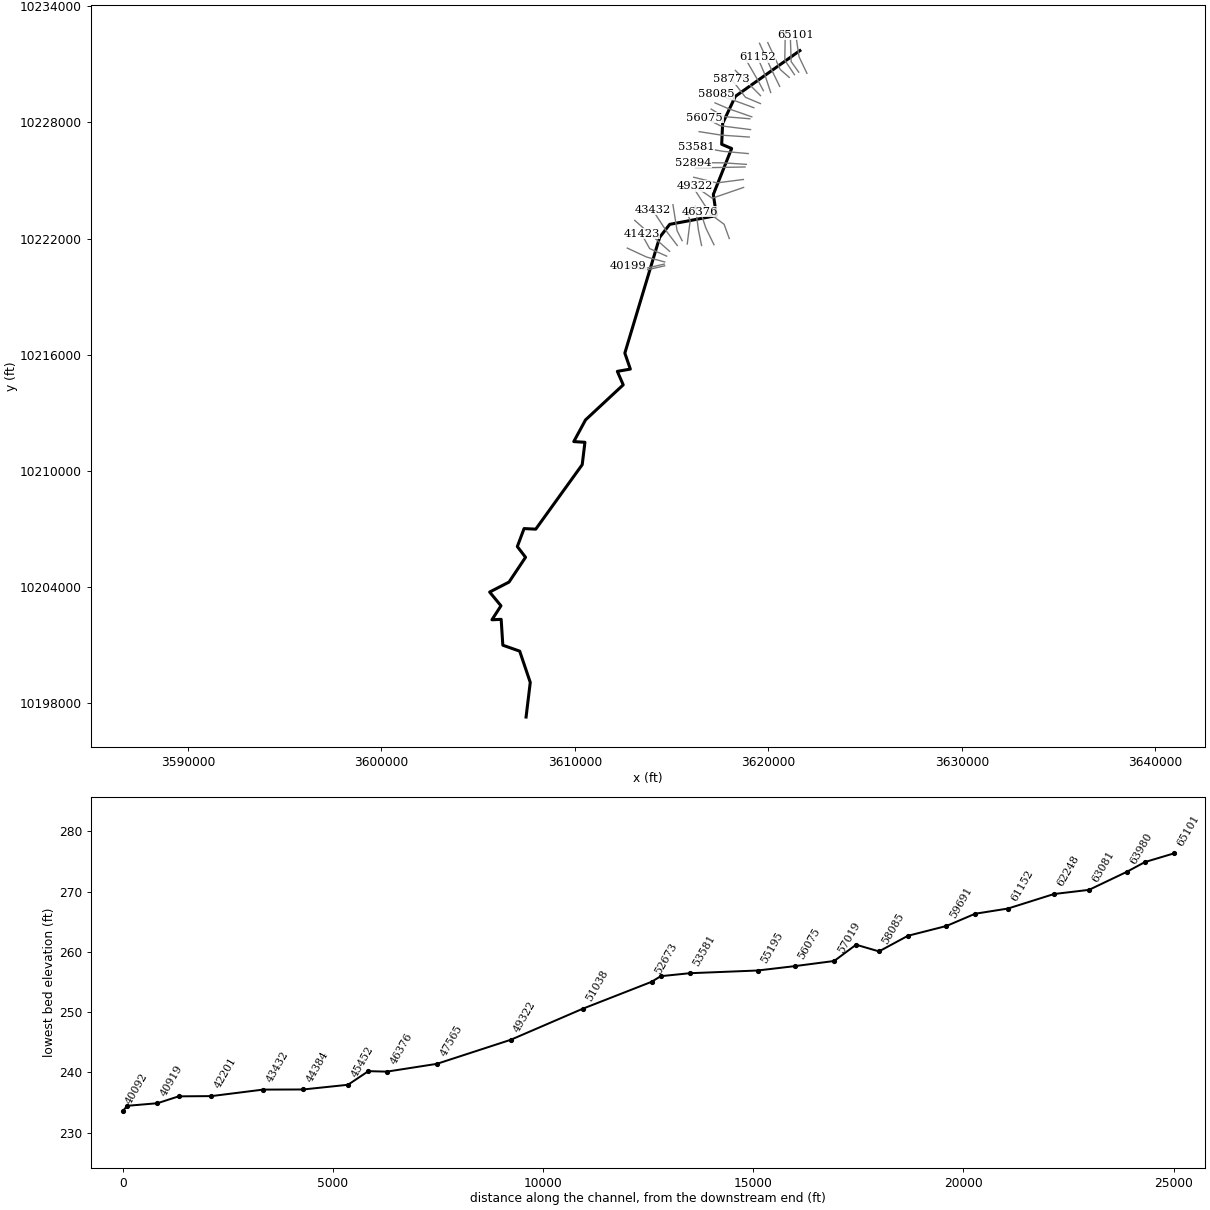
--- PANTHER CREEK.prj (project) ---

Proj Title=PANTHER CREEK Base Level Engineering
Current Plan=p01
Default Exp/Contr=0.3,0.1
English Units
Geom File=g01
Flow File=f01
Plan File=p01
Y Axis Title=Elevation
X Axis Title(PF)=Main Channel Distance
X Axis Title(XS)=Station
BEGIN DESCRIPTION:
PANTHER CREEK
END DESCRIPTION:
DSS Export Rating Curves= 0
DSS Export Rating Curve Sorted= 0
DSS Export Volume Flow Curves= 0
DXF OffsetX= 0
DXF OffsetY= 0
DXF ScaleX= 1
DXF ScaleY= 10

--- PANTHER CREEK.p01 (plan) ---

Plan Title=Multiple Run
Short Identifier=Multiple
Geom File=g01
Flow File=f01
Subcritical Flow
K Sum by GR= 0
Std Step Tol= 0.01
Critical Tol= 0.01
Num of Std Step Trials= 20
Max Error Tol= 0.3
Flow Tol Ratio= 0.001
Split Flow NTrial= 30
Split Flow Tol= 0.02
Split Flow Ratio= 0.02
Log Output Level= 0
Friction Slope Method= 1
Unsteady Friction Slope Method= 2
Unsteady Bridges Friction Slope Method= 1
Parabolic Critical Depth
Global Vel Dist=  1 , 1 , 1
Global Log Level= 0
CheckData=True
Encroach Param= -1, 0, 0, 0
BEGIN DESCRIPTION:
Multiple Run
END DESCRIPTION:

--- PANTHER CREEK.f01 (steady flow) ---

Flow Title=Multiple
Program Version=4.10
Number of Profiles= 7
Profile Names=10-year,25-year,50-year,1pct_min,100-year,1pct_plu,500-year
River Rch & RM=PANTHER CREEK,Reach-1         ,65101
     401     523     619     538     727     984    1005
River Rch & RM=PANTHER CREEK,Reach-1         ,63081
     860    1166    1416    1258    1701    2300    2459
River Rch & RM=PANTHER CREEK,Reach-1         ,56075
     988    1346    1639    1458    1972    2667    2862
River Rch & RM=PANTHER CREEK,Reach-1         ,47565
    1450    2005    2467    2216    2996    4052    4430
River Rch & RM=PANTHER CREEK,Reach-1         ,41423
    1588    2202    2713    2439    3298    4461    4887
River Rch & RM=PANTHER CREEK,Reach-1         ,34568
    1706    2371    2927    2634    3563    4818    5294
River Rch & RM=PANTHER CREEK,Reach-1         ,33835
    1706    2371    2927    2634    3563    4818    5294
River Rch & RM=PANTHER CREEK,Reach-1         ,33441
    1790    2497    3089    2788    3770    5099    5631
River Rch & RM=PANTHER CREEK,Reach-1         ,30834
    2285    3211    3993    3618    4893    6617    7367
River Rch & RM=PANTHER CREEK,Reach-1         ,29792
    2285    3211    3993    3618    4893    6617    7367
River Rch & RM=PANTHER CREEK,Reach-1         ,19751
    2396    3374    4202    3812    5155    6972    7783
River Rch & RM=PANTHER CREEK,Reach-1         ,19568
    2431    3417    4249    3850    5206    7041    7836
River Rch & RM=PANTHER CREEK,Reach-1         ,12198
    2858    4032    5026    4562    6170    8344    9322
River Rch & RM=PANTHER CREEK,Reach-1         ,8082
    2858    4032    5026    4562    6170    8344    9322
Boundary for River Rch & Prof#=PANTHER CREEK,Reach-1         , 1
Up Type= 0
Dn Type= 3
Dn Slope=0.005
Boundary for River Rch & Prof#=PANTHER CREEK,Reach-1         , 2
Up Type= 0
Dn Type= 3
Dn Slope=0.005
Boundary for River Rch & Prof#=PANTHER CREEK,Reach-1         , 3
Up Type= 0
Dn Type= 3
Dn Slope=0.005
Boundary for River Rch & Prof#=PANTHER CREEK,Reach-1         , 4
Up Type= 0
Dn Type= 3
Dn Slope=0.005
Boundary for River Rch & Prof#=PANTHER CREEK,Reach-1         , 5
Up Type= 0
Dn Type= 3
Dn Slope=0.005
Boundary for River Rch & Prof#=PANTHER CREEK,Reach-1         , 6
Up Type= 0
Dn Type= 3
Dn Slope=0.005
Boundary for River Rch & Prof#=PANTHER CREEK,Reach-1         , 7
Up Type= 0
Dn Type= 3
Dn Slope=0.005
DSS Import GetInterval= 0
DSS Import GetPeak= 0
DSS Import FillOption= 0

--- PANTHER CREEK.g01 (geometry) ---

Geom Title=Existing Conditions
Program Version=4.10

River Reach=PANTHER CREEK   ,Reach-1
Reach XY= 30
      3621628.47     10231713.84      3618293.96     10229350.94
      3617636.22     10227950.58      3617586.22     10226872.53
      3618100.37     10226654.56      3617154.68      10224280.9
      3617315.42     10223187.19      3614900.47     10222734.14
      3614381.03     10222065.13       3612581.1     10216080.69
      3612864.61     10215254.03      3612193.82     10215136.13
      3612496.99     10214439.51      3610549.61     10212628.32
        3609942.     10211506.55      3610518.29     10211470.52
      3610378.44     10210313.99      3607975.87     10206980.43
      3607373.72     10207011.32      3607024.02     10206081.18
      3607449.26     10205527.58      3606594.63     10204245.42
      3605594.39     10203730.09      3606178.91     10203020.61
      3605712.37     10202296.34      3606188.68      10202320.5
      3606274.81     10200982.97       3607147.2     10200675.32
      3607692.83     10199060.43      3607476.63     10197270.66

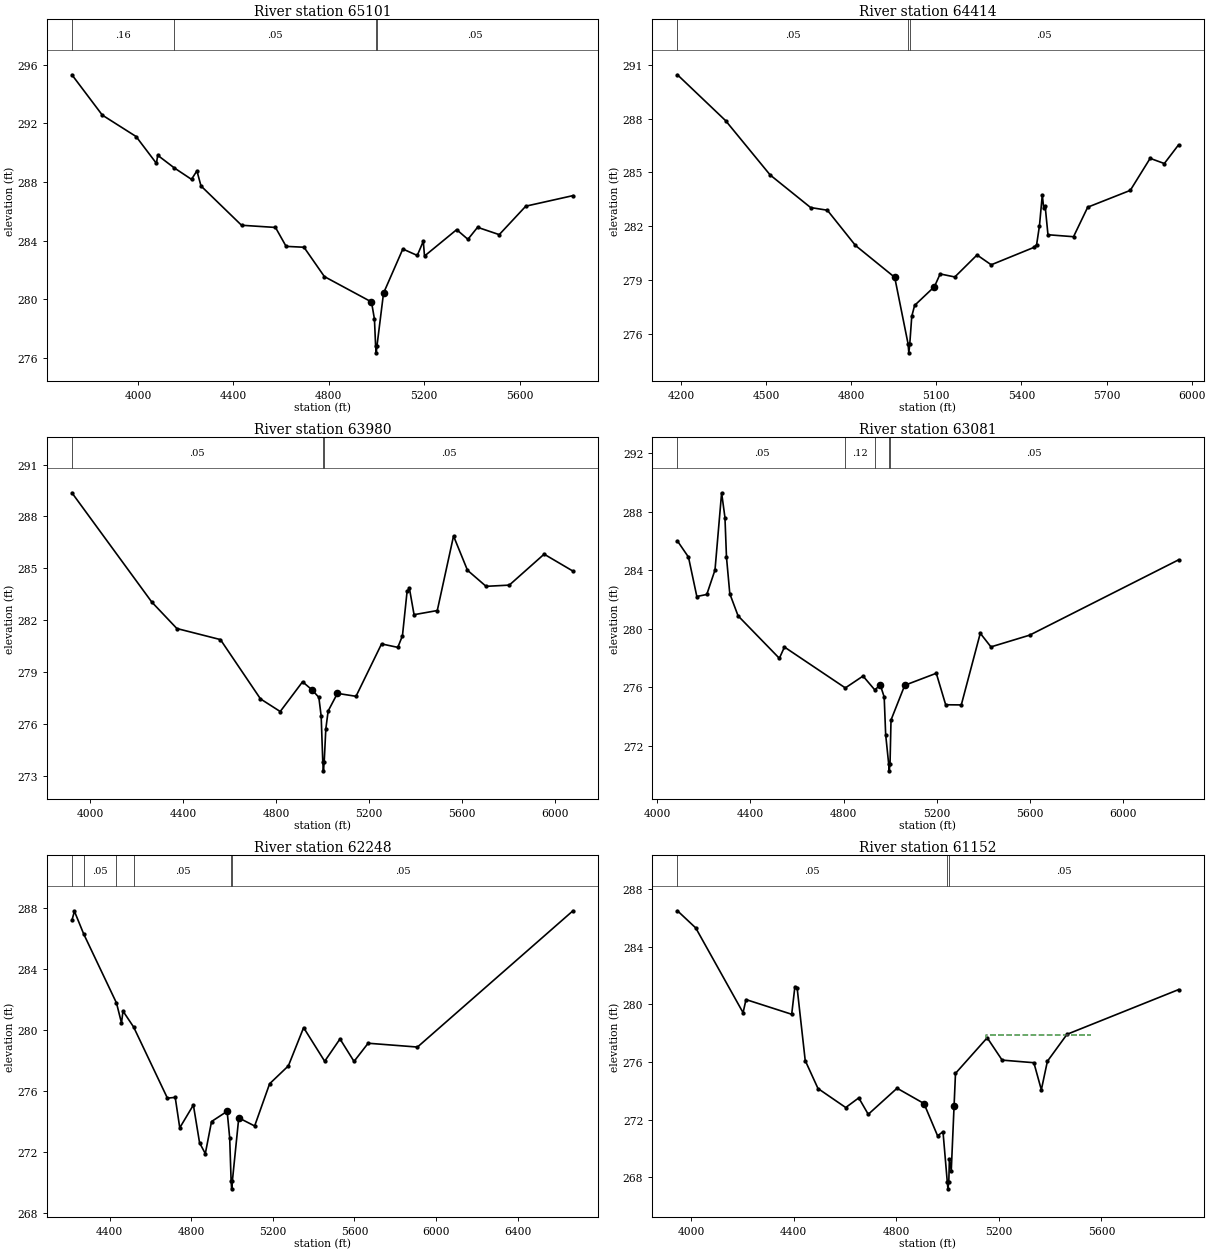
Type RM Length L Ch R = 1 ,65101   ,687,687,687
BEGIN DESCRIPTION:
PANTHER CREEK 83.0
END DESCRIPTION:
XS GIS Cut Line= 3
      3621992.11     10230541.63      3621582.91      10231397.7
      3621416.37     10232537.46
#Sta/Elev= 30
  3723.2  295.31  3850.7  292.56  3992.3   291.1  4077.5  289.27    4083  289.82
  4152.4  288.96  4224.6  288.18  4247.3  288.76  4264.4  287.73  4434.3  285.05
  4576.7   284.9  4621.2  283.61  4696.2  283.55  4781.7  281.55  4979.2  279.82
  4991.6  278.65  4996.4  276.85  4999.2  276.35  5002.4  276.85  5029.7  280.42
  5110.6  283.43  5171.2  282.99  5196.4  283.96  5201.5  282.95  5336.3  284.75
  5383.5  284.09  5423.9  284.91  5514.8  284.41    5626  286.35  5823.9  287.07
#Mann= 4 ,-1 , 0
  3723.2     .16       0  4152.4     .05       0  4996.4     .03       0
  5002.4     .05       0
Bank Sta=4979.2,5029.7
XS Rating Curve= 0 ,0
Exp/Cntr=0.3,0.1

Type RM Length L Ch R = 1 ,64414   ,434,434,434
BEGIN DESCRIPTION:
PANTHER CREEK 82.0
END DESCRIPTION:
XS GIS Cut Line= 3
      3621567.28     10230600.83      3621176.66      10231147.7
      3621142.11      10232241.6
#Sta/Elev= 30
  4187.2  290.46  4356.8   287.9  4514.1  284.86  4656.7  283.04  4715.7  282.89
  4814.9  280.92  4953.2  279.14  5000.3  275.42    5003  274.92  5006.3  275.42
  5013.3  276.96  5023.3  277.57  5093.3  278.62  5113.3  279.33  5165.1  279.16
  5243.4  280.39  5293.4  279.84  5443.5  280.81  5453.5  280.97  5463.5  282.02
  5473.5  283.74  5478.6  282.99  5483.6  283.12  5493.5  281.52  5583.6  281.41
  5633.6  283.06  5783.7     284  5853.7  285.79  5903.7   285.5  5953.7  286.54
#Mann= 3 ,-1 , 0
  4187.2     .05       0  5000.3     .03       0  5006.3     .05       0
Bank Sta=4953.2,5093.3
XS Rating Curve= 0 ,0
Exp/Cntr=0.3,0.1

Type RM Length L Ch R = 1 ,63980   ,899,899,899
BEGIN DESCRIPTION:
PANTHER CREEK 81.0
END DESCRIPTION:
XS GIS Cut Line= 3
      3621348.56     10230470.58      3620848.54     10231215.41
      3620869.37     10232475.84
#Sta/Elev= 30
  3921.4  289.37  4265.4  283.05  4373.4  281.52    4561  280.88  4733.5  277.45
  4818.5  276.72  4914.7  278.44  4954.8  277.98  4984.8  277.54  4994.8  276.45
  5001.8  273.79  5004.5  273.29  5007.8  273.79  5014.8  275.71  5024.8  276.75
  5064.8  277.77  5144.8   277.6  5254.8  280.63  5324.8  280.43  5344.8   281.1
  5364.8  283.67  5374.8  283.84  5394.8  282.32  5494.8  282.56  5564.8  286.87
  5624.8  284.89  5704.9  283.96  5804.9  284.03  5954.9  285.82  6079.1  284.84
#Mann= 3 ,-1 , 0
  3921.4     .05       0  5001.8     .03       0  5007.8     .05       0
Bank Sta=4954.8,5064.8
XS Rating Curve= 0 ,0
Exp/Cntr=0.3,0.1

Type RM Length L Ch R = 1 ,63081   ,833,833,833
BEGIN DESCRIPTION:
PANTHER CREEK 80.0
END DESCRIPTION:
XS GIS Cut Line= 3
      3621077.68     10230330.01      3620614.16     10230736.24
      3619968.38     10232126.76
#Sta/Elev= 30
  4087.2  285.99  4134.5  284.89  4170.4   282.2  4213.1  282.34  4248.3  284.01
  4276.7  289.28    4291  287.59  4297.6  284.88  4311.8  282.39  4347.3  280.88
  4524.4  277.98  4546.2  278.75  4807.4  275.96  4883.4  276.77  4933.5  275.83
  4957.6  276.15  4974.1  275.34  4980.5  272.76  4993.2   270.8  4995.9   270.3
  4999.2   270.8  5003.4  273.77  5062.3  276.14  5197.6  276.96  5237.9  274.81
  5304.9   274.8  5386.3  279.69  5432.1  278.76  5597.9  279.56  6236.7   284.7
#Mann= 5 ,-1 , 0
  4087.2     .05       0  4807.4     .12       0  4933.5     .05       0
  4993.2     .03       0  4999.2     .05       0
Bank Sta=4957.6,5062.3
XS Rating Curve= 0 ,0
Exp/Cntr=0.3,0.1

Type RM Length L Ch R = 1 ,62248   ,1096,1096,1096
BEGIN DESCRIPTION:
PANTHER CREEK 78.0
END DESCRIPTION:
XS GIS Cut Line= 3
       3620582.9     10229866.46      3620150.62     10230751.86
       3619542.1     10232091.65
#Sta/Elev= 30
  4214.8  287.16  4227.1  287.76  4272.7  286.27  4433.4  281.76  4457.9  280.46
  4465.4  281.23  4517.4  280.19  4683.1  275.54  4721.3  275.59  4743.6   273.6
  4810.4  275.09  4840.8  272.62  4868.9  271.91  4899.4  274.01    4976  274.68
  4988.4  272.95  4995.5  270.11  4998.2  269.61  5001.5  270.11  5032.9  274.25
  5110.8  273.72  5184.2  276.48  5276.2  277.65  5350.9  280.15  5454.2  277.95
  5529.3  279.41  5598.1  277.94  5667.3  279.13  5909.1  278.88  6671.6  287.79
#Mann= 6 ,-1 , 0
  4214.8     .16       0  4272.7     .05       0  4433.4     .16       0
  4517.4     .05       0  4995.5     .03       0  5001.5     .05       0
Bank Sta=4976,5032.9
XS Rating Curve= 0 ,0
Exp/Cntr=0.3,0.1

Type RM Length L Ch R = 1 ,61152   ,779,779,779
BEGIN DESCRIPTION:
PANTHER CREEK 76.0
END DESCRIPTION:
XS GIS Cut Line= 3
      3620119.38      10229548.7      3619792.11     10230541.64
      3619437.13     10231376.74
#Sta/Elev= 30
  3947.6  286.49  4018.9   285.3  4203.4  279.42  4214.8  280.33  4392.9  279.31
  4405.4  281.23    4414  281.15  4445.6   276.1  4495.4  274.16  4603.5  272.84
  4654.3  273.51  4691.3  272.37  4803.6  274.18  4908.4  273.12  4961.5  270.88
  4982.6  271.16  4999.2   267.7  5001.9   267.2  5005.2   267.7  5007.6  269.25
  5014.8  268.45  5025.7  272.92  5031.3  275.21  5154.9  277.68  5213.1  276.13
  5336.8  275.95  5365.9  274.07  5389.5  276.05  5465.9  277.92  5900.5  281.02
#Mann= 3 ,-1 , 0
  3947.6     .05       0  4999.2     .03       0  5005.2     .05       0
#XS Ineff= 1 ,-1
 5151.99 5559.66  277.86
Permanent Ineff=
       F
Bank Sta=4908.4,5025.7
XS Rating Curve= 0 ,0
Exp/Cntr=0.3,0.1

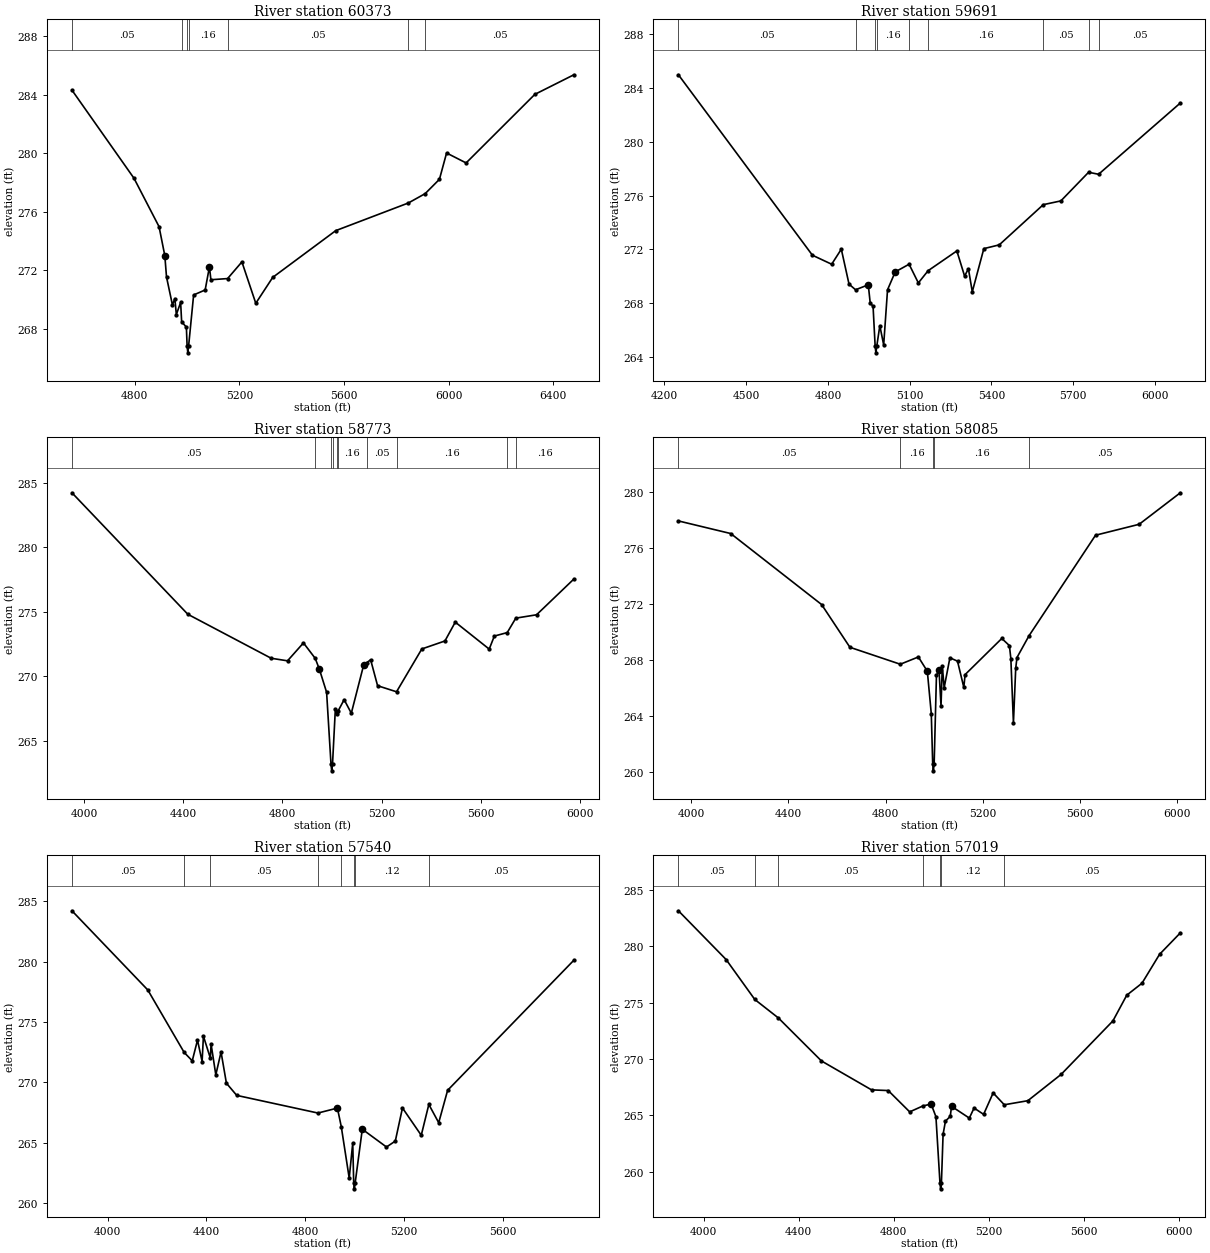
Type RM Length L Ch R = 1 ,60373   ,682,682,682
BEGIN DESCRIPTION:
PANTHER CREEK 75.0
END DESCRIPTION:
XS GIS Cut Line= 3
      3619742.11     10229641.63      3619483.95     10230132.07
      3618801.65     10231314.39
#Sta/Elev= 30
  4559.8  284.31  4797.1  278.28  4892.9  274.97  4914.9  272.99  4921.4  271.53
    4944  269.62  4953.3  270.05    4959  268.96  4975.4  269.79  4979.3  268.46
  4997.4   268.1  5000.1  266.84  5002.8  266.34  5006.1  266.84  5025.1   270.3
  5069.2  270.64  5085.5  272.22  5091.2  271.34    5155  271.42  5209.7  272.56
  5262.8  269.73  5327.5   271.5  5568.7   274.7  5846.2  276.59  5910.5  277.23
  5965.1  278.21  5992.4  280.01  6067.1  279.33  6329.9  284.02  6479.1  285.36
#Mann= 7 ,-1 , 0
  4559.8     .05       0  4979.3     .16       0  5000.1     .07       0
  5006.1     .16       0    5155     .05       0  5846.2      .1       0
  5910.5     .05       0
Bank Sta=4914.9,5085.5
XS Rating Curve= 0 ,0
Exp/Cntr=0.3,0.1

Type RM Length L Ch R = 1 ,59691   ,918,918,918
BEGIN DESCRIPTION:
PANTHER CREEK 73.0
END DESCRIPTION:
XS GIS Cut Line= 3
      3619593.34     10229387.26      3619092.11     10229891.64
      3618292.07     10230691.68
#Sta/Elev= 30
  4251.1  284.99    4743  271.57  4813.7   270.9  4849.1  272.02  4877.4  269.42
  4901.4     269  4948.1  269.37  4955.1  268.03  4965.7  267.76  4973.3  264.81
  4976.1  264.31  4979.3  264.81  4990.5  266.33  5004.6   264.9  5018.8     269
    5047  270.33  5097.9   270.9  5131.9  269.51  5167.8  270.42  5273.3  271.89
  5301.6  270.02  5315.7  270.56  5329.9  268.85  5372.3  272.06  5428.9  272.34
  5590.5  275.33  5655.1  275.61  5756.9  277.74  5793.5  277.59  6093.6  282.89
#Mann= 9 ,-1 , 0
  4251.1     .05       0  4901.4     .16       0  4973.3     .07       0
  4979.3     .16       0  5097.9     .05       0  5167.8     .16       0
  5590.5     .05       0  5756.9     .16       0  5793.5     .05       0
Bank Sta=4948.1,5047
XS Rating Curve= 0 ,0
Exp/Cntr=0.3,0.1

Type RM Length L Ch R = 1 ,58773   ,688,688,688
BEGIN DESCRIPTION:
PANTHER CREEK 71.0
END DESCRIPTION:
XS GIS Cut Line= 3
      3619588.12     10228975.82      3618817.29     10229298.74
      3618092.08     10230241.67
#Sta/Elev= 30
  3950.4  284.24    4418  274.82  4754.3  271.41  4820.3  271.21  4884.6   272.6
  4932.1   271.4    4949  270.55    4978  268.77  4995.8  263.18  4998.6  262.68
  5001.8  263.18  5013.3  267.48  5019.6  267.09  5024.4  267.32  5048.7   268.2
  5077.7  267.15  5127.5  270.88  5139.9  271.07  5155.7  271.29  5183.7  269.28
  5260.2  268.81  5362.2  272.13  5455.5  272.75  5497.2  274.21  5634.1  272.12
  5654.9  273.13  5706.9   273.4  5741.5  274.52  5825.2  274.78  5975.7  277.55
#Mann= 10 ,-1 , 0
  3950.4     .05       0  4932.1     .16       0  4995.8     .07       0
  5001.8     .16       0  5019.6     .05       0  5024.4     .16       0
  5139.9     .05       0  5260.2     .16       0  5706.9     .05       0
  5741.5     .16       0
Bank Sta=4949,5127.5
XS Rating Curve= 0 ,0
Exp/Cntr=0.3,0.1

Type RM Length L Ch R = 1 ,58085   ,545,545,545
BEGIN DESCRIPTION:
PANTHER CREEK 70.0
END DESCRIPTION:
XS GIS Cut Line= 3
      3619249.62     10228762.26      3618259.99     10229126.86
      3617301.67     10229454.99
#Sta/Elev= 30
  3946.7  277.93  4162.2  277.03  4536.7  271.96  4653.2  268.91  4860.8   267.7
  4935.2  268.22  4972.1   267.2  4988.4  264.17  4994.2  260.59    4997  260.09
  5000.2  260.59  5009.7   266.9  5020.3  267.27  5028.5  264.72  5033.8  267.59
  5041.4  266.02  5065.1  268.16  5096.4  267.92  5122.4  266.05  5127.7  266.96
  5278.9  269.54  5310.2  269.03  5316.2   268.1  5326.8  263.51  5336.2   267.4
  5341.4  268.18  5390.9  269.73    5665  276.91  5844.7  277.69  6014.3  279.94
#Mann= 5 ,-1 , 0
  3946.7     .05       0  4860.8     .16       0  4994.2     .07       0
  5000.2     .16       0  5390.9     .05       0
Bank Sta=4972.1,5020.3
XS Rating Curve= 0 ,0
Exp/Cntr=0.3,0.1

Type RM Length L Ch R = 1 ,57540   ,521,521,521
BEGIN DESCRIPTION:
PANTHER CREEK 68.0
END DESCRIPTION:
XS GIS Cut Line= 3
      3619142.11     10228291.64      3617942.11     10228711.43
       3617242.1     10229011.44
#Sta/Elev= 30
  3855.1   284.2  4162.3  277.65  4309.7  272.48  4342.4  271.79  4363.6   273.5
  4382.3  271.73  4387.6  273.83  4415.7  272.01  4418.6  273.18  4437.8  270.63
    4459  272.52  4480.7  269.94  4522.5  268.93  4851.5  267.47  4930.3  267.88
    4946  266.34  4978.1  262.09  4992.4  264.98  4996.3   261.7    4999   261.2
  5002.3   261.7  5031.1  266.13  5129.1  264.66  5164.8  265.15  5193.8  267.89
  5269.9  265.63  5300.6  268.18  5340.6  266.67  5376.7  269.35    5888  280.11
#Mann= 8 ,-1 , 0
  3855.1     .05       0  4309.7     .08       0  4415.7     .05       0
  4851.5     .16       0    4946     .12       0  4996.3     .07       0
  5002.3     .12       0  5300.6     .05       0
Bank Sta=4930.3,5031.1
XS Rating Curve= 0 ,0
Exp/Cntr=0.3,0.1

Type RM Length L Ch R = 1 ,57019   ,944,944,944
BEGIN DESCRIPTION:
PANTHER CREEK 67.0
END DESCRIPTION:
XS GIS Cut Line= 3
       3619042.1     10228191.64      3617687.08     10228303.95
       3617042.1     10228691.64
#Sta/Elev= 30
  3894.2  283.14  4094.9  278.82  4215.6  275.28    4315  273.64  4496.3  269.83
    4707  267.27  4777.2  267.21  4867.5  265.32  4923.6  265.85  4957.8  266.01
  4977.9  264.89    4995     259  4997.7   258.5    5001     259    5008  263.33
    5018   264.5  5038.1  264.92  5043.7  265.81  5118.4  264.77  5138.4  265.66
  5178.6   265.1  5218.7     267  5265.6  265.95  5364.7  266.31  5504.7  268.64
  5722.7  273.38    5781  275.66  5845.1  276.72    5919  279.28  6006.4  281.18
#Mann= 7 ,-1 , 0
  3894.2     .05       0  4215.6     .08       0    4315     .05       0
  4923.6     .12       0    4995     .07       0    5001     .12       0
  5265.6     .05       0
Bank Sta=4957.8,5043.7
XS Rating Curve= 0 ,0
Exp/Cntr=0.3,0.1

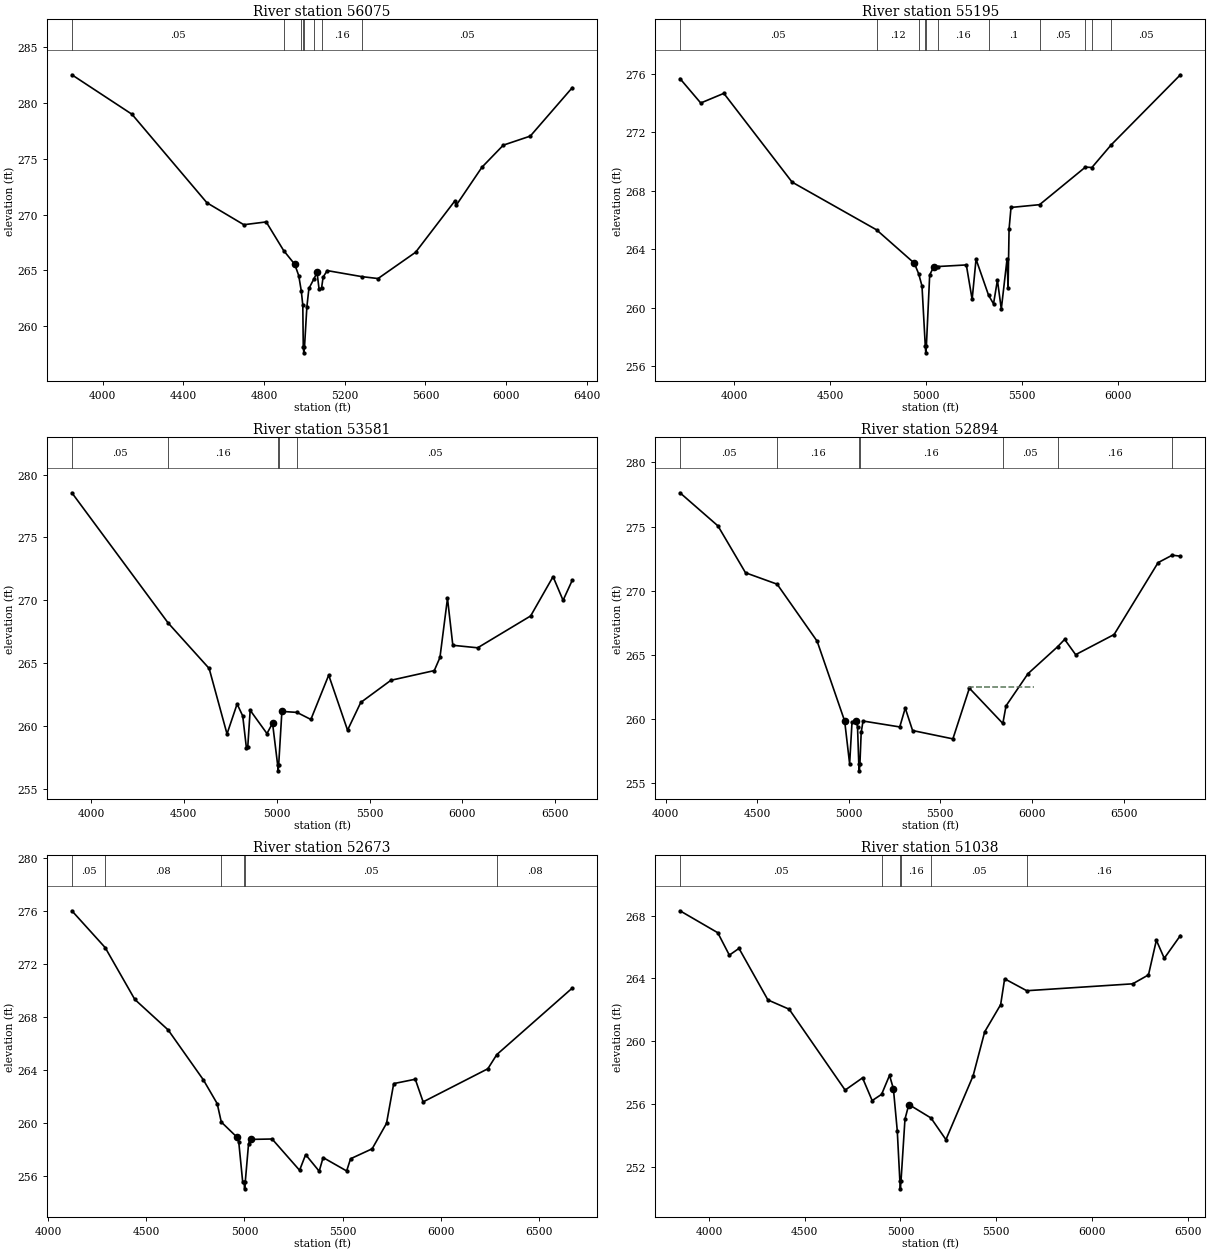
Type RM Length L Ch R = 1 ,56075   ,880,880,880
BEGIN DESCRIPTION:
PANTHER CREEK 66.0
END DESCRIPTION:
XS GIS Cut Line= 3
      3619077.75     10227632.07       3617515.2     10227829.99
      3616706.95     10228238.39
#Sta/Elev= 30
  3847.1  282.49  4145.1  278.96  4516.6  271.05  4699.5  269.09  4810.4  269.34
  4896.9  266.78  4951.5  265.56  4971.7  264.54  4984.5  263.15  4991.8  261.89
  4994.2  258.14    4997  257.64  5000.2  258.14    5012  261.75  5022.1  263.39
  5045.5   264.2  5062.4  264.82  5072.3  263.36  5084.6   263.4  5092.6  264.41
  5112.8  264.99  5284.6  264.45  5364.8  264.28  5551.1  266.63  5746.1  271.23
  5751.7  270.81  5879.9  274.23  5985.7   276.2  6119.5  277.01  6327.7  281.34
#Mann= 8 ,-1 , 0
  3847.1     .05       0  4896.9     .12       0  4984.5     .16       0
  4994.2     .07       0  5000.2     .16       0  5045.5     .12       0
  5084.6     .16       0  5284.6     .05       0
Bank Sta=4951.5,5062.4
XS Rating Curve= 0 ,0
Exp/Cntr=0.3,0.1

Type RM Length L Ch R = 1 ,55195   ,1614,1614,1614
BEGIN DESCRIPTION:
PANTHER CREEK 63.0
END DESCRIPTION:
XS GIS Cut Line= 3
      3619010.03     10227246.65      3617567.29     10227345.61
      3616420.42     10227526.64
#Sta/Elev= 30
  3717.6  275.67  3825.8     274  3946.1  274.66  4301.9  268.59  4741.7  265.33
  4938.4  263.05  4961.3  262.32  4978.5  261.49  4995.5  257.42  4998.3  256.92
  5001.5  257.42  5018.6  262.25  5038.6  262.77  5060.5  262.82  5209.5  262.93
  5239.8  260.57  5260.1  263.32  5325.3  260.86  5351.2  260.27  5371.5  261.89
  5391.7  259.91  5421.9  263.36    5427  261.33  5432.2  265.38  5442.3  266.86
  5591.2  267.05  5830.1  269.62  5863.7  269.59  5964.3  271.14  6324.8  275.93
#Mann= 11 ,-1 , 0
  3717.6     .05       0  4741.7     .12       0  4961.3      .1       0
  4995.5     .07       0  5001.5      .1       0  5060.5     .16       0
  5325.3      .1       0  5591.2     .05       0  5830.1     .16       0
  5863.7      .1       0  5964.3     .05       0
Bank Sta=4938.4,5038.6
XS Rating Curve= 0 ,0
Exp/Cntr=0.3,0.1

Type RM Length L Ch R = 1 ,53581   ,687,687,687
BEGIN DESCRIPTION:
PANTHER CREEK 62.0
END DESCRIPTION:
XS GIS Cut Line= 3
      3618957.95     10226392.49      3617671.45     10226507.07
      3616290.15      10226745.4
#Sta/Elev= 30
  3897.7  278.55  4415.9  268.21  4636.5   264.6  4732.7   259.4    4787  261.78
  4817.2  260.83  4837.2  258.27  4844.3  258.36  4857.3  261.28  4947.7  259.43
  4977.8  260.25  5004.9  256.97  5007.7  256.47  5010.9  256.97    5028  261.19
  5109.1  261.11    5184  260.55    5280  264.07  5381.4   259.7  5452.5   261.9
  5614.8  263.66  5848.2  264.43  5878.7  265.47  5919.3  270.17    5948  266.44
  6081.6  266.24  6366.9  268.77  6487.5  271.89  6541.4  270.01    6591  271.61
#Mann= 5 ,-1 , 0
  3897.7     .05       0  4415.9     .16       0  5004.9     .07       0
  5010.9     .16       0  5109.1     .05       0
Bank Sta=4977.8,5028
XS Rating Curve= 0 ,0
Exp/Cntr=0.3,0.1

Type RM Length L Ch R = 1 ,52894   ,221,221,221
BEGIN DESCRIPTION:
PANTHER CREEK 61.0
END DESCRIPTION:
XS GIS Cut Line= 3
      3618858.98      10225835.2      3617681.87     10225913.32
      3616130.44      10225927.7
#Sta/Elev= 30
    4079  277.64  4286.3  275.06  4436.7  271.41  4609.3  270.52  4827.5  266.08
  4977.8  259.86  5004.9  256.53  5017.9  259.76    5038   259.9    5048  259.43
    5055  256.48  5057.8  255.98    5061  256.48    5068  258.97  5078.1  259.86
  5278.5   259.4  5308.5  260.87  5348.5  259.12  5568.5  258.47  5658.5  262.42
  5841.1  259.67  5858.5  261.04  5978.5  263.55  6139.5  265.64  6178.5  266.22
  6238.5  265.03  6448.5   266.6  6688.5   272.2  6765.7  272.78  6810.2   272.7
#Mann= 7 ,-1 , 0
    4079     .05       0  4609.3     .16       0    5055     .07       0
    5061     .16       0  5841.1     .05       0  6139.5     .16       0
  6765.7     .05       0
#XS Ineff= 1 ,-1
 5658.52 6011.36  262.51
Permanent Ineff=
       F
Bank Sta=4977.8,5038
XS Rating Curve= 0 ,0
Exp/Cntr=0.3,0.1

Type RM Length L Ch R = 1 ,52673   ,1635,1635,1635
BEGIN DESCRIPTION:
PANTHER CREEK 60.0
END DESCRIPTION:
XS GIS Cut Line= 3
      3618792.94     10225699.78      3617188.81     10225668.53
      3616241.55     10225670.75
#Sta/Elev= 30
    4120  276.02  4289.9  273.24  4440.9  269.33  4610.9  267.03  4790.2  263.27
    4861  261.47  4881.9  260.08    4961  258.95    4971  258.57    4991  255.56
    4998  255.54  5000.8  255.04    5004  255.54    5021  258.45    5031  258.77
    5141   258.8  5281.1  256.44    5312  257.62  5381.1  256.37  5401.1   257.4
  5521.1  256.39  5541.1  257.31  5651.1  258.06  5724.4  259.98  5761.1  262.98
  5871.1  263.31  5911.1   261.6  6241.1   264.1  6286.8  265.17  6671.7  270.19
#Mann= 6 ,-1 , 0
    4120     .05       0  4289.9     .08       0  4881.9     .05       0
    4998     .03       0    5004     .05       0  6286.8     .08       0
Bank Sta=4961,5031
XS Rating Curve= 0 ,0
Exp/Cntr=0.3,0.1

Type RM Length L Ch R = 1 ,51038   ,1716,1716,1716
BEGIN DESCRIPTION:
PANTHER CREEK 59.0
END DESCRIPTION:
XS GIS Cut Line= 3
      3618707.88     10225053.94      3617332.91     10224876.86
      3616140.18     10225168.54
#Sta/Elev= 30
  3848.6  268.32    4046  266.92  4106.5  265.49  4156.9  265.92  4308.1  262.63
    4419  262.04  4711.4  256.88  4802.2  257.66  4852.6  256.21  4901.9  256.61
  4943.3  257.82  4963.5  256.97  4983.7  254.29  4997.3  251.08    5000  250.58
  5003.3  251.08    5024  255.03  5044.2  255.96  5159.8   255.1  5237.9  253.72
  5379.9  257.79  5440.5   260.6  5523.8  262.33  5544.6  263.98  5660.1  263.22
  6213.7  263.66  6296.1  264.23  6337.3  266.44  6378.5  265.29  6462.8  266.74
#Mann= 6 ,-1 , 0
  3848.6     .05       0  4901.9     .16       0  4997.3     .07       0
  5003.3     .16       0  5159.8     .05       0  5660.1     .16       0
Bank Sta=4963.5,5044.2
XS Rating Curve= 0 ,0
Exp/Cntr=0.3,0.1

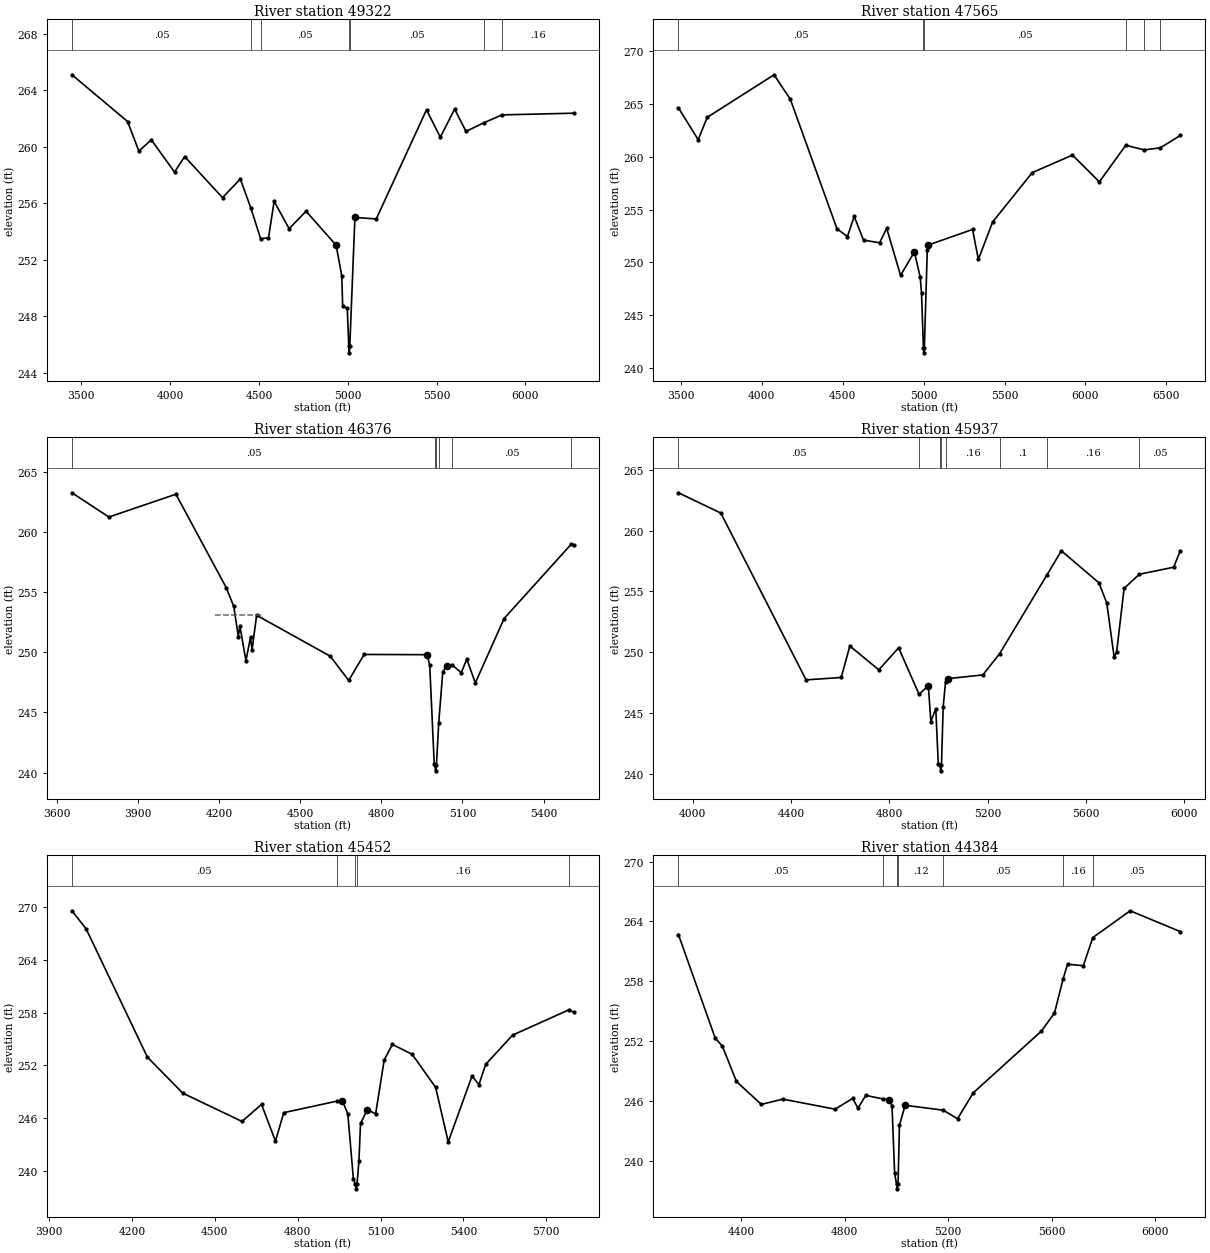
Type RM Length L Ch R = 1 ,49322   ,1757,1757,1757
BEGIN DESCRIPTION:
PANTHER CREEK 59.1
END DESCRIPTION:
XS GIS Cut Line= 3
      3618718.33     10224642.49      3617098.54      10224085.2
      3616181.85     10224715.42
#Sta/Elev= 30
  3447.2  265.11  3760.5   261.8  3823.9  259.71  3894.1   260.5  4024.8  258.22
  4081.5  259.32  4294.8  256.41    4395  257.73  4454.2  255.68  4509.2  253.51
  4553.6  253.55  4585.3  256.15  4669.9  254.21  4765.1  255.45  4934.3  253.04
    4966  250.88  4971.3  248.72  4997.3  248.57  5005.3  245.92  5008.1  245.42
  5011.3  245.92  5040.1  255.01  5160.2   254.9  5443.1  262.63  5520.9  260.69
  5601.4  262.68  5665.5   261.1  5765.7  261.71  5868.4  262.27  6272.6  262.39
#Mann= 7 ,-1 , 0
  3447.2     .05       0  4454.2     .12       0  4509.2     .05       0
  5005.3     .03       0  5011.3     .05       0  5765.7      .1       0
  5868.4     .16       0
Bank Sta=4934.3,5040.1
XS Rating Curve= 0 ,0
Exp/Cntr=0.3,0.1

Type RM Length L Ch R = 1 ,47565   ,1189,1189,1189
BEGIN DESCRIPTION:
PANTHER CREEK 58.0
END DESCRIPTION:
XS GIS Cut Line= 4
      3617978.76     10222001.82      3617711.63     10222737.93
       3617015.2     10223251.86      3616228.73     10224470.63
#Sta/Elev= 30
  3486.4  264.65  3608.5  261.63  3664.4  263.75  4077.1  267.78  4177.7  265.45
  4465.5  253.19  4529.9  252.45  4571.9  254.36  4629.3  252.11  4728.7  251.86
  4772.4  253.23    4858  248.77  4943.6     251  4979.1  248.61  4987.5  247.11
  4999.1  241.93  5001.9  241.43  5005.1  241.93    5023  251.15  5029.2  251.65
  5302.4  253.12  5338.7  250.28  5426.5  253.83  5671.3  258.51  5919.4  260.17
  6085.7  257.63  6248.6   261.1  6362.7  260.66  6462.1  260.86  6585.5  262.03
#Mann= 6 ,-1 , 0
  3486.4     .05       0  4999.1     .03       0  5005.1     .05       0
  6248.6     .16       0  6362.7      .1       0  6462.1     .16       0
Bank Sta=4943.6,5029.2
XS Rating Curve= 0 ,0
Exp/Cntr=0.3,0.1

Type RM Length L Ch R = 1 ,46376   ,439,439,439
BEGIN DESCRIPTION:
PANTHER CREEK 56.0
END DESCRIPTION:
XS GIS Cut Line= 3
      3617187.07     10221684.18      3616770.41     10222538.32
      3616484.11     10223397.21
#Sta/Elev= 30
  3656.1  263.29  3792.6  261.27  4040.5  263.17  4226.3   255.4  4254.4  253.83
  4271.3  251.31  4276.9   252.2  4299.4  249.32  4316.4  251.27  4321.9  250.19
  4338.9  253.09  4610.8  249.69  4679.3  247.67  4736.4  249.83  4969.2  249.81
  4978.9  248.94  4995.5  240.74  4997.8  240.64  5000.6  240.14  5003.8  240.64
  5012.2  244.14  5027.2  248.37  5042.1  248.91  5060.7  248.98  5095.7  248.31
  5115.9  249.44  5147.5  247.46  5253.8  252.82  5501.8     259  5511.8  258.92
#Mann= 6 ,-1 , 0
  3656.1     .05       0  4997.8     .03       0  5003.8     .05       0
  5012.2     .12       0  5060.7     .05       0  5501.8     .16       0
#XS Ineff= 1 ,-1
 4184.66 4357.95  253.08
Permanent Ineff=
       F
Bank Sta=4969.2,5042.1
XS Rating Curve= 0 ,0
Exp/Cntr=0.3,0.1

Type RM Length L Ch R = 1 ,45937   ,485,485,485
BEGIN DESCRIPTION:
PANTHER CREEK 55.0
END DESCRIPTION:
XS GIS Cut Line= 3
      3616546.45      10221642.5      3616384.99     10222434.16
      3616224.41     10223658.52
#Sta/Elev= 30
  3941.5  263.12  4114.1  261.45  4461.1  247.71    4604  247.91  4639.3   250.5
    4757  248.54  4837.7  250.35    4921  246.52  4958.7  247.23  4968.9  244.27
    4989  245.34  4999.1  240.81  5006.1  240.72  5008.9  240.22  5012.1  240.72
  5019.2  245.51  5028.9  247.57  5037.6  247.81  5180.6  248.12  5249.2  249.88
    5441  256.34  5500.2  258.34  5652.8  255.71  5684.9  254.05  5715.1  249.57
  5725.2  250.02  5755.5  255.25  5817.7  256.41  5957.2  256.99  5984.3  258.35
#Mann= 8 ,-1 , 0
  3941.5     .05       0    4921     .12       0  5006.1     .07       0
  5012.1     .12       0  5028.9     .16       0  5249.2      .1       0
    5441     .16       0  5817.7     .05       0
#XS Ineff= 1 ,-1
 5501.42 5988.64  258.18
Permanent Ineff=
       F
Bank Sta=4958.7,5037.6
XS Rating Curve= 0 ,0
Exp/Cntr=0.3,0.1

Type RM Length L Ch R = 1 ,45452   ,1068,1068,1068
BEGIN DESCRIPTION:
PANTHER CREEK 54.0
END DESCRIPTION:
XS GIS Cut Line= 3
      3615806.87      10221720.6      3615957.91     10222923.74
      3615749.58     10223491.44
#Sta/Elev= 30
  3982.7  269.57  4034.1  267.51  4255.9  252.93  4383.9  248.84  4598.5  245.62
  4669.1  247.56  4719.5  243.39  4749.7  246.62  4940.7  247.92  4961.4  247.99
  4981.5  246.49  5001.7  239.11  5008.8  238.46  5011.5  237.96  5014.8  238.46
  5021.8  241.13  5027.6  245.39  5052.1  246.96  5082.3  246.48  5113.1  252.58
  5142.8  254.38  5214.4  253.26  5299.6  249.49  5345.1   243.3  5431.3  250.78
  5456.4  249.81  5480.7  252.11  5578.4  255.44  5781.5   258.3    5800  258.04
#Mann= 5 ,-1 , 0
  3982.7     .05       0  4940.7     .16       0  5008.8     .07       0
  5014.8     .16       0  5781.5     .05       0
#XS Ineff= 1 ,-1
 5144.89 5600.85  254.32
Permanent Ineff=
       F
Bank Sta=4961.4,5052.1
XS Rating Curve= 0 ,0
Exp/Cntr=0.3,0.1

Type RM Length L Ch R = 1 ,44384   ,952,952,952
BEGIN DESCRIPTION:
PANTHER CREEK 52.0
END DESCRIPTION:
XS GIS Cut Line= 3
      3615542.11     10221891.63      3615280.83     10222408.11
      3615067.29     10223751.84
#Sta/Elev= 30
  4157.8  262.69  4299.9   252.3  4327.7  251.49    4382  247.95  4478.1  245.65
  4561.3  246.18  4762.9  245.17  4831.3  246.25  4851.6  245.28  4881.9  246.55
  4949.7  246.19  4973.1  246.12  4983.2   245.5  4993.3  238.74  5000.5  237.68
  5003.2  237.18  5006.5  237.68  5011.9  243.55  5033.8  245.56  5181.2  245.07
  5236.3  244.21  5297.1  246.81  5560.4     253    5611  254.82  5643.9   258.2
  5661.6  259.71  5722.4  259.56    5759  262.38  5903.4  265.07  6097.2  262.98
#Mann= 7 ,-1 , 0
  4157.8     .05       0  4949.7     .12       0  5000.5     .07       0
  5006.5     .12       0  5181.2     .05       0  5643.9     .16       0
    5759     .05       0
Bank Sta=4973.1,5033.8
XS Rating Curve= 0 ,0
Exp/Cntr=0.3,0.1

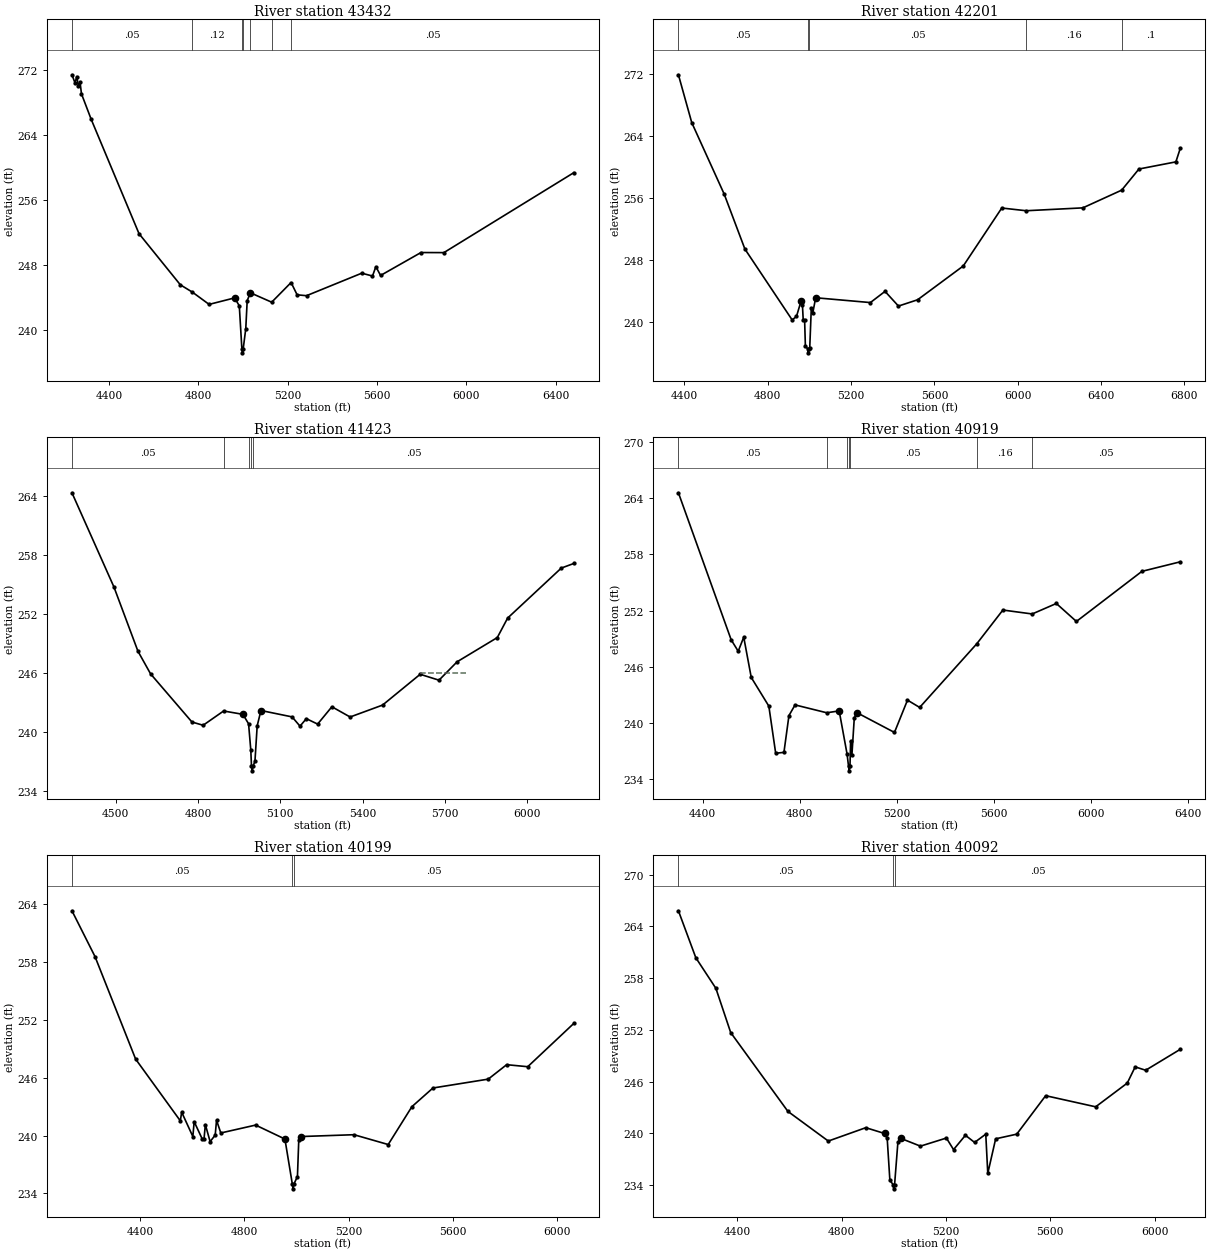
Type RM Length L Ch R = 1 ,43432   ,1231,1231,1231
BEGIN DESCRIPTION:
PANTHER CREEK 50.0
END DESCRIPTION:
XS GIS Cut Line= 3
      3615292.12     10221641.63      3614759.99     10222340.41
      3614009.99     10223486.25
#Sta/Elev= 30
  4234.3  271.37  4247.9  270.38  4256.1  271.15  4262.4  270.05  4270.7  270.43
    4277  269.02  4320.6  265.88  4534.7  251.82  4719.7  245.53  4774.1  244.62
  4848.6  243.12  4962.9  243.92  4983.8  242.94  4995.3  237.66  4998.1  237.16
  5001.3  237.66  5012.8  240.14  5019.1  243.57  5033.2  244.55  5128.8  243.39
  5215.7  245.81  5242.7   244.3  5284.8  244.19  5532.2  246.96  5580.3  246.61
  5595.4  247.76  5616.5  246.68  5797.4   249.5    5900  249.49  6482.1  259.33
#Mann= 7 ,-1 , 0
  4234.3     .05       0  4774.1     .12       0  4995.3     .07       0
  5001.3     .12       0  5033.2     .16       0  5128.8     .12       0
  5215.7     .05       0
Bank Sta=4962.9,5033.2
XS Rating Curve= 0 ,0
Exp/Cntr=0.3,0.1

Type RM Length L Ch R = 1 ,42201   ,778,778,778
BEGIN DESCRIPTION:
PANTHER CREEK 48.0
END DESCRIPTION:
XS GIS Cut Line= 3
      3614892.13     10221341.62      3614442.11     10221741.64
      3613092.14     10222941.61
#Sta/Elev= 30
  4371.7  271.87  4435.7  265.71  4591.2  256.52  4690.7  249.44  4917.4  240.32
  4938.3  240.77    4960  242.73  4966.7  242.26  4970.5  240.34  4977.2  240.34
  4980.9  236.98  4992.1  236.58  4994.9  236.08  4998.1  236.58  5001.8   236.7
  5009.3  241.81    5016  241.16  5030.3  243.17  5292.8  242.55  5363.1  243.99
  5427.5   242.1  5519.4  242.91  5738.5  247.26  5923.3  254.72  6040.4  254.37
  6312.2  254.74  6498.6  257.02  6581.4  259.74  6758.7  260.66    6780  262.42
#Mann= 5 ,-1 , 0
  4371.7     .05       0  4992.1     .03       0  4998.1     .05       0
  6040.4     .16       0  6498.6      .1       0
Bank Sta=4960,5030.3
XS Rating Curve= 0 ,0
Exp/Cntr=0.3,0.1

Type RM Length L Ch R = 1 ,41423   ,504,504,504
BEGIN DESCRIPTION:
PANTHER CREEK 47.0
END DESCRIPTION:
XS GIS Cut Line= 3
       3614742.1     10221091.65      3613864.16     10221481.03
      3613442.09     10222241.66
#Sta/Elev= 30
  4340.2  264.29  4493.3  254.72  4580.9  248.19    4627  245.89  4777.8     241
  4818.6  240.67  4893.3  242.12  4963.7  241.78  4984.3  240.82  4992.4  238.15
  4994.9  236.54  4997.7  236.04  5000.9  236.54  5007.5     237  5015.7  240.61
  5029.4  242.17    5143  241.52  5171.8  240.58    5195  241.34  5236.1  240.79
  5288.1  242.55  5354.6  241.51  5472.9  242.72  5610.1  245.85  5678.7  245.25
  5744.8  247.12  5891.3  249.58    5929  251.56  6124.7  256.64  6170.5  257.11
#Mann= 5 ,-1 , 0
  4340.2     .05       0  4893.3     .12       0  4984.3     .05       0
  4994.9     .03       0  5000.9     .05       0
#XS Ineff= 1 ,-1
 5612.22 5775.57  245.96
Permanent Ineff=
       F
Bank Sta=4963.7,5029.4
XS Rating Curve= 0 ,0
Exp/Cntr=0.3,0.1

Type RM Length L Ch R = 1 ,40919   ,720,720,720
BEGIN DESCRIPTION:
PANTHER CREEK 46.0
END DESCRIPTION:
XS GIS Cut Line= 3
       3614642.1     10220791.64      3613707.91     10221043.53
      3612708.42     10221506.84
#Sta/Elev= 30
  4299.5  264.59    4517  248.89    4546  247.67  4568.8  249.17  4599.8  244.87
  4672.3  241.81  4700.5  236.78  4734.5  236.87  4755.2   240.8  4780.4  241.94
  4911.1   241.1  4962.3   241.3  4994.9  236.68  5000.8   235.4  5003.5   234.9
  5006.8   235.4  5009.5   238.1  5014.7  236.57  5024.5  240.53  5034.8  241.12
  5190.2     239  5243.9  242.45  5294.1  241.67  5529.3  248.46  5637.2  252.07
    5758  251.65  5857.6  252.77  5940.3  250.85  6210.3   256.2  6368.7  257.22
#Mann= 7 ,-1 , 0
  4299.5     .05       0  4911.1     .12       0  4994.9     .05       0
  5000.8    .035       0  5006.8     .05       0  5529.3     .16       0
    5758     .05       0
Bank Sta=4962.3,5034.8
XS Rating Curve= 0 ,0
Exp/Cntr=0.3,0.1

Type RM Length L Ch R = 1 ,40199   ,107,107,107
BEGIN DESCRIPTION:
PANTHER CREEK 45.0
END DESCRIPTION:
XS GIS Cut Line= 3
       3614618.2     10220680.61      3613714.04     10220472.69
      3612726.83     10220605.04
#Sta/Elev= 30
  4139.1  263.34  4227.4  258.59  4383.2  247.94  4554.5  241.53  4559.7  242.43
  4602.5   239.9  4607.6  241.44  4637.9  239.68  4645.3  239.65  4650.5  241.14
  4668.7  239.37  4688.2  240.05  4693.3  241.59  4709.7  240.27  4843.1  241.09
  4955.4  239.64  4983.8  234.97  4986.5  234.47  4989.8  234.97  5003.4  235.74
  5008.5  239.54  5017.5   239.9  5220.1  240.09  5351.3  239.07  5442.1     243
  5522.8  244.94  5734.7  245.86  5805.3  247.36  5886.1  247.15  6062.9  251.65
#Mann= 3 ,-1 , 0
  4139.1     .05       0  4983.8     .03       0  4989.8     .05       0
Bank Sta=4955.4,5017.5
XS Rating Curve= 0 ,0
Exp/Cntr=0.3,0.1

Type RM Length L Ch R = 1 ,40092   ,629,629,629
BEGIN DESCRIPTION:
PANTHER CREEK 44.0
END DESCRIPTION:
XS GIS Cut Line= 3
      3614642.09     10220591.64      3613737.91     10220383.71
      3612750.52     10220516.09
#Sta/Elev= 30
  4174.3  265.81  4241.1  260.36  4317.9  256.82  4374.7  251.69    4594  242.55
  4748.9  239.11  4892.6  240.66  4964.4  239.99  4974.6  239.44  4984.9  234.57
    4997  234.07  4999.8  233.57    5003  234.07  5015.7  238.99  5025.9  239.43
  5102.1  238.52  5201.6  239.46    5229  238.12  5274.5  239.78  5309.7  238.95
  5352.5  239.91  5360.2  235.36  5390.4  239.37  5471.2  239.91  5582.1  244.37
  5773.8  243.08  5894.9  245.83  5925.2  247.71  5965.5  247.32  6098.3  249.75
#Mann= 3 ,-1 , 0
  4174.3     .05       0    4997     .03       0    5003     .05       0
Bank Sta=4964.4,5025.9
XS Rating Curve= 0 ,0
Exp/Cntr=0.3,0.1