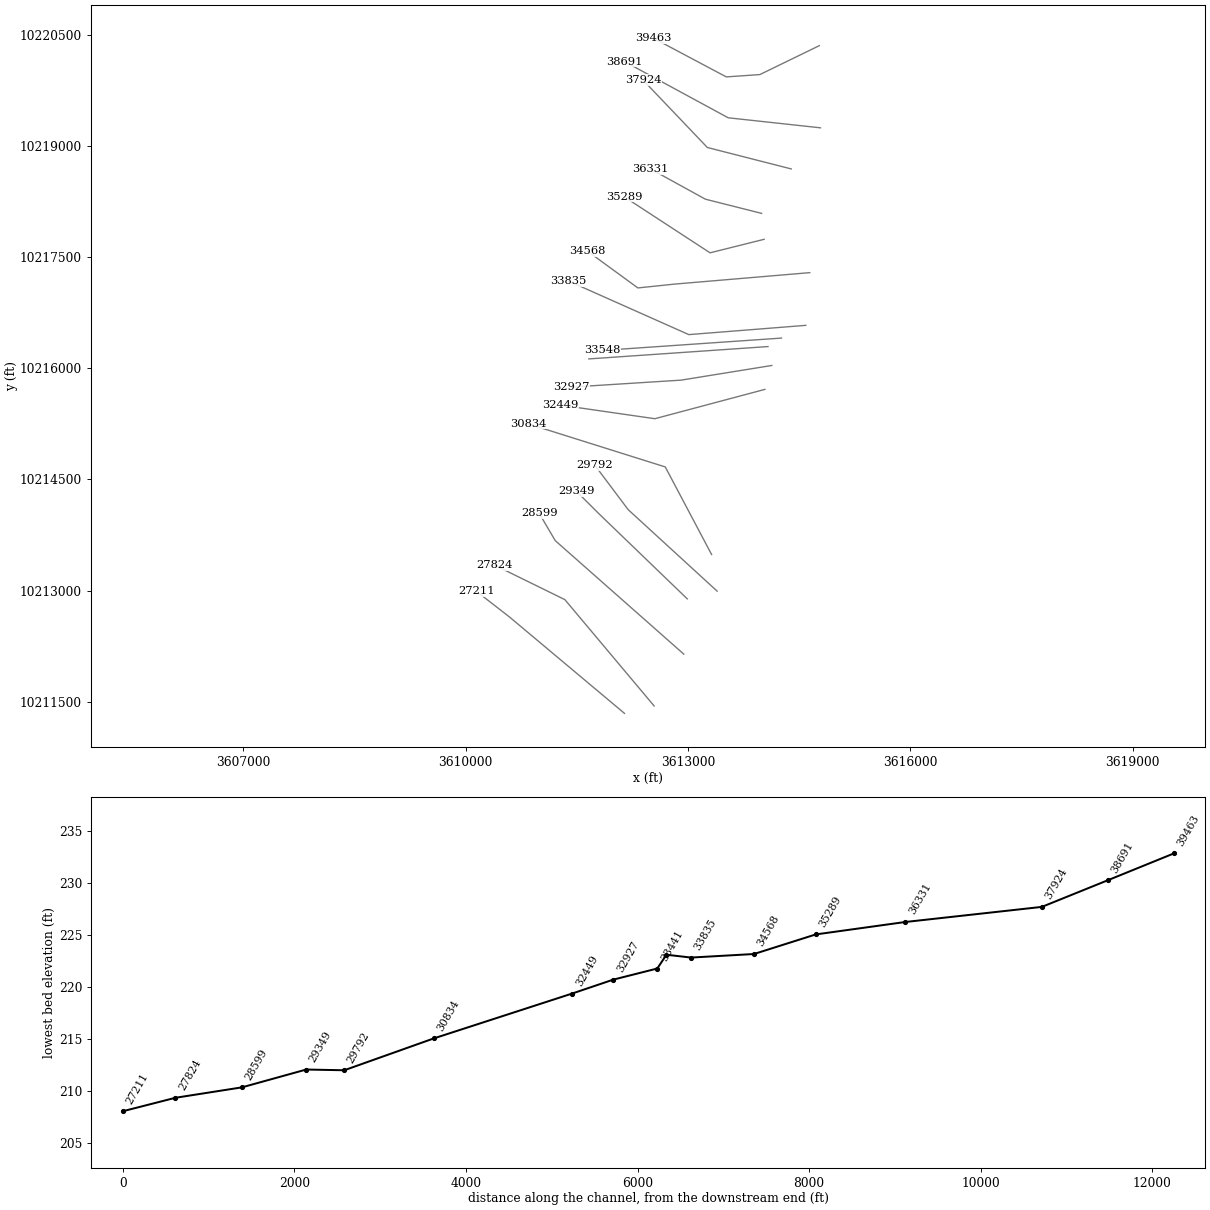
HEC-RAS study PANTHER CREEK.prj: PANTHER CREEK Base Level Engineering

--- PANTHER CREEK.g01 (geometry) --- (continued)

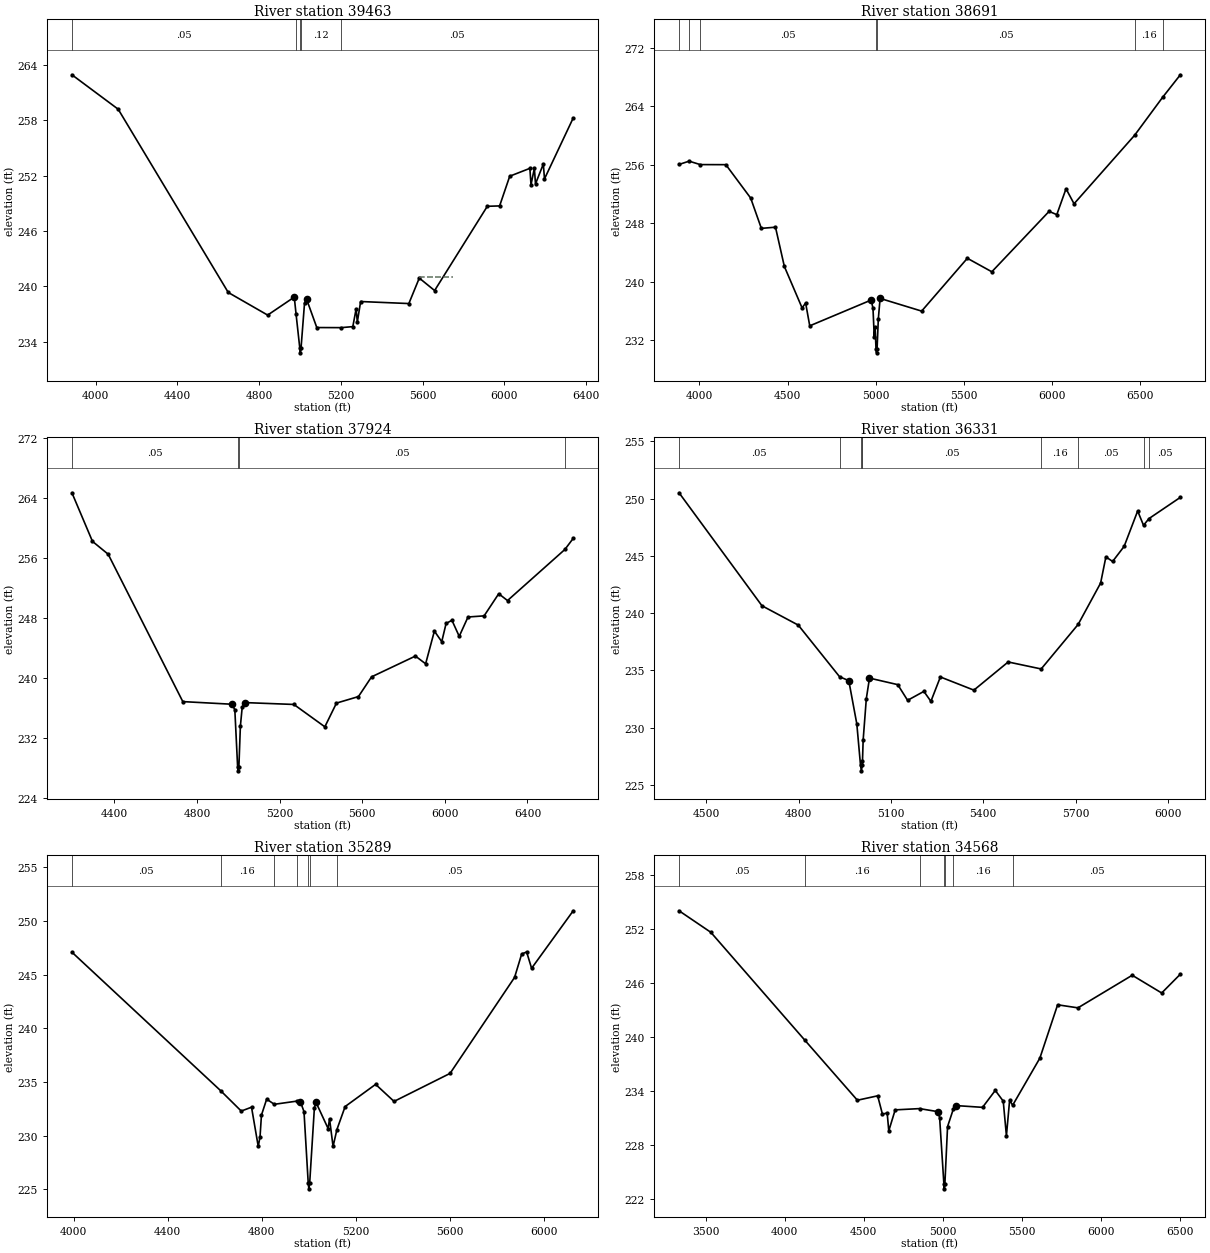
Type RM Length L Ch R = 1 ,39463   ,772,772,772
BEGIN DESCRIPTION:
PANTHER CREEK 43.0
END DESCRIPTION:
XS GIS Cut Line= 4
      3614770.39     10220356.02      3613968.33     10219965.41
       3613515.2     10219934.16      3612536.56     10220454.71
#Sta/Elev= 30
  3883.2  262.94  4109.7  259.21  4648.8  239.35  4841.7   236.9    4972  238.85
    4981  236.97  4999.1  233.31  5001.8  232.81  5005.1  233.31  5022.1  238.16
  5032.2  238.63  5082.3  235.55  5201.5  235.54  5258.7  235.65    5275  237.58
  5280.7  236.14    5297  238.37  5533.1  238.15  5584.2  240.91  5659.2  239.56
  5917.3  248.69  5977.5  248.73  6027.1  251.95  6125.7   252.8  6131.3  251.03
  6147.7   252.8  6153.3  251.12  6191.6  253.27  6197.3  251.66    6338  258.26
#Mann= 5 ,-1 , 0
  3883.2     .05       0    4981     .12       0  4999.1     .07       0
  5005.1     .12       0  5201.5     .05       0
#XS Ineff= 1 ,-1
 5586.36  5748.3  241.08
Permanent Ineff=
       F
Bank Sta=4972,5032.2
XS Rating Curve= 0 ,0
Exp/Cntr=0.3,0.1

Type RM Length L Ch R = 1 ,38691   ,767,767,767
BEGIN DESCRIPTION:
PANTHER CREEK 41.0
END DESCRIPTION:
XS GIS Cut Line= 3
      3614786.07     10219246.65      3613541.24     10219382.07
       3612142.1     10220141.64
#Sta/Elev= 30
    3884  256.05  3941.2   256.5  4004.5  256.03  4149.5  256.02  4290.4  251.44
    4351  247.29  4431.2  247.45  4481.5  242.07  4582.1  236.39  4602.2  237.06
  4625.5  233.93  4974.4  237.47  4984.4  236.31  4991.5  232.46  4996.5  233.78
  5001.5  230.73  5004.3  230.23  5007.5  230.73  5014.6  234.88  5024.7  237.69
  5260.4  235.95  5519.7  243.19  5658.6  241.34  5983.5  249.62  6027.2  249.17
  6079.6  252.72  6125.1  250.66  6468.4  260.04  6627.2  265.24  6728.2  268.34
#Mann= 7 ,-1 , 0
    3884     .05       0  3941.2     .16       0  4004.5     .05       0
  5001.5     .03       0  5007.5     .05       0  6468.4     .16       0
  6627.2     .05       0
Bank Sta=4974.4,5024.7
XS Rating Curve= 0 ,0
Exp/Cntr=0.3,0.1

Type RM Length L Ch R = 1 ,37924   ,1593,1593,1593
BEGIN DESCRIPTION:
PANTHER CREEK 40.0
END DESCRIPTION:
XS GIS Cut Line= 3
      3614392.08     10218691.65      3613259.99     10218981.03
      3612392.13     10219891.61
#Sta/Elev= 30
  4195.1  264.75  4294.6  258.27  4370.5  256.56  4731.8  236.91  4969.2  236.56
  4983.6  235.83  4997.2  228.18  4999.9  227.68  5003.2  228.18  5010.5  233.65
  5019.2  236.13  5031.1  236.78  5269.4  236.53  5419.3  233.55  5475.5  236.71
  5581.9  237.58  5645.4  240.21  5857.7  242.98  5907.1  241.95  5949.5  246.31
  5985.1   244.9  6006.2  247.33  6034.5  247.75  6069.7  245.61  6112.2  248.19
  6190.2  248.34  6260.9  251.29  6303.4  250.38    6581  257.19  6621.5  258.67
#Mann= 4 ,-1 , 0
  4195.1     .05       0  4997.2     .03       0  5003.2     .05       0
    6581     .16       0
Bank Sta=4969.2,5031.1
XS Rating Curve= 0 ,0
Exp/Cntr=0.3,0.1

Type RM Length L Ch R = 1 ,36331   ,1042,1042,1042
BEGIN DESCRIPTION:
PANTHER CREEK 39.0
END DESCRIPTION:
XS GIS Cut Line= 3
      3613992.09     10218091.65      3613233.95     10218283.11
      3612492.13     10218691.63
#Sta/Elev= 30
  4411.4  250.52  4680.8  240.65  4798.8  238.96    4933  234.45  4962.9  234.11
    4989  230.33    5001  226.73  5003.7  226.23    5007  226.73  5007.4  227.07
  5009.6  228.92  5019.9  232.54  5030.2  234.33    5122  233.76    5154  232.39
  5206.9  233.17  5229.7   232.3  5260.5  234.43  5369.4  233.28  5480.8  235.74
    5588  235.13  5708.1  239.02  5781.1  242.63  5798.3  244.92  5820.1  244.52
  5857.6  245.84  5901.5  248.93  5920.5  247.68  5938.5  248.27  6040.2  250.12
#Mann= 9 ,-1 , 0
  4411.4     .05       0    4933     .12       0    5001     .07       0
    5007     .12       0  5007.4     .05       0    5588     .16       0
  5708.1     .05       0  5920.5     .16       0  5938.5     .05       0
Bank Sta=4962.9,5030.2
XS Rating Curve= 0 ,0
Exp/Cntr=0.3,0.1

Type RM Length L Ch R = 1 ,35289   ,721,721,721
BEGIN DESCRIPTION:
PANTHER CREEK 37.0
END DESCRIPTION:
XS GIS Cut Line= 3
      3614025.67     10217741.46      3613296.45     10217559.16
      3612140.19     10218314.37
#Sta/Elev= 30
  3992.8   247.1    4625   234.2  4713.2  232.29  4756.9  232.65  4785.5  228.99
  4793.1  229.89  4799.1  231.91  4821.3   233.4  4853.9  232.92  4950.7  233.22
    4965  233.15  4980.1  232.24  4998.2  225.54  5000.9  225.04  5004.2  225.54
  5024.4  232.61  5031.4  233.09  5082.7  230.66  5088.7  231.58  5103.8  228.99
  5120.2  230.57  5155.1  232.71  5284.8  234.78  5363.2  233.19  5601.5   235.8
    5876  244.75  5906.2  246.93  5927.3  247.12  5948.4   245.6  6125.5  250.96
#Mann= 7 ,-1 , 0
  3992.8     .05       0    4625     .16       0  4853.9     .12       0
  4950.7     .16       0  4998.2     .07       0  5004.2     .16       0
  5120.2     .05       0
Bank Sta=4965,5031.4
XS Rating Curve= 0 ,0
Exp/Cntr=0.3,0.1

Type RM Length L Ch R = 1 ,34568   ,733,733,733
BEGIN DESCRIPTION:
PANTHER CREEK 36.0
END DESCRIPTION:
XS GIS Cut Line= 4
      3614642.07     10217291.64      3612822.49     10217137.28
      3612322.49      10217085.2      3611646.24     10217579.38
#Sta/Elev= 30
  3332.7  254.04  3533.4  251.65  4128.1  239.65  4459.1     233  4587.2  233.49
  4617.3  231.46  4647.4  231.58  4657.4   229.6  4697.9  231.93  4851.7  232.07
  4968.5  231.73  4978.6  231.06  5005.7  223.66  5008.4  223.16  5011.7  223.66
  5028.7  230.07  5065.6  232.04  5078.9  232.41  5249.7  232.21  5330.1  234.09
  5380.4   232.9  5400.5  229.06  5420.6  232.98  5440.1  232.45  5611.6  237.67
  5723.9   243.6  5852.2  243.26  6195.1  246.88  6381.2  244.91  6499.1     247
#Mann= 7 ,-1 , 0
  3332.7     .05       0  4128.1     .16       0  4851.7     .12       0
  5005.7     .07       0  5011.7     .12       0  5065.6     .16       0
  5440.1     .05       0
Bank Sta=4968.5,5078.9
XS Rating Curve= 0 ,0
Exp/Cntr=0.3,0.1

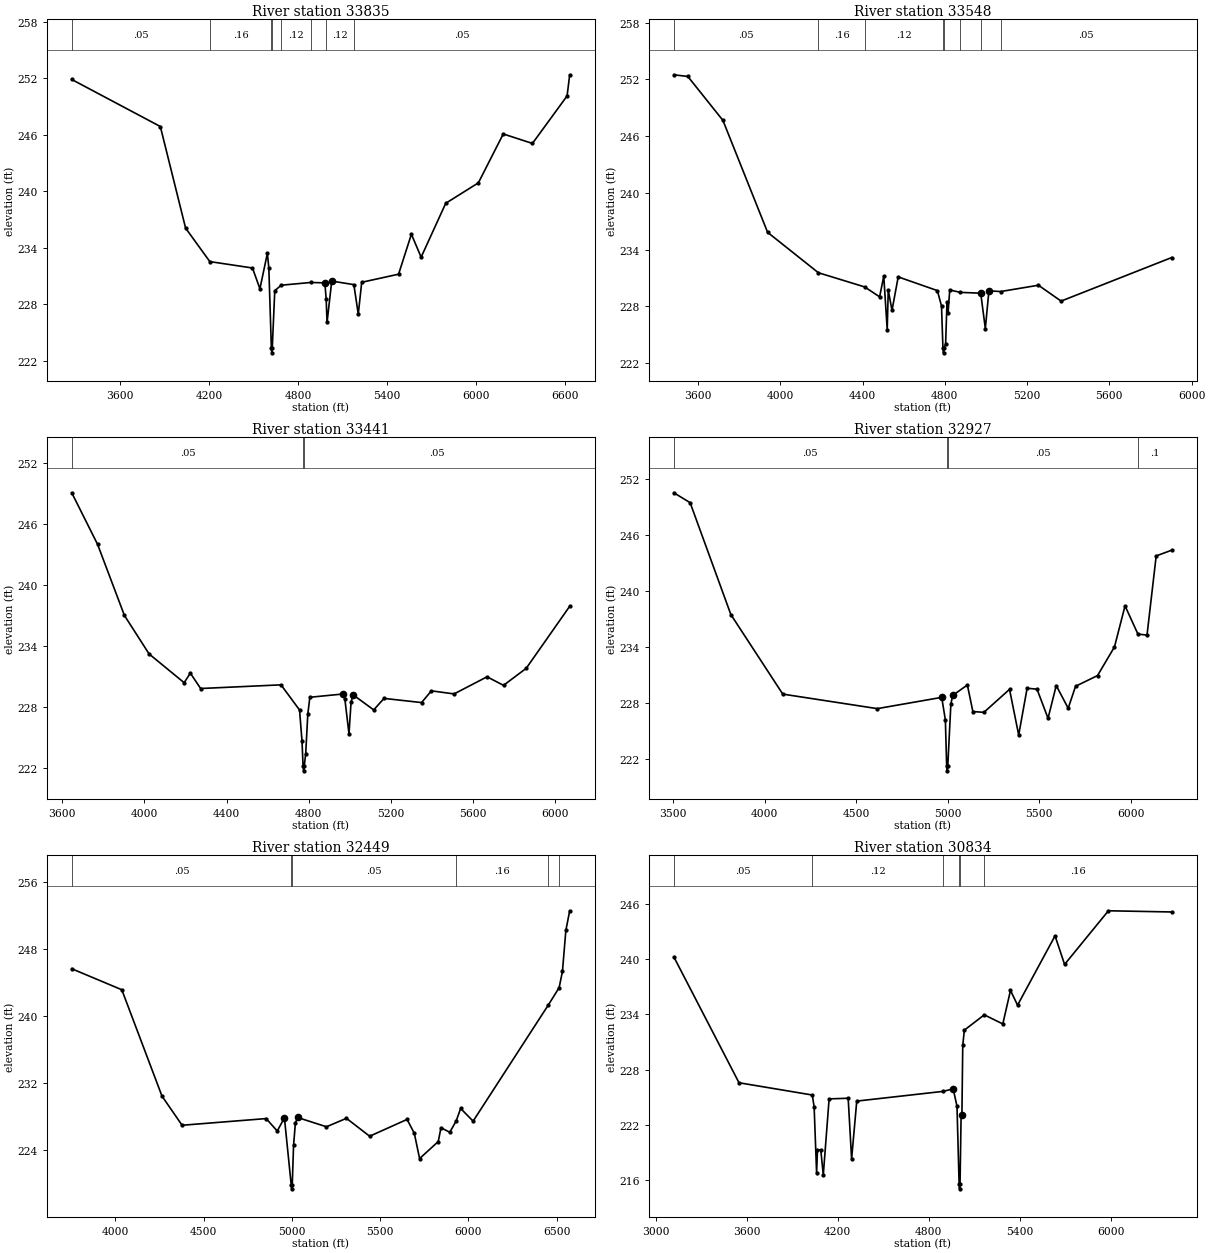
Type RM Length L Ch R = 1 ,33835   ,287,287,287
BEGIN DESCRIPTION:
PANTHER CREEK 35.0
END DESCRIPTION:
XS GIS Cut Line= 3
      3614588.14     10216579.99      3613009.99     10216454.99
      3611386.05     10217178.47
#Sta/Elev= 30
    3272  251.88  3869.9  246.88  4040.4  236.08  4203.9  232.52  4491.8  231.84
    4542  229.63  4592.2  233.39  4602.2  231.85  4619.3  223.32    4622  222.82
  4625.3  223.32  4642.3  229.43    4686  230.01    4885   230.3  4980.3  230.26
  4989.2  228.54  4995.1  226.05  5026.8  230.45  5176.1  230.07  5205.9  226.93
  5229.1  230.32  5477.9  231.18  5564.4  235.43  5630.1  232.99  5796.3  238.72
  6016.4  240.89  6184.5  246.09  6381.3  245.08  6615.3  250.13  6632.9  252.38
#Mann= 8 ,-1 , 0
    3272     .05       0  4203.9     .16       0  4619.3     .07       0
  4625.3     .16       0    4686     .12       0    4885     .16       0
  4989.2     .12       0  5176.1     .05       0
Bank Sta=4980.3,5026.8
XS Rating Curve= 0 ,0
Exp/Cntr=0.3,0.1

Type RM Length L Ch R = 1 ,33548   ,107,107,107
BEGIN DESCRIPTION:
PANTHER CREEK 34.0
END DESCRIPTION:
XS GIS Cut Line= 3
      3614259.98     10216408.11      3612749.58     10216303.95
      3611845.21     10216241.58
#Sta/Elev= 30
    3483  252.49    3551  252.31  3721.4  247.67  3938.7  235.83  4185.4  231.56
  4410.4  230.06  4483.2  229.01  4503.3   231.2  4520.1  225.54  4525.1  229.72
  4543.4  227.58  4573.5  231.12  4763.9  229.67    4784  228.04    4791  223.59
  4793.7  223.09    4797  223.59    4804  224.04  4810.7  228.46  4815.8  227.28
    4824  229.74  4876.2  229.48  4974.4   229.4  4974.9  229.36    4997  225.66
  5014.5  229.65  5071.1  229.57  5255.1  230.24  5365.3  228.56  5903.5  233.17
#Mann= 8 ,-1 , 0
    3483     .05       0  4185.4     .16       0  4410.4     .12       0
    4791     .07       0    4797     .12       0  4876.2     .16       0
  4974.9     .12       0  5071.1     .05       0
Bank Sta=4974.4,5014.5
XS Rating Curve= 0 ,0
Exp/Cntr=0.3,0.1

Type RM Length L Ch R = 1 ,33441   ,514,514,514
BEGIN DESCRIPTION:
PANTHER CREEK 34.1
END DESCRIPTION:
XS GIS Cut Line= 3
      3614077.65     10216293.53      3612567.29     10216189.36
      3611660.99     10216126.86
#Sta/Elev= 30
  3646.8  249.06  3772.6  243.99    3903  237.02  4023.2  233.24  4193.6  230.42
  4223.7  231.36  4273.8  229.85  4664.8  230.21    4755  227.74  4767.1  224.65
    4772  222.27  4774.8  221.77    4778  222.27    4785  223.47  4795.1  227.33
  4805.1  228.99  4965.5  229.31  4975.5   228.8  4995.5  225.41  5005.6  228.51
  5015.6  229.23  5115.8  227.75  5165.9  228.88  5348.5  228.47  5396.5  229.62
  5506.8  229.32  5667.1     231  5747.3  230.16  5857.6  231.83  6069.2  237.92
#Mann= 3 ,-1 , 0
  3646.8     .05       0    4772     .04       0    4778     .05       0
Bank Sta=4965.5,5015.6
XS Rating Curve= 0 ,0
Exp/Cntr=0.3,0.1

Type RM Length L Ch R = 1 ,32927   ,478,478,478
BEGIN DESCRIPTION:
PANTHER CREEK 33.0
END DESCRIPTION:
XS GIS Cut Line= 3
      3614129.76     10216038.32      3612905.83     10215840.41
      3611426.92     10215746.67
#Sta/Elev= 30
  3503.2  250.56    3592   249.5  3814.8  237.48  4098.5  228.94  4615.1  227.38
  4967.2  228.59  4987.2  226.17  4994.3   221.2    4997   220.7  5000.3   221.2
  5017.3  227.87  5027.3   228.8  5107.5  229.92  5137.5  227.07  5197.7  226.98
  5337.9  229.45    5388  224.55    5434  229.57  5488.2  229.47  5548.4  226.34
  5593.2  229.86  5658.6  227.42  5698.7  229.78  5818.9  230.93  5911.6  234.01
  5969.2  238.42  6039.8  235.38  6089.4  235.28  6139.5  243.78  6224.9   244.4
#Mann= 4 ,-1 , 0
  3503.2     .05       0  4994.3    .035       0  5000.3     .05       0
  6039.8      .1       0
Bank Sta=4967.2,5027.3
XS Rating Curve= 0 ,0
Exp/Cntr=0.3,0.1

Type RM Length L Ch R = 1 ,32449   ,1615,1615,1615
BEGIN DESCRIPTION:
PANTHER CREEK 32.0
END DESCRIPTION:
XS GIS Cut Line= 3
      3614036.05     10215715.41      3612551.66     10215319.57
       3611280.6     10215503.11
#Sta/Elev= 30
  3752.8  245.68  4036.3  243.17    4264  230.45  4377.8  226.97  4853.9  227.77
  4916.8  226.28  4957.4  227.86  4995.8  219.87  4998.6  219.37  5001.8  219.87
  5009.2  224.56  5019.5  227.23  5031.9   227.9  5195.5  226.79  5308.8   227.8
  5440.2  225.66  5652.3  227.67  5693.1  226.01  5723.1  222.99  5828.7  225.02
  5844.3  226.68    5894  226.13  5930.5  227.49  5955.5  228.98  6026.2  227.46
  6452.6  241.36  6513.5  243.42  6532.2  245.36  6551.6  250.27  6573.3  252.61
#Mann= 6 ,-1 , 0
  3752.8     .05       0  4995.8    .035       0  5001.8     .05       0
  5930.5     .16       0  6452.6     .05       0  6513.5     .16       0
Bank Sta=4957.4,5031.9
XS Rating Curve= 0 ,0
Exp/Cntr=0.3,0.1

Type RM Length L Ch R = 1 ,30834   ,1042,1042,1042
BEGIN DESCRIPTION:
PANTHER CREEK 31.0
END DESCRIPTION:
XS GIS Cut Line= 3
       3613317.3     10213486.21      3612692.29     10214668.53
      3610838.14     10215251.86
#Sta/Elev= 30
  3119.9  240.22  3549.2  226.57  4032.1  225.24  4044.2  223.94  4060.5  216.76
  4066.2   219.3  4088.2  219.25  4104.5  216.56  4142.9  224.82  4268.5  224.89
  4291.1   218.3    4325  224.58  4890.8  225.63  4960.6   225.9  4985.5  224.02
  4999.6  215.56  5002.3  215.06  5005.6  215.56  5012.6  223.02  5017.9  223.06
  5023.5  230.64    5034  232.28  5165.3  233.94  5287.4  232.95    5338  236.59
  5384.6  234.99  5631.6  242.51  5694.5  239.41  5983.3  245.23    6401   245.1
#Mann= 6 ,-1 , 0
  3119.9     .05       0  4032.1     .12       0  4890.8     .05       0
  4999.6     .03       0  5005.6     .05       0  5165.3     .16       0
Bank Sta=4960.6,5017.9
XS Rating Curve= 0 ,0
Exp/Cntr=0.3,0.1

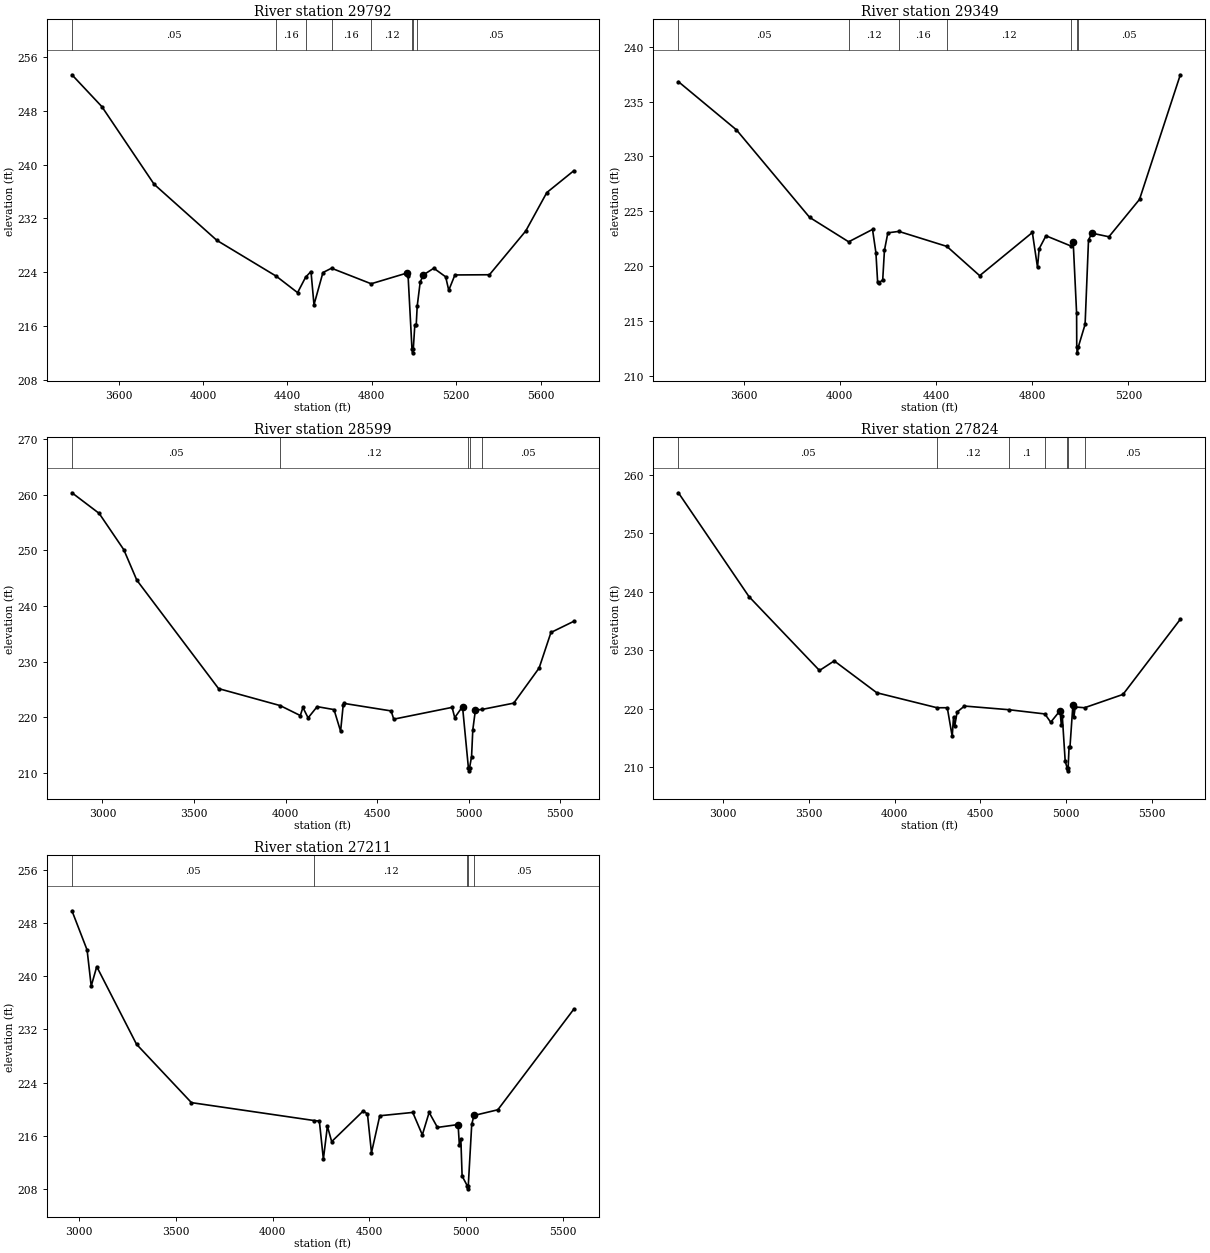
Type RM Length L Ch R = 1 ,29792   ,443,443,443
BEGIN DESCRIPTION:
PANTHER CREEK 30.0
END DESCRIPTION:
XS GIS Cut Line= 3
      3613392.14     10212991.61      3612192.11     10214091.64
      3611742.12     10214691.62
#Sta/Elev= 30
  3379.4  253.35    3521  248.62  3768.8  237.07  4066.1  228.73  4347.6   223.4
  4448.4  220.96  4486.5  223.26  4511.9   224.1  4526.1  219.16  4568.6  223.95
  4609.2  224.59    4797  222.28  4965.1  223.86  4971.9   223.5  4990.5  212.51
  4993.2  212.01  4996.5  212.51  5003.9  216.18  5010.5  216.18  5015.1  218.94
  5029.2  222.51  5043.8  223.59  5093.8  224.59    5150  223.31  5164.6  221.31
  5193.8  223.59  5357.3  223.62  5529.2  230.12  5629.2  235.84  5757.3  239.09
#Mann= 8 ,-1 , 0
  3379.4     .05       0  4347.6     .16       0  4486.5     .12       0
  4609.2     .16       0    4797     .12       0  4990.5     .07       0
  4996.5     .12       0  5015.1     .05       0
Bank Sta=4965.1,5043.8
XS Rating Curve= 0 ,0
Exp/Cntr=0.3,0.1

Type RM Length L Ch R = 1 ,29349   ,750,750,750
BEGIN DESCRIPTION:
PANTHER CREEK 29.0
END DESCRIPTION:
XS GIS Cut Line= 3
      3612989.14      10212887.3      3611792.11     10214041.64
      3611492.12     10214341.63
#Sta/Elev= 30
  3328.7  236.82  3570.2  232.42  3874.3  224.44  4036.7  222.21  4135.9  223.34
    4150  221.22  4157.2  218.51  4164.2  218.49  4178.3  218.74  4185.5  221.44
  4199.7  223.03  4245.3  223.16  4445.2  221.79  4581.5  219.12  4800.6  223.06
    4822  219.88  4828.9  221.58  4857.2  222.76  4961.9  221.82  4970.4   222.2
  4984.6   215.7  4985.2  212.58  4987.9  212.08  4991.2  212.58  5019.9  214.68
  5034.1  222.38  5048.2     223  5118.9  222.67  5246.2  226.08  5415.9  237.45
#Mann= 7 ,-1 , 0
  3328.7     .05       0  4036.7     .12       0  4245.3     .16       0
  4445.2     .12       0  4961.9     .05       0  4985.2     .03       0
  4991.2     .05       0
Bank Sta=4970.4,5048.2
XS Rating Curve= 0 ,0
Exp/Cntr=0.3,0.1

Type RM Length L Ch R = 1 ,28599   ,775,775,775
BEGIN DESCRIPTION:
PANTHER CREEK 27.0
END DESCRIPTION:
XS GIS Cut Line= 3
      3612942.11     10212141.63      3611207.91     10213673.74
      3610992.09     10214041.67
#Sta/Elev= 30
  2833.2  260.31  2981.7  256.61  3116.4  250.08  3187.5  244.61  3633.8  225.14
  3970.1  222.09  4080.1   220.3  4094.3  221.75  4122.7  219.88  4172.1   221.9
  4264.1  221.37  4300.1  217.48  4314.3  222.17    4321  222.47  4576.1  221.13
  4590.3  219.65  4909.1  221.77  4923.3  219.92  4965.9  221.91  4998.1  210.87
  5000.8  210.37  5004.1  210.87  5015.3  212.94    5022  217.73  5036.2  221.28
  5072.8   221.4  5245.5  222.53  5384.2  228.84  5448.7  235.22  5573.8  237.23
#Mann= 5 ,-1 , 0
  2833.2     .05       0  3970.1     .12       0  4998.1     .07       0
  5004.1     .12       0  5072.8     .05       0
Bank Sta=4965.9,5036.2
XS Rating Curve= 0 ,0
Exp/Cntr=0.3,0.1

Type RM Length L Ch R = 1 ,27824   ,613,613,613
BEGIN DESCRIPTION:
PANTHER CREEK 26.0
END DESCRIPTION:
XS GIS Cut Line= 3
      3612542.07     10211441.68      3611338.12     10212876.86
      3610392.13     10213341.63
#Sta/Elev= 30
  2739.5  256.92  3151.2  239.16  3562.3  226.53  3648.2  228.17  3896.6  222.72
    4248  220.16  4307.7  220.16  4336.4  215.25  4344.1  218.58  4350.7  216.96
    4365  219.43  4407.9  220.45  4667.8  219.82  4876.7   219.1  4910.9  217.68
  4964.9  219.64  4972.8  217.23  4978.4  218.77  4995.3  211.03  5006.5  209.87
  5009.2  209.37  5012.5  209.87  5017.8  213.38  5023.3  213.49  5040.2  220.62
  5045.8  218.55    5054  220.29  5108.1  220.16  5332.5  222.44  5666.8  235.29
#Mann= 7 ,-1 , 0
  2739.5     .05       0    4248     .12       0  4667.8      .1       0
  4876.7     .12       0  5006.5     .07       0  5012.5     .12       0
  5108.1     .05       0
Bank Sta=4964.9,5040.2
XS Rating Curve= 0 ,0
Exp/Cntr=0.3,0.1

Type RM Length L Ch R = 1 ,27211   ,553,553,553
BEGIN DESCRIPTION:
PANTHER CREEK 25.0
END DESCRIPTION:
XS GIS Cut Line= 3
       3612142.1     10211341.64      3610592.11     10212641.64
      3610142.09     10212991.65
#Sta/Elev= 30
  2962.9  249.82  3041.2  243.93  3062.4  238.51    3091  241.44  3296.6  229.78
  3580.2  221.02  4214.7  218.33  4241.1  218.25  4261.9  212.54  4282.7  217.48
  4304.8  215.17  4467.5  219.76  4489.6  219.33  4510.4   213.5  4553.3  219.05
  4723.7  219.55  4773.2  216.18  4808.3  219.55  4851.2   217.3  4957.9  217.73
  4964.4  214.69  4972.2  215.49  4978.7     210  5004.6  208.58  5007.4  208.08
  5010.6  208.58  5028.4  217.77    5040  219.09  5163.3  219.95    5556  235.06
#Mann= 5 ,-1 , 0
  2962.9     .05       0  4214.7     .12       0  5004.6     .07       0
  5010.6     .12       0    5040     .05       0
Bank Sta=4957.9,5040
XS Rating Curve= 0 ,0
Exp/Cntr=0.3,0.1