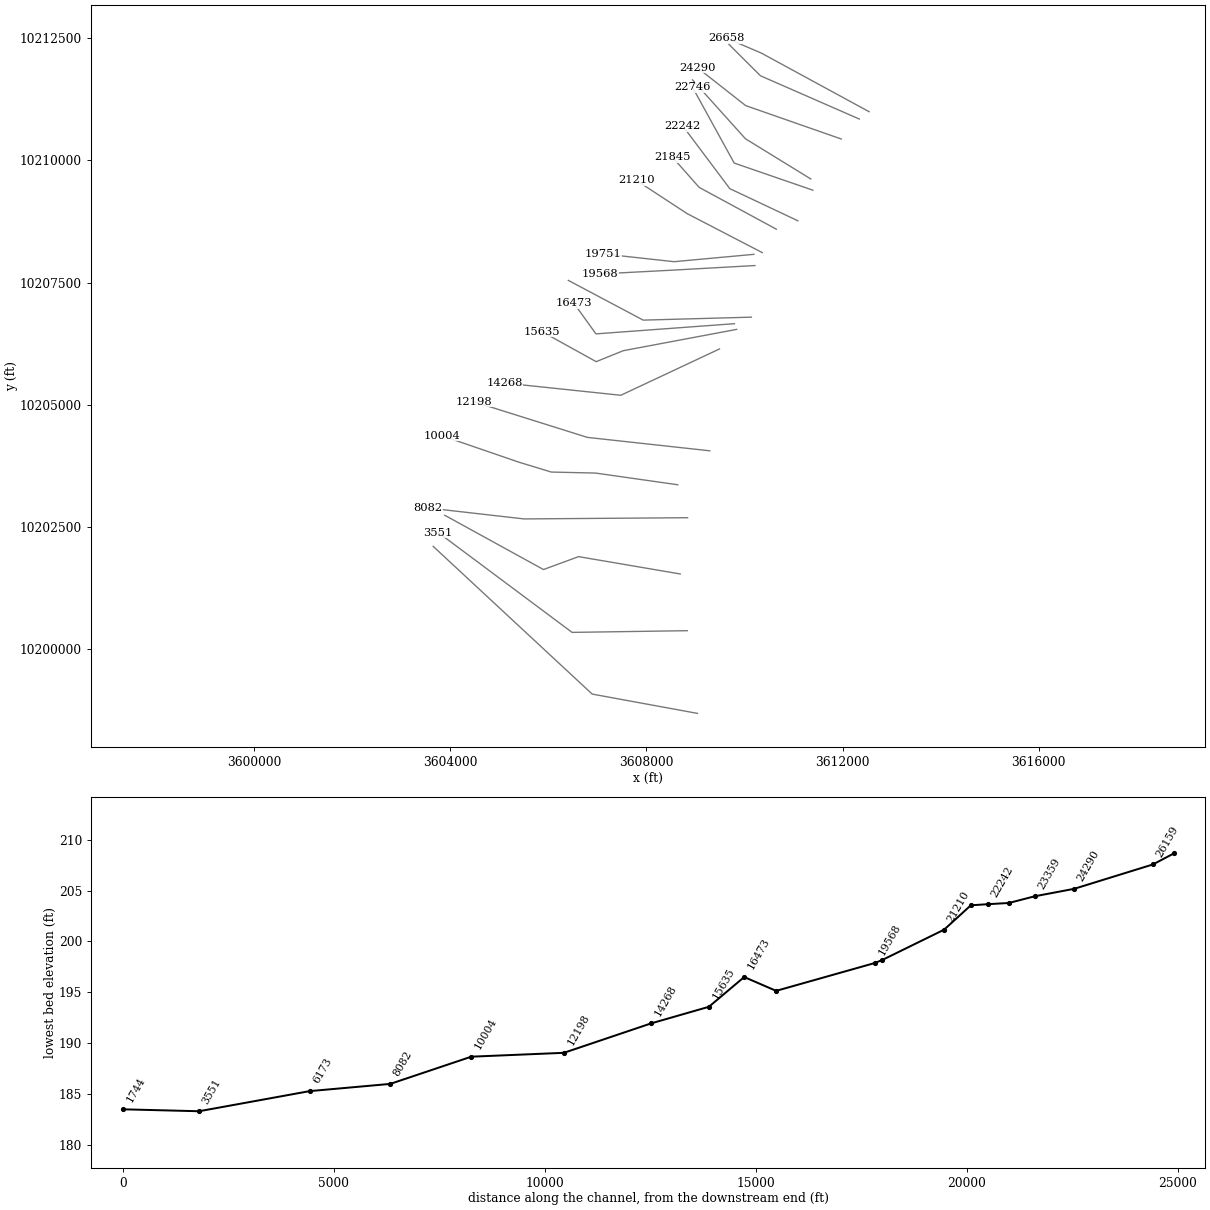
HEC-RAS study PANTHER CREEK.prj: PANTHER CREEK Base Level Engineering

--- PANTHER CREEK.g01 (geometry) --- (continued)

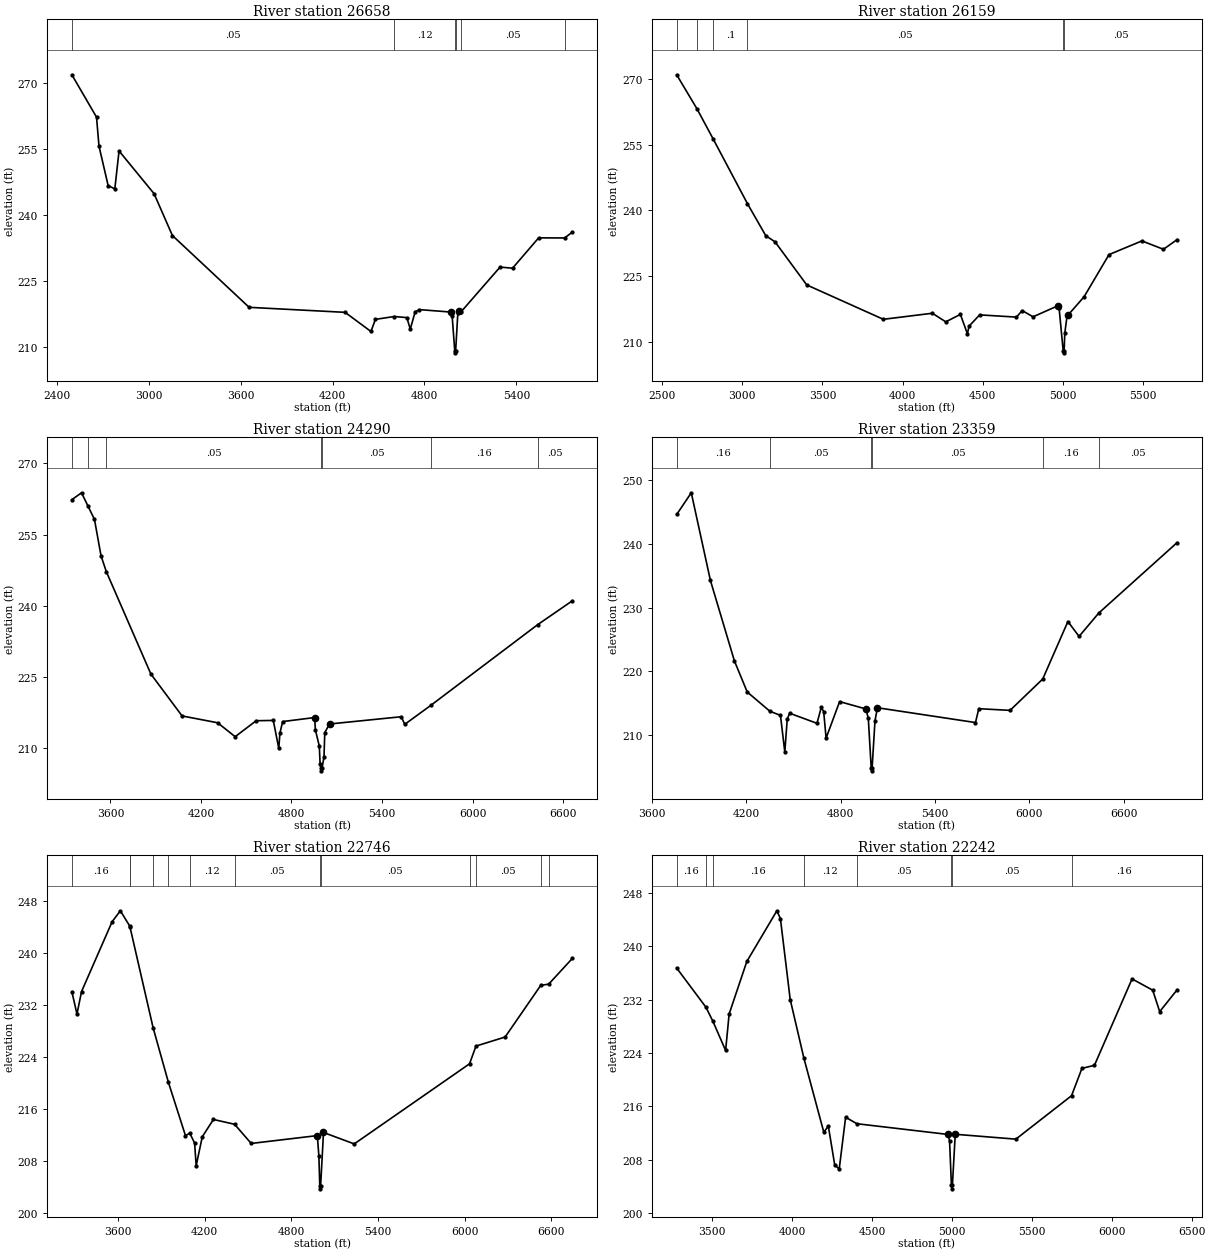
Type RM Length L Ch R = 1 ,26658   ,499,499,499
BEGIN DESCRIPTION:
PANTHER CREEK 24.0
END DESCRIPTION:
XS GIS Cut Line= 3
      3612542.12     10210991.63      3610342.11     10212191.64
       3609642.1     10212491.65
#Sta/Elev= 30
  2497.4  271.96  2658.3  262.32  2674.5  255.71  2734.3  246.73  2777.9  245.98
  2805.4  254.62  3034.2  244.89  3153.8  235.37    3655  219.02  4281.5  217.88
  4450.5  213.52  4479.4  216.28  4602.5  216.93  4684.9  216.68  4707.3  214.05
    4739     218  4766.6   218.5  4973.5  217.94  4980.6  217.09  4997.6  209.16
  5000.3  208.66  5003.6  209.16  5017.9  217.77  5025.2  218.25  5039.4  218.02
  5293.5  228.18  5375.1  227.93  5545.6  234.84  5714.8  234.81    5765  236.13
#Mann= 6 ,-1 , 0
  2497.4     .05       0  4602.5     .12       0  4997.6     .07       0
  5003.6     .12       0  5039.4     .05       0  5714.8     .16       0
Bank Sta=4973.5,5025.2
XS Rating Curve= 0 ,0
Exp/Cntr=0.3,0.1

Type RM Length L Ch R = 1 ,26159   ,1869,1869,1869
BEGIN DESCRIPTION:
PANTHER CREEK 23.0
END DESCRIPTION:
XS GIS Cut Line= 3
      3612342.07     10210841.66       3610327.7     10211725.82
        3609677.     10212376.52
#Sta/Elev= 30
  2590.7  270.92  2717.9  263.13  2819.1  256.24  3032.3  241.54  3146.3  234.26
    3204  232.86  3401.8  223.04  3879.3  215.21  4185.1  216.59  4268.6  214.63
  4359.8  216.33  4403.5  211.92  4414.2  213.66    4480  216.22  4709.3  215.71
  4745.2   217.2  4812.8  215.78  4968.3   218.3  4975.4  217.74  5000.7  208.07
  5003.5  207.57  5006.7  208.07  5010.8  212.05  5024.9  215.97    5032  216.21
    5131  220.34  5286.5  229.95  5491.6  233.07    5626  231.16  5710.8  233.36
#Mann= 6 ,-1 , 0
  2590.7     .05       0  2717.9     .16       0  2819.1      .1       0
  3032.3     .05       0  5000.7     .03       0  5006.7     .05       0
Bank Sta=4968.3,5032
XS Rating Curve= 0 ,0
Exp/Cntr=0.3,0.1

Type RM Length L Ch R = 1 ,24290   ,931,931,931
BEGIN DESCRIPTION:
PANTHER CREEK 22.0
END DESCRIPTION:
XS GIS Cut Line= 3
       3611973.5     10210434.17      3610025.62     10211116.45
      3609042.11     10211891.64
#Sta/Elev= 30
  3344.6  262.35  3408.5  263.81  3452.5  260.93  3494.4  258.19  3537.8  250.52
  3572.7  247.19  3868.5  225.57    4075  216.75  4310.3  215.31  4426.8  212.37
    4566  215.74  4679.5   215.8  4715.8  209.91  4723.5  213.14  4741.5  215.56
  4953.3  216.41  4958.6  213.79  4984.4  210.39  4989.7  206.66    4996  205.67
  4998.8  205.17    5002  205.67  5015.4  208.07  5020.7  213.24    5052  215.05
  5527.9  216.58  5550.5  214.97  5724.4     219  6430.8  235.98  6660.8  241.02
#Mann= 7 ,-1 , 0
  3344.6     .16       0  3452.5      .1       0  3572.7     .05       0
    4996     .03       0    5002     .05       0  5724.4     .16       0
  6430.8     .05       0
Bank Sta=4953.3,5052
XS Rating Curve= 0 ,0
Exp/Cntr=0.3,0.1

Type RM Length L Ch R = 1 ,23359   ,613,613,613
BEGIN DESCRIPTION:
PANTHER CREEK 20.0
END DESCRIPTION:
XS GIS Cut Line= 3
      3611353.78     10209616.42      3610020.41     10210439.36
      3608942.09     10211641.66
#Sta/Elev= 30
  3758.2  244.58  3851.1  247.98  3972.8  234.25  4125.4  221.65  4206.7  216.79
  4350.4  213.78  4418.2  213.12  4445.8  207.39  4461.2  212.52  4476.6  213.46
  4650.4  211.88  4677.6  214.37    4693  213.73  4708.4  209.56  4794.3  215.28
  4961.4  214.13  4976.8  212.67  4995.1  204.94  4997.8  204.44  5001.1  204.94
  5019.3  212.28  5034.7  214.32  5658.4     212  5679.3  214.17  5878.2  213.91
    6086  218.82    6246  227.82    6317  225.49  6442.3  229.15  6940.1  240.17
#Mann= 6 ,-1 , 0
  3758.2     .16       0  4350.4     .05       0  4995.1     .03       0
  5001.1     .05       0    6086     .16       0  6442.3     .05       0
Bank Sta=4961.4,5034.7
XS Rating Curve= 0 ,0
Exp/Cntr=0.3,0.1

Type RM Length L Ch R = 1 ,22746   ,504,504,504
BEGIN DESCRIPTION:
PANTHER CREEK 19.0
END DESCRIPTION:
XS GIS Cut Line= 3
       3611395.4     10209387.28      3609792.11     10209941.64
       3608942.1     10211491.65
#Sta/Elev= 30
  3281.5   234.1  3316.7  230.66  3348.5  234.13  3560.2  244.87  3617.2  246.55
  3682.8  244.17  3683.9  244.05    3844  228.55  3949.8  220.16    4068  211.96
  4097.9  212.34  4131.3  210.81    4142  207.34  4184.4  211.79  4261.3  214.45
  4408.1  213.71  4522.9  210.76  4980.8  211.97  4991.7  208.76  4997.7  204.28
  5000.5  203.78  5003.7  204.28  5023.5  212.45  5236.2  210.69  6034.5  223.01
  6079.1  225.74  6280.8  227.13  6527.3  235.07  6582.7  235.27  6745.7  239.21
#Mann= 13 ,-1 , 0
  3281.5     .16       0  3682.8      .1       0  3683.9     .16       0
    3844      .1       0  3949.8     .05       0  4097.9     .12       0
  4408.1     .05       0  4997.7     .03       0  5003.7     .05       0
  6034.5     .16       0  6079.1     .05       0  6527.3     .16       0
  6582.7     .05       0
Bank Sta=4980.8,5023.5
XS Rating Curve= 0 ,0
Exp/Cntr=0.3,0.1

Type RM Length L Ch R = 1 ,22242   ,397,397,397
BEGIN DESCRIPTION:
PANTHER CREEK 18.0
END DESCRIPTION:
XS GIS Cut Line= 3
      3611088.96     10208762.48       3609702.7     10209418.53
      3608745.54     10210698.21
#Sta/Elev= 30
    3277  236.72  3460.2  230.85  3503.1  228.78  3583.3  224.38  3605.4  229.84
  3716.1   237.7  3904.1  245.29  3926.3  244.11  3987.6     232  4073.6  223.19
  4197.9  212.13  4226.2  213.06  4266.1  207.25  4294.4  206.63  4334.4  214.38
  4404.6  213.41  4976.9   211.8    4985  210.78  4996.6  204.16  4999.4  203.66
  5002.6  204.16  5020.5  211.83  5399.8   211.1  5748.2   217.6  5813.6   221.7
  5891.6  222.15  6127.1  235.09  6256.4   233.4  6300.1  230.19  6408.7  233.45
#Mann= 8 ,-1 , 0
    3277     .16       0  3460.2      .1       0  3503.1     .16       0
  4073.6     .12       0  4404.6     .05       0  4996.6     .03       0
  5002.6     .05       0  5748.2     .16       0
Bank Sta=4976.9,5020.5
XS Rating Curve= 0 ,0
Exp/Cntr=0.3,0.1

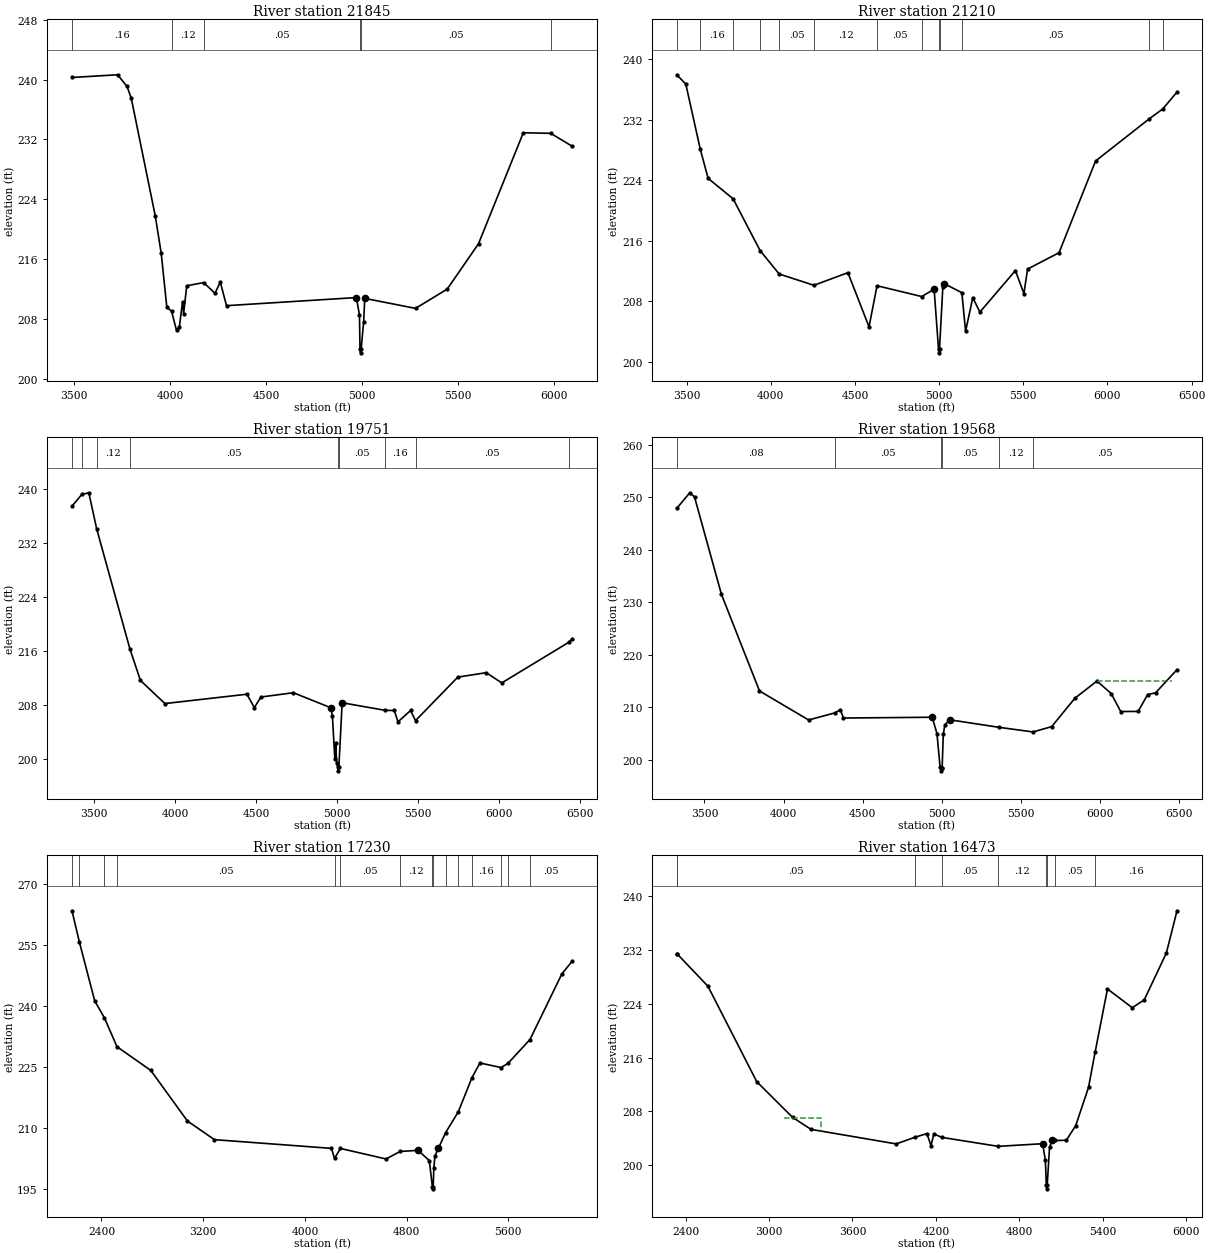
Type RM Length L Ch R = 1 ,21845   ,635,635,635
BEGIN DESCRIPTION:
PANTHER CREEK 17.0
END DESCRIPTION:
XS GIS Cut Line= 3
      3610650.62      10208590.4       3609077.7     10209444.57
      3608537.69     10210057.28
#Sta/Elev= 30
  3488.8  240.27  3726.1  240.63  3775.8  239.07  3797.6   237.5  3923.1  221.75
  3953.7  216.82    3983   209.6  4007.4  209.12  4033.3  206.54  4048.5  207.06
  4064.7  210.37  4070.4  208.78  4086.6  212.49  4174.7  212.92  4233.9  211.49
  4261.4  212.99  4293.8  209.84  4970.4  210.92  4986.6  208.59  4989.3  204.05
    4992  203.55  4995.3  204.05  5008.4   207.7  5014.1  210.81  5278.7  209.48
  5443.7  212.05  5606.8   218.1  5840.2   232.9    5983  232.82  6095.4  231.09
#Mann= 6 ,-1 , 0
  3488.8     .16       0  4007.4     .12       0  4174.7     .05       0
  4989.3     .03       0  4995.3     .05       0    5983     .16       0
Bank Sta=4970.4,5014.1
XS Rating Curve= 0 ,0
Exp/Cntr=0.3,0.1

Type RM Length L Ch R = 1 ,21210   ,1459,1459,1459
BEGIN DESCRIPTION:
PANTHER CREEK 16.0
END DESCRIPTION:
XS GIS Cut Line= 3
      3610364.17     10208111.24      3608832.91     10208908.11
      3607792.09     10209591.65
#Sta/Elev= 30
  3441.6  237.95  3495.6  236.73  3581.1  228.15  3628.3  224.24  3776.6  221.54
  3936.8  214.69  4050.4  211.58  4256.5  210.09  4458.5  211.76  4583.9  204.59
  4631.4  210.03  4896.9   208.6  4970.5  209.57  4996.6  201.65  4999.4  201.15
  5002.6  201.65  5022.2  209.86  5031.2   210.3  5135.3  209.11  5157.4     204
  5200.1  208.46  5242.3  206.54  5453.2  212.04  5503.7     209  5525.6  212.24
  5712.4   214.4  5929.3  226.54  6248.3  232.12  6328.5  233.43    6413  235.66
#Mann= 13 ,-1 , 0
  3441.6      .1       0  3581.1     .16       0  3776.6     .12       0
  3936.8     .16       0  4050.4     .05       0  4256.5     .12       0
  4631.4     .05       0  4896.9     .12       0  4996.6     .07       0
  5002.6     .12       0  5135.3     .05       0  6248.3     .16       0
  6328.5     .05       0
Bank Sta=4970.5,5031.2
XS Rating Curve= 0 ,0
Exp/Cntr=0.3,0.1

Type RM Length L Ch R = 1 ,19751   ,183,183,183
BEGIN DESCRIPTION:
PANTHER CREEK 13.0
END DESCRIPTION:
XS GIS Cut Line= 3
       3610193.7     10208075.92      3608564.33     10207925.49
      3607119.21     10208085.02
#Sta/Elev= 30
  3363.7  237.53  3424.7  239.27  3467.7  239.51  3516.5  234.11  3721.1  216.32
  3786.5  211.61  3937.7  208.18  4444.2  209.57  4490.1  207.57  4530.2  209.15
  4731.1  209.79  4962.1  207.56  4972.1  206.31  4987.3  199.88  4992.4  202.36
  4998.6  199.29  5005.9  198.68  5008.6  198.18  5011.9  198.68  5032.4   208.3
  5298.5  207.17  5354.4  207.15  5377.3  205.46    5455  207.15  5485.5  205.64
  5746.7  212.11  5922.3  212.77  6018.4  211.25  6431.2  217.27  6453.9  217.83
#Mann= 9 ,-1 , 0
  3363.7      .1       0  3424.7     .16       0  3516.5     .12       0
  3721.1     .05       0  5005.9     .04       0  5011.9     .05       0
  5298.5     .16       0  5485.5     .05       0  6431.2     .16       0
Bank Sta=4962.1,5032.4
XS Rating Curve= 0 ,0
Exp/Cntr=0.3,0.1

Type RM Length L Ch R = 1 ,19568   ,2338,2338,2338
BEGIN DESCRIPTION:
PANTHER CREEK 12.0
END DESCRIPTION:
XS GIS Cut Line= 3
      3610214.55     10207846.76      3608541.88      10207752.9
       3607056.9     10207675.32
#Sta/Elev= 30
  3324.7  247.86  3407.3  250.84  3437.3  250.05  3607.6  231.48    3848  213.09
  4158.4  207.56  4325.9  208.92  4358.8  209.52  4378.8  207.93  4939.7  208.08
  4969.7  204.98  4989.8  198.52  4994.4  198.37  4997.1  197.87  5000.4  198.37
  5002.4  198.37  5009.8  204.81  5019.8  206.62  5049.8   207.6  5359.5  206.17
  5577.4  205.28  5695.3   206.3  5840.9  211.68  5981.1  214.98  6071.2  212.59
  6131.3  209.17  6241.5  209.19  6301.5   212.4  6351.6  212.73    6487  217.14
#Mann= 6 ,-1 , 0
  3324.7     .08       0  4325.9     .05       0  4994.4    .035       0
  5000.4     .05       0  5359.5     .12       0  5577.4     .05       0
#XS Ineff= 1 ,-1
 5986.93 6452.27  215.06
Permanent Ineff=
       F
Bank Sta=4939.7,5049.8
XS Rating Curve= 0 ,0
Exp/Cntr=0.3,0.1

Type RM Length L Ch R = 1 ,17230   ,757,757,757
BEGIN DESCRIPTION:
PANTHER CREEK 11.0
END DESCRIPTION:
XS GIS Cut Line= 3
      3610142.13     10206791.64      3607937.08     10206731.03
      3606410.88     10207543.34
#Sta/Elev= 30
  2168.3  263.48    2226  255.85  2346.8  241.34  2423.3  237.17    2522  230.07
  2788.6  224.22  3075.9  211.81  3288.8  207.22  4209.1  205.08    4233   202.6
  4279.4  205.06  4638.1  202.47    4749  204.32  4889.6  204.59  4978.3  202.09
  5002.9  195.63  5005.7  195.13  5008.9  195.63  5014.2  200.18  5022.3  203.15
  5049.9   205.1  5107.4  208.97  5206.6  214.08  5313.5  222.42  5376.7  226.07
  5541.9  224.95  5596.2  225.94  5770.3  231.83  6020.9  247.95  6103.1  251.13
#Mann= 15 ,-1 , 0
  2168.3      .1       0    2226     .05       0  2423.3      .1       0
    2522     .05       0    4233     .12       0  4279.4     .05       0
    4749     .12       0  5002.9     .07       0  5008.9     .12       0
  5107.4     .05       0  5206.6     .12       0  5313.5     .16       0
  5541.9     .05       0  5596.2     .16       0  5770.3     .05       0
Bank Sta=4889.6,5049.9
XS Rating Curve= 0 ,0
Exp/Cntr=0.3,0.1

Type RM Length L Ch R = 1 ,16473   ,838,838,838
BEGIN DESCRIPTION:
PANTHER CREEK 9.0
END DESCRIPTION:
XS GIS Cut Line= 3
      3609796.48     10206658.12      3606973.54     10206449.78
      3606526.35     10207073.76
#Sta/Elev= 30
  2335.7  231.43  2338.7  231.43  2560.7  226.61  2911.6  212.42  3169.1  207.12
  3302.2  205.33  3914.4  203.17  4053.1  204.19    4135   204.7    4165  202.92
  4185.1  204.65  4243.1  204.14  4648.2  202.81  4967.2   203.2  4987.3  200.76
  4994.3  196.99    4997  196.49  5000.3  196.99  5017.4  202.68  5037.4  203.68
  5056.6  203.68  5137.7  203.71  5205.5  205.89  5297.7  211.58  5344.6  216.77
    5434  226.21  5612.1  223.43  5698.1  224.58  5857.6  231.56    5934  237.84
#Mann= 9 ,-1 , 0
  2335.7      .1       0  2338.7     .05       0  4053.1     .12       0
  4243.1     .05       0  4648.2     .12       0  4994.3     .07       0
  5000.3     .12       0  5056.6     .05       0  5344.6     .16       0
#XS Ineff= 1 ,-1
 3109.09    3375  207.02
Permanent Ineff=
       F
Bank Sta=4967.2,5037.4
XS Rating Curve= 0 ,0
Exp/Cntr=0.3,0.1

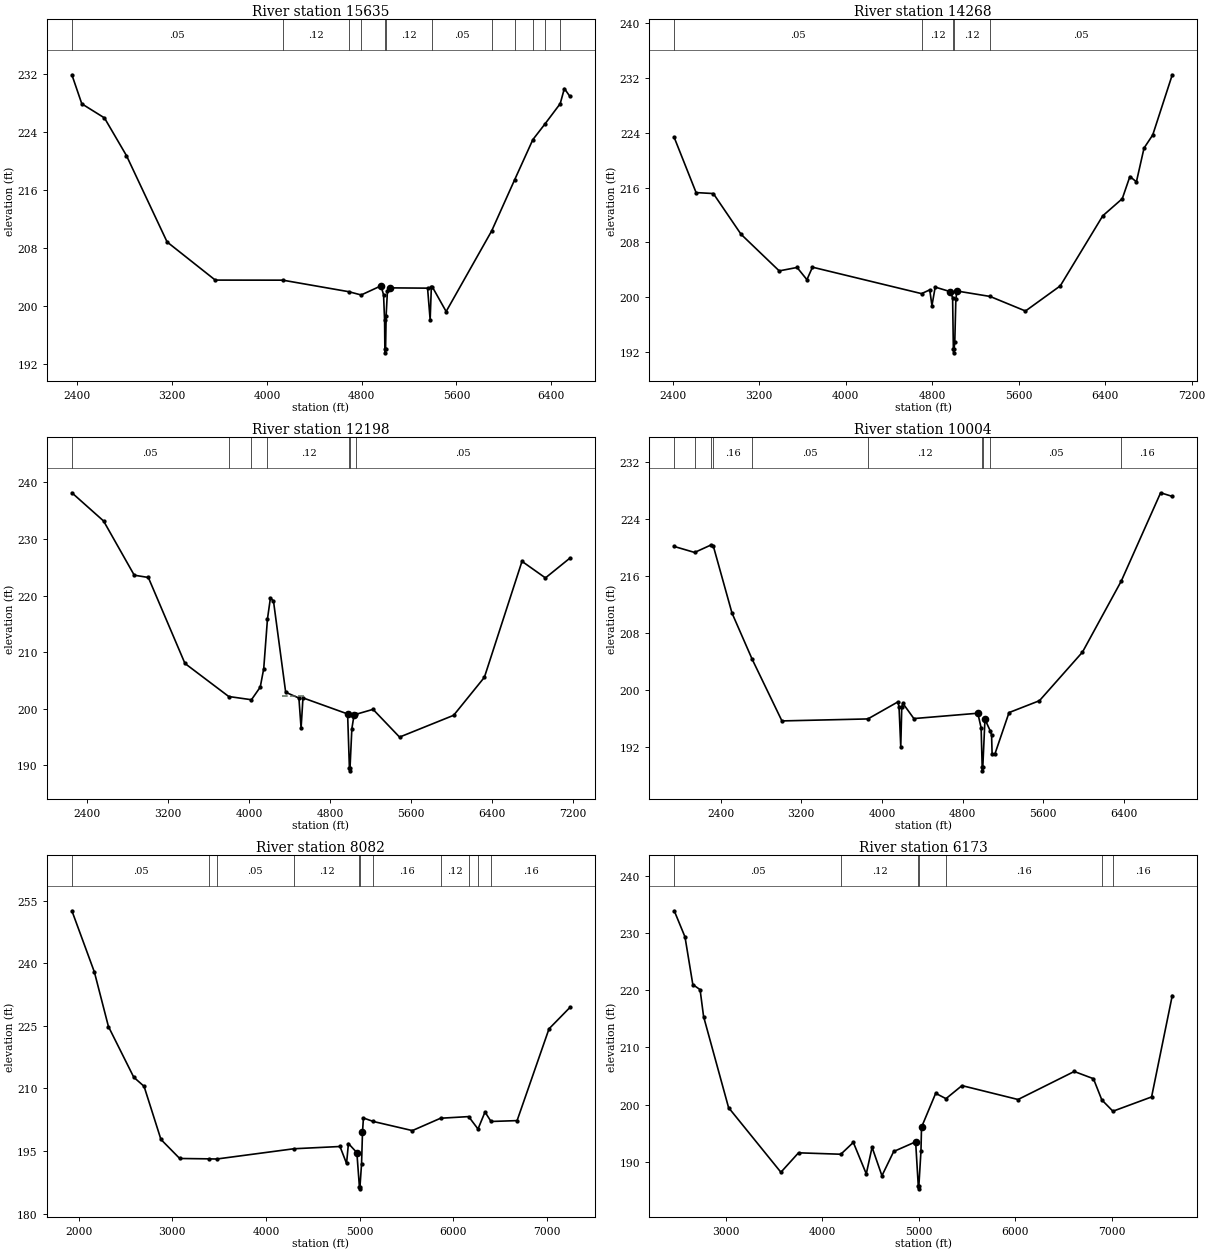
Type RM Length L Ch R = 1 ,15635   ,1367,1367,1367
BEGIN DESCRIPTION:
PANTHER CREEK 8.0
END DESCRIPTION:
XS GIS Cut Line= 4
      3609842.14     10206541.65      3607530.83     10206106.03
      3606978.74     10205882.07      3605879.78     10206491.45
#Sta/Elev= 30
  2353.2  231.86    2437  227.86    2628  225.92  2814.2  220.72  3157.1  208.83
  3563.6  203.58  4133.7  203.57  4691.3  201.98  4795.4  201.53  4962.8  202.79
  4984.4  201.54    4993  198.03  4995.4  194.06  4998.2  193.56  5001.4  194.06
    5006  198.67  5016.8  202.01  5038.4  202.51  5355.8  202.47  5377.6  198.12
  5387.9  202.67  5396.4  202.63  5512.7  199.25  5897.2  210.36  6091.5  217.42
  6244.7  222.93  6347.6   225.1  6475.5  227.88  6510.7  229.97  6557.6  228.87
#Mann= 12 ,-1 , 0
  2353.2     .05       0  4133.7     .12       0  4691.3     .05       0
  4795.4     .12       0  4995.4     .07       0  5001.4     .12       0
  5396.4     .05       0  5897.2     .07       0  6091.5     .16       0
  6244.7     .05       0  6347.6     .16       0  6475.5     .05       0
Bank Sta=4962.8,5038.4
XS Rating Curve= 0 ,0
Exp/Cntr=0.3,0.1

Type RM Length L Ch R = 1 ,14268   ,2070,2070,2070
BEGIN DESCRIPTION:
PANTHER CREEK 7.0
END DESCRIPTION:
XS GIS Cut Line= 3
      3609492.14     10206141.66      3607480.48     10205194.57
      3605112.39     10205444.58
#Sta/Elev= 30
  2415.5  223.28  2617.6  215.26  2777.1  215.12  3033.3  209.19  3386.2  203.86
  3551.3  204.36  3642.4  202.58  3693.6   204.4  4702.2  200.55  4778.1   201.1
  4798.2   198.8  4828.4   201.5  4969.2  200.83  4989.3  199.94  4996.3  192.43
  4999.1  191.93  5002.3  192.43  5009.4   193.5  5019.4  199.79  5029.5  200.93
  5335.5  200.14    5663  198.02  5984.8  201.68  6377.6  211.88  6557.9  214.37
  6628.3   217.6  6688.7  216.83  6759.1  221.74  6839.5  223.65  7020.2  232.41
#Mann= 5 ,-1 , 0
  2415.5     .05       0  4702.2     .12       0  4996.3     .07       0
  5002.3     .12       0  5335.5     .05       0
#XS Ineff= 1 ,-1
 3179.55 3697.73  204.27
Permanent Ineff=
       F
Bank Sta=4969.2,5029.5
XS Rating Curve= 0 ,0
Exp/Cntr=0.3,0.1

Type RM Length L Ch R = 1 ,12198   ,2194,2194,2194
BEGIN DESCRIPTION:
PANTHER CREEK 6.0
END DESCRIPTION:
XS GIS Cut Line= 3
      3609293.49      10204059.7      3606799.92     10204333.46
      3604495.32     10205059.12
#Sta/Elev= 30
  2248.8  238.15  2562.1  233.17  2865.6  223.59  3004.7  223.19  3366.9     208
  3799.8  202.16  4024.4  201.59  4111.3  203.82  4145.8  207.09  4182.9  215.89
  4211.9  219.55  4242.1  219.04  4362.8  202.91  4493.6  201.89  4515.2  196.57
  4533.8  201.92  4975.2  199.08    4993  189.53  4995.7  189.03    4999  189.53
  5017.2  196.47  5038.8  198.88  5060.5  199.03  5226.8  199.89  5488.9  194.99
  6023.6  198.84  6327.6  205.55  6699.5  226.04  6931.3  223.11  7173.5  226.61
#Mann= 7 ,-1 , 0
  2248.8     .05       0  3799.8     .12       0  4024.4     .16       0
  4182.9     .12       0    4993     .07       0    4999     .12       0
  5060.5     .05       0
#XS Ineff= 2 ,-1
 2852.27  4212.5  219.27    4325 4543.18   202.3
Permanent Ineff=
       F       F
Bank Sta=4975.2,5038.8
XS Rating Curve= 0 ,0
Exp/Cntr=0.3,0.1

Type RM Length L Ch R = 1 ,10004   ,1922,1922,1922
BEGIN DESCRIPTION:
PANTHER CREEK 6.1
END DESCRIPTION:
XS GIS Cut Line= 5
      3608640.75     10203365.25      3606966.59     10203604.29
      3606063.81     10203625.13      3605404.09     10203826.52
      3603840.74     10204365.25
#Sta/Elev= 30
  1941.2  220.16  2143.2  219.32    2306  220.37  2328.9  220.21  2513.8  210.81
  2713.6  204.33  3008.9  195.66    3861  195.94    4157  198.32  4169.8  197.67
    4187  192.02    4197  197.65    4207  198.15    4317  195.99  4950.8  196.74
  4983.7  194.69  4994.2  189.15  4996.9  188.65  5000.2  189.15  5021.7  195.89
  5075.7  194.21  5087.3  193.65  5092.5  191.05  5120.1  191.01  5260.2  196.83
  5561.8   198.5  5988.2  205.32  6373.3  215.31  6763.2   227.7  6878.7  227.19
#Mann= 10 ,-1 , 0
  1941.2     .05       0  2143.2     .16       0    2306     .12       0
  2328.9     .16       0  2713.6     .05       0    3861     .12       0
  4994.2     .07       0  5000.2     .12       0  5075.7     .05       0
  6373.3     .16       0
Bank Sta=4950.8,5021.7
XS Rating Curve= 0 ,0
Exp/Cntr=0.3,0.1

Type RM Length L Ch R = 1 ,8082    ,1909,1909,1909
BEGIN DESCRIPTION:
PANTHER CREEK 5.0
END DESCRIPTION:
XS GIS Cut Line= 3
       3608842.1     10202691.64      3605508.26     10202666.79
      3603542.11     10202891.64
#Sta/Elev= 30
  1929.2  252.56  2169.2  237.89  2319.2  224.83  2589.2   212.7  2699.2  210.52
  2879.2   197.8  3079.2  193.24  3395.8  193.15  3473.3  193.11  4298.1  195.57
  4789.3  196.11  4859.3  192.04  4879.3  196.82  4969.3  194.64  4996.3  186.47
    4999  185.97  5002.3  186.47  5019.3  191.94  5029.3  199.53  5039.3  202.94
  5144.6   202.1  5561.2  199.92  5862.4  202.88  6161.8  203.27  6261.6  200.29
  6336.2  204.37  6400.5   202.1  6678.5  202.31  7018.9  224.29  7242.1  229.41
#Mann= 11 ,-1 , 0
  1929.2     .05       0  3395.8     .16       0  3473.3     .05       0
  4298.1     .12       0  4996.3     .07       0  5002.3     .12       0
  5144.6     .16       0  5862.4     .12       0  6161.8     .05       0
  6261.6      .1       0  6400.5     .16       0
Bank Sta=4969.3,5029.3
XS Rating Curve= 0 ,0
Exp/Cntr=0.3,0.1

Type RM Length L Ch R = 1 ,6173    ,2622,2622,2622
BEGIN DESCRIPTION:
PANTHER CREEK 4.0
END DESCRIPTION:
XS GIS Cut Line= 4
      3608692.11     10201541.64      3606619.37     10201895.96
      3605904.09     10201632.07      3603892.08     10202741.65
#Sta/Elev= 30
  2466.8  233.88  2578.4  229.31  2659.6  220.98  2734.8  220.09  2771.2  215.38
  3030.2  199.46  3572.6  188.16  3755.2  191.56  4193.8  191.31  4323.4  193.38
  4457.6  187.88  4517.7  192.53    4620  187.55  4741.8  191.79  4969.3  193.48
  4996.7  185.76  4999.4  185.26  5002.7  185.76  5024.8  191.96  5030.1  196.03
    5177  201.96  5283.9  201.03  5449.6  203.31  6030.9  200.88  6613.3  205.78
  6812.4  204.52  6899.4  200.81  7014.6  198.83  7415.3  201.33  7629.7  219.06
#Mann= 7 ,-1 , 0
  2466.8     .05       0  4193.8     .12       0  4996.7     .07       0
  5002.7     .12       0  5283.9     .16       0  6899.4     .05       0
  7014.6     .16       0
Bank Sta=4969.3,5030.1
XS Rating Curve= 0 ,0
Exp/Cntr=0.3,0.1

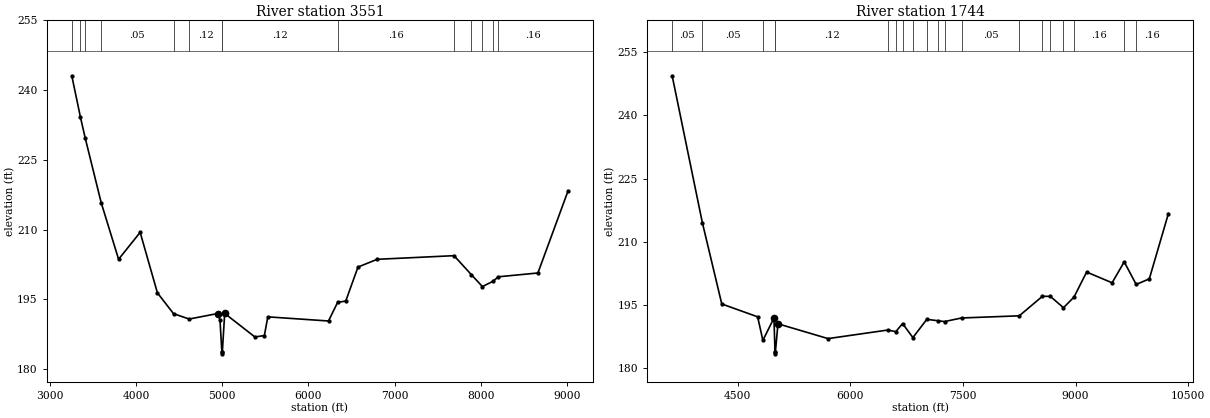
Type RM Length L Ch R = 1 ,3551    ,1807,1807,1807
BEGIN DESCRIPTION:
PANTHER CREEK 3.0
END DESCRIPTION:
XS GIS Cut Line= 3
      3608834.67     10200382.07      3606487.42     10200347.35
      3603759.81     10202387.86
#Sta/Elev= 30
  3256.9  243.05  3357.2  234.15  3411.7  229.72  3597.8  215.77  3799.5  203.61
  4049.6  209.39  4249.6  196.39  4436.8  191.91  4617.8  190.76  4949.7  191.95
  4975.4  190.55  4996.7  183.78  4999.4  183.28  5002.7  183.78  5029.7  191.97
  5379.7  186.91  5489.7  187.21  5529.7  191.23  6233.4  190.34    6339  194.34
  6433.5  194.63  6575.2  201.93  6797.5   203.6  7688.8  204.38  7890.7  200.28
  8017.7  197.74  8144.7  198.91  8200.8  199.84  8661.4  200.66  9010.8  218.31
#Mann= 14 ,-1 , 0
  3256.9     .16       0  3357.2     .05       0  3411.7     .16       0
  3597.8     .05       0  4436.8      .1       0  4617.8     .12       0
  4996.7     .07       0  5002.7     .12       0    6339     .16       0
  7688.8     .12       0  7890.7     .05       0  8017.7     .16       0
  8144.7     .12       0  8200.8     .16       0
Bank Sta=4949.7,5029.7
XS Rating Curve= 0 ,0
Exp/Cntr=0.3,0.1

Type RM Length L Ch R = 1 ,1744    ,0,0,0
BEGIN DESCRIPTION:
PANTHER CREEK 1.0
END DESCRIPTION:
XS GIS Cut Line= 3
      3609042.15     10198691.63      3606897.15     10199086.07
      3603656.17     10202105.77
#Sta/Elev= 30
  3625.4  249.37  4027.6  214.56  4286.3  195.29  4764.2  192.24  4833.7  186.66
  4981.5  191.96  4995.1  183.97  4997.8  183.47  5001.1  183.97  5034.6  190.59
  5701.9  187.08  6497.9  189.11  6604.6  188.73  6695.2  190.64  6832.2  187.32
  7017.8  191.65  7168.2  191.31  7253.7  191.12  7480.2  191.97  8249.5  192.48
  8558.3  197.12  8663.6  197.08  8838.3   194.4  8978.4  196.92  9146.6  202.85
  9486.2  200.31  9647.3  205.27    9807  199.91  9981.6  201.24 10236.1  216.72
#Mann= 20 ,-1 , 0
  3625.4     .05       0  4027.6     .05       0  4833.7     .12       0
  4995.1     .07       0  5001.1     .12       0  6497.9     .07       0
  6604.6     .12       0  6695.2     .07       0  6832.2     .12       0
  7017.8     .05       0  7168.2     .05       0  7253.7     .12       0
  7480.2     .05       0  8249.5      .1       0  8558.3      .1       0
  8663.6     .16       0  8838.3     .05       0  8978.4     .16       0
  9647.3     .12       0    9807     .16       0
Bank Sta=4981.5,5034.6
XS Rating Curve= 0 ,0
Exp/Cntr=0.3,0.1

Chan Stop Cuts=-1
Use User Specified Reach Order=0
Composite Channel Slope=5