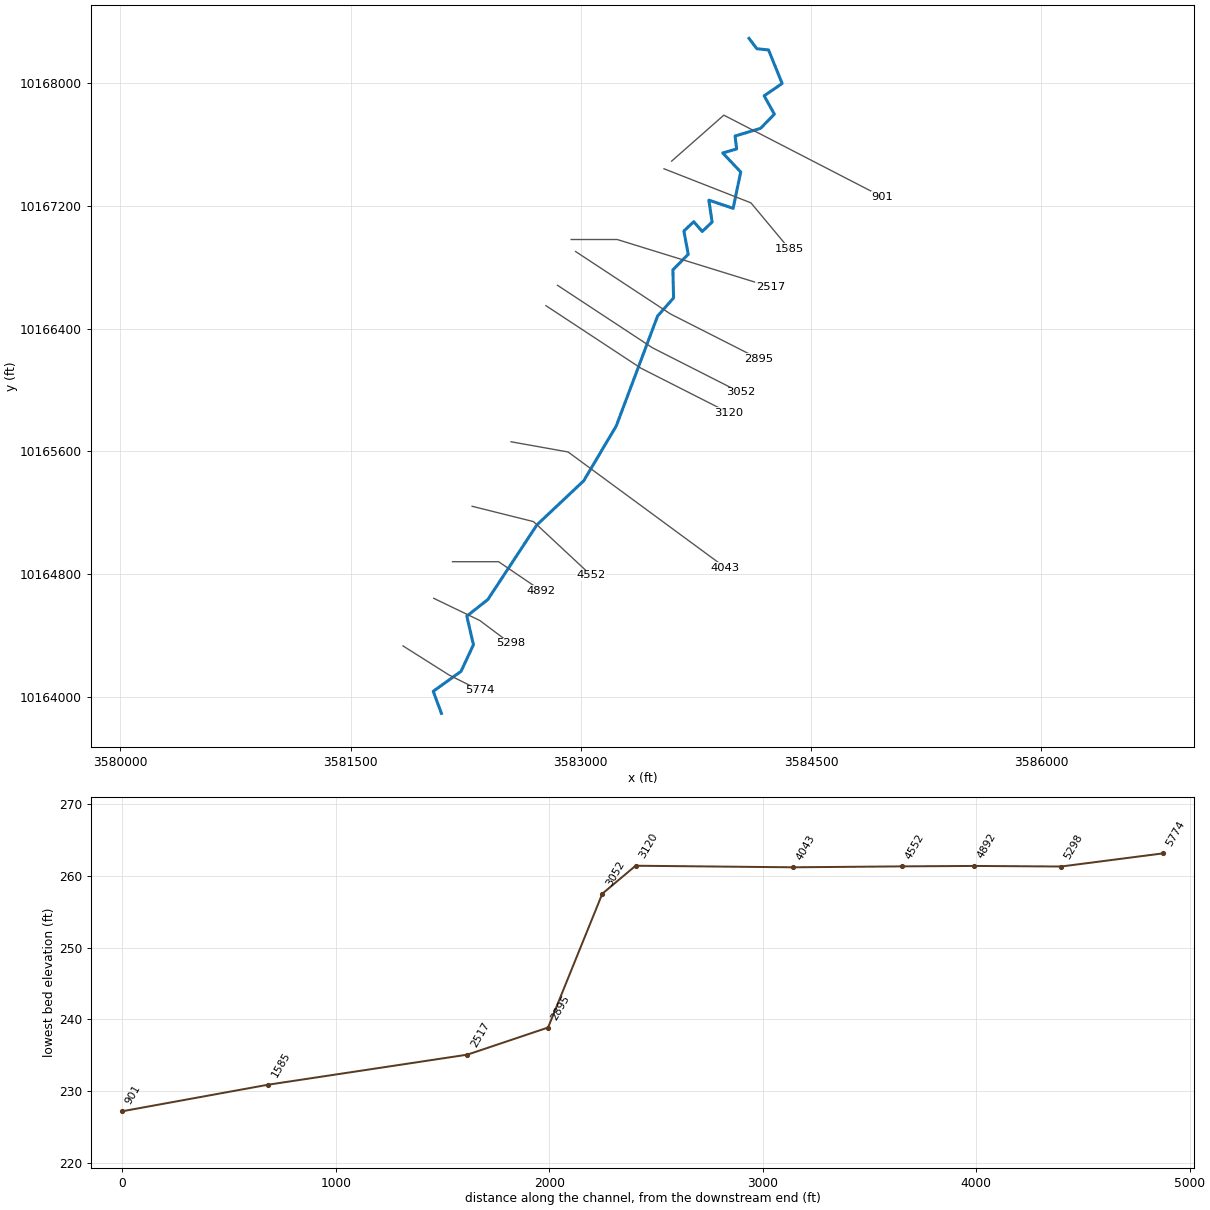
--- PEACH CREEK SOUTH TRIB 10 2.prj (project) ---

Proj Title=PEACH CREEK SOUTH TRIB 10 2 Base Level Engineering
Current Plan=p01
Default Exp/Contr=0.3,0.1
English Units
Geom File=g01
Flow File=f01
Plan File=p01
Y Axis Title=Elevation
X Axis Title(PF)=Main Channel Distance
X Axis Title(XS)=Station
BEGIN DESCRIPTION:
PEACH CREEK SOUTH TRIB 10 2
END DESCRIPTION:
DSS Export Rating Curves= 0
DSS Export Rating Curve Sorted= 0
DSS Export Volume Flow Curves= 0
DXF OffsetX= 0
DXF OffsetY= 0
DXF ScaleX= 1
DXF ScaleY= 10

--- PEACH CREEK SOUTH TRIB 10 2.p01 (plan) ---

Plan Title=Multiple Run
Short Identifier=Multiple
Geom File=g01
Flow File=f01
Subcritical Flow
K Sum by GR= 0
Std Step Tol= 0.01
Critical Tol= 0.01
Num of Std Step Trials= 20
Max Error Tol= 0.3
Flow Tol Ratio= 0.001
Split Flow NTrial= 30
Split Flow Tol= 0.02
Split Flow Ratio= 0.02
Log Output Level= 0
Friction Slope Method= 1
Unsteady Friction Slope Method= 2
Unsteady Bridges Friction Slope Method= 1
Parabolic Critical Depth
Global Vel Dist=  1 , 1 , 1
Global Log Level= 0
CheckData=True
Encroach Param= -1, 0, 0, 0
BEGIN DESCRIPTION:
Multiple Run
END DESCRIPTION:

--- PEACH CREEK SOUTH TRIB 10 2.f01 (steady flow) ---

Flow Title=Multiple
Program Version=4.10
Number of Profiles= 7
Profile Names=10-year,25-year,50-year,1pct_min,100-year,1pct_plu,500-year
River Rch & RM=PEACH CREEK SOUT,Reach-1         ,5774
     416     551     659     578     782    1057    1103
Boundary for River Rch & Prof#=PEACH CREEK SOUT,Reach-1         , 1
Up Type= 0
Dn Type= 3
Dn Slope=0.005
Boundary for River Rch & Prof#=PEACH CREEK SOUT,Reach-1         , 2
Up Type= 0
Dn Type= 3
Dn Slope=0.005
Boundary for River Rch & Prof#=PEACH CREEK SOUT,Reach-1         , 3
Up Type= 0
Dn Type= 3
Dn Slope=0.005
Boundary for River Rch & Prof#=PEACH CREEK SOUT,Reach-1         , 4
Up Type= 0
Dn Type= 3
Dn Slope=0.005
Boundary for River Rch & Prof#=PEACH CREEK SOUT,Reach-1         , 5
Up Type= 0
Dn Type= 3
Dn Slope=0.005
Boundary for River Rch & Prof#=PEACH CREEK SOUT,Reach-1         , 6
Up Type= 0
Dn Type= 3
Dn Slope=0.005
Boundary for River Rch & Prof#=PEACH CREEK SOUT,Reach-1         , 7
Up Type= 0
Dn Type= 3
Dn Slope=0.005
DSS Import GetInterval= 0
DSS Import GetPeak= 0
DSS Import FillOption= 0

--- PEACH CREEK SOUTH TRIB 10 2.g01 (geometry) ---

Geom Title=Existing Conditions
Program Version=4.10

River Reach=PEACH CREEK SOUT,Reach-1
Reach XY= 30
      3582092.11     10163891.64       3582038.8     10164035.53
      3582219.72     10164165.56      3582300.69     10164338.82
      3582257.51     10164525.48      3582394.64       10164634.
      3582714.08     10165120.11      3583019.64      10165408.3
      3583231.44     10165765.94      3583500.32     10166481.44
      3583604.49     10166599.71      3583600.15     10166783.09
      3583699.98       10166884.      3583671.77     10167035.91
      3583735.91     10167096.46      3583791.46     10167033.09
       3583855.7     10167094.81      3583834.25     10167237.08
      3583992.51     10167183.69      3584041.99     10167420.67
      3583924.84     10167544.54      3584015.38     10167570.95
      3584005.15     10167655.08      3584171.24     10167705.26
      3584261.26      10167797.5       3584194.6     10167917.29
      3584311.78      10167997.5      3584223.24     10168216.25
       3584147.2     10168224.06      3584095.96     10168291.94

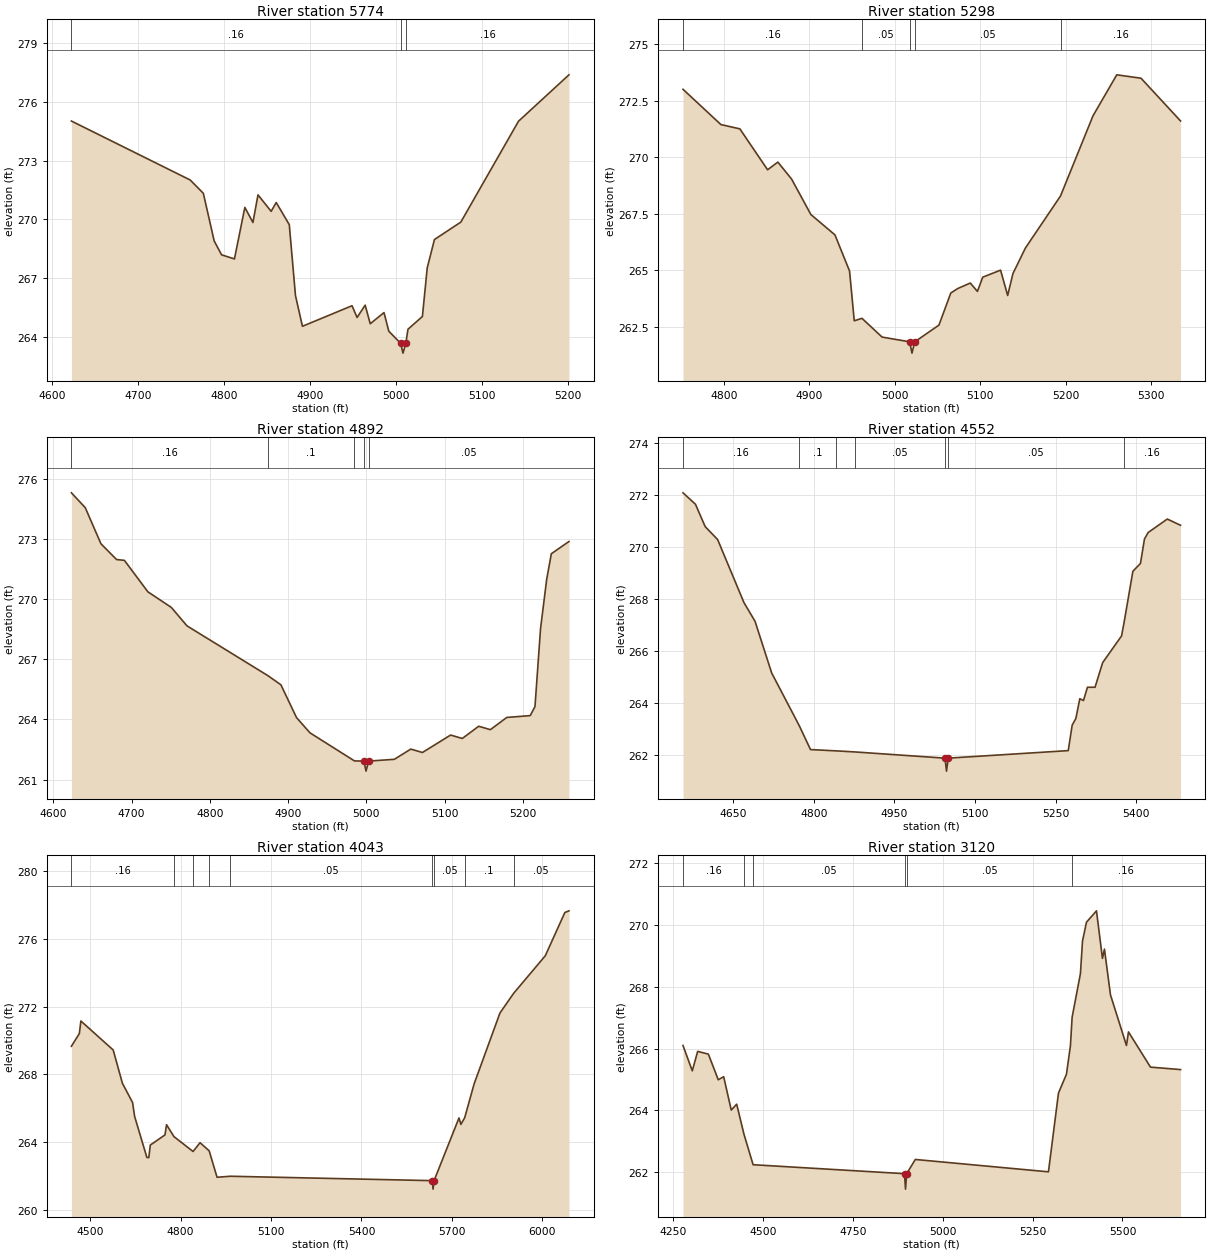
Type RM Length L Ch R = 1 ,5774    ,476,476,476
BEGIN DESCRIPTION:
PEACH CREEK SOUTH TRIB 10.2 10.0
END DESCRIPTION:
XS GIS Cut Line= 3
      3581841.71      10164331.4      3582142.11     10164141.64
      3582342.09     10164041.65
#Sta/Elev= 30
  4622.5  275.02  4760.7  272.01    4776  271.33  4788.6   268.9  4797.2  268.19
  4812.2  267.98  4824.3  270.61  4833.7  269.84  4839.6  271.25  4854.9  270.41
  4860.8  270.86    4876  269.73  4883.2  266.11  4891.3  264.54    4949  265.59
  4954.9  264.99  4964.3  265.62  4970.2  264.67  4986.2  265.24  4991.8  264.29
  5005.6  263.67  5008.3  263.17  5011.6  263.67  5014.1  264.39  5030.9  265.04
  5036.5  267.52  5044.9  268.97  5075.6  269.86  5142.7  275.01  5201.4  277.38
#Mann= 3 ,-1 , 0
  4622.5     .16       0  5005.6     .07       0  5011.6     .16       0
Bank Sta=5005.6,5011.6
XS Rating Curve= 0 ,0
Exp/Cntr=0.3,0.1

Type RM Length L Ch R = 1 ,5298    ,406,406,406
BEGIN DESCRIPTION:
PEACH CREEK SOUTH TRIB 10.2 9.0
END DESCRIPTION:
XS GIS Cut Line= 3
      3582042.06     10164641.66      3582341.91     10164497.19
      3582541.88     10164347.21
#Sta/Elev= 30
  4751.9  273.01  4796.3  271.45  4818.5  271.26    4851  269.45    4863  269.79
  4879.1  269.04  4901.7  267.47  4929.9  266.57    4947  264.97  4952.5  262.77
  4961.5  262.88  4985.1  262.05  5017.4  261.84  5020.1  261.34  5023.4  261.84
  5051.7  262.58  5065.6     264  5073.9   264.2  5088.4  264.44  5096.8  264.07
    5103   264.7  5123.9  265.01  5132.2  263.89  5138.4  264.86    5153  265.99
  5194.1  268.29  5232.2  271.84    5260  273.65  5288.4   273.5  5334.7  271.61
#Mann= 5 ,-1 , 0
  4751.9     .16       0  4961.5     .05       0  5017.4    .033       0
  5023.4     .05       0  5194.1     .16       0
Bank Sta=5017.4,5023.4
XS Rating Curve= 0 ,0
Exp/Cntr=0.3,0.1

Type RM Length L Ch R = 1 ,4892    ,340,340,340
BEGIN DESCRIPTION:
PEACH CREEK SOUTH TRIB 10.2 8.0
END DESCRIPTION:
XS GIS Cut Line= 3
       3582164.4     10164880.35      3582464.38     10164880.35
      3582742.14     10164691.62
#Sta/Elev= 30
    4623  275.31  4640.7  274.57  4660.7  272.77  4680.7  271.98  4690.7  271.94
  4720.7  270.37  4750.7  269.59  4770.7  268.67  4873.9  266.19  4890.7  265.73
  4910.7  264.09  4927.9  263.33  4984.7  261.93  4996.8  261.92  4999.5  261.42
  5002.8  261.92  5035.7  262.01  5056.7  262.52  5071.6  262.35  5107.6  263.22
  5122.5  263.05  5143.5  263.66  5158.4  263.49  5179.4   264.1  5209.3  264.19
  5215.4  264.64  5222.5  268.53  5230.3  270.98  5236.3  272.27  5258.8  272.88
#Mann= 5 ,-1 , 0
    4623     .16       0  4873.9      .1       0  4984.7     .05       0
  4996.8    .033       0  5002.8     .05       0
Bank Sta=4996.8,5002.8
XS Rating Curve= 0 ,0
Exp/Cntr=0.3,0.1

Type RM Length L Ch R = 1 ,4552    ,509,509,509
BEGIN DESCRIPTION:
PEACH CREEK SOUTH TRIB 10.2 7.0
END DESCRIPTION:
XS GIS Cut Line= 3
      3582292.12     10165241.64      3582692.11     10165141.64
      3583067.01     10164791.61
#Sta/Elev= 30
  4556.9  272.08  4580.1  271.64  4598.1  270.78  4621.3  270.28  4670.3  267.85
  4690.9  267.13  4721.8  265.14  4773.1  263.11    4794  262.19    4842  262.14
  4875.9   262.1  5044.1  261.86  5046.9  261.36  5050.1  261.86  5273.3  262.15
  5280.6  263.13  5287.5  263.39  5294.8  264.15  5301.6  264.08    5309  264.59
  5323.1  264.59  5337.3  265.54  5372.5  266.57  5377.3  267.11  5393.5  269.06
  5407.6  269.36    5415   270.3  5421.8  270.55  5457.5  271.07  5482.1  270.83
#Mann= 7 ,-1 , 0
  4556.9     .16       0  4773.1      .1       0    4842     .07       0
  4875.9     .05       0  5044.1    .033       0  5050.1     .05       0
  5377.3     .16       0
Bank Sta=5044.1,5050.1
XS Rating Curve= 0 ,0
Exp/Cntr=0.3,0.1

Type RM Length L Ch R = 1 ,4043    ,738,738,738
BEGIN DESCRIPTION:
PEACH CREEK SOUTH TRIB 10.2 6.0
END DESCRIPTION:
XS GIS Cut Line= 3
       3582545.8      10165662.1       3582917.3     10165595.56
      3583942.14     10164841.62
#Sta/Elev= 30
  4438.2  269.66  4464.5  270.41  4469.6  271.15  4576.7  269.44  4607.2  267.48
    4641  266.34  4647.8  265.52  4688.4   263.1  4694.8  263.09  4699.8  263.83
  4748.5  264.43  4753.6  265.03  4778.1  264.33  4841.6  263.45  4864.7  263.97
    4895  263.49  4921.1  261.93  4964.9  261.99  5634.7  261.73  5637.4  261.23
  5640.7  261.73  5723.3  265.43  5729.5  265.05  5742.2  265.44  5773.5  267.44
  5859.1  271.62  5904.4  272.78  6009.5     275  6074.3  277.55  6087.9  277.65
#Mann= 9 ,-1 , 0
  4438.2     .16       0  4778.1     .07       0  4841.6     .05       0
    4895     .07       0  4964.9     .05       0  5634.7    .033       0
  5640.7     .05       0  5742.2      .1       0  5904.4     .05       0
Bank Sta=5634.7,5640.7
XS Rating Curve= 0 ,0
Exp/Cntr=0.3,0.1

Type RM Length L Ch R = 1 ,3120    ,156,156,156
BEGIN DESCRIPTION:
PEACH CREEK SOUTH TRIB 10.2 5.2
END DESCRIPTION:
XS GIS Cut Line= 3
      3582773.15     10166549.21      3583392.11     10166141.64
      3583965.25     10165850.59
#Sta/Elev= 30
  4277.6   266.1  4303.4  265.28  4318.4  265.91  4348.2  265.82  4375.7  264.99
  4390.7  265.09  4411.8  264.01  4426.9   264.2  4447.1  263.23  4472.6  262.24
  4893.7  261.95  4896.5  261.45  4899.7  261.95  4923.8  262.41  5294.1  262.01
    5322  264.56  5344.2  265.17  5355.2  266.09  5359.9  267.01  5383.1  268.43
  5388.8  269.48  5399.8  270.09  5427.7  270.46  5444.3  268.92  5449.9  269.22
  5466.6  267.74  5511.1   266.1  5516.7  266.54  5577.9   265.4  5661.5  265.32
#Mann= 6 ,-1 , 0
  4277.6     .16       0  4447.1      .1       0  4472.6     .05       0
  4893.7    .033       0  4899.7     .05       0  5359.9     .16       0
Bank Sta=4893.7,4899.7
XS Rating Curve= 0 ,0
Exp/Cntr=0.3,0.1

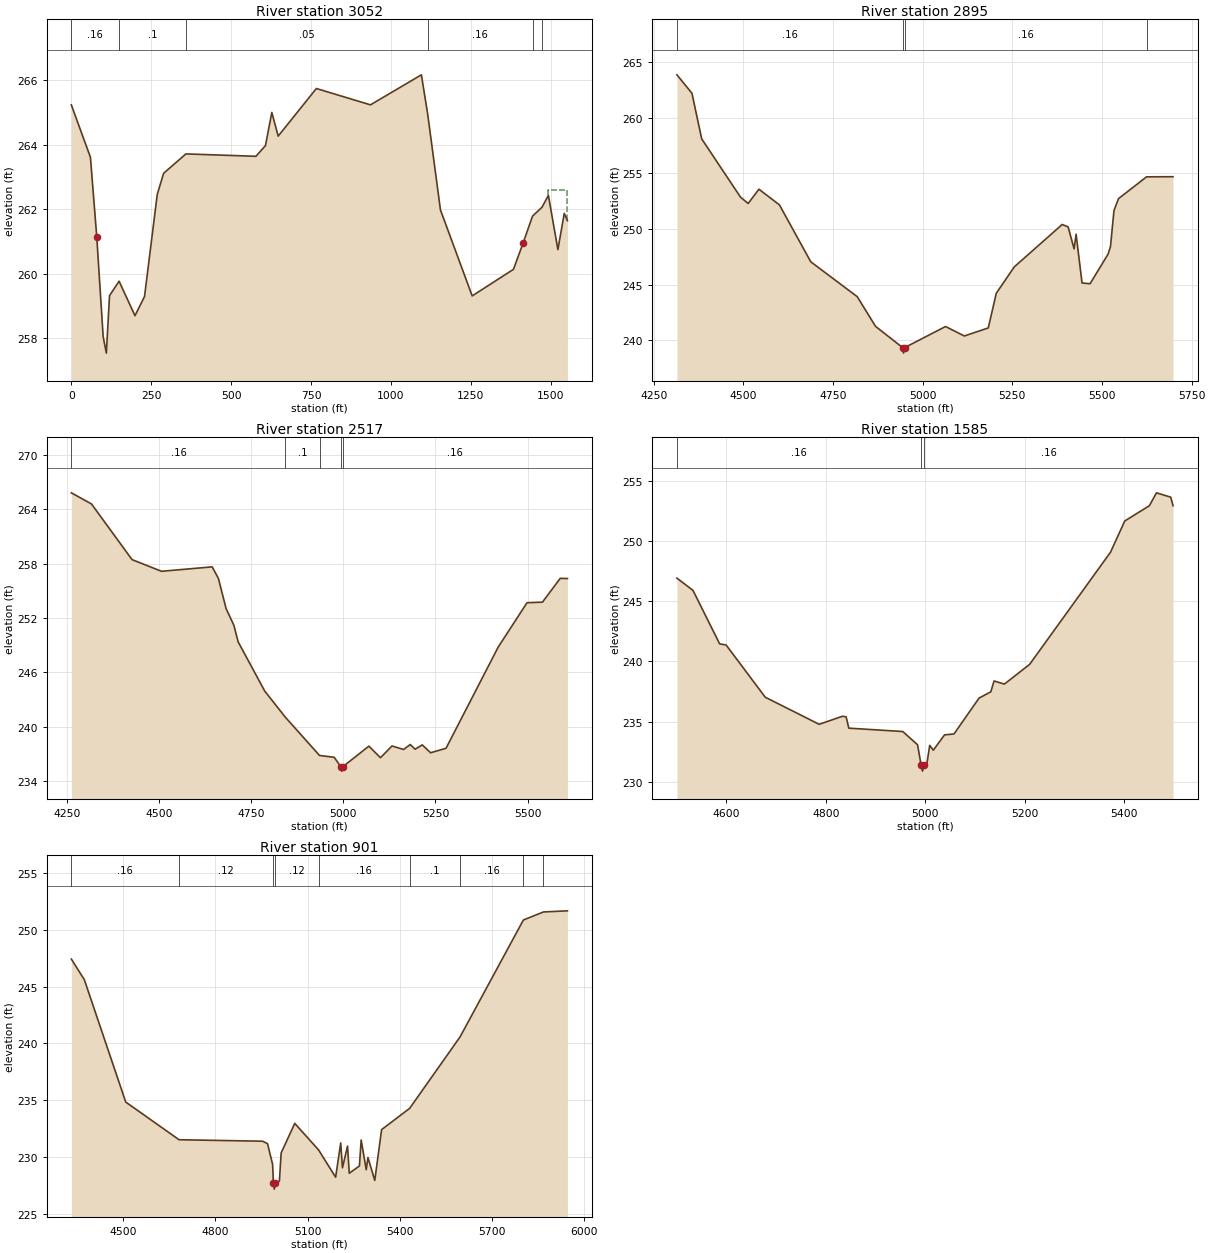
Type RM Length L Ch R = 1 ,3052    ,254,254,254
BEGIN DESCRIPTION:
PEACH CREEK SOUTH TRIB 10.2 5.1
END DESCRIPTION:
XS GIS Cut Line= 3
      3582848.38     10166682.04      3583467.37     10166274.45
      3584038.78     10165984.27
#Sta/Elev= 30
       0 265.23359.73294263.610379.64392 261.128 99.5549258.0531109.5104257.5426
119.4659 259.324149.3324259.7708199.1098258.7022228.9763259.2977268.7982262.4618
288.7092263.1138358.3976263.7143577.4185263.6402607.2849263.9719627.1959264.9987
647.1069264.2662766.5728265.7403935.8161265.23421095.104266.16451114.969264.9382
1154.698261.98071254.022259.31511383.142260.13831412.939260.94211442.736 261.785
1472.533262.06391492.398262.42961522.195260.7499 1542.06261.87011551.992261.6445
#Mann= 6 ,-1 , 0
       0     .16       0149.3324      .1       0358.3976     .05       0
1114.969     .16       01442.736    .033       01472.533     .16       0
#XS Ineff= 1 ,-1
 1492.45 1558.64   262.6
Permanent Ineff=
       F
Bank Sta=79.64392,1412.939
XS Rating Curve= 0 ,0
Exp/Cntr=0.3,0.1

Type RM Length L Ch R = 1 ,2895    ,378,378,378
BEGIN DESCRIPTION:
PEACH CREEK SOUTH TRIB 10.2 5.0
END DESCRIPTION:
XS GIS Cut Line= 3
      3582966.13     10166902.36       3583585.1     10166494.79
      3584157.69     10166204.01
#Sta/Elev= 30
  4314.8  263.85  4356.7  262.19  4383.8   258.1  4492.2  252.86  4513.5   252.3
  4543.4  253.58  4600.6  252.17    4688  247.06  4817.5  243.93  4868.7  241.26
    4944  239.36  4946.7  238.86    4950  239.36  5063.8  241.25  5116.1   240.4
  5182.9  241.12  5205.2  244.23  5255.3   246.6    5389  250.41  5405.5   250.2
  5422.2  248.22  5427.8  249.54  5444.4  245.16  5466.7  245.09  5516.8  247.74
  5523.6  248.41  5533.4  251.66    5546  252.73  5624.3  254.69  5698.1   254.7
#Mann= 4 ,-1 , 0
  4314.8     .16       0    4944     .07       0    4950     .16       0
  5624.3      .1       0
Bank Sta=4944,4950
XS Rating Curve= 0 ,0
Exp/Cntr=0.3,0.1

Type RM Length L Ch R = 1 ,2517    ,932,932,932
BEGIN DESCRIPTION:
PEACH CREEK SOUTH TRIB 10.2 3.0
END DESCRIPTION:
XS GIS Cut Line= 3
      3582937.42     10166980.55      3583237.46     10166980.55
      3584236.84      10166671.2
#Sta/Elev= 30
  4261.9  265.82  4316.6  264.59  4426.6  258.44  4506.6  257.15  4644.1  257.64
    4661  256.36  4681.9  253.02  4702.9  251.19  4714.5  249.36  4786.6  243.92
  4842.8  241.02  4935.4   236.8  4975.1   236.6    4993  235.57  4995.7  235.07
    4999  235.57  5069.3  237.83  5100.7  236.55  5132.1  237.85  5163.5  237.46
  5181.5  238.01  5194.9  237.49  5214.1  237.97  5236.8   237.1  5278.6  237.59
  5420.3  248.78  5498.5  253.68  5540.3  253.74  5588.6  256.37  5608.1  256.35
#Mann= 5 ,-1 , 0
  4261.9     .16       0  4842.8      .1       0  4935.4     .16       0
    4993     .07       0    4999     .16       0
Bank Sta=4993,4999
XS Rating Curve= 0 ,0
Exp/Cntr=0.3,0.1

Type RM Length L Ch R = 1 ,1585    ,684,684,684
BEGIN DESCRIPTION:
PEACH CREEK SOUTH TRIB 10.2 2.0
END DESCRIPTION:
XS GIS Cut Line= 3
      3583542.12     10167441.64      3584108.54     10167219.46
       3584357.8     10166920.35
#Sta/Elev= 30
  4500.7  246.91  4532.9   245.9  4586.6  241.45  4599.6  241.36  4678.3  237.02
  4786.8  234.77  4833.7  235.44    4841  235.39  4846.4  234.45  4954.9  234.17
  4984.7  233.07  4991.8  231.38  4994.6  230.88  4997.8  231.38  5003.8   231.6
  5009.1  233.02  5016.3  232.62  5038.9  233.89    5058  233.97  5108.4  236.95
    5132  237.47  5138.5  238.37  5159.3  238.11  5210.1  239.75  5372.8  249.07
  5401.4  251.66  5450.9  252.93  5465.2     254  5493.9  253.64  5498.5  252.93
#Mann= 3 ,-1 , 0
  4500.7     .16       0  4991.8     .07       0  4997.8     .16       0
Bank Sta=4991.8,4997.8
XS Rating Curve= 0 ,0
Exp/Cntr=0.3,0.1

Type RM Length L Ch R = 1 ,901     ,0,0,0
BEGIN DESCRIPTION:
PEACH CREEK SOUTH TRIB 10.2 1.0
END DESCRIPTION:
XS GIS Cut Line= 3
      3583592.13     10167491.67      3583931.94     10167791.17
      3584963.22      10167258.9
#Sta/Elev= 30
  4331.6  247.43  4373.8  245.62  4508.5  234.84  4681.9  231.52  4953.5  231.39
  4969.6  231.18  4986.2  229.35  4988.8  227.67  4991.6  227.17  4994.8  227.67
  5008.3  227.88    5014  230.36  5058.3  232.96  5135.8  230.62  5191.2  228.22
  5207.7  231.24  5213.4  229.05  5229.9  230.96  5235.5  228.57  5268.6  229.21
  5274.2   231.5  5290.7  228.88  5296.3  229.95  5318.5  227.94  5340.7  232.41
  5431.8  234.28  5595.7  240.57  5801.8  250.87    5867  251.58  5945.1  251.68
#Mann= 9 ,-1 , 0
  4331.6     .16       0  4681.9     .12       0  4988.8     .07       0
  4994.8     .12       0  5135.8     .16       0  5431.8      .1       0
  5595.7     .16       0  5801.8      .1       0    5867     .16       0
Bank Sta=4988.8,4994.8
XS Rating Curve= 0 ,0
Exp/Cntr=0.3,0.1
Stream Node=PEACH CREEK SOUT,Reach-1         , 0 , 0 ,Upstream end
Stream Node=PEACH CREEK SOUT,Reach-1         , 0 , 1 ,Downstream end

Chan Stop Cuts=-1
Use User Specified Reach Order=0
Composite Channel Slope=5