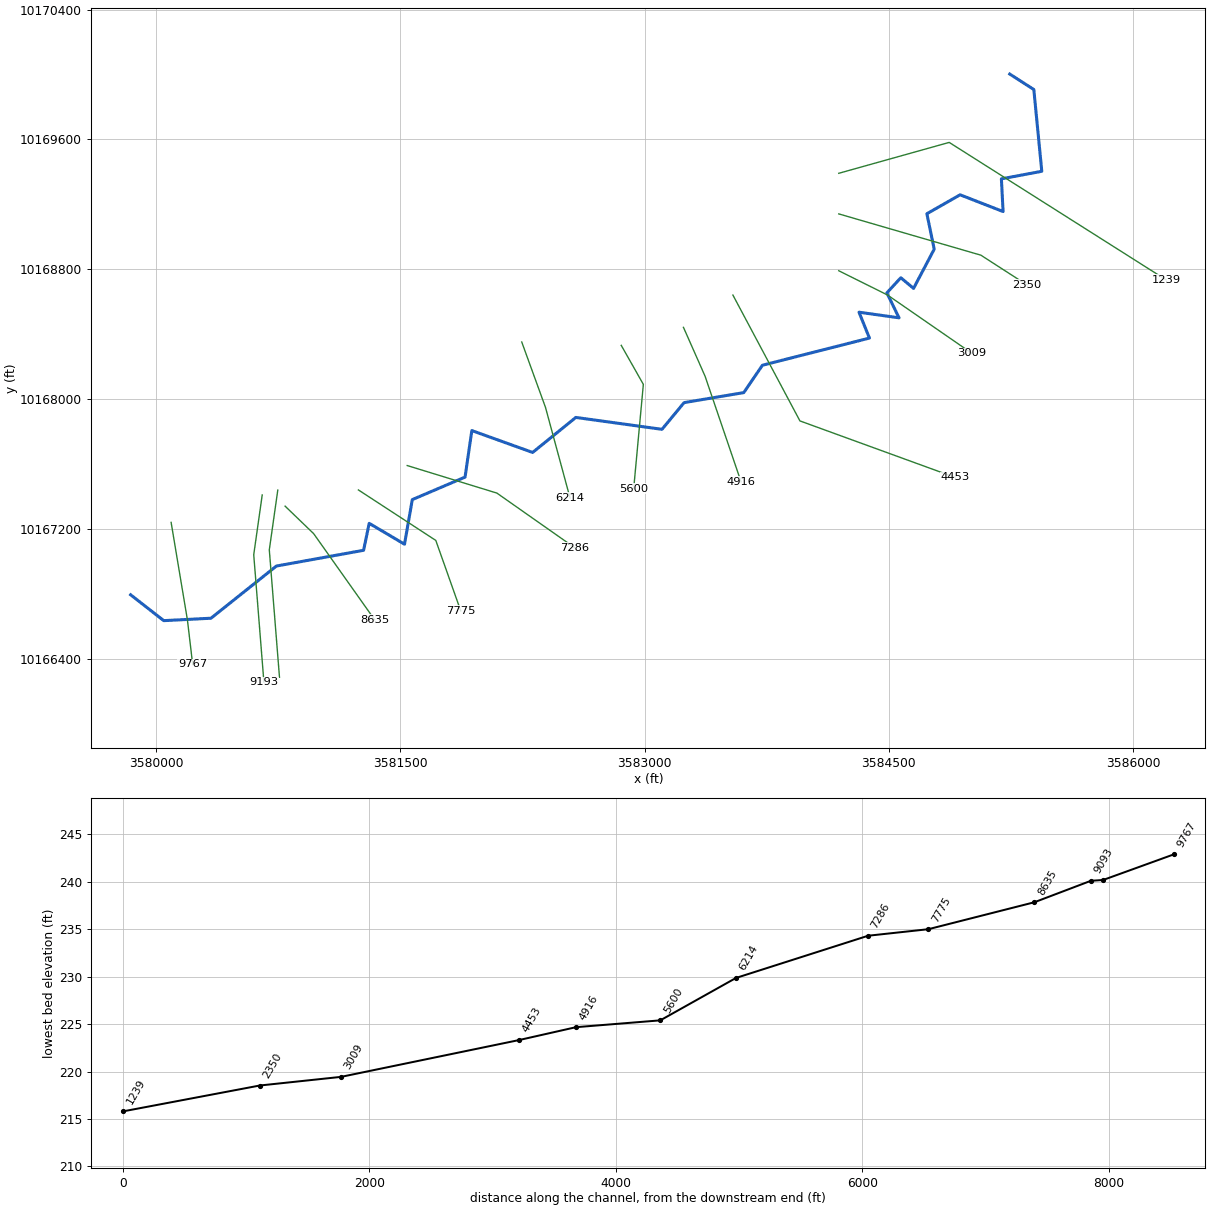
--- PEACH CREEK SOUTH TRIB 10.prj (project) ---

Proj Title=PEACH CREEK SOUTH TRIB 10 Base Level Engineering
Current Plan=p01
Default Exp/Contr=0.3,0.1
English Units
Geom File=g01
Flow File=f01
Plan File=p01
Y Axis Title=Elevation
X Axis Title(PF)=Main Channel Distance
X Axis Title(XS)=Station
BEGIN DESCRIPTION:
PEACH CREEK SOUTH TRIB 10
END DESCRIPTION:
DSS Export Rating Curves= 0
DSS Export Rating Curve Sorted= 0
DSS Export Volume Flow Curves= 0
DXF OffsetX= 0
DXF OffsetY= 0
DXF ScaleX= 1
DXF ScaleY= 10

--- PEACH CREEK SOUTH TRIB 10.p01 (plan) ---

Plan Title=Multiple Run
Short Identifier=Multiple
Geom File=g01
Flow File=f01
Subcritical Flow
K Sum by GR= 0
Std Step Tol= 0.01
Critical Tol= 0.01
Num of Std Step Trials= 20
Max Error Tol= 0.3
Flow Tol Ratio= 0.001
Split Flow NTrial= 30
Split Flow Tol= 0.02
Split Flow Ratio= 0.02
Log Output Level= 0
Friction Slope Method= 1
Unsteady Friction Slope Method= 2
Unsteady Bridges Friction Slope Method= 1
Parabolic Critical Depth
Global Vel Dist=  1 , 1 , 1
Global Log Level= 0
CheckData=True
Encroach Param= -1, 0, 0, 0
BEGIN DESCRIPTION:
Multiple Run
END DESCRIPTION:

--- PEACH CREEK SOUTH TRIB 10.f01 (steady flow) ---

Flow Title=Multiple
Program Version=4.10
Number of Profiles= 7
Profile Names=10-year,25-year,50-year,1pct_min,100-year,1pct_plu,500-year
River Rch & RM=PEACH CREEK SOUT,Reach-1         ,9767
     603     815     989     880    1190    1610    1726
River Rch & RM=PEACH CREEK SOUT,Reach-1         ,4453
     909    1256    1546    1393    1884    2548    2804
River Rch & RM=PEACH CREEK SOUT,Reach-1         ,3009
     909    1256    1546    1393    1884    2548    2804
Boundary for River Rch & Prof#=PEACH CREEK SOUT,Reach-1         , 1
Up Type= 0
Dn Type= 3
Dn Slope=0.005
Boundary for River Rch & Prof#=PEACH CREEK SOUT,Reach-1         , 2
Up Type= 0
Dn Type= 3
Dn Slope=0.005
Boundary for River Rch & Prof#=PEACH CREEK SOUT,Reach-1         , 3
Up Type= 0
Dn Type= 3
Dn Slope=0.005
Boundary for River Rch & Prof#=PEACH CREEK SOUT,Reach-1         , 4
Up Type= 0
Dn Type= 3
Dn Slope=0.005
Boundary for River Rch & Prof#=PEACH CREEK SOUT,Reach-1         , 5
Up Type= 0
Dn Type= 3
Dn Slope=0.005
Boundary for River Rch & Prof#=PEACH CREEK SOUT,Reach-1         , 6
Up Type= 0
Dn Type= 3
Dn Slope=0.005
Boundary for River Rch & Prof#=PEACH CREEK SOUT,Reach-1         , 7
Up Type= 0
Dn Type= 3
Dn Slope=0.005
DSS Import GetInterval= 0
DSS Import GetPeak= 0
DSS Import FillOption= 0

--- PEACH CREEK SOUTH TRIB 10.g01 (geometry) ---

Geom Title=Existing Conditions
Program Version=4.10

River Reach=PEACH CREEK SOUT,Reach-1
Reach XY= 30
      3579843.59     10166795.63      3580046.88     10166636.45
      3580336.94     10166651.39      3580738.72     10166972.82
      3581274.08     10167069.77      3581308.55     10167235.85
      3581525.34     10167107.23       3581573.2     10167381.89
      3581897.19     10167520.53      3581938.77     10167807.08
      3582312.13     10167672.36      3582577.41     10167888.01
      3583106.57     10167814.83      3583242.38     10167979.31
       3583608.7     10168040.94      3583723.37     10168209.47
       3584380.5     10168376.74      3584316.45     10168536.18
      3584562.36      10168501.5      3584487.42     10168655.24
      3584573.18      10168748.4      3584651.41     10168682.89
      3584778.28     10168924.34      3584733.23     10169142.58
      3584937.26      10169259.2      3585201.27      10169156.1
      3585190.81     10169357.41       3585438.9     10169403.99
      3585390.03      10169907.5      3585242.11     10170002.96

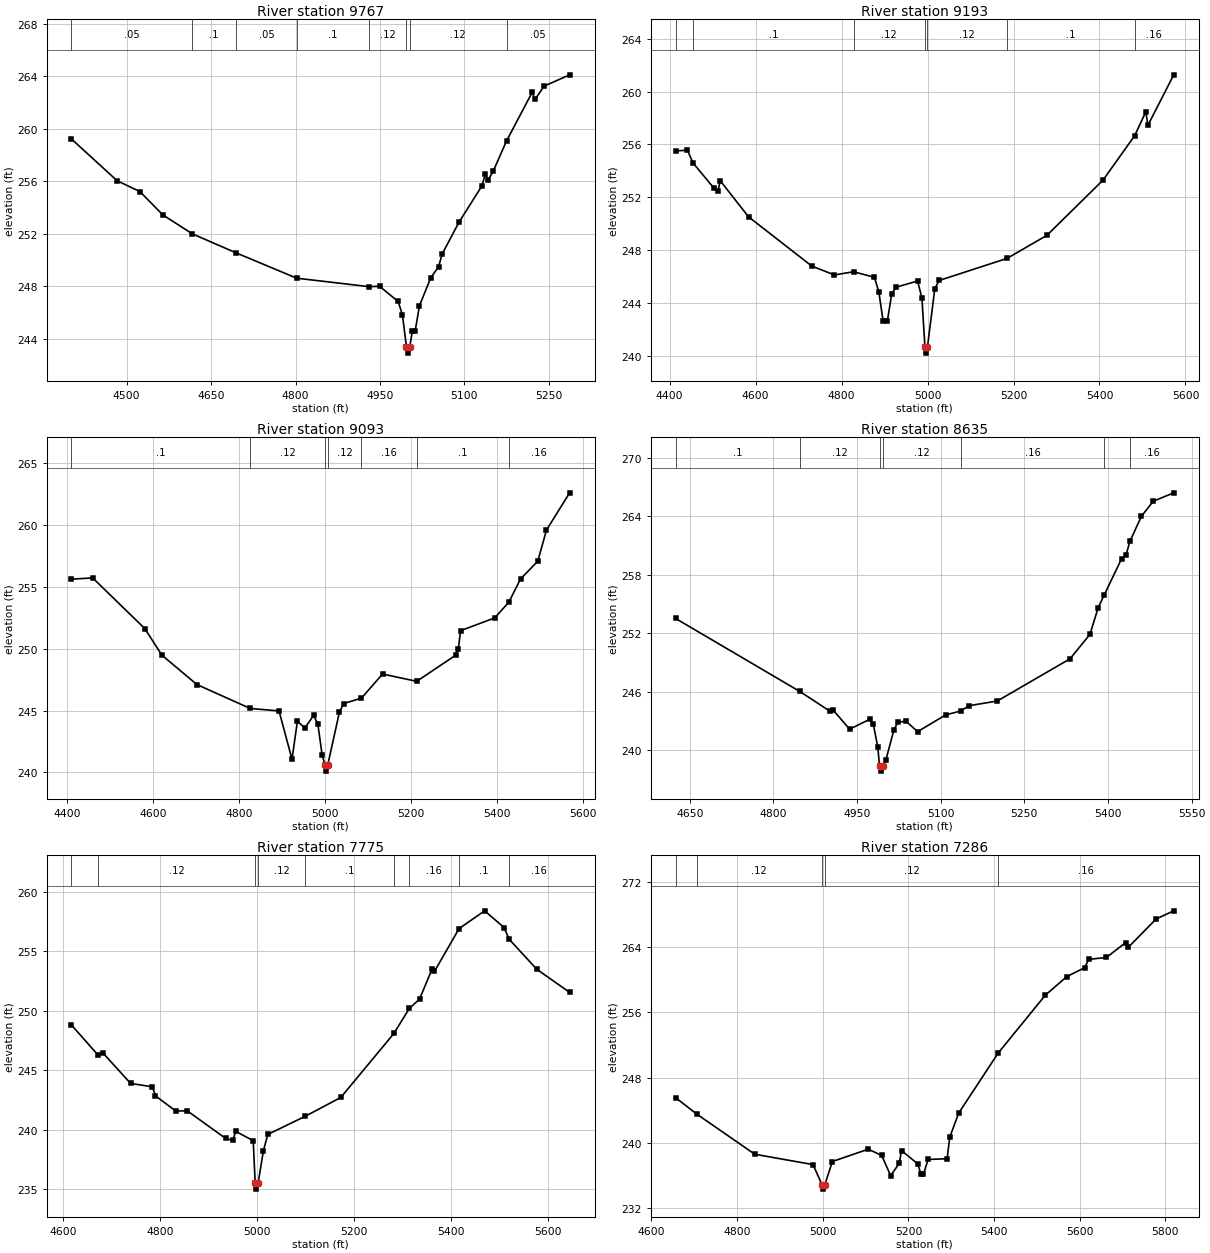
Type RM Length L Ch R = 1 ,9767    ,574,574,574
BEGIN DESCRIPTION:
PEACH CREEK SOUTH TRIB 10 16.0
END DESCRIPTION:
XS GIS Cut Line= 3
       3580092.1     10167241.66      3580192.11     10166641.64
      3580224.46     10166366.64
#Sta/Elev= 30
  4401.9  259.22    4483  256.04  4523.6  255.21  4564.1  253.44  4616.7  251.99
  4694.5  250.54  4802.2  248.61    4930  247.97  4949.4  247.99  4982.3  246.84
  4989.9  245.83  4997.1   243.4  4999.8   242.9  5003.1   243.4  5007.7  244.62
  5012.7  244.62  5020.3  246.52  5040.4  248.65  5054.2  249.48  5060.5  250.45
  5090.8   252.9    5131  255.63  5137.3  256.53  5142.3   256.1  5151.2  256.76
  5174.9  259.07  5220.4  262.77  5225.4  262.23  5241.8  263.25  5287.1  264.11
#Mann= 8 ,-1 , 0
  4401.9     .05       0  4616.7      .1       0  4694.5     .05       0
  4802.2      .1       0    4930     .12       0  4997.1     .07       0
  5003.1     .12       0  5174.9     .05       0
Bank Sta=4997.1,5003.1
XS Rating Curve= 0 ,0
Exp/Cntr=0.3,0.1

Type RM Length L Ch R = 1 ,9193    ,100,100,100
BEGIN DESCRIPTION:
PEACH CREEK SOUTH TRIB 10 15.1
END DESCRIPTION:
XS GIS Cut Line= 3
      3580651.53     10167410.41      3580599.44     10167042.36
      3580661.94     10166257.66
#Sta/Elev= 30
  4413.8  255.51  4441.6  255.56  4454.4   254.6  4503.5  252.68  4512.6  252.47
  4517.7  253.26  4583.6  250.52  4730.8  246.79  4783.4  246.12    4828  246.36
  4876.5  245.94  4886.8  244.82  4896.6  242.64  4906.6  242.64  4916.7  244.69
  4926.7  245.19  4976.8  245.66  4986.9  244.39  4993.9   240.7  4996.7   240.2
  4999.9   240.7    5017  245.09    5027   245.7  5184.8  247.37  5277.8  249.12
  5408.2   253.3    5482  256.67  5507.7  258.47  5512.7  257.45  5572.7  261.27
#Mann= 7 ,-1 , 0
  4413.8     .16       0  4454.4      .1       0    4828     .12       0
  4993.9     .07       0  4999.9     .12       0  5184.8      .1       0
    5482     .16       0
Bank Sta=4993.9,4999.9
XS Rating Curve= 0 ,0
Exp/Cntr=0.3,0.1

Type RM Length L Ch R = 1 ,9093    ,458,458,458
BEGIN DESCRIPTION:
PEACH CREEK SOUTH TRIB 10 15.0
END DESCRIPTION:
XS GIS Cut Line= 3
      3580747.17     10167440.52      3580695.08     10167072.47
      3580757.58     10166287.77
#Sta/Elev= 30
  4410.6  255.61    4460  255.71  4581.2  251.62  4620.8  249.48  4702.4   247.1
  4826.4  245.17  4893.5  244.97  4923.6  241.07  4936.2  244.13  4953.7  243.59
  4973.8  244.61  4983.8  243.92  4993.8  241.38  5000.8  240.61  5003.6  240.11
  5006.8  240.61  5033.9  244.87    5044  245.57  5085.1     246  5134.3  247.95
  5213.7  247.36  5304.8  249.48  5310.7     250  5315.7  251.45  5395.1  252.48
    5428  253.75  5455.3  255.63  5495.4  257.06  5515.5  259.57  5569.5  262.58
#Mann= 7 ,-1 , 0
  4410.6      .1       0  4826.4     .12       0  5000.8     .07       0
  5006.8     .12       0  5085.1     .16       0  5213.7      .1       0
    5428     .16       0
Bank Sta=5000.8,5006.8
XS Rating Curve= 0 ,0
Exp/Cntr=0.3,0.1

Type RM Length L Ch R = 1 ,8635    ,860,860,860
BEGIN DESCRIPTION:
PEACH CREEK SOUTH TRIB 10 14.0
END DESCRIPTION:
XS GIS Cut Line= 3
      3580792.14     10167341.61      3580967.52     10167172.18
       3581342.1     10166641.65
#Sta/Elev= 30
  4624.6  253.51  4847.4  246.02  4901.1  244.01  4907.2  244.11  4936.8  242.15
  4972.5  243.16  4979.3  242.64  4987.3   240.3  4990.4  238.35  4993.1  237.85
  4996.4  238.35    5002  239.04    5016  242.05    5023  242.86  5037.7  242.97
  5058.7   241.9  5109.1  243.62  5135.7  244.01    5151  244.56  5201.5  245.04
    5332  249.37  5367.7  251.88  5382.5  254.63  5393.3  255.92  5424.3  259.62
  5432.2  259.97  5439.2   261.4    5460  263.99  5481.2  265.53  5517.9  266.39
#Mann= 7 ,-1 , 0
  4624.6      .1       0  4847.4     .12       0  4990.4     .07       0
  4996.4     .12       0  5135.7     .16       0  5393.3      .1       0
  5439.2     .16       0
Bank Sta=4990.4,4996.4
XS Rating Curve= 0 ,0
Exp/Cntr=0.3,0.1

Type RM Length L Ch R = 1 ,7775    ,489,489,489
BEGIN DESCRIPTION:
PEACH CREEK SOUTH TRIB 10 12.0
END DESCRIPTION:
XS GIS Cut Line= 3
      3581242.09     10167441.66      3581717.52     10167130.52
      3581871.01     10166696.03
#Sta/Elev= 30
  4616.7  248.81  4671.7  246.28  4681.5  246.47  4738.8   243.9    4784  243.61
  4790.1  242.86  4832.3  241.57  4855.7   241.6  4934.9  239.28    4950   239.1
  4955.9  239.87  4992.1  239.08  4996.2  235.51  4998.9  235.01  5002.2  235.51
  5013.2  238.25  5022.3  239.61  5098.8  241.12  5173.1  242.72  5282.9  248.11
  5314.6  250.21  5335.6  250.98  5361.2  253.48  5366.5  253.32  5417.4  256.92
  5470.1  258.41  5510.5     257  5520.3  256.04  5577.7   253.5  5645.7  251.55
#Mann= 9 ,-1 , 0
  4616.7     .16       0  4671.7     .12       0  4996.2     .07       0
  5002.2     .12       0  5098.8      .1       0  5282.9     .12       0
  5314.6     .16       0  5417.4      .1       0  5520.3     .16       0
Bank Sta=4996.2,5002.2
XS Rating Curve= 0 ,0
Exp/Cntr=0.3,0.1

Type RM Length L Ch R = 1 ,7286    ,1072,1072,1072
BEGIN DESCRIPTION:
PEACH CREEK SOUTH TRIB 10 11.0
END DESCRIPTION:
XS GIS Cut Line= 3
      3581542.15     10167591.63      3582092.52     10167422.18
      3582572.65     10167084.26
#Sta/Elev= 30
  4656.4  245.55  4705.4  243.55  4841.4   238.6  4977.4  237.33  4998.6  234.82
  5001.4  234.32  5004.6  234.82  5022.6  237.71  5106.3  239.22  5137.7  238.45
  5158.6  235.97  5178.7  237.49  5183.9  239.05  5221.9  237.42  5229.4  236.13
  5235.1  236.13    5246  237.96  5290.4  238.05  5296.5  240.68  5317.4  243.65
  5409.6  251.02  5519.5  258.11    5570  260.41  5611.9   261.5  5620.5  262.51
  5662.4  262.75  5706.8  264.56  5712.9  263.97  5778.2  267.47  5819.4  268.47
#Mann= 5 ,-1 , 0
  4656.4     .16       0  4705.4     .12       0  4998.6     .07       0
  5004.6     .12       0  5409.6     .16       0
Bank Sta=4998.6,5004.6
XS Rating Curve= 0 ,0
Exp/Cntr=0.3,0.1

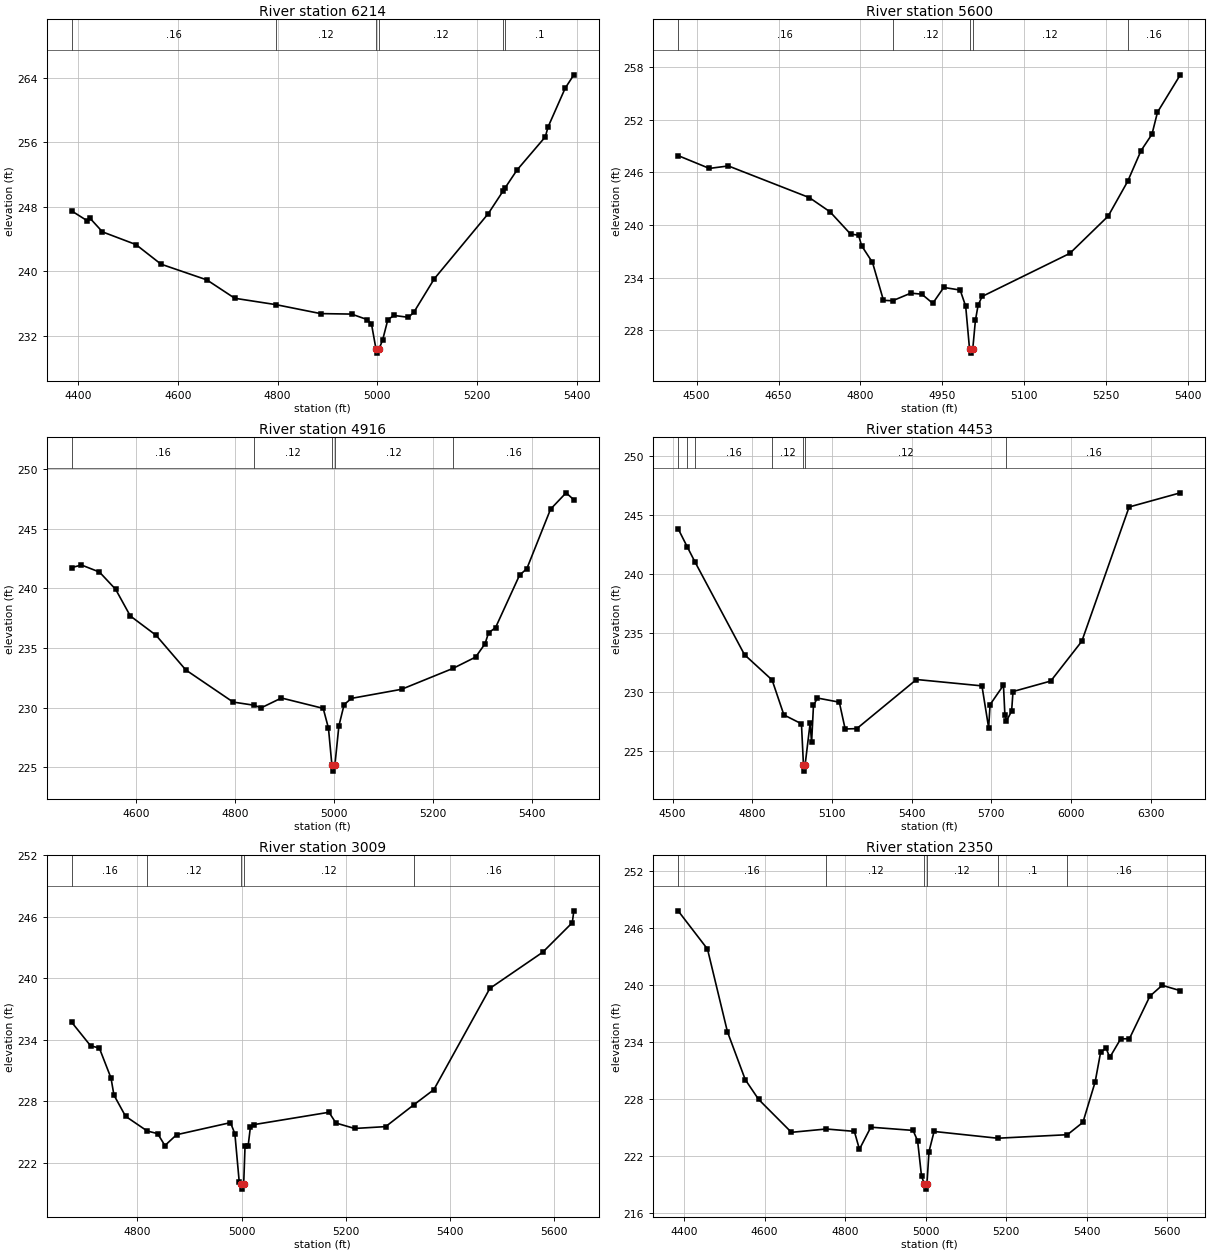
Type RM Length L Ch R = 1 ,6214    ,614,614,614
BEGIN DESCRIPTION:
PEACH CREEK SOUTH TRIB 10 9.0
END DESCRIPTION:
XS GIS Cut Line= 3
       3582245.3     10168352.73      3582391.13     10167949.96
       3582542.1     10167391.67
#Sta/Elev= 30
  4387.1   247.5  4418.3  246.28  4423.6  246.61  4448.9   244.9  4515.9  243.33
  4566.2   240.9  4658.1  238.95  4714.1  236.67  4796.7  235.88  4886.2  234.77
  4948.2  234.71  4979.5  234.03  4988.1   233.5  4997.2  230.37  4999.9  229.87
  5003.2  230.37  5010.5   231.5  5020.9  234.01  5033.2  234.54  5062.3  234.31
    5073  234.93  5114.1  239.09  5222.2  247.16  5252.1  249.98  5255.2  250.28
  5279.9  252.57  5336.6  256.68    5342  257.89  5376.5  262.72  5393.8  264.37
#Mann= 6 ,-1 , 0
  4387.1     .16       0  4796.7     .12       0  4997.2     .07       0
  5003.2     .12       0  5252.1     .16       0  5255.2      .1       0
Bank Sta=4997.2,5003.2
XS Rating Curve= 0 ,0
Exp/Cntr=0.3,0.1

Type RM Length L Ch R = 1 ,5600    ,684,684,684
BEGIN DESCRIPTION:
PEACH CREEK SOUTH TRIB 10 7.0
END DESCRIPTION:
XS GIS Cut Line= 3
      3582856.43     10168331.87      3582992.11     10168091.64
       3582932.8     10167449.98
#Sta/Elev= 30
    4466  247.92  4523.2  246.46  4558.1  246.74  4706.5  243.13  4744.4  241.51
  4782.1  238.97  4796.7  238.85  4802.2  237.65  4822.2  235.74  4842.3  231.42
    4859  231.37  4892.5  232.24  4912.6  232.12  4932.7  231.08  4952.8  232.89
  4982.9  232.59    4993  230.74    5000   225.9  5002.8   225.4    5006   225.9
  5010.8  229.13  5015.8  230.88  5023.1  231.86  5183.8  236.77  5254.1  241.02
  5289.8  244.98  5314.3  248.48  5334.4  250.36  5344.5  252.87  5386.3  257.13
#Mann= 5 ,-1 , 0
    4466     .16       0    4859     .12       0    5000     .07       0
    5006     .12       0  5289.8     .16       0
Bank Sta=5000,5006
XS Rating Curve= 0 ,0
Exp/Cntr=0.3,0.1

Type RM Length L Ch R = 1 ,4916    ,463,463,463
BEGIN DESCRIPTION:
PEACH CREEK SOUTH TRIB 10 6.0
END DESCRIPTION:
XS GIS Cut Line= 3
      3583238.34     10168443.04      3583371.19     10168141.76
      3583592.11     10167491.64
#Sta/Elev= 30
  4469.7  241.74  4489.5  241.96  4525.9  241.37  4558.7  239.92  4588.3  237.69
  4640.4  236.07  4700.7  233.16  4796.3  230.47  4839.2   230.2  4852.8  229.98
  4894.1  230.81  4978.6  229.94  4989.2  228.28  4996.2  225.18  4998.9  224.68
  5002.2  225.18  5010.3  228.47  5020.9  230.26  5035.8  230.78  5137.1  231.54
    5241  233.29  5286.9  234.24    5306  235.36    5313  236.27  5327.2  236.71
  5375.8  241.11  5390.5  241.65  5438.5  246.64  5469.9  248.01  5485.6  247.43
#Mann= 5 ,-1 , 0
  4469.7     .16       0  4839.2     .12       0  4996.2     .07       0
  5002.2     .12       0    5241     .16       0
Bank Sta=4996.2,5002.2
XS Rating Curve= 0 ,0
Exp/Cntr=0.3,0.1

Type RM Length L Ch R = 1 ,4453    ,1444,1444,1444
BEGIN DESCRIPTION:
PEACH CREEK SOUTH TRIB 10 5.0
END DESCRIPTION:
XS GIS Cut Line= 3
      3583542.13      10168641.6      3583953.63     10167866.63
        3584905.     10167519.41
#Sta/Elev= 30
  4520.9  243.85  4555.6   242.3    4585  241.01  4770.8  233.18  4874.6  231.04
  4919.1  228.08  4985.1  227.33  4992.7  223.82  4995.4  223.32  4998.7  223.82
  5017.7  227.36  5023.3  225.76  5030.4  228.89  5045.3  229.51  5127.6  229.16
  5149.6  226.89  5193.5  226.92    5418  231.08  5664.5  230.54  5689.7  226.99
  5695.1  228.95  5745.5   230.6  5750.8   228.1  5756.9  227.58  5776.1  228.39
  5781.4  230.06  5923.5  230.95  6040.4  234.32  6218.4  245.69  6411.1  246.89
#Mann= 7 ,-1 , 0
  4520.9     .16       0  4555.6      .1       0    4585     .16       0
  4874.6     .12       0  4992.7     .07       0  4998.7     .12       0
  5756.9     .16       0
#XS Ineff= 1 ,-1
 5418.18 6026.14  230.96
Permanent Ineff=
       F
Bank Sta=4992.7,4998.7
XS Rating Curve= 0 ,0
Exp/Cntr=0.3,0.1

Type RM Length L Ch R = 1 ,3009    ,659,659,659
BEGIN DESCRIPTION:
PEACH CREEK SOUTH TRIB 10 4.0
END DESCRIPTION:
XS GIS Cut Line= 3
       3584192.1     10168791.65      3584492.11     10168641.64
      3585008.17       10168284.
#Sta/Elev= 30
    4674  235.73  4710.3  233.43  4727.1  233.21  4749.5  230.28  4755.1  228.62
  4777.4  226.55    4819  225.11  4838.9  224.86  4852.9  223.69  4875.3  224.75
  4978.7  225.93  4987.1  224.84  4995.4  220.17    4998  219.94  5000.8  219.44
    5004  219.94  5006.6  223.64  5012.5  223.64  5016.8  225.47  5022.9  225.73
  5167.6  226.94    5181  225.89  5216.8  225.36  5276.3  225.54  5330.6  227.68
  5368.8  229.15  5476.2  239.03  5577.6  242.56  5634.3  245.44  5637.3   246.6
#Mann= 5 ,-1 , 0
    4674     .16       0    4819     .12       0    4998     .07       0
    5004     .12       0  5330.6     .16       0
Bank Sta=4998,5004
XS Rating Curve= 0 ,0
Exp/Cntr=0.3,0.1

Type RM Length L Ch R = 1 ,2350    ,1111,1111,1111
BEGIN DESCRIPTION:
PEACH CREEK SOUTH TRIB 10 2.0
END DESCRIPTION:
XS GIS Cut Line= 3
      3584192.15     10169141.63      3585064.74     10168887.46
       3585348.2      10168704.2
#Sta/Elev= 30
  4385.6  247.78  4458.5  243.76    4508  235.07  4552.2  230.04  4585.4  227.96
  4666.8   224.5  4753.4  224.85    4823   224.6  4835.6  222.72  4863.9  225.04
  4968.8   224.7    4980   223.6  4989.7   219.9  4997.1  219.03  4999.8  218.53
  5003.1  219.03  5008.3  222.48  5020.9  224.59  5178.5  223.88  5351.8  224.25
  5390.3  225.55  5420.6  229.79  5434.2  232.91  5447.7  233.35  5456.9  232.37
    5484  234.32  5505.7  234.34  5556.5  238.81  5586.9  239.95    5632  239.39
#Mann= 6 ,-1 , 0
  4385.6     .16       0  4753.4     .12       0  4997.1     .07       0
  5003.1     .12       0  5178.5      .1       0  5351.8     .16       0
Bank Sta=4997.1,5003.1
XS Rating Curve= 0 ,0
Exp/Cntr=0.3,0.1

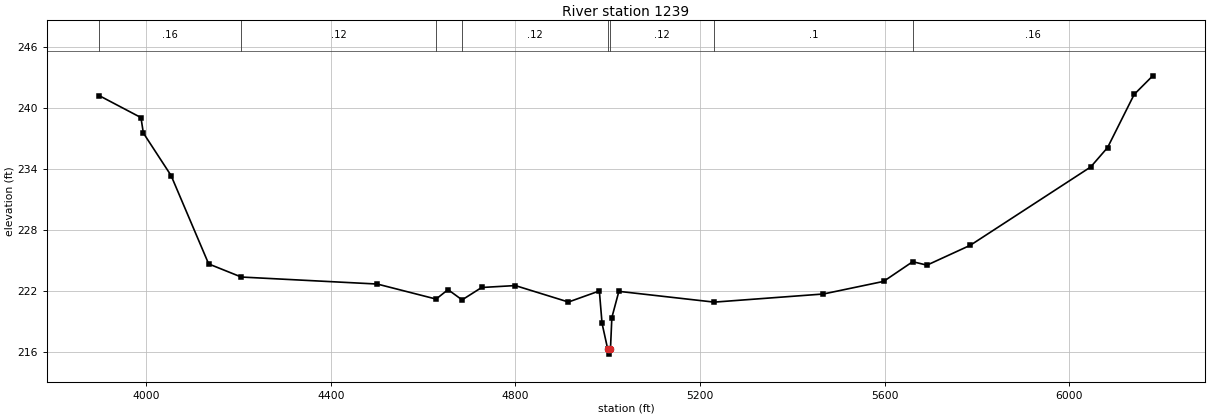
Type RM Length L Ch R = 1 ,1239    ,0,0,0
BEGIN DESCRIPTION:
PEACH CREEK SOUTH TRIB 10 1.0
END DESCRIPTION:
XS GIS Cut Line= 3
      3584192.15     10169391.65       3584870.3     10169581.91
      3586202.06     10168735.68
#Sta/Elev= 30
  3898.3  241.25  3988.7  239.09  3993.9  237.57    4054  233.38  4135.4  224.68
  4206.1  223.39  4500.6   222.7  4628.1  221.22  4653.9  222.15  4684.4  221.14
  4726.7  222.36  4799.6  222.55  4914.8  220.93  4981.7  222.02  4987.6  218.82
  4999.8   216.3  5002.6   215.8  5005.8   216.3  5008.8   219.4    5024  221.98
  5230.5  220.92    5467  221.72  5597.4  222.96  5660.5   224.9  5691.4  224.56
  5785.4  226.52  6046.2  234.23  6082.7  236.14  6140.3  241.37  6180.5   243.2
#Mann= 8 ,-1 , 0
  3898.3     .16       0  4206.1     .12       0  4628.1     .16       0
  4684.4     .12       0  4999.8     .07       0  5005.8     .12       0
  5230.5      .1       0  5660.5     .16       0
Bank Sta=4999.8,5005.8
XS Rating Curve= 0 ,0
Exp/Cntr=0.3,0.1

Chan Stop Cuts=-1
Use User Specified Reach Order=0
Composite Channel Slope=5