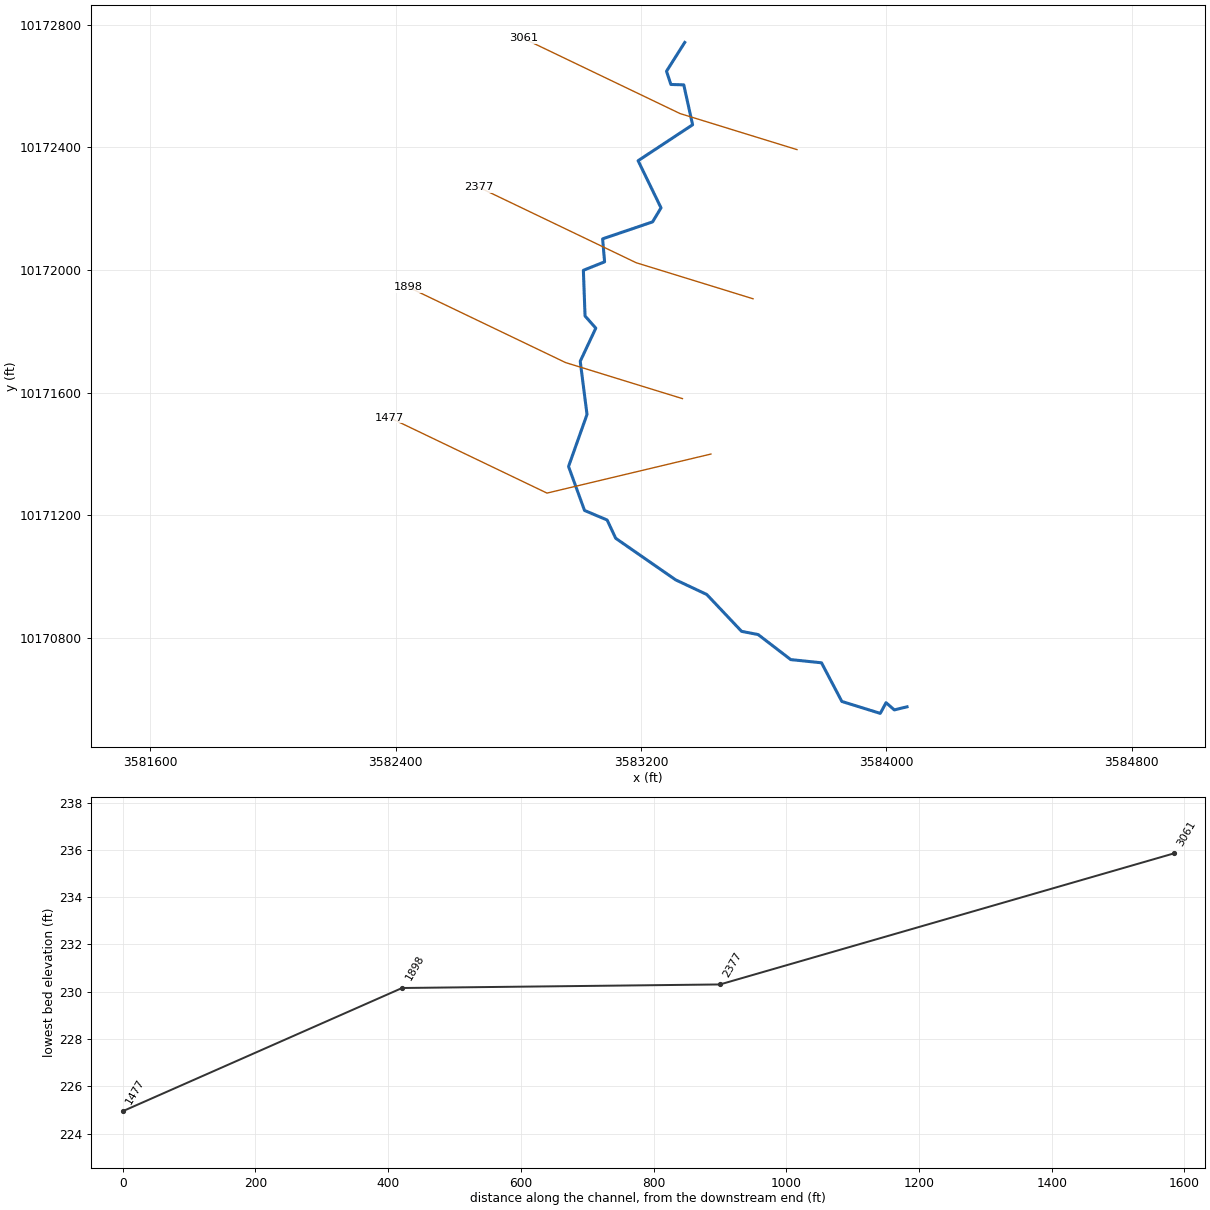
--- PEACH CREEK SOUTH TRIB 11.prj (project) ---

Proj Title=PEACH CREEK SOUTH TRIB 11 Base Level Engineering
Current Plan=p01
Default Exp/Contr=0.3,0.1
English Units
Geom File=g01
Flow File=f01
Plan File=p01
BEGIN DESCRIPTION:
PEACH CREEK SOUTH TRIB 11
END DESCRIPTION:

--- PEACH CREEK SOUTH TRIB 11.p01 (plan) ---

Plan Title=Multiple Run
Short Identifier=Multiple
Geom File=g01
Flow File=f01
Subcritical Flow
K Sum by GR= 0
Std Step Tol= 0.01
Critical Tol= 0.01
Num of Std Step Trials= 20
Max Error Tol= 0.3
Flow Tol Ratio= 0.001
Split Flow NTrial= 30
Split Flow Tol= 0.02
Split Flow Ratio= 0.02
Log Output Level= 0
Friction Slope Method= 1
Unsteady Friction Slope Method= 2
Unsteady Bridges Friction Slope Method= 1
Parabolic Critical Depth
Global Vel Dist=  1 , 1 , 1
Global Log Level= 0
CheckData=True
Encroach Param= -1, 0, 0, 0
BEGIN DESCRIPTION:
Multiple Run
END DESCRIPTION:

--- PEACH CREEK SOUTH TRIB 11.f01 (steady flow) ---

Flow Title=Multiple
Number of Profiles=7
Profile Names=10-year,25-year,50-year,1pct_min,100-year,1pct_plu,500-year
River Rch & RM= PEACH CREEK SOUT,Reach-1,3061
     195     245     284     242     327     442     432
Boundary for River Rch & Prof#=PEACH CREEK SOUT,Reach-1,1
Up Type=0
Dn Type=3
Dn Slope=0.005
Boundary for River Rch & Prof#=PEACH CREEK SOUT,Reach-1,2
Up Type=0
Dn Type=3
Dn Slope=0.005
Boundary for River Rch & Prof#=PEACH CREEK SOUT,Reach-1,3
Up Type=0
Dn Type=3
Dn Slope=0.005
Boundary for River Rch & Prof#=PEACH CREEK SOUT,Reach-1,4
Up Type=0
Dn Type=3
Dn Slope=0.005
Boundary for River Rch & Prof#=PEACH CREEK SOUT,Reach-1,5
Up Type=0
Dn Type=3
Dn Slope=0.005
Boundary for River Rch & Prof#=PEACH CREEK SOUT,Reach-1,6
Up Type=0
Dn Type=3
Dn Slope=0.005
Boundary for River Rch & Prof#=PEACH CREEK SOUT,Reach-1,7
Up Type=0
Dn Type=3
Dn Slope=0.005

--- PEACH CREEK SOUTH TRIB 11.g01 (geometry) ---

Geom Title=Existing Conditions

River Reach=PEACH CREEK SOUT,Reach-1
Reach XY= 30
      3583342.11     10172741.64      3583282.64     10172647.72
      3583296.86     10172604.65      3583338.96     10172603.35
      3583367.71     10172473.24      3583190.04     10172356.13
      3583264.74     10172202.46      3583237.21     10172156.72
      3583074.33     10172101.47      3583080.71     10172026.53
      3583011.54     10171998.90      3583017.02     10171849.98
      3583052.07     10171810.38      3583001.29     10171702.31
      3583023.42     10171529.13      3582963.20     10171359.52
      3583015.28     10171216.29      3583089.07     10171185.04
      3583116.99     10171125.48      3583312.31     10170990.10
      3583413.87     10170942.36      3583527.44     10170822.20
      3583581.41     10170811.72      3583687.74     10170730.12
      3583788.01     10170719.71      3583854.36     10170593.71
      3583979.69     10170554.84      3583998.58     10170589.65
      3584025.59     10170566.20      3584066.94     10170576.23

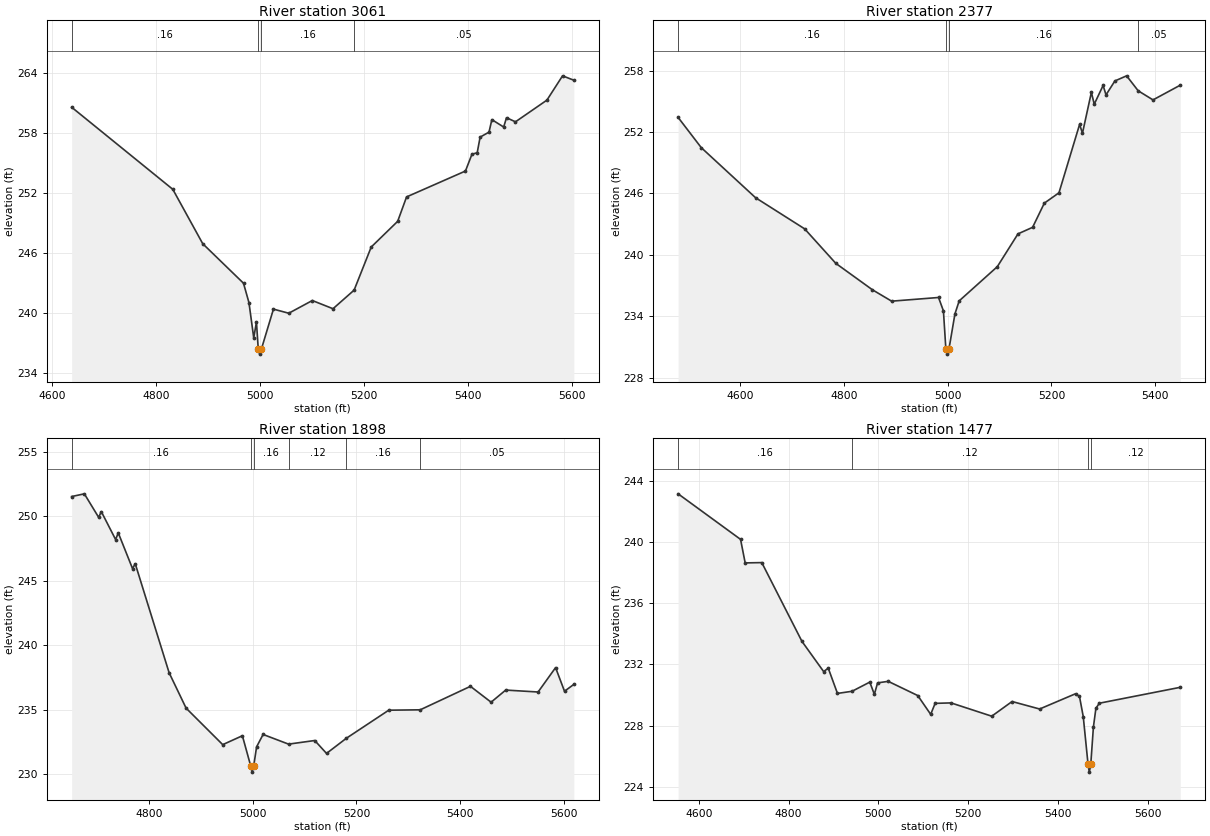
Type RM Length L Ch R = 1,3061,684,684,684
BEGIN DESCRIPTION:
PEACH CREEK SOUTH TRIB 11 4.0
END DESCRIPTION:
XS GIS Cut Line= 3
      3583708.03     10172392.30      3583326.95     10172509.76
      3582815.35     10172754.99
#Sta/Elev= 30
  4637.1  260.54  4831.7  252.33  4889.3  246.89  4967.7  242.94  4978.2  241.00
  4987.4  237.48  4992.6  239.06  4996.1  236.35  4998.8  235.85  5002.1  236.35
  5025.3  240.35  5054.8  239.94  5100.1  241.21  5139.9  240.39  5180.5  242.25
  5213.4  246.56  5264.3  249.13  5281.4  251.57  5394.7  254.16  5407.2  255.84
  5417.3  255.99  5422.9  257.55  5440.0  258.05  5445.5  259.30  5468.2  258.56
  5473.7  259.49  5490.9  259.08  5551.4  261.25  5581.5  263.68  5603.2  263.24
#Mann=4,-1,0
  4637.1    0.16       0  4996.1    0.07       0  5002.1    0.16       0
  5180.5    0.05       0
Bank Sta=4996.1,5002.1
Exp/Cntr=0.3,0.1

Type RM Length L Ch R = 1,2377,479,479,479
BEGIN DESCRIPTION:
PEACH CREEK SOUTH TRIB 11 3.0
END DESCRIPTION:
XS GIS Cut Line= 3
      3583564.74     10171906.21      3583183.72     10172023.65
      3582670.36     10172269.72
#Sta/Elev= 30
  4480.5  253.42  4525.1  250.47  4629.8  245.58  4724.4  242.54  4784.5  239.17
  4855.1  236.59  4892.1  235.48  4982.5  235.84  4991.9  234.53  4996.6  230.81
  4999.4  230.31  5002.6  230.81  5014.1  234.24  5022.3  235.51  5095.8  238.85
  5135.6  242.05  5163.8  242.69  5186.4  245.05  5214.6  246.06  5254.4  252.74
  5259.9  251.88  5277.1  255.87  5282.6  254.71  5299.7  256.54  5305.3  255.62
  5322.4  256.98  5345.0  257.48  5367.3  256.02  5395.9  255.13  5448.5  256.57
#Mann=4,-1,0
  4480.5    0.16       0  4996.6    0.07       0  5002.6    0.16       0
  5367.3    0.05       0
Bank Sta=4996.6,5002.6
Exp/Cntr=0.3,0.1

Type RM Length L Ch R = 1,1898,421,421,421
BEGIN DESCRIPTION:
PEACH CREEK SOUTH TRIB 11 2.0
END DESCRIPTION:
XS GIS Cut Line= 3
      3583334.71     10171580.69      3582953.69     10171698.13
      3582440.33     10171944.20
#Sta/Elev= 30
  4651.1  251.52  4675.6  251.73  4703.1  249.91  4708.3  250.35  4735.8  248.19
  4741.0  248.70  4768.4  245.94  4773.7  246.31  4839.0  237.86  4871.7  235.12
  4942.3  232.29  4980.2  232.98  4996.1  230.66  4998.9  230.16  5002.1  230.66
  5007.6  232.12  5020.1  233.08  5069.2  232.33  5119.7  232.61  5142.4  231.61
  5180.8  232.79  5262.3  234.96  5323.0  234.99  5419.8  236.81  5459.6  235.58
  5487.8  236.52  5550.2  236.37  5583.9  238.26  5601.1  236.43  5619.1  236.96
#Mann=6,-1,0
  4651.1    0.16       0  4996.1    0.07       0  5002.1    0.16       0
  5069.2    0.12       0  5180.8    0.16       0  5323.0    0.05       0
Bank Sta=4996.1,5002.1
Exp/Cntr=0.3,0.1

Type RM Length L Ch R = 1,1477,0,0,0
BEGIN DESCRIPTION:
PEACH CREEK SOUTH TRIB 11 1.0
END DESCRIPTION:
XS GIS Cut Line= 3
      3583427.46     10171400.05      3582892.92     10171272.78
      3582379.54     10171518.86
#Sta/Elev= 30
  4554.0  243.16  4693.1  240.18  4703.4  238.64  4740.4  238.66  4829.8  233.51
  4878.2  231.53  4888.5  231.75  4909.0  230.10  4941.5  230.24  4981.0  230.84
  4991.2  230.04  4998.4  230.79  5022.1  230.89  5087.9  229.96  5116.7  228.73
  5126.6  229.45  5162.0  229.48  5252.7  228.61  5298.0  229.57  5359.4  229.08
  5439.5  230.08  5448.2  229.90  5456.6  228.58  5467.3  225.45  5470.1  224.95
  5473.3  225.45  5479.2  227.90  5484.8  229.13  5492.5  229.46  5672.8  230.50
#Mann=4,-1,0
  4554.0    0.16       0  4941.5    0.12       0  5467.3    0.07       0
  5473.3    0.12       0
Bank Sta=5467.3,5473.3
Exp/Cntr=0.3,0.1

Chan Stop Cuts=-1