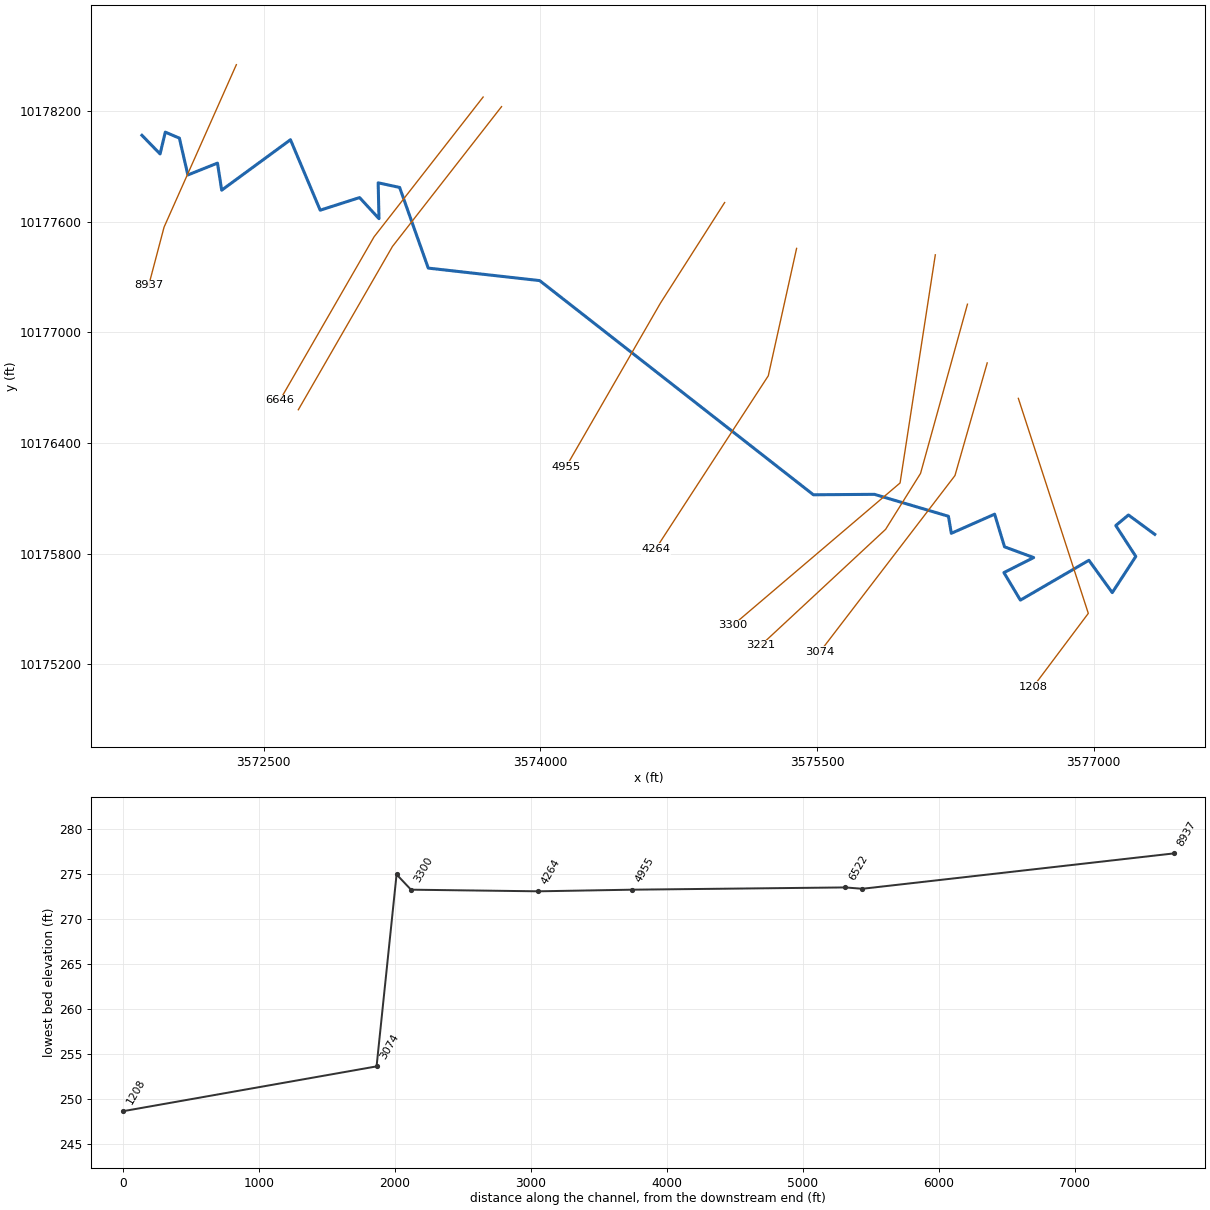
--- PEACH CREEK SOUTH TRIB 16 4.prj (project) ---

Proj Title=PEACH CREEK SOUTH TRIB 16 4 Base Level Engineering
Current Plan=p01
Default Exp/Contr=0.3,0.1
English Units
Geom File=g01
Flow File=f01
Plan File=p01
Y Axis Title=Elevation
X Axis Title(PF)=Main Channel Distance
X Axis Title(XS)=Station
BEGIN DESCRIPTION:
PEACH CREEK SOUTH TRIB 16 4
END DESCRIPTION:
DSS Export Rating Curves= 0
DSS Export Rating Curve Sorted= 0
DSS Export Volume Flow Curves= 0
DXF OffsetX= 0
DXF OffsetY= 0
DXF ScaleX= 1
DXF ScaleY= 10

--- PEACH CREEK SOUTH TRIB 16 4.p01 (plan) ---

Plan Title=Multiple Run
Short Identifier=Multiple
Geom File=g01
Flow File=f01
Subcritical Flow
K Sum by GR= 0
Std Step Tol= 0.01
Critical Tol= 0.01
Num of Std Step Trials= 20
Max Error Tol= 0.3
Flow Tol Ratio= 0.001
Split Flow NTrial= 30
Split Flow Tol= 0.02
Split Flow Ratio= 0.02
Log Output Level= 0
Friction Slope Method= 1
Unsteady Friction Slope Method= 2
Unsteady Bridges Friction Slope Method= 1
Parabolic Critical Depth
Global Vel Dist=  1 , 1 , 1
Global Log Level= 0
CheckData=True
Encroach Param= -1, 0, 0, 0
BEGIN DESCRIPTION:
Multiple Run
END DESCRIPTION:

--- PEACH CREEK SOUTH TRIB 16 4.f01 (steady flow) ---

Flow Title=Multiple
Program Version=4.10
Number of Profiles= 7
Profile Names=10-year,25-year,50-year,1pct_min,100-year,1pct_plu,500-year
River Rch & RM=PEACH CREEK SOUT,Reach-1         ,8937
     605     812     981     868    1174    1587    1683
Boundary for River Rch & Prof#=PEACH CREEK SOUT,Reach-1         , 1
Up Type= 0
Dn Type= 3
Dn Slope=0.008
Boundary for River Rch & Prof#=PEACH CREEK SOUT,Reach-1         , 2
Up Type= 0
Dn Type= 3
Dn Slope=0.008
Boundary for River Rch & Prof#=PEACH CREEK SOUT,Reach-1         , 3
Up Type= 0
Dn Type= 3
Dn Slope=0.008
Boundary for River Rch & Prof#=PEACH CREEK SOUT,Reach-1         , 4
Up Type= 0
Dn Type= 3
Dn Slope=0.008
Boundary for River Rch & Prof#=PEACH CREEK SOUT,Reach-1         , 5
Up Type= 0
Dn Type= 3
Dn Slope=0.008
Boundary for River Rch & Prof#=PEACH CREEK SOUT,Reach-1         , 6
Up Type= 0
Dn Type= 3
Dn Slope=0.008
Boundary for River Rch & Prof#=PEACH CREEK SOUT,Reach-1         , 7
Up Type= 0
Dn Type= 3
Dn Slope=0.008
DSS Import GetInterval= 0
DSS Import GetPeak= 0
DSS Import FillOption= 0

--- PEACH CREEK SOUTH TRIB 16 4.g01 (geometry) ---

Geom Title=Existing Conditions
Program Version=4.10

River Reach=PEACH CREEK SOUT,Reach-1
Reach XY= 30
      3571839.21     10178068.18      3571937.65     10177967.16
      3571965.94     10178085.36      3572042.31     10178052.85
      3572088.26     10177853.12      3572248.85     10177917.36
      3572271.82     10177770.71      3572644.69      10178044.1
       3572805.9     10177662.06      3573019.51      10177730.5
      3573124.72     10177616.14      3573120.38     10177810.59
       3573236.7     10177785.41      3573392.08     10177347.92
      3573996.25     10177280.21      3575480.62     10176118.75
      3575811.55     10176121.12      3576212.99      10176002.2
      3576228.62     10175909.75      3576463.43     10176013.48
      3576517.24      10175836.4      3576675.23     10175778.24
      3576513.77     10175696.64      3576603.18     10175547.34
      3576974.71     10175763.48      3577101.45     10175588.13
      3577229.05     10175784.31      3577120.54     10175951.85
      3577189.12     10176009.14      3577331.95     10175904.09

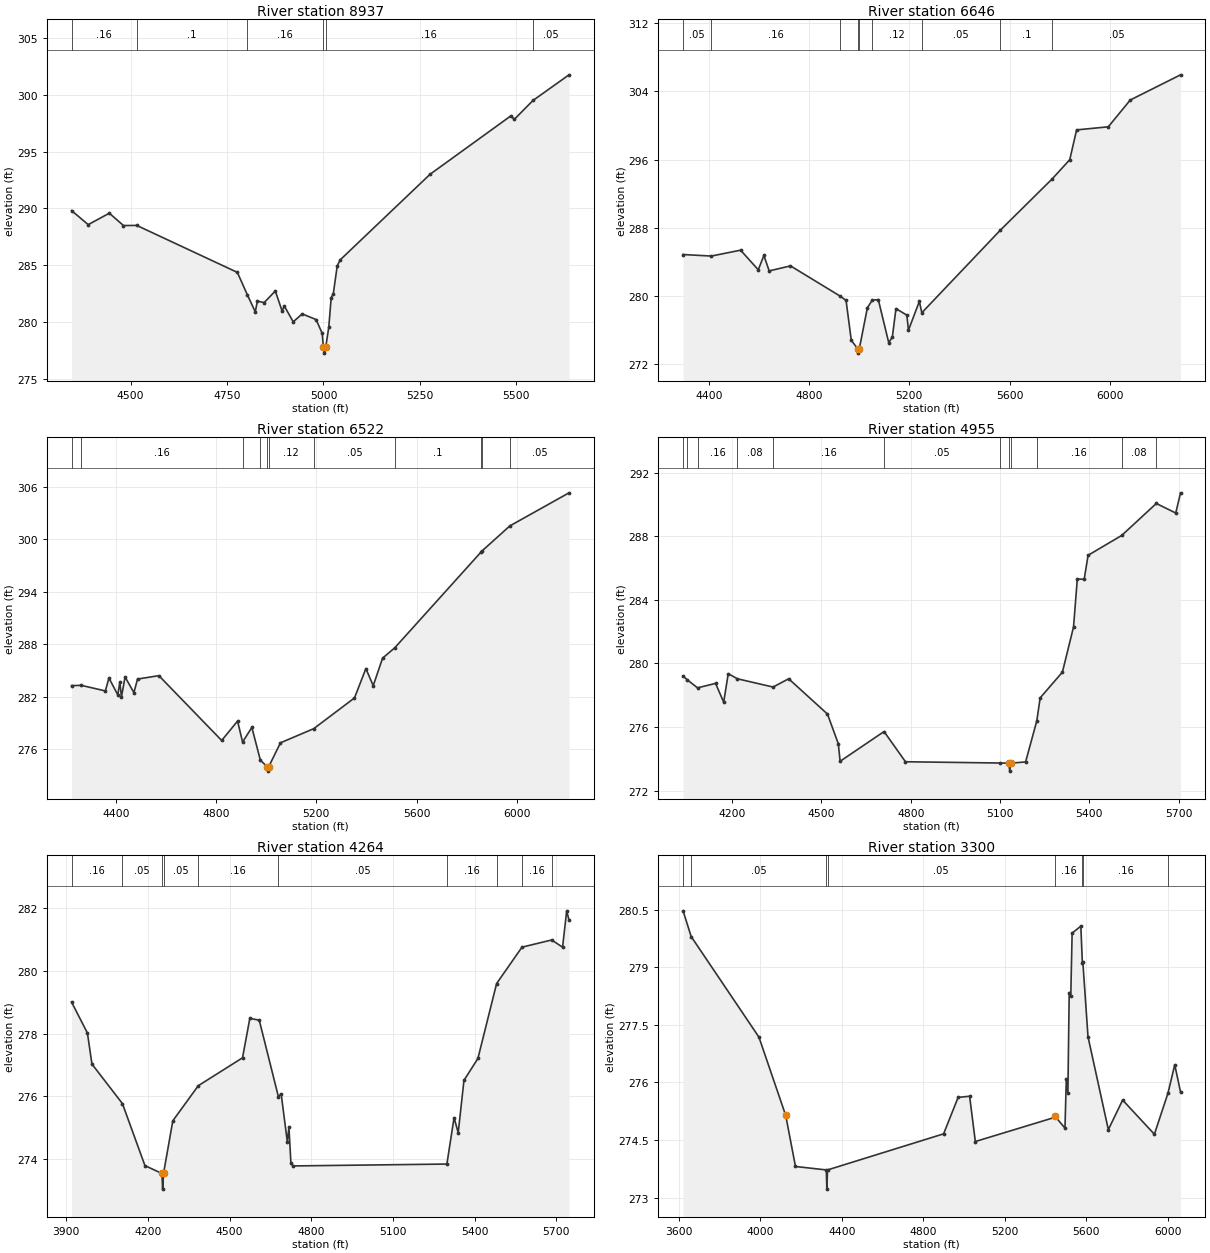
Type RM Length L Ch R = 1 ,8937    ,2291,2291,2291
BEGIN DESCRIPTION:
PEACH CREEK SOUTH TRIB 16.4 8.0
END DESCRIPTION:
XS GIS Cut Line= 3
      3572351.24     10178451.18       3571959.3     10177570.41
      3571876.05     10177254.95
#Sta/Elev= 30
  4346.6  289.81  4389.9  288.57  4444.6  289.58  4481.3  288.49  4515.8   288.5
  4776.7  284.36  4802.5  282.39  4823.2  280.88  4828.6  281.82  4846.4   281.7
  4875.1  282.72  4892.9  280.94  4898.4   281.4  4921.6     280  4944.9   280.7
  4980.9   280.2  4996.8  278.98  4999.8  277.74  5002.6  277.24  5005.8  277.74
  5013.8  279.53  5020.1  282.14  5025.5  282.47  5035.7  284.93  5043.3  285.46
  5276.5  293.01  5485.2  298.14  5495.5  297.87  5543.5  299.52  5636.9  301.78
#Mann= 6 ,-1 , 0
  4346.6     .16       0  4515.8      .1       0  4802.5     .16       0
  4999.8     .07       0  5005.8     .16       0  5543.5     .05       0
Bank Sta=4999.8,5005.8
XS Rating Curve= 0 ,0
Exp/Cntr=0.3,0.1

Type RM Length L Ch R = 1 ,6646    ,124,124,124
BEGIN DESCRIPTION:
PEACH CREEK SOUTH TRIB 16.4 7.2
END DESCRIPTION:
XS GIS Cut Line= 3
      3573689.56     10178275.75      3573097.96     10177517.37
      3572587.56     10176631.99
#Sta/Elev= 30
  4297.6  284.87    4410  284.69    4527  285.38  4597.5  283.08  4619.9  284.76
    4641  282.95    4726  283.54  4924.4  279.99  4947.6  279.49  4968.4  274.82
  4994.4  273.82  4997.1  273.32  5000.4  273.82  5032.6  278.64  5052.1  279.52
  5076.1  279.59  5117.7  274.55  5132.1   275.2  5146.6  278.53    5190  277.77
  5196.4     276  5239.8  279.38  5249.7  278.05  5563.3  287.74  5769.6  293.73
  5839.6  295.98  5866.9  299.47  5993.2  299.83  6080.9  302.97  6281.4  305.92
#Mann= 9 ,-1 , 0
  4297.6     .05       0    4410     .16       0  4924.4     .05       0
  4994.4     .04       0  5000.4     .05       0  5052.1     .12       0
  5249.7     .05       0  5563.3      .1       0  5769.6     .05       0
Bank Sta=4994.4,5000.4
XS Rating Curve= 0 ,0
Exp/Cntr=0.3,0.1

Type RM Length L Ch R = 1 ,6522    ,1567,1567,1567
BEGIN DESCRIPTION:
PEACH CREEK SOUTH TRIB 16.4 7.1
END DESCRIPTION:
XS GIS Cut Line= 3
      3573789.39     10178223.68      3573197.78     10177465.28
      3572687.35     10176579.83
#Sta/Elev= 30
  4223.7  283.26  4262.8  283.29  4358.5  282.65  4372.9  284.13  4408.2   282.2
  4416.4  283.68  4422.7  281.95  4437.2  284.25  4472.4  282.46  4486.9  284.01
    4572   284.4  4822.4  276.98  4885.8   279.2  4905.8   276.8  4942.8  278.47
  4976.8  274.72    5004  273.97  5006.8  273.47    5010  273.97  5056.8  276.71
  5189.5  278.33  5352.1  281.85  5397.5  285.21  5426.8  283.25  5464.1   286.4
  5513.4  287.61  5857.7  298.58  5862.5  298.72  5971.5  301.54  6207.6  305.33
#Mann= 11 ,-1 , 0
  4223.7     .05       0  4262.8     .16       0  4905.8     .05       0
  4976.8     .12       0    5004     .07       0    5010     .12       0
  5189.5     .05       0  5513.4      .1       0  5857.7     .05       0
  5862.5      .1       0  5971.5     .05       0
Bank Sta=5004,5010
XS Rating Curve= 0 ,0
Exp/Cntr=0.3,0.1

Type RM Length L Ch R = 1 ,4955    ,691,691,691
BEGIN DESCRIPTION:
PEACH CREEK SOUTH TRIB 16.4 7.0
END DESCRIPTION:
XS GIS Cut Line= 3
      3574999.26     10177703.58      3574650.32     10177156.73
       3574139.9     10176271.31
#Sta/Elev= 30
  4035.5   279.2    4050  278.96  4084.1  278.46  4144.6  278.74  4171.9  277.56
  4187.2  279.35  4218.1  279.03  4337.7  278.51  4390.2  279.03  4520.5  276.81
  4556.9  274.94  4562.9  273.84  4710.5  275.71  4782.4  273.81  5101.4  273.73
  5129.8  273.72  5132.5  273.22  5135.8  273.72  5185.9   273.8  5223.4  276.38
  5234.8  277.83  5309.5  279.45  5346.8  282.29  5359.5  285.31  5382.6  285.29
  5395.7   286.8  5508.7  288.05  5624.8  290.06  5690.1  289.46  5706.2  290.73
#Mann= 12 ,-1 , 0
  4035.5     .05       0    4050     .07       0  4084.1     .16       0
  4218.1     .08       0  4337.7     .16       0  4710.5     .05       0
  5101.4     .07       0  5129.8    .033       0  5135.8     .07       0
  5223.4     .16       0  5508.7     .08       0  5624.8     .05       0
Bank Sta=5129.8,5135.8
XS Rating Curve= 0 ,0
Exp/Cntr=0.3,0.1

Type RM Length L Ch R = 1 ,4264    ,937,937,937
BEGIN DESCRIPTION:
PEACH CREEK SOUTH TRIB 16.4 6.0
END DESCRIPTION:
XS GIS Cut Line= 3
      3575389.49     10177454.88      3575235.93     10176763.86
      3574625.34     10175825.03
#Sta/Elev= 30
  3919.1  279.01  3977.5  278.02  3994.1  277.03    4106  275.77  4188.8  273.79
  4251.1  273.54  4253.8  273.04  4257.1  273.54  4291.2  275.22  4384.8  276.34
  4547.3  277.23  4574.2  278.49  4608.8  278.43  4679.1  275.99  4689.3  276.08
  4711.9  274.55  4717.8  275.02  4725.1  273.87    4733  273.78  5298.2  273.84
  5324.6  275.32  5339.8  274.84  5360.9  276.51  5412.2  277.21  5480.9   279.6
  5574.1  280.76  5683.1  280.99  5723.2  280.76  5738.4  281.92  5746.9  281.62
#Mann= 10 ,-1 , 0
  3919.1     .16       0    4106     .05       0  4251.1    .033       0
  4257.1     .05       0  4384.8     .16       0  4679.1     .05       0
  5298.2     .16       0  5480.9     .05       0  5574.1     .16       0
  5683.1     .05       0
Bank Sta=4251.1,4257.1
XS Rating Curve= 0 ,0
Exp/Cntr=0.3,0.1

Type RM Length L Ch R = 1 ,3300    ,106,106,106
BEGIN DESCRIPTION:
PEACH CREEK SOUTH TRIB 16.4 5.0
END DESCRIPTION:
XS GIS Cut Line= 3
      3576141.79     10177419.95      3575950.67     10176182.77
      3575043.04     10175410.15
#Sta/Elev= 30
  3619.9  280.47  3659.7   279.8  3992.6  277.18  4124.1  275.14  4172.1  273.81
  4323.5  273.72  4326.2  273.22  4329.5  273.72  4899.7  274.66  4971.1  275.61
  5027.5  275.64  5055.6  274.46  5446.1  275.09  5446.6  275.12    5496  274.81
  5502.5  276.08  5510.3  275.73  5516.8  278.34  5524.5  278.25  5531.1  279.89
  5573.9  280.07  5581.4  279.12  5583.7  279.14  5609.1  277.19    5709  274.77
  5779.3  275.54  5935.2  274.65    6002  275.72  6035.2  276.46  6063.7  275.75
#Mann= 8 ,-1 , 0
  3619.9     .16       0  3659.7     .05       0  4323.5    .033       0
  4329.5     .05       0  5446.1     .16       0  5581.4     .05       0
  5583.7     .16       0    6002     .05       0
Bank Sta=4124.1,5446.6
XS Rating Curve= 0 ,0
Exp/Cntr=0.3,0.1

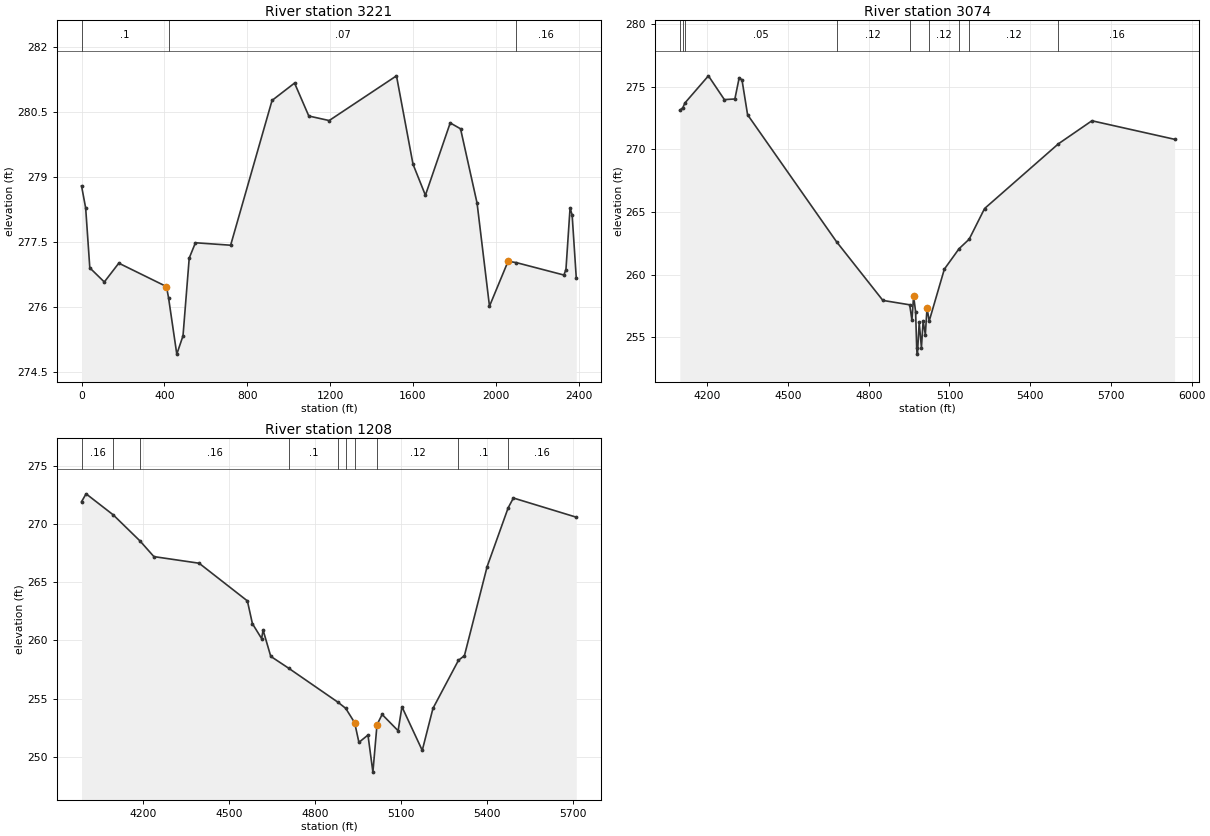
Type RM Length L Ch R = 1 ,3221    ,147,147,147
BEGIN DESCRIPTION:
PEACH CREEK SOUTH TRIB 16.4 4.0
END DESCRIPTION:
XS GIS Cut Line= 4
      3576316.12     10177152.38      3576061.78     10176234.85
      3575872.05       10175931.      3575196.03     10175302.64
#Sta/Elev= 30
       0278.788819.99421278.278539.98842276.8991109.9682276.5735179.9479277.0072
409.8813276.4681419.8784276.2153459.8668274.9108489.8582275.3321519.8495277.1246
549.8408277.4775719.7916277.4208919.7336 280.7581028.332281.15791097.114280.3986
1195.373280.29411520.315281.32481600.125279.28741659.983278.57271779.698280.2393
1829.579280.10411909.389278.38971969.247276.01562059.033277.05062098.938277.0199
2328.392 276.7342338.369276.86022358.321 278.2842368.297278.1145 2388.25276.6635
#Mann= 3 ,-1 , 0
       0      .1       0419.8784     .07       02098.938     .16       0
Bank Sta=409.8813,2059.033
XS Rating Curve= 0 ,0
Exp/Cntr=0.3,0.1

Type RM Length L Ch R = 1 ,3074    ,1866,1866,1866
BEGIN DESCRIPTION:
PEACH CREEK SOUTH TRIB 16.4 3.0
END DESCRIPTION:
XS GIS Cut Line= 3
      3576423.28     10176833.82      3576248.36     10176222.89
      3575516.65     10175267.59
#Sta/Elev= 30
  4097.7  273.12  4108.8  273.32  4116.6   273.7    4204  275.87  4263.3  273.97
  4302.3  274.02  4318.4  275.72  4328.8  275.54  4349.6  272.76  4680.1  262.62
  4852.4  257.93  4952.1  257.58  4960.3  256.36  4966.6  258.28  4974.1  257.02
  4978.1  254.14  4980.9  253.64  4987.4  256.17  4995.7  254.16    5002  256.28
  5010.2   255.2  5016.5  257.33  5024.5  256.28  5080.9  260.43  5135.5  262.06
  5173.1  262.82  5230.4  265.27  5504.8  270.44  5629.3  272.28  5936.5   270.8
#Mann= 9 ,-1 , 0
  4097.7     .05       0  4108.8     .16       0  4116.6     .05       0
  4680.1     .12       0  4952.1     .07       0  5024.5     .12       0
  5135.5     .05       0  5173.1     .12       0  5504.8     .16       0
Bank Sta=4966.6,5016.5
XS Rating Curve= 0 ,0
Exp/Cntr=0.3,0.1

Type RM Length L Ch R = 1 ,1208    ,0,0,0
BEGIN DESCRIPTION:
PEACH CREEK SOUTH TRIB 16.4 1.0
END DESCRIPTION:
XS GIS Cut Line= 3
      3576592.11     10176641.62      3576971.46     10175475.61
      3576671.86     10175076.14
#Sta/Elev= 30
  3986.6  271.93  4002.5  272.61  4097.2   270.8  4190.4  268.56    4239  267.21
  4396.7  266.64    4565   263.4  4582.6  261.44  4614.6  260.16  4619.8  260.89
  4646.5  258.63  4709.5   257.6  4881.1  254.68  4907.9  254.16  4939.2  252.92
    4954  251.23  4985.6  251.86  5002.8  248.67  5017.1  252.75    5035  253.63
  5090.7  252.23  5104.1  254.29  5174.9  250.54  5212.2  254.15  5301.2  258.29
    5322  258.69  5401.2  266.35  5474.6  271.41  5492.8  272.25  5712.1   270.6
#Mann= 10 ,-1 , 0
  3986.6     .16       0  4097.2      .1       0  4190.4     .16       0
  4709.5      .1       0  4881.1     .16       0  4907.9     .12       0
  4939.2     .07       0  5017.1     .12       0  5301.2      .1       0
  5474.6     .16       0
Bank Sta=4939.2,5017.1
XS Rating Curve= 0 ,0
Exp/Cntr=0.3,0.1
Stream Node=PEACH CREEK SOUT,Reach-1         , 0 , 0 ,Upstream end
Stream Node=PEACH CREEK SOUT,Reach-1         , 0 , 1 ,Downstream end

Chan Stop Cuts=-1
Use User Specified Reach Order=0
Composite Channel Slope=5