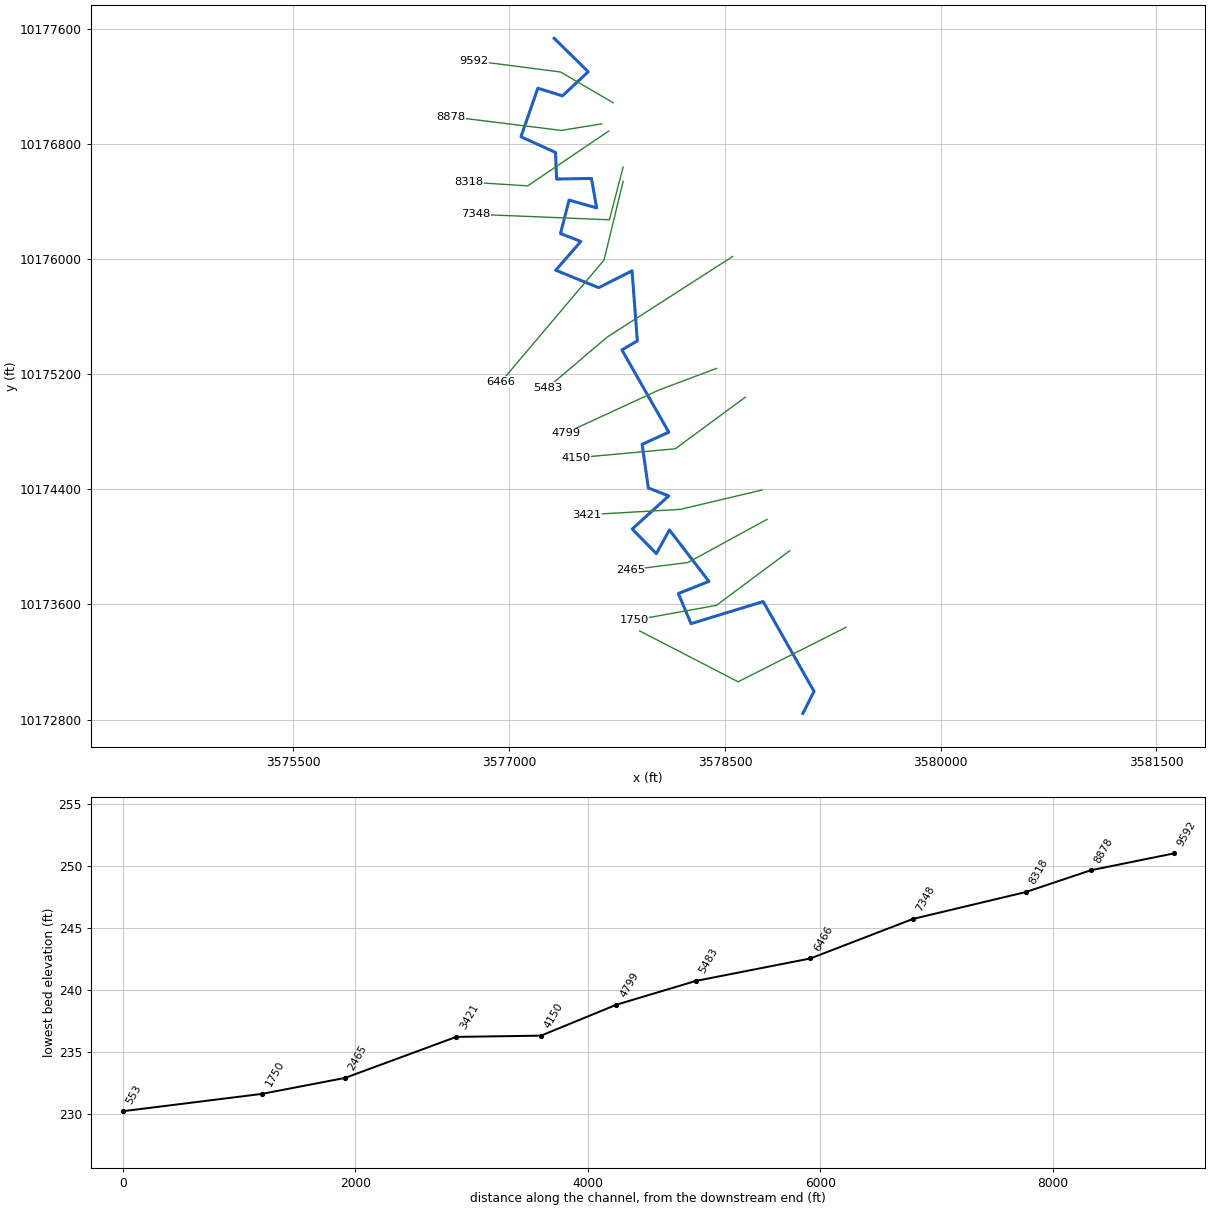
--- PEACH CREEK SOUTH TRIB 16.prj (project) ---

Proj Title=PEACH CREEK SOUTH TRIB 16 Base Level Engineering
Current Plan=p01
Default Exp/Contr=0.3,0.1
English Units
Geom File=g01
Flow File=f01
Plan File=p01
BEGIN DESCRIPTION:
PEACH CREEK SOUTH TRIB 16
END DESCRIPTION:

--- PEACH CREEK SOUTH TRIB 16.p01 (plan) ---

Plan Title=Multiple Run
Short Identifier=Multiple
Geom File=g01
Flow File=f01
Subcritical Flow
K Sum by GR= 0
Std Step Tol= 0.01
Critical Tol= 0.01
Num of Std Step Trials= 20
Max Error Tol= 0.3
Flow Tol Ratio= 0.001
Split Flow NTrial= 30
Split Flow Tol= 0.02
Split Flow Ratio= 0.02
Log Output Level= 0
Friction Slope Method= 1
Unsteady Friction Slope Method= 2
Unsteady Bridges Friction Slope Method= 1
Parabolic Critical Depth
Global Vel Dist=  1 , 1 , 1
Global Log Level= 0
CheckData=True
Encroach Param= -1, 0, 0, 0
BEGIN DESCRIPTION:
Multiple Run
END DESCRIPTION:

--- PEACH CREEK SOUTH TRIB 16.f01 (steady flow) ---

Flow Title=Multiple
Number of Profiles=7
Profile Names=10-year,25-year,50-year,1pct_min,100-year,1pct_plu,500-year
River Rch & RM= PEACH CREEK SOUT,Reach-1,9592
     628     843    1016     897    1214    1641    1735
River Rch & RM= PEACH CREEK SOUT,Reach-1,6466
    1147    1592    1964    1770    2394    3238    3569
Boundary for River Rch & Prof#=PEACH CREEK SOUT,Reach-1,1
Up Type=0
Dn Type=3
Dn Slope=0.005
Boundary for River Rch & Prof#=PEACH CREEK SOUT,Reach-1,2
Up Type=0
Dn Type=3
Dn Slope=0.005
Boundary for River Rch & Prof#=PEACH CREEK SOUT,Reach-1,3
Up Type=0
Dn Type=3
Dn Slope=0.005
Boundary for River Rch & Prof#=PEACH CREEK SOUT,Reach-1,4
Up Type=0
Dn Type=3
Dn Slope=0.005
Boundary for River Rch & Prof#=PEACH CREEK SOUT,Reach-1,5
Up Type=0
Dn Type=3
Dn Slope=0.005
Boundary for River Rch & Prof#=PEACH CREEK SOUT,Reach-1,6
Up Type=0
Dn Type=3
Dn Slope=0.005
Boundary for River Rch & Prof#=PEACH CREEK SOUT,Reach-1,7
Up Type=0
Dn Type=3
Dn Slope=0.005

--- PEACH CREEK SOUTH TRIB 16.g01 (geometry) ---

Geom Title=Existing Conditions

River Reach=PEACH CREEK SOUT,Reach-1
Reach XY= 30
      3577312.65     10177536.29      3577549.53     10177304.22
      3577370.43     10177136.25      3577198.87     10177189.75
      3577081.97     10176851.96      3577322.09     10176742.73
      3577329.58     10176558.10      3577571.94     10176562.16
      3577608.08     10176357.38      3577416.05     10176411.46
      3577356.89     10176179.11      3577497.96     10176124.19
      3577323.90     10175923.96      3577622.38     10175802.75
      3577854.03     10175919.68      3577890.99     10175433.15
      3577783.85     10175369.57      3578109.65     10174797.95
      3577924.21     10174713.28      3577967.35     10174410.46
      3578108.79     10174354.73      3577855.48     10174124.78
      3578023.00     10173953.73      3578114.07     10174118.13
      3578388.79     10173760.45      3578176.00     10173676.29
      3578264.06     10173466.77      3578765.85     10173620.26
      3579119.52     10172995.95      3579042.11     10172842.96

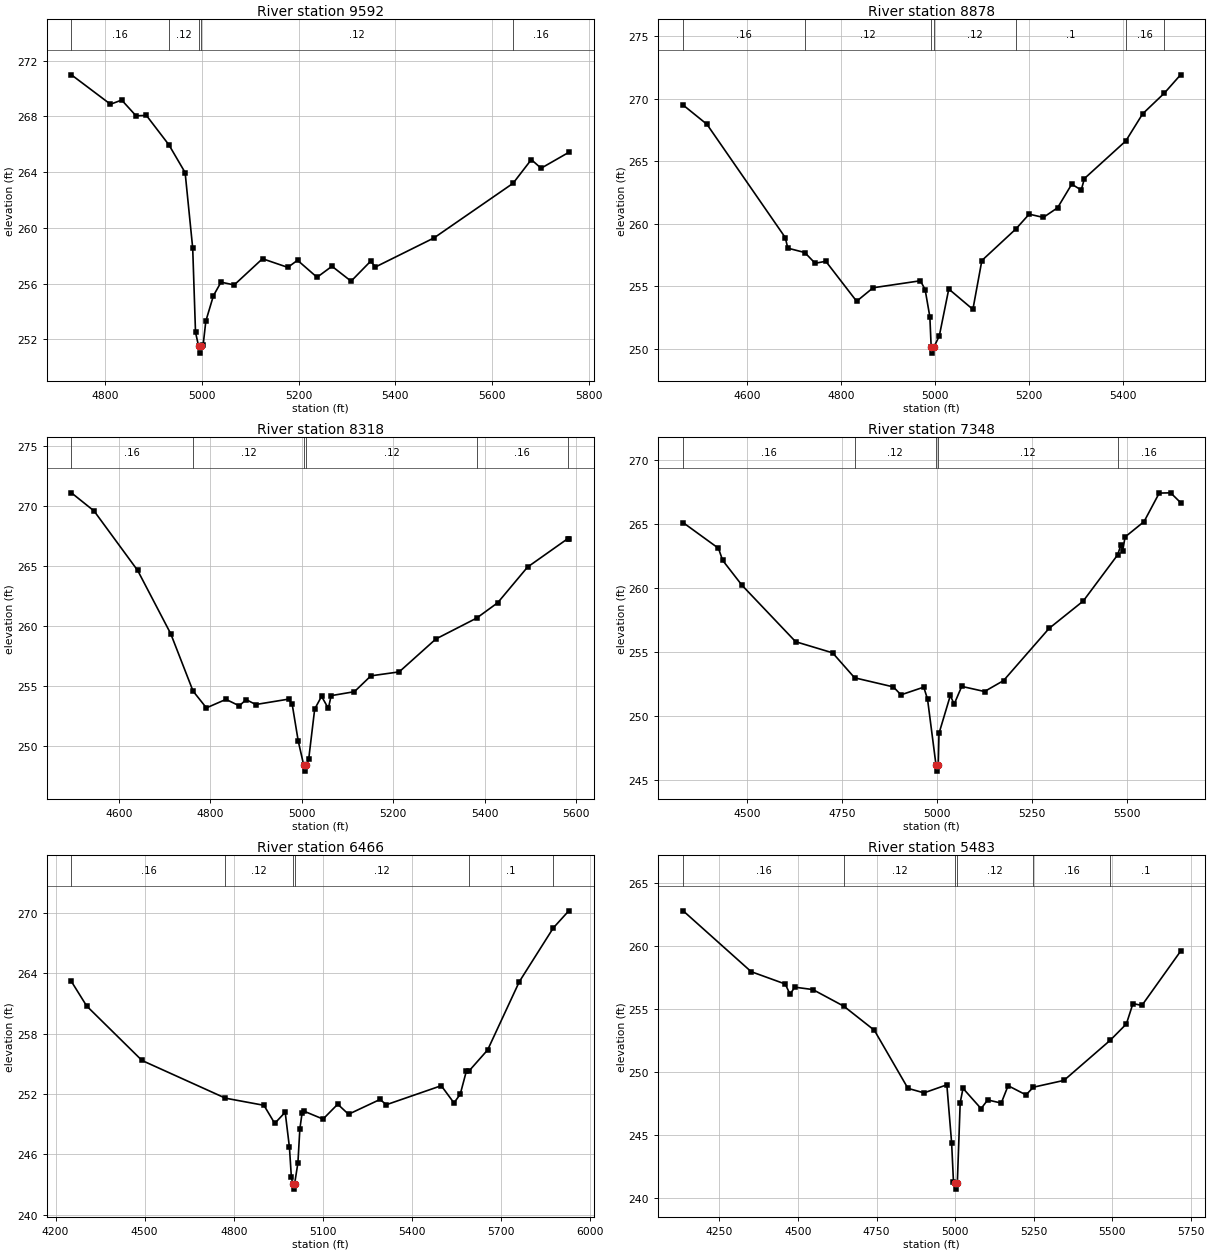
Type RM Length L Ch R = 1,9592,714,714,714
BEGIN DESCRIPTION:
PEACH CREEK SOUTH TRIB 16 14.0
END DESCRIPTION:
XS GIS Cut Line= 3
      3577721.93     10177088.68      3577357.35     10177302.22
      3576755.17     10177380.09
#Sta/Elev= 30
  4729.5  270.98  4810.4  268.87  4833.6  269.17  4863.3  268.04  4884.7  268.07
  4931.3  265.96  4964.9  263.97  4980.6  258.55  4986.4  252.52  4992.8  251.52
  4995.6  251.02  4998.8  251.52  5002.1  251.57  5007.8  253.32  5023.5  255.14
  5039.2  256.11  5066.5  255.91  5125.1  257.79  5177.5  257.17  5197.6  257.68
  5238.0  256.46  5268.9  257.25  5308.5  256.18  5348.9  257.61  5359.0  257.20
  5480.0  259.28  5643.8  263.20  5681.6  264.90  5701.8  264.28  5759.2  265.42
#Mann=5,-1,0
  4729.5    0.16       0  4931.3    0.12       0  4992.8    0.07       0
  4998.8    0.12       0  5643.8    0.16       0
Bank Sta=4992.8,4998.8
Exp/Cntr=0.3,0.1

Type RM Length L Ch R = 1,8878,560,560,560
BEGIN DESCRIPTION:
PEACH CREEK SOUTH TRIB 16 13.0
END DESCRIPTION:
XS GIS Cut Line= 3
      3577642.14     10176941.65      3577362.55     10176895.97
      3576592.07     10176991.65
#Sta/Elev= 30
  4463.1  269.51  4513.8  267.97  4680.6  258.91  4686.1  258.06  4722.2  257.71
  4744.3  256.85  4767.0  257.01  4832.7  253.81  4867.8  254.89  4968.5  255.45
  4978.6  254.75  4988.7  252.56  4991.5  250.16  4994.3  249.66  4997.5  250.16
  5008.8  251.03  5029.0  254.79  5080.4  253.16  5099.5  257.07  5171.8  259.59
  5200.3  260.78  5230.5  260.52  5260.8  261.29  5291.0  263.18  5311.2  262.71
  5318.0  263.63  5406.2  266.64  5442.1  268.81  5488.4  270.47  5522.8  271.93
#Mann=7,-1,0
  4463.1    0.16       0  4722.2    0.12       0  4991.5    0.07       0
  4997.5    0.12       0  5171.8     0.1       0  5406.2    0.16       0
  5488.4    0.05       0
Bank Sta=4991.5,4997.5
Exp/Cntr=0.3,0.1

Type RM Length L Ch R = 1,8318,970,970,970
BEGIN DESCRIPTION:
PEACH CREEK SOUTH TRIB 16 12.0
END DESCRIPTION:
XS GIS Cut Line= 3
      3577692.13     10176891.66      3577128.18     10176510.56
      3576721.95     10176536.60
#Sta/Elev= 30
  4496.0  271.09  4545.5  269.58  4640.9  264.62  4713.3  259.34  4762.0  254.57
  4791.2  253.17  4834.0  253.88  4863.1  253.34  4878.1  253.86  4899.1  253.45
  4971.0  253.90  4978.8  253.47  4992.0  250.41  5004.0  248.40  5006.7  247.90
  5010.0  248.40  5015.0  248.93  5028.0  253.07  5043.0  254.13  5057.9  253.13
  5064.0  254.19  5114.9  254.52  5150.9  255.84  5212.8  256.17  5293.0  258.91
  5382.1  260.65  5428.2  261.93  5493.4  264.90  5581.8  267.28  5583.7  267.28
#Mann=6,-1,0
  4496.0    0.16       0  4762.0    0.12       0  5004.0    0.07       0
  5010.0    0.12       0  5382.1    0.16       0  5581.8     0.1       0
Bank Sta=5004,5010
Exp/Cntr=0.3,0.1

Type RM Length L Ch R = 1,7348,882,882,882
BEGIN DESCRIPTION:
PEACH CREEK SOUTH TRIB 16 11.0
END DESCRIPTION:
XS GIS Cut Line= 3
      3577792.12     10176641.68      3577696.78     10176274.74
      3576765.99     10176312.93
#Sta/Elev= 30
  4331.4  265.14  4424.4  263.14  4435.4  262.20  4486.4  260.25  4627.8  255.84
  4725.2  254.97  4783.2  253.02  4885.3  252.31  4905.4  251.69  4965.4  252.29
  4975.4  251.35  4997.6  246.23  5000.3  245.73  5003.6  246.23  5005.6  248.68
  5035.5  251.64  5045.5  250.96  5065.5  252.35  5125.5  251.95  5175.6  252.80
  5295.7  256.88  5385.8  259.02  5476.3  262.62  5484.7  263.38  5489.7  262.95
  5495.9  264.02  5545.9  265.22  5585.9  267.45  5616.0  267.47  5642.1  266.71
#Mann=5,-1,0
  4331.4    0.16       0  4783.2    0.12       0  4997.6    0.07       0
  5003.6    0.12       0  5476.3    0.16       0
Bank Sta=4997.6,5003.6
Exp/Cntr=0.3,0.1

Type RM Length L Ch R = 1,6466,983,983,983
BEGIN DESCRIPTION:
PEACH CREEK SOUTH TRIB 16 10.0
END DESCRIPTION:
XS GIS Cut Line= 3
      3577792.10     10176541.64      3577659.43     10175994.93
      3576942.13     10175146.48
#Sta/Elev= 30
  4253.5  263.20  4304.9  260.76  4491.0  255.34  4771.7  251.59  4901.3  250.88
  4937.6  249.08  4972.8  250.19  4987.1  246.70  4993.6  243.73  4998.4  243.04
  5001.1  242.54  5004.4  243.04  5015.6  245.15  5022.2  248.54  5029.9  250.16
  5036.5  250.29  5100.2  249.51  5149.6  250.99  5185.9  249.99  5291.8  251.46
  5313.4  250.94  5498.0  252.83  5540.6  251.12  5561.7  251.97  5582.5  254.29
  5590.6  254.27  5654.0  256.39  5760.6  263.18  5875.0  268.53  5927.1  270.23
#Mann=6,-1,0
  4253.5    0.16       0  4771.7    0.12       0  4998.4    0.07       0
  5004.4    0.12       0  5590.6     0.1       0  5875.0    0.16       0
Bank Sta=4998.4,5004.4
Exp/Cntr=0.3,0.1

Type RM Length L Ch R = 1,5483,684,684,684
BEGIN DESCRIPTION:
PEACH CREEK SOUTH TRIB 16 8.0
END DESCRIPTION:
XS GIS Cut Line= 3
      3578554.34     10176019.98      3577680.26     10175458.47
      3577265.00     10175105.50
#Sta/Elev= 30
  4134.3  262.82  4350.9  257.99  4459.4  257.01  4474.6  256.20  4489.8  256.76
  4547.3  256.57  4645.9  255.25  4743.1  253.34  4850.1  248.73  4901.3  248.37
  4974.0  249.01  4989.2  244.41  4995.1  241.31  5001.4  241.23  5004.1  240.73
  5007.4  241.23  5016.5  247.59  5025.5  248.73  5083.0  247.12  5104.1  247.81
  5147.2  247.56  5169.1  248.94  5226.1  248.21  5249.4  248.82  5346.9  249.36
  5494.0  252.54  5545.7  253.84  5566.6  255.46  5595.1  255.31  5718.2  259.61
#Mann=6,-1,0
  4134.3    0.16       0  4645.9    0.12       0  5001.4    0.07       0
  5007.4    0.12       0  5249.4    0.16       0  5494.0     0.1       0
Bank Sta=5001.4,5007.4
Exp/Cntr=0.3,0.1

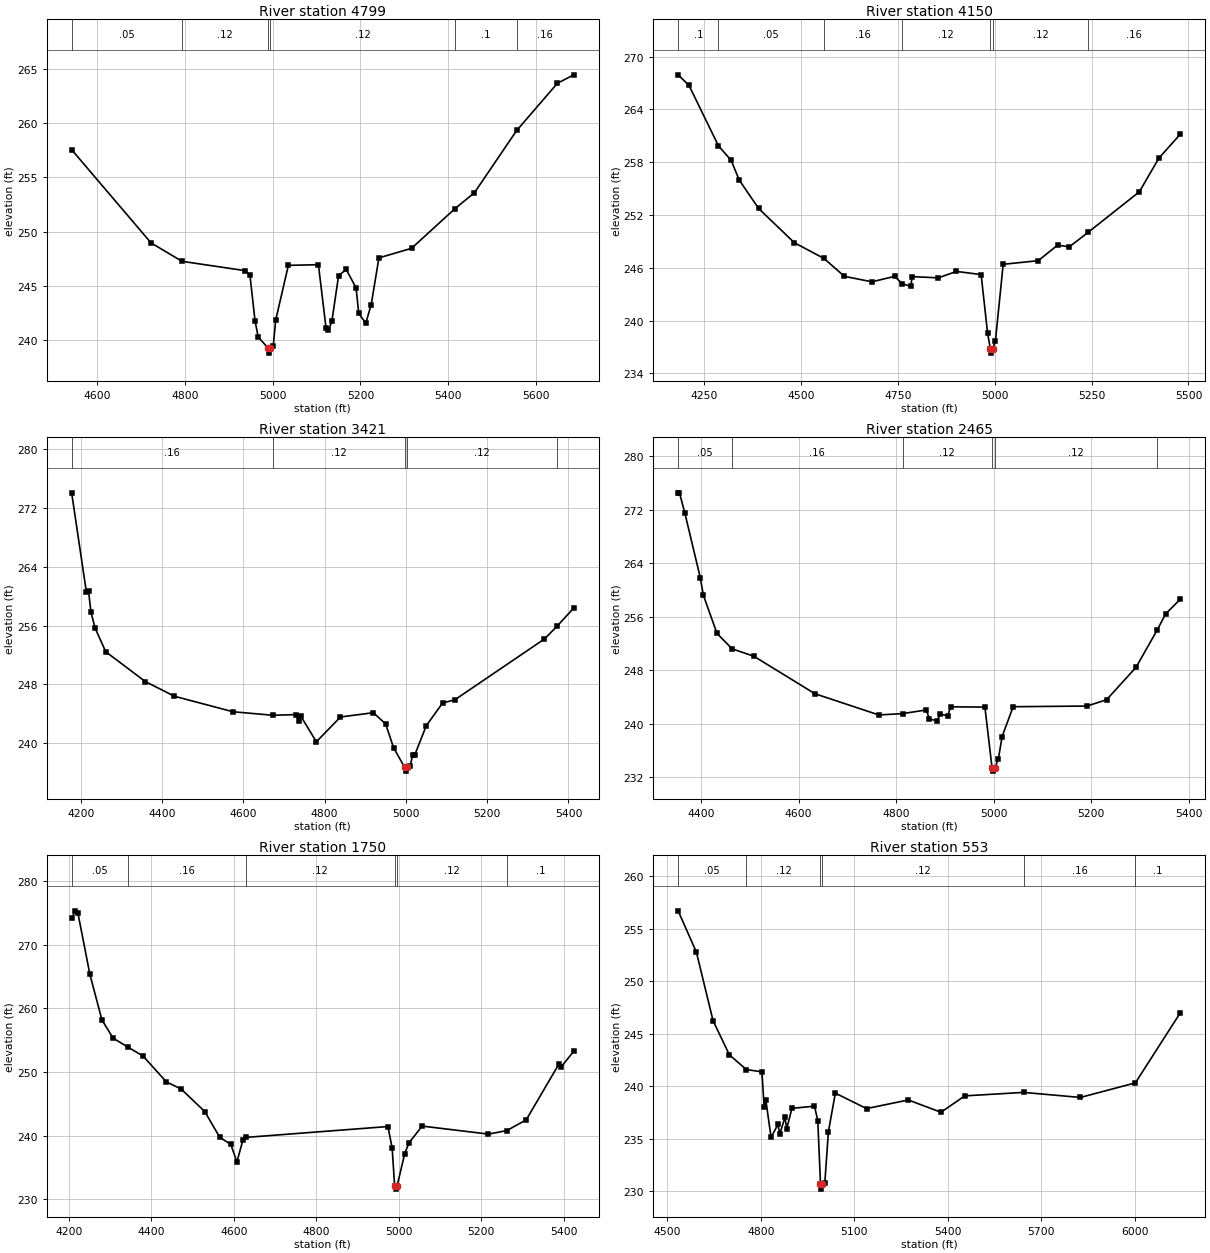
Type RM Length L Ch R = 1,4799,649,649,649
BEGIN DESCRIPTION:
PEACH CREEK SOUTH TRIB 16 7.0
END DESCRIPTION:
XS GIS Cut Line= 3
      3578442.13     10175241.65      3578042.11     10175091.64
      3577392.12     10174791.65
#Sta/Elev= 30
  4542.7  257.56  4723.4  248.97  4794.0  247.27  4937.9  246.41  4948.6  245.97
  4960.1  241.80  4967.3  240.30  4989.0  239.31  4991.7  238.81  4995.0  239.31
  5001.6  239.47  5007.1  241.85  5036.0  246.90  5104.4  246.96  5121.8  241.10
  5127.3  240.90  5135.1  241.76  5150.3  245.96  5167.7  246.52  5190.2  244.82
  5196.2  242.47  5212.2  241.57  5224.6  243.29  5242.1  247.59  5316.4  248.47
  5414.2  252.09  5459.6  253.60  5555.7  259.33  5648.6  263.69  5685.8  264.46
#Mann=6,-1,0
  4542.7    0.05       0  4794.0    0.12       0  4989.0    0.07       0
  4995.0    0.12       0  5414.2     0.1       0  5555.7    0.16       0
Bank Sta=4989,4995
Exp/Cntr=0.3,0.1

Type RM Length L Ch R = 1,4150,729,729,729
BEGIN DESCRIPTION:
PEACH CREEK SOUTH TRIB 16 6.0
END DESCRIPTION:
XS GIS Cut Line= 3
      3578642.09     10175041.63      3578154.22     10174682.43
      3577466.89     10174619.95
#Sta/Elev= 30
  4182.9  267.92  4211.1  266.71  4286.9  259.86  4319.5  258.22  4340.6  255.97
  4390.7  252.74  4482.6  248.86  4559.4  247.06  4612.1  245.03  4683.1  244.41
  4741.7  245.03  4761.1  244.20  4783.4  243.89  4786.9  245.00  4854.4  244.86
  4901.3  245.59  4964.9  245.23  4981.6  238.55  4988.7  236.81  4991.4  236.31
  4994.7  236.81  5001.7  237.68  5021.8  246.40  5112.2  246.81  5162.4  248.58
  5192.5  248.38  5241.6  250.05  5373.3  254.64  5423.5  258.45  5478.9  261.18
#Mann=7,-1,0
  4182.9     0.1       0  4286.9    0.05       0  4559.4    0.16       0
  4761.1    0.12       0  4988.7    0.07       0  4994.7    0.12       0
  5241.6    0.16       0
Bank Sta=4988.7,4994.7
Exp/Cntr=0.3,0.1

Type RM Length L Ch R = 1,3421,956,956,956
BEGIN DESCRIPTION:
PEACH CREEK SOUTH TRIB 16 5.0
END DESCRIPTION:
XS GIS Cut Line= 3
      3578758.44     10174395.98      3578189.65     10174261.28
      3577539.63     10174224.10
#Sta/Elev= 30
  4177.6  274.08  4214.0  260.52  4219.1  260.76  4225.2  257.80  4235.5  255.65
  4261.4  252.46  4358.8  248.40  4430.4  246.40  4574.6  244.29  4673.0  243.81
  4728.8  243.90  4736.4  243.09  4741.5  243.68  4779.7  240.20  4839.0  243.58
  4919.9  244.16  4950.0  242.64  4970.0  239.36  4997.1  236.71  4999.8  236.21
  5003.1  236.71  5010.1  236.87  5016.7  238.39  5021.7  238.40  5050.1  242.38
  5090.2  245.48  5120.2  245.91  5340.6  254.18  5371.4  255.90  5413.2  258.42
#Mann=5,-1,0
  4177.6    0.16       0  4673.0    0.12       0  4997.1    0.07       0
  5003.1    0.12       0  5371.4    0.16       0
Bank Sta=4997.1,5003.1
Exp/Cntr=0.3,0.1

Type RM Length L Ch R = 1,2465,715,715,715
BEGIN DESCRIPTION:
PEACH CREEK SOUTH TRIB 16 3.0
END DESCRIPTION:
XS GIS Cut Line= 3
      3578792.07     10174191.62      3578242.11     10173891.64
      3577842.08     10173841.64
#Sta/Elev= 30
  4353.1  274.51  4355.9  274.51  4366.8  271.52  4398.6  261.81  4404.8  259.21
  4432.8  253.49  4463.7  251.19  4508.3  250.08  4633.6  244.47  4764.6  241.30
  4813.3  241.50  4862.3  242.05  4868.0  240.70  4884.2  240.41  4889.9  241.38
  4906.0  241.20  4911.7  242.52  4982.1  242.47  4996.7  233.40  4999.5  232.90
  5002.7  233.40  5009.8  234.77  5017.3  238.06  5040.0  242.53  5191.2  242.63
  5231.5  243.57  5292.0  248.43  5335.8  254.06  5352.4  256.39  5382.7  258.61
#Mann=6,-1,0
  4353.1    0.05       0  4463.7    0.16       0  4813.3    0.12       0
  4996.7    0.07       0  5002.7    0.12       0  5335.8    0.16       0
Bank Sta=4996.7,5002.7
Exp/Cntr=0.3,0.1

Type RM Length L Ch R = 1,1750,1197,1197,1197
BEGIN DESCRIPTION:
PEACH CREEK SOUTH TRIB 16 2.0
END DESCRIPTION:
XS GIS Cut Line= 3
      3578951.09     10173974.10      3578440.68     10173593.89
      3577868.45     10173490.83
#Sta/Elev= 30
  4206.7  274.11  4215.4  275.31  4221.7  275.02  4250.9  265.34  4280.1  258.18
  4307.2  255.32  4342.2  253.95  4380.0  252.50  4436.5  248.44  4471.9  247.35
  4529.6  243.79  4565.8  239.75  4592.8  238.63  4607.4  235.87  4622.0  239.30
  4628.7  239.73  4973.8  241.44  4984.0  238.04  4990.0  232.11  4992.7  231.61
  4996.0  232.11  5014.4  237.18  5024.6  238.86  5056.7  241.51  5217.6  240.25
  5262.0  240.80  5309.1  242.49  5388.6  251.27  5393.6  250.78  5424.6  253.28
#Mann=6,-1,0
  4206.7    0.05       0  4342.2    0.16       0  4628.7    0.12       0
  4990.0    0.07       0  4996.0    0.12       0  5262.0     0.1       0
Bank Sta=4990,4996
Exp/Cntr=0.3,0.1

Type RM Length L Ch R = 1,553,0,0,0
BEGIN DESCRIPTION:
PEACH CREEK SOUTH TRIB 16 1.0
END DESCRIPTION:
XS GIS Cut Line= 3
      3579342.12     10173441.65      3578591.72     10173062.64
      3577907.11     10173416.18
#Sta/Elev= 30
  4534.6  256.71  4593.2  252.78  4646.7  246.25  4699.0  243.00  4753.7  241.59
  4803.5  241.38  4810.5  238.06  4816.1  238.68  4832.8  235.14  4855.1  236.38
  4860.7  235.43  4877.4  237.05  4883.0  235.96  4899.7  237.90  4972.1  238.11
  4982.7  236.73  4991.4  230.71  4994.2  230.21  4997.4  230.71  5005.2  230.78
  5016.7  235.66  5039.0  239.35  5139.3  237.88  5273.1  238.70  5377.9  237.53
  5454.3  239.09  5642.9  239.42  5825.3  238.94  6001.7  240.33  6145.8  247.00
#Mann=6,-1,0
  4534.6    0.05       0  4753.7    0.12       0  4991.4    0.07       0
  4997.4    0.12       0  5642.9    0.16       0  6001.7     0.1       0
Bank Sta=4991.4,4997.4
Exp/Cntr=0.3,0.1

Chan Stop Cuts=-1