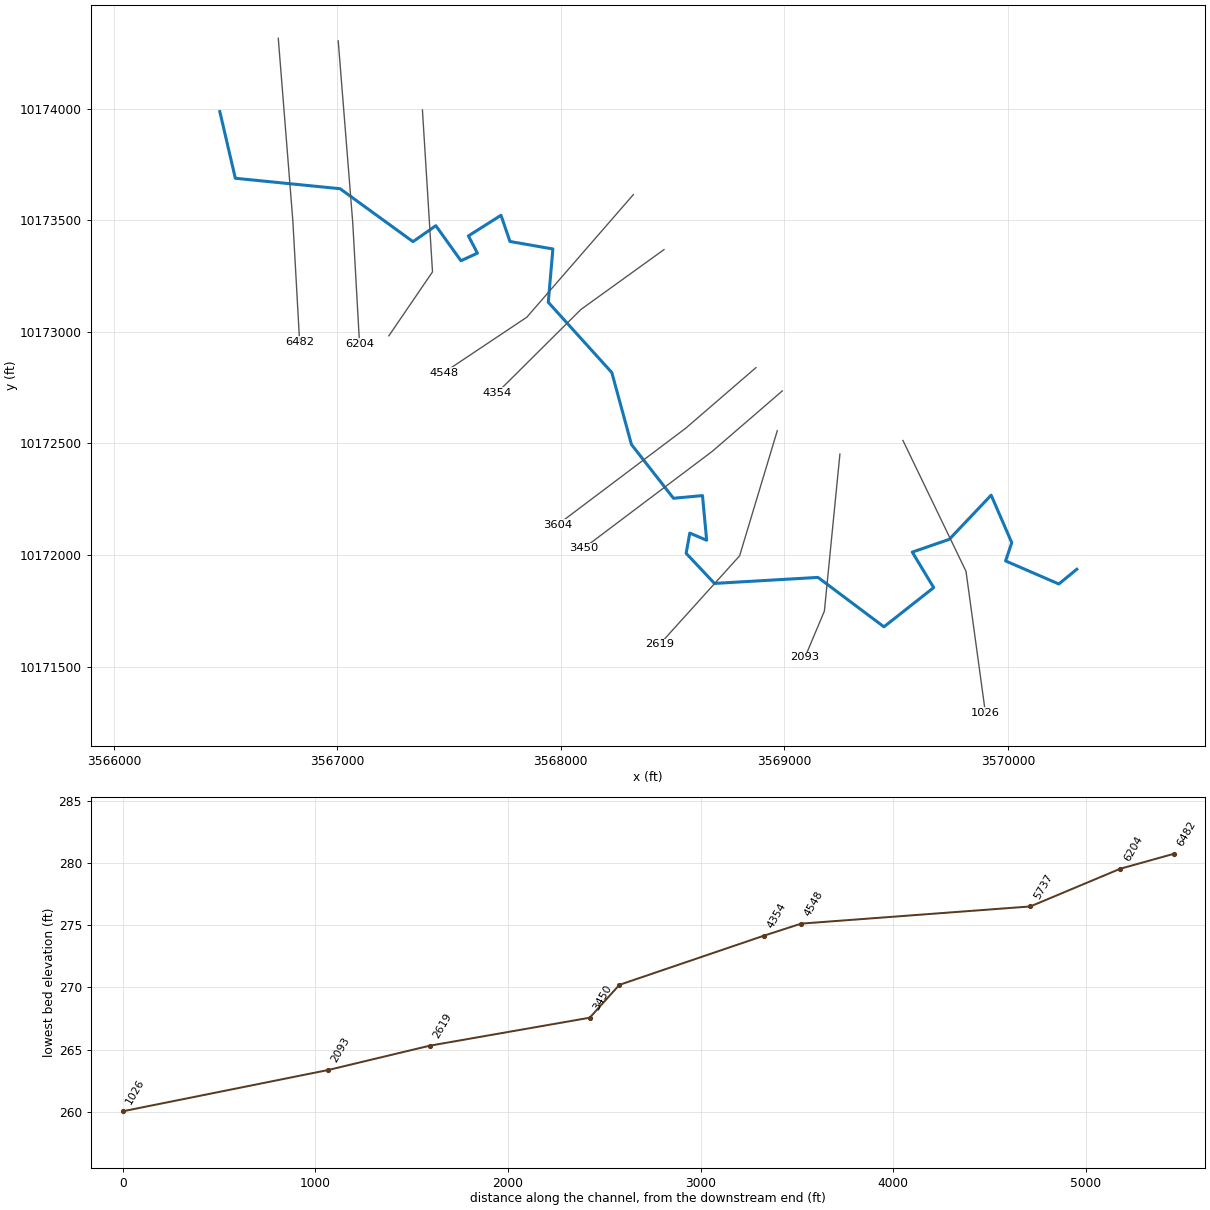
--- PEACH CREEK SOUTH TRIB 22.prj (project) ---

Proj Title=PEACH CREEK SOUTH TRIB 22 Base Level Engineering
Current Plan=p01
Default Exp/Contr=0.3,0.1
English Units
Geom File=g01
Flow File=f01
Plan File=p01
BEGIN DESCRIPTION:
PEACH CREEK SOUTH TRIB 22
END DESCRIPTION:

--- PEACH CREEK SOUTH TRIB 22.p01 (plan) ---

Plan Title=Multiple Run
Short Identifier=Multiple
Geom File=g01
Flow File=f01
Subcritical Flow
K Sum by GR= 0
Std Step Tol= 0.01
Critical Tol= 0.01
Num of Std Step Trials= 20
Max Error Tol= 0.3
Flow Tol Ratio= 0.001
Split Flow NTrial= 30
Split Flow Tol= 0.02
Split Flow Ratio= 0.02
Log Output Level= 0
Friction Slope Method= 1
Unsteady Friction Slope Method= 2
Unsteady Bridges Friction Slope Method= 1
Parabolic Critical Depth
Global Vel Dist=  1 , 1 , 1
Global Log Level= 0
CheckData=True
Encroach Param= -1, 0, 0, 0
BEGIN DESCRIPTION:
Multiple Run
END DESCRIPTION:

--- PEACH CREEK SOUTH TRIB 22.f01 (steady flow) ---

Flow Title=Multiple
Number of Profiles=7
Profile Names=10-year,25-year,50-year,1pct_min,100-year,1pct_plu,500-year
River Rch & RM= PEACH CREEK SOUT,Reach-1,6482
     384     500     591     513     693     938     955
River Rch & RM= PEACH CREEK SOUT,Reach-1,6204
     600     804     969     855    1156    1564    1651
Boundary for River Rch & Prof#=PEACH CREEK SOUT,Reach-1,1
Up Type=0
Dn Type=3
Dn Slope=0.005
Boundary for River Rch & Prof#=PEACH CREEK SOUT,Reach-1,2
Up Type=0
Dn Type=3
Dn Slope=0.005
Boundary for River Rch & Prof#=PEACH CREEK SOUT,Reach-1,3
Up Type=0
Dn Type=3
Dn Slope=0.005
Boundary for River Rch & Prof#=PEACH CREEK SOUT,Reach-1,4
Up Type=0
Dn Type=3
Dn Slope=0.005
Boundary for River Rch & Prof#=PEACH CREEK SOUT,Reach-1,5
Up Type=0
Dn Type=3
Dn Slope=0.005
Boundary for River Rch & Prof#=PEACH CREEK SOUT,Reach-1,6
Up Type=0
Dn Type=3
Dn Slope=0.005
Boundary for River Rch & Prof#=PEACH CREEK SOUT,Reach-1,7
Up Type=0
Dn Type=3
Dn Slope=0.005

--- PEACH CREEK SOUTH TRIB 22.g01 (geometry) ---

Geom Title=Existing Conditions

River Reach=PEACH CREEK SOUT,Reach-1
Reach XY= 30
      3566474.18     10173986.27      3566543.63     10173687.66
      3567012.38     10173640.78      3567338.57     10173403.72
      3567440.65     10173475.25      3567553.15     10173318.31
      3567626.76     10173352.33      3567586.48     10173429.42
      3567732.32     10173521.78      3567772.43     10173404.53
      3567964.49     10173370.89      3567943.87     10173132.17
      3568228.16     10172817.50      3568316.05     10172495.24
      3568504.10     10172254.53      3568633.79     10172266.51
      3568652.54     10172066.51      3568577.02     10172098.80
      3568560.75     10172008.06      3568687.61     10171873.22
      3569150.70     10171900.13      3569445.82     10171678.93
      3569668.39     10171854.50      3569572.50     10172013.37
      3569738.30     10172070.69      3569925.46     10172268.42
      3570017.79     10172055.45      3569990.00     10171973.96
      3570228.28     10171870.66      3570308.58     10171936.52

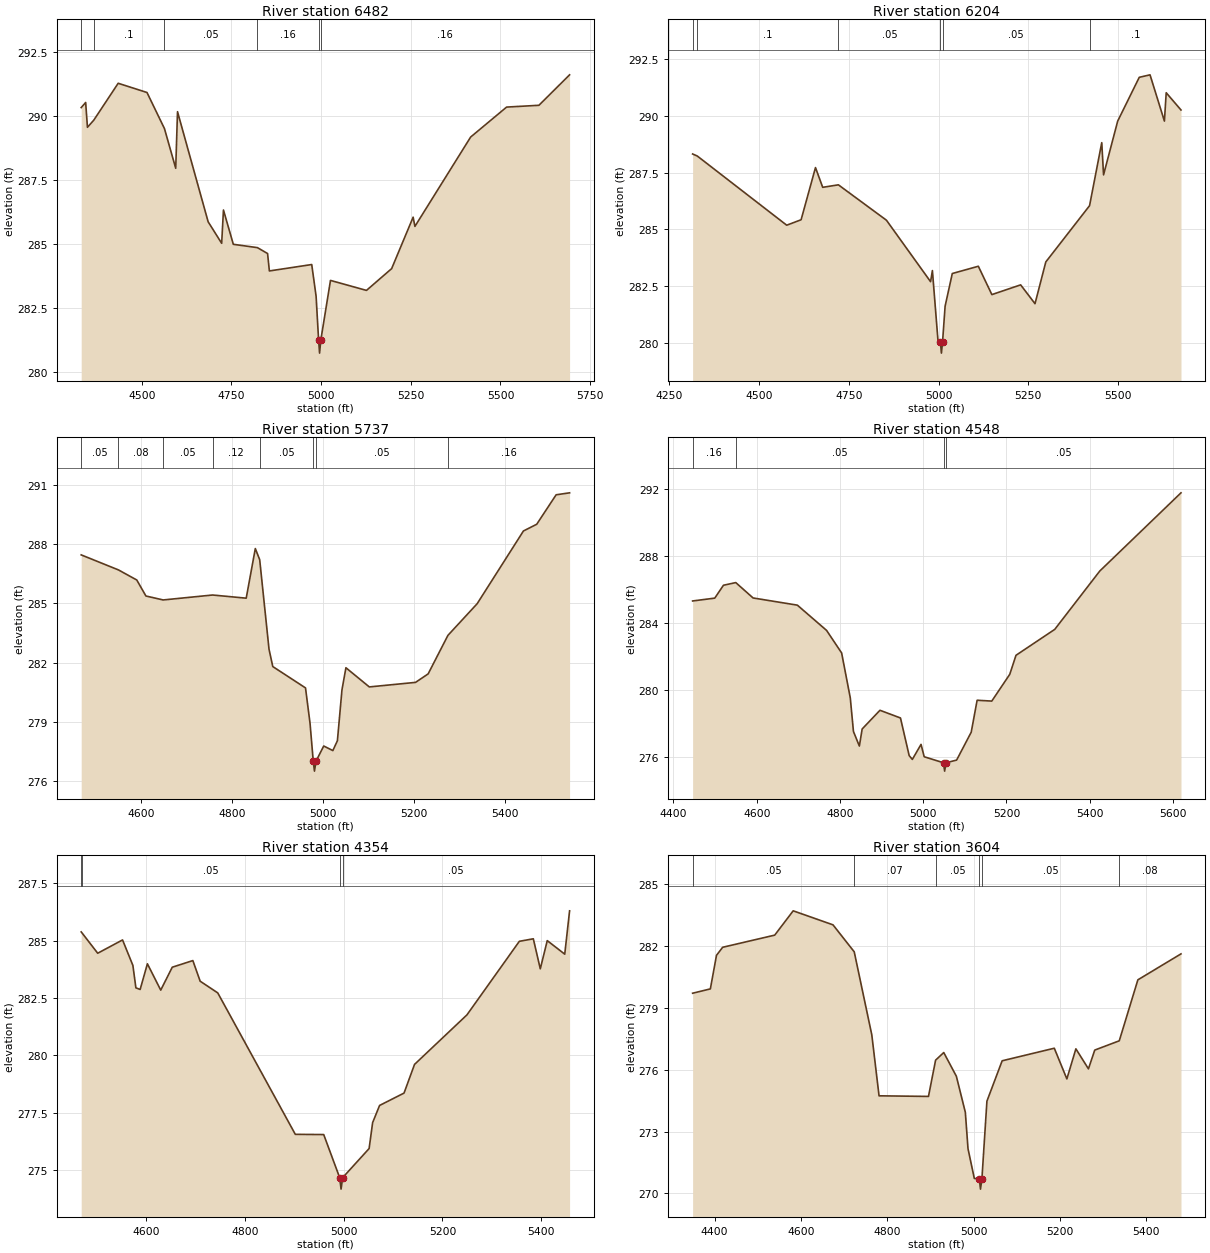
Type RM Length L Ch R = 1,6482,278,278,278
BEGIN DESCRIPTION:
PEACH CREEK SOUTH TRIB 22 10.1
END DESCRIPTION:
XS GIS Cut Line= 3
      3566735.76     10174314.43      3566800.86     10173498.49
      3566831.23     10172956.28
#Sta/Elev= 30
  4331.1  290.33  4343.5  290.53  4348.5  289.56  4366.2  289.84  4434.2  291.28
  4514.5  290.92  4563.2  289.51  4594.6  287.96  4599.6  290.17  4685.0  285.87
  4722.7  285.03  4727.7  286.33  4755.2  284.99  4822.5  284.86  4850.7  284.63
  4855.7  283.95  4973.8  284.20  4986.0  282.96  4993.0  281.24  4995.7  280.74
  4999.0  281.24  5026.1  283.58  5126.4  283.19  5196.6  284.04  5256.5  286.05
  5261.5  285.69  5416.9  289.18  5517.1  290.35  5607.2  290.42  5692.7  291.61
#Mann=6,-1,0
  4331.1    0.05       0  4366.2     0.1       0  4563.2    0.05       0
  4822.5    0.16       0  4993.0    0.07       0  4999.0    0.16       0
Bank Sta=4993,4999
Exp/Cntr=0.3,0.1

Type RM Length L Ch R = 1,6204,467,467,467
BEGIN DESCRIPTION:
PEACH CREEK SOUTH TRIB 22 10.0
END DESCRIPTION:
XS GIS Cut Line= 3
      3567003.99     10174302.97      3567069.09     10173486.99
      3567099.41     10172945.51
#Sta/Elev= 30
  4314.6  288.32  4327.6  288.23  4576.8  285.18  4616.9  285.42  4657.0  287.72
  4677.1  286.85  4720.8  286.96  4854.7  285.40  4977.7  282.69  4982.8  283.18
  4998.1  280.14  5005.1  280.04  5007.9  279.54  5011.1  280.04  5018.2  281.61
  5038.2  283.05  5110.8  283.37  5148.5  282.12  5228.7  282.55  5268.7  281.72
  5298.8  283.56  5420.7  286.04  5454.7  288.82  5459.7  287.40  5499.1  289.77
  5559.2  291.70  5589.2  291.81  5629.3  289.77  5634.3  291.02  5675.5  290.26
#Mann=6,-1,0
  4314.6    0.05       0  4327.6     0.1       0  4720.8    0.05       0
  5005.1    0.04       0  5011.1    0.05       0  5420.7     0.1       0
Bank Sta=5005.1,5011.1
Exp/Cntr=0.3,0.1

Type RM Length L Ch R = 1,5737,1189,1189,1189
BEGIN DESCRIPTION:
PEACH CREEK SOUTH TRIB 22 9.0
END DESCRIPTION:
XS GIS Cut Line= 3
      3567380.78     10173993.55      3567425.86     10173268.46
      3567230.55     10172982.00
#Sta/Elev= 30
  4468.5  287.45  4550.3  286.69  4590.6  286.18  4610.7  285.37  4648.6  285.17
  4757.2  285.42  4831.1  285.26  4851.1  287.77  4860.7  287.21  4881.2  282.68
  4889.5  281.80  4961.4  280.72  4971.4  278.92  4978.4  277.01  4981.1  276.51
  4984.4  277.01  5001.4  277.78  5021.5  277.55  5031.5  278.05  5041.5  280.62
  5050.2  281.74  5101.6  280.77  5203.2  281.00  5230.9  281.43  5274.4  283.38
  5338.6  284.98  5440.3  288.66  5469.5  289.00  5512.1  290.49  5541.7  290.59
#Mann=8,-1,0
  4468.5    0.05       0  4550.3    0.08       0  4648.6    0.05       0
  4757.2    0.12       0  4860.7    0.05       0  4978.4    0.03       0
  4984.4    0.05       0  5274.4    0.16       0
Bank Sta=4978.4,4984.4
Exp/Cntr=0.3,0.1

Type RM Length L Ch R = 1,4548,194,194,194
BEGIN DESCRIPTION:
PEACH CREEK SOUTH TRIB 22 8.0
END DESCRIPTION:
XS GIS Cut Line= 3
      3568324.32     10173614.17      3567847.74     10173065.33
      3567476.27     10172817.20
#Sta/Elev= 30
  4446.0  285.31  4499.2  285.48  4520.1  286.25  4549.7  286.41  4591.3  285.49
  4697.7  285.06  4767.9  283.55  4804.1  282.20  4824.9  279.51  4832.5  277.50
  4846.7  276.63  4853.4  277.65  4896.2  278.77  4945.5  278.31  4966.4  276.06
  4974.0  275.83  4994.9  276.73  5002.5  275.99  5048.9  275.63  5051.6  275.13
  5054.9  275.63  5080.4  275.79  5115.5  277.46  5129.7  279.37  5164.9  279.32
  5208.1  280.92  5223.1  282.06  5316.2  283.61  5424.4  287.10  5619.6  291.78
#Mann=4,-1,0
  4446.0    0.16       0  4549.7    0.05       0  5048.9    0.03       0
  5054.9    0.05       0
Bank Sta=5048.9,5054.9
Exp/Cntr=0.3,0.1

Type RM Length L Ch R = 1,4354,750,750,750
BEGIN DESCRIPTION:
PEACH CREEK SOUTH TRIB 22 7.0
END DESCRIPTION:
XS GIS Cut Line= 3
      3568461.57     10173368.05      3568089.93     10173100.06
      3567713.90     10172725.98
#Sta/Elev= 30
  4468.9  285.38  4470.4  285.34  4502.3  284.45  4552.6  285.03  4573.5  283.92
  4579.6  282.94  4588.2  282.87  4602.9  283.99  4629.9  282.84  4653.2  283.84
  4694.9  284.13  4709.7  283.23  4745.3  282.72  4902.3  276.55  4959.8  276.54
  4992.1  274.66  4994.9  274.16  4998.1  274.66  5051.7  275.93  5058.8  277.06
  5072.9  277.81  5122.4  278.35  5143.6  279.60  5249.7  281.76  5355.8  284.97
  5384.1  285.08  5398.2  283.77  5412.3  285.00  5447.7  284.41  5457.5  286.30
#Mann=4,-1,0
  4468.9    0.16       0  4470.4    0.05       0  4992.1    0.03       0
  4998.1    0.05       0
Bank Sta=4992.1,4998.1
Exp/Cntr=0.3,0.1

Type RM Length L Ch R = 1,3604,154,154,154
BEGIN DESCRIPTION:
PEACH CREEK SOUTH TRIB 22 6.0
END DESCRIPTION:
XS GIS Cut Line= 3
      3568872.91     10172839.42      3568558.76     10172568.16
      3567986.70     10172137.01
#Sta/Elev= 30
  4349.0  279.72  4390.1  279.93  4404.3  281.56  4418.6  281.95  4539.2  282.54
  4582.0  283.72  4674.2  283.04  4723.4  281.73  4764.1  277.70  4780.9  274.74
  4895.4  274.71  4911.9  276.47  4930.8  276.84  4960.0  275.69  4980.8  273.94
  4987.0  272.17  5001.6  270.73  5013.2  270.71  5015.9  270.21  5019.2  270.71
  5030.8  274.48  5066.1  276.44  5186.9  277.05  5216.0  275.56  5236.9  277.02
  5266.0  276.05  5280.6  276.96  5337.4  277.41  5380.5  280.37  5480.4  281.63
#Mann=6,-1,0
  4349.0    0.05       0  4723.4    0.07       0  4911.9    0.05       0
  5013.2    0.04       0  5019.2    0.05       0  5337.4    0.08       0
Bank Sta=5013.2,5019.2
Exp/Cntr=0.3,0.1

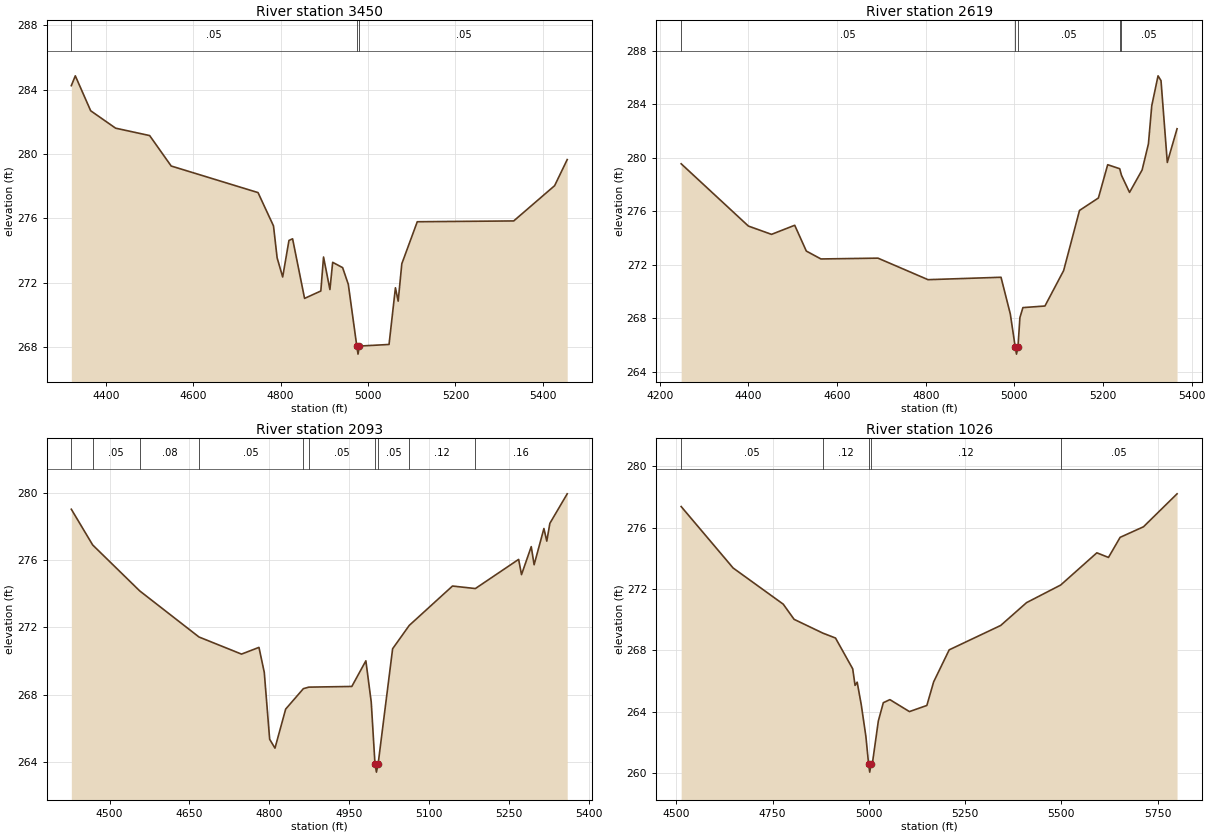
Type RM Length L Ch R = 1,3450,831,831,831
BEGIN DESCRIPTION:
PEACH CREEK SOUTH TRIB 22 6.1
END DESCRIPTION:
XS GIS Cut Line= 3
      3568990.96     10172735.26      3568676.82     10172463.99
      3568102.12     10172030.85
#Sta/Elev= 30
  4321.2  284.24  4330.3  284.85  4365.5  282.68  4422.5  281.60  4500.4  281.14
  4549.7  279.25  4748.4  277.60  4783.8  275.53  4792.1  273.55  4804.8  272.36
  4819.2  274.63  4827.5  274.73  4854.9  271.03  4892.1  271.49  4898.3  273.60
  4912.9  271.58  4919.2  273.27  4942.0  272.94  4955.0  271.90  4974.4  268.07
  4977.2  267.57  4980.4  268.07  5048.2  268.17  5062.8  271.69  5069.1  270.86
  5077.4  273.18  5112.8  275.79  5333.5  275.84  5427.1  278.03  5455.9  279.65
#Mann=3,-1,0
  4321.2    0.05       0  4974.4    0.04       0  4980.4    0.05       0
Bank Sta=4974.4,4980.4
Exp/Cntr=0.3,0.1

Type RM Length L Ch R = 1,2619,526,526,526
BEGIN DESCRIPTION:
PEACH CREEK SOUTH TRIB 22 5.0
END DESCRIPTION:
XS GIS Cut Line= 3
      3568968.50     10172556.94      3568800.00     10171996.76
      3568442.38     10171600.29
#Sta/Elev= 30
  4248.2  279.56  4399.9  274.90  4452.1  274.28  4504.4  274.96  4530.6  273.03
  4563.6  272.44  4692.3  272.50  4805.2  270.89  4969.9  271.07  4990.9  268.32
  5002.1  265.82  5004.8  265.32  5008.1  265.82  5012.5  268.05  5019.3  268.80
  5069.0  268.92  5111.2  271.57  5147.0  276.07  5189.6  277.00  5210.6  279.49
  5237.7  279.19  5241.7  278.70  5259.9  277.42  5288.3  279.10  5302.5  281.05
  5310.0  283.90  5324.2  286.14  5330.9  285.78  5345.1  279.66  5367.1  282.18
#Mann=5,-1,0
  4248.2    0.05       0  5002.1    0.03       0  5008.1    0.05       0
  5237.7    0.08       0  5241.7    0.05       0
Bank Sta=5002.1,5008.1
Exp/Cntr=0.3,0.1

Type RM Length L Ch R = 1,2093,1067,1067,1067
BEGIN DESCRIPTION:
PEACH CREEK SOUTH TRIB 22 3.0
END DESCRIPTION:
XS GIS Cut Line= 3
      3569248.78     10172452.50      3569179.34     10171749.36
      3569092.09     10171541.60
#Sta/Elev= 30
  4428.0  279.05  4468.1  276.92  4556.5  274.18  4667.9  271.43  4747.8  270.41
  4780.6  270.81  4790.6  269.32  4800.7  265.33  4810.7  264.80  4830.8  267.13
  4864.1  268.35  4874.5  268.44  4955.1  268.48  4981.5  270.01  4991.6  267.55
  4998.6  263.87  5001.4  263.37  5004.6  263.87  5031.8  270.73  5063.0  272.12
  5144.3  274.47  5187.3  274.32  5268.6  276.06  5274.0  275.15  5292.3  276.82
  5297.7  275.74  5316.1  277.90  5321.5  277.15  5327.3  278.21  5359.9  279.97
#Mann=10,-1,0
  4428.0    0.08       0  4468.1    0.05       0  4556.5    0.08       0
  4667.9    0.05       0  4864.1    0.12       0  4874.5    0.05       0
  4998.6    0.04       0  5004.6    0.05       0  5063.0    0.12       0
  5187.3    0.16       0
Bank Sta=4998.6,5004.6
Exp/Cntr=0.3,0.1

Type RM Length L Ch R = 1,1026,0,0,0
BEGIN DESCRIPTION:
PEACH CREEK SOUTH TRIB 22 1.0
END DESCRIPTION:
XS GIS Cut Line= 3
      3569530.90     10172513.24      3569813.02     10171927.31
      3569899.62     10171295.13
#Sta/Elev= 30
  4512.3  277.38  4647.3  273.37  4777.5  271.01  4805.7  270.02  4880.5  269.12
  4913.3  268.80  4958.0  266.79  4964.1  265.71  4969.6  265.92  4980.2  264.45
  4992.2  262.39  4999.4  260.55  5002.2  260.05  5005.4  260.55  5009.3  260.65
  5024.6  263.39  5037.5  264.58  5054.6  264.78  5105.4  264.00  5150.6  264.40
  5168.3  265.94  5208.7  268.03  5342.5  269.62  5409.7  271.11  5498.4  272.26
  5592.3  274.36  5622.5  274.06  5652.8  275.37  5713.5  276.06  5800.7  278.21
#Mann=5,-1,0
  4512.3    0.05       0  4880.5    0.12       0  4999.4    0.07       0
  5005.4    0.12       0  5498.4    0.05       0
Bank Sta=4999.4,5005.4
Exp/Cntr=0.3,0.1

Chan Stop Cuts=-1