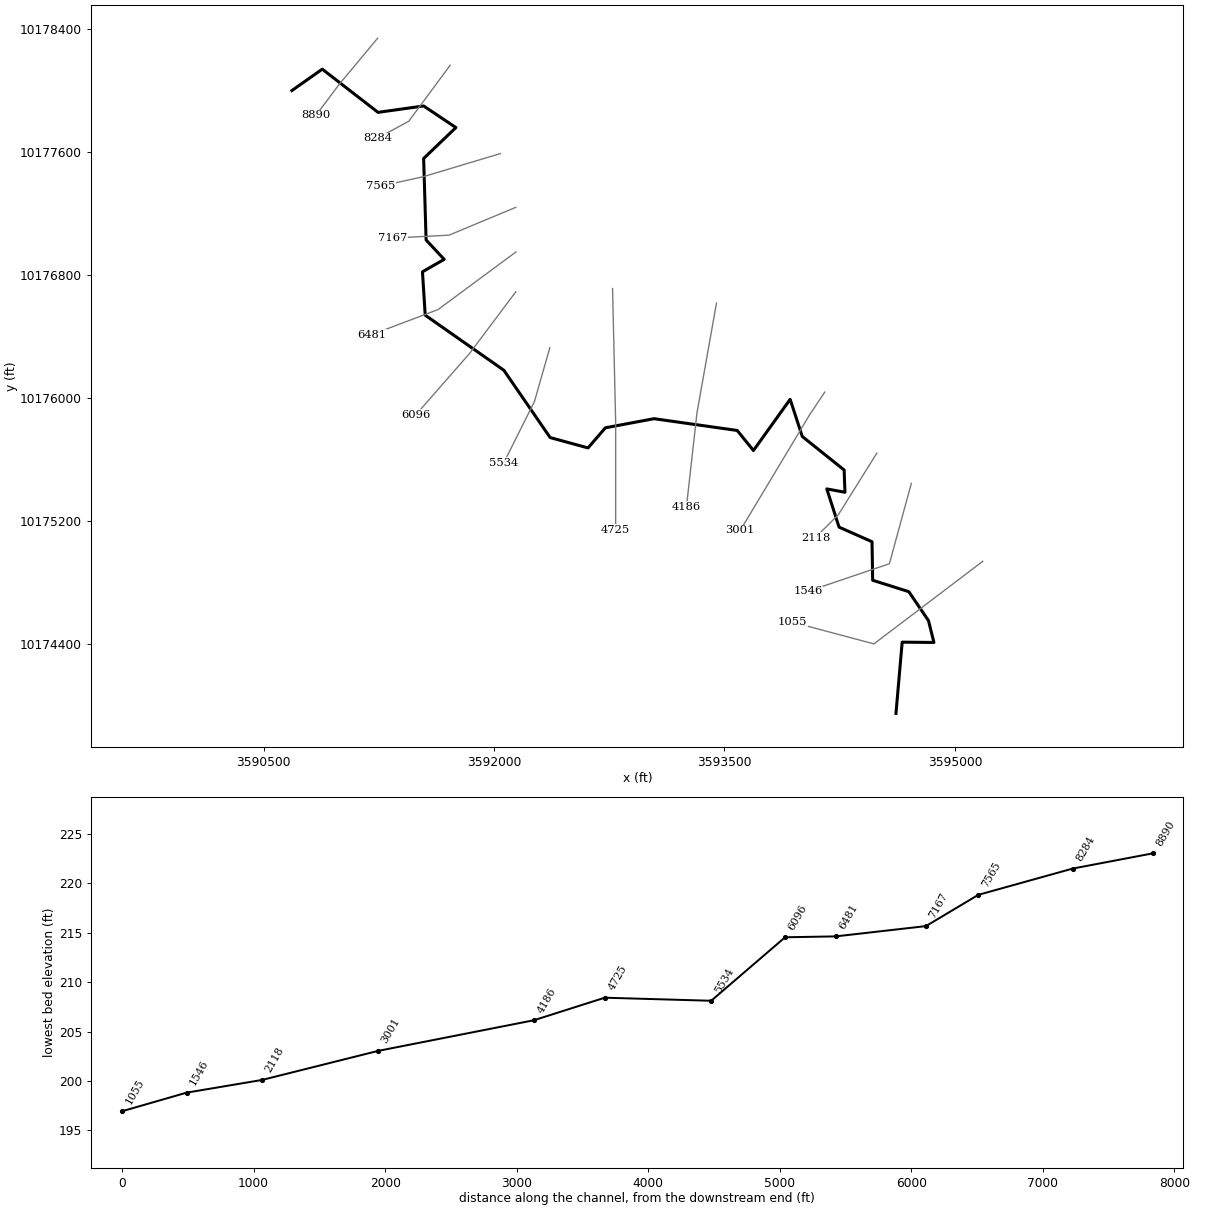
--- PEACH CREEK SOUTH TRIB 6.prj (project) ---

Proj Title=PEACH CREEK SOUTH TRIB 6 Base Level Engineering
Current Plan=p01
Default Exp/Contr=0.3,0.1
English Units
Geom File=g01
Flow File=f01
Plan File=p01
BEGIN DESCRIPTION:
PEACH CREEK SOUTH TRIB 6
END DESCRIPTION:

--- PEACH CREEK SOUTH TRIB 6.p01 (plan) ---

Plan Title=Multiple Run
Short Identifier=Multiple
Geom File=g01
Flow File=f01
Subcritical Flow
K Sum by GR= 0
Std Step Tol= 0.01
Critical Tol= 0.01
Num of Std Step Trials= 20
Max Error Tol= 0.3
Flow Tol Ratio= 0.001
Split Flow NTrial= 30
Split Flow Tol= 0.02
Split Flow Ratio= 0.02
Log Output Level= 0
Friction Slope Method= 1
Unsteady Friction Slope Method= 2
Unsteady Bridges Friction Slope Method= 1
Parabolic Critical Depth
Global Vel Dist=  1 , 1 , 1
Global Log Level= 0
CheckData=True
Encroach Param= -1, 0, 0, 0
BEGIN DESCRIPTION:
Multiple Run
END DESCRIPTION:

--- PEACH CREEK SOUTH TRIB 6.f01 (steady flow) ---

Flow Title=Multiple
Number of Profiles=7
Profile Names=10-year,25-year,50-year,1pct_min,100-year,1pct_plu,500-year
River Rch & RM= PEACH CREEK SOUT,Reach-1,8890
     540     718     860     754    1020    1380    1439
Boundary for River Rch & Prof#=PEACH CREEK SOUT,Reach-1,1
Up Type=0
Dn Type=3
Dn Slope=0.005
Boundary for River Rch & Prof#=PEACH CREEK SOUT,Reach-1,2
Up Type=0
Dn Type=3
Dn Slope=0.005
Boundary for River Rch & Prof#=PEACH CREEK SOUT,Reach-1,3
Up Type=0
Dn Type=3
Dn Slope=0.005
Boundary for River Rch & Prof#=PEACH CREEK SOUT,Reach-1,4
Up Type=0
Dn Type=3
Dn Slope=0.005
Boundary for River Rch & Prof#=PEACH CREEK SOUT,Reach-1,5
Up Type=0
Dn Type=3
Dn Slope=0.005
Boundary for River Rch & Prof#=PEACH CREEK SOUT,Reach-1,6
Up Type=0
Dn Type=3
Dn Slope=0.005
Boundary for River Rch & Prof#=PEACH CREEK SOUT,Reach-1,7
Up Type=0
Dn Type=3
Dn Slope=0.005

--- PEACH CREEK SOUTH TRIB 6.g01 (geometry) ---

Geom Title=Existing Conditions

River Reach=PEACH CREEK SOUT,Reach-1
Reach XY= 30
      3590684.49     10178001.65      3590882.45     10178141.02
      3591245.30     10177859.77      3591542.17     10177901.44
      3591752.24     10177760.81      3591542.17     10177559.42
      3591558.24     10177029.04      3591675.89     10176903.01
      3591534.55     10176821.82      3591552.48     10176539.52
      3592064.28     10176181.18      3592365.67     10175742.99
      3592612.20     10175675.63      3592725.30     10175806.56
      3593041.71     10175865.83      3593583.38     10175789.17
      3593688.93     10175658.61      3593927.82     10175991.95
      3594006.85     10175749.98      3594279.32     10175531.84
      3594284.49     10175386.96      3594166.48     10175408.87
      3594246.23     10175160.00      3594460.81     10175064.86
      3594464.98     10174814.17      3594700.39     10174739.86
      3594828.27     10174551.25      3594863.80     10174409.22
      3594657.09     10174411.28      3594616.63     10173947.69

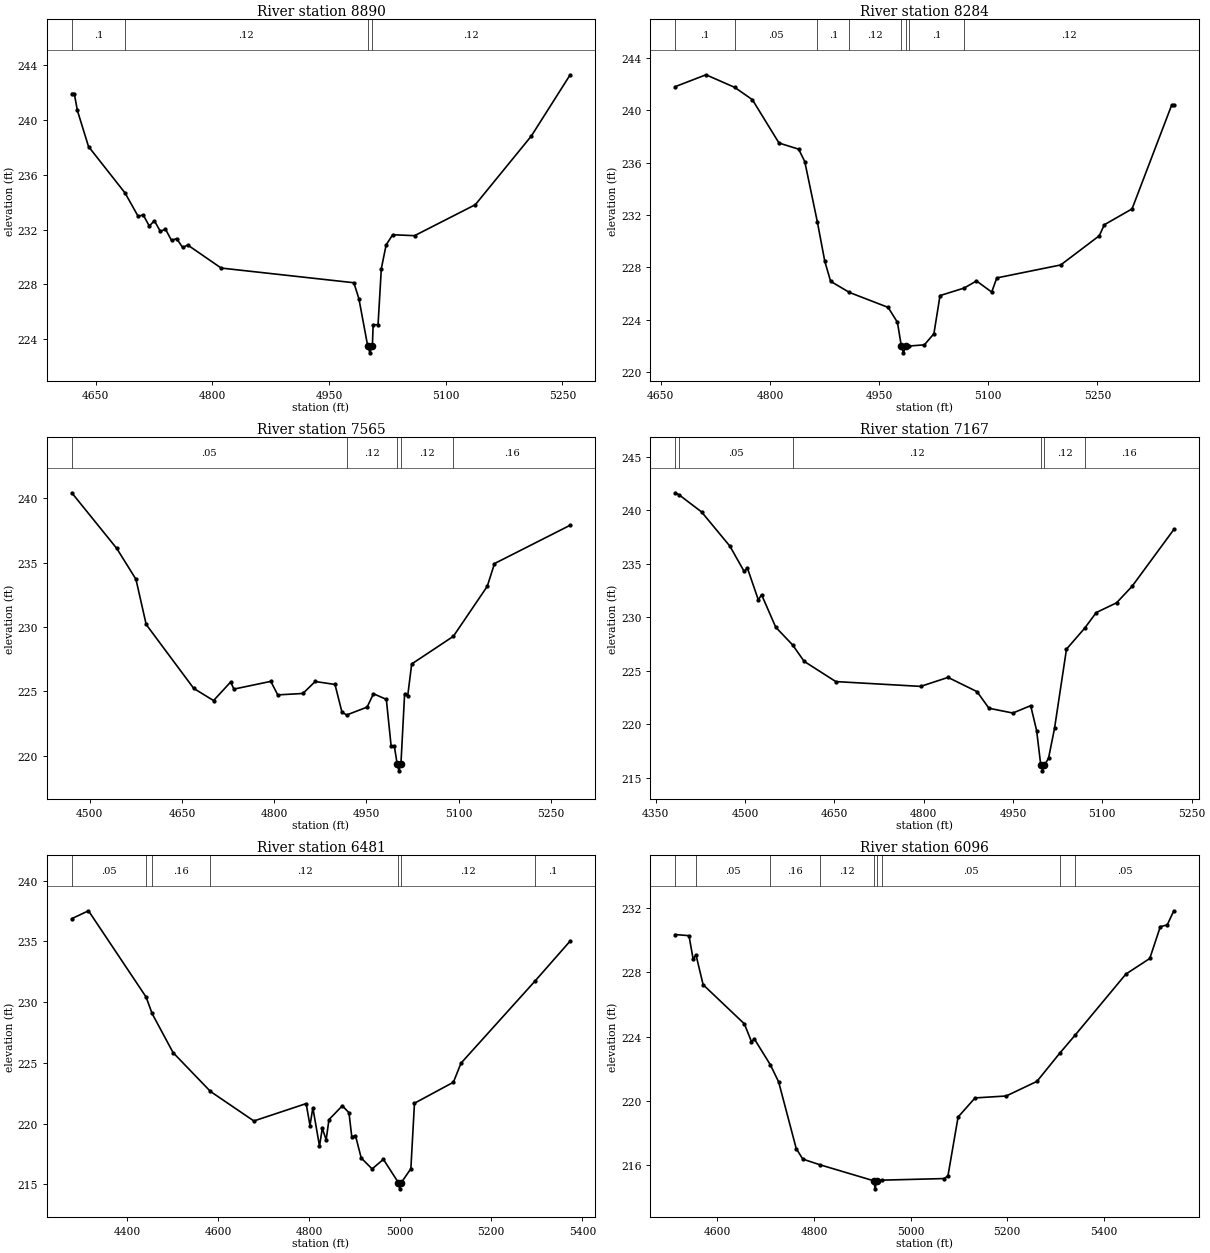
Type RM Length L Ch R = 1,8890,606,606,606
BEGIN DESCRIPTION:
PEACH CREEK SOUTH TRIB 6 18.0
END DESCRIPTION:
XS GIS Cut Line= 3
      3591242.10     10178341.64      3590992.11     10178041.64
      3590842.11     10177841.65
#Sta/Elev= 30
  4619.4  241.91  4622.6  241.91  4626.6  240.68  4640.9  238.05  4687.9  234.66
  4704.7  232.96  4711.2  233.07  4719.0  232.25  4725.5  232.64  4733.3  231.86
  4739.8  232.03  4747.6  231.20  4754.1  231.34  4761.9  230.69  4768.4  230.87
  4811.4  229.19  4981.9  228.12  4988.4  226.95  4999.7  223.51  5002.5  223.01
  5005.7  223.51  5006.7  225.06  5013.0  225.06  5017.2  229.15  5023.4  230.88
  5031.8  231.62  5059.9  231.55  5138.0  233.81  5209.9  238.81  5259.9  243.28
#Mann=4,-1,0
  4619.4     0.1       0  4687.9    0.12       0  4999.7    0.07       0
  5005.7    0.12       0
Bank Sta=4999.7,5005.7
Exp/Cntr=0.3,0.1

Type RM Length L Ch R = 1,8284,719,719,719
BEGIN DESCRIPTION:
PEACH CREEK SOUTH TRIB 6 17.0
END DESCRIPTION:
XS GIS Cut Line= 3
      3591714.90     10178166.66      3591445.39     10177802.02
      3591242.15     10177691.66
#Sta/Elev= 30
  4670.2  241.81  4712.2  242.71  4751.6  241.75  4775.9  240.81  4812.5  237.50
  4839.5  237.03  4847.9  236.08  4865.1  231.50  4875.4  228.47  4883.4  226.94
  4909.3  226.09  4962.4  224.95  4975.2  223.81  4980.6  221.98  4983.4  221.48
  4986.6  221.98  4990.9  222.00  5012.2  222.09  5025.3  222.94  5033.7  225.85
  5067.0  226.43  5083.8  226.97  5104.7  226.12  5111.7  227.20  5199.5  228.19
  5252.5  230.42  5259.4  231.26  5297.5  232.47  5352.1  240.42  5354.9  240.42
#Mann=8,-1,0
  4670.2     0.1       0  4751.6    0.05       0  4865.1     0.1       0
  4909.3    0.12       0  4980.6    0.07       0  4986.6    0.12       0
  4990.9     0.1       0  5067.0    0.12       0
Bank Sta=4980.6,4986.6
Exp/Cntr=0.3,0.1

Type RM Length L Ch R = 1,7565,398,398,398
BEGIN DESCRIPTION:
PEACH CREEK SOUTH TRIB 6 15.0
END DESCRIPTION:
XS GIS Cut Line= 3
      3592042.15     10177591.65      3591542.11     10177441.64
      3591260.40     10177379.23
#Sta/Elev= 30
  4470.9  240.42  4544.0  236.10  4575.3  233.70  4591.9  230.19  4669.3  225.22
  4701.5  224.28  4729.3  225.72  4734.6  225.17  4794.6  225.77  4805.9  224.72
  4846.8  224.83  4866.8  225.76  4899.0  225.53  4910.3  223.38  4918.0  223.16
  4951.2  223.77  4961.6  224.81  4982.5  224.37  4990.3  220.74  4995.5  220.74
  5000.2  219.32  5003.0  218.82  5006.2  219.32  5012.2  224.78  5017.3  224.66
  5023.7  227.12  5091.5  229.27  5146.6  233.15  5158.4  234.92  5281.5  237.90
#Mann=5,-1,0
  4470.9    0.05       0  4918.0    0.12       0  5000.2    0.07       0
  5006.2    0.12       0  5091.5    0.16       0
Bank Sta=5000.2,5006.2
Exp/Cntr=0.3,0.1

Type RM Length L Ch R = 1,7167,686,686,686
BEGIN DESCRIPTION:
PEACH CREEK SOUTH TRIB 6 14.0
END DESCRIPTION:
XS GIS Cut Line= 3
      3592142.09     10177241.64      3591707.25     10177060.45
      3591342.11     10177041.64
#Sta/Elev= 30
  4383.3  241.64  4389.9  241.43  4427.2  239.85  4474.8  236.65  4498.7  234.29
  4504.1  234.61  4522.5  231.63  4527.9  232.12  4551.7  229.08  4580.1  227.42
  4599.4  225.89  4652.5  224.00  4795.0  223.55  4841.0  224.39  4889.6  223.06
  4909.6  221.51  4949.7  221.06  4979.7  221.75  4989.7  219.41  4996.7  216.16
  4999.5  215.66  5002.7  216.16  5009.7  216.85  5019.7  219.62  5039.8  227.03
  5070.2  228.98  5089.8  230.45  5123.9  231.36  5149.9  232.90  5220.0  238.21
#Mann=6,-1,0
  4383.3     0.1       0  4389.9    0.05       0  4580.1    0.12       0
  4996.7    0.07       0  5002.7    0.12       0  5070.2    0.16       0
Bank Sta=4996.7,5002.7
Exp/Cntr=0.3,0.1

Type RM Length L Ch R = 1,6481,385,385,385
BEGIN DESCRIPTION:
PEACH CREEK SOUTH TRIB 6 13.0
END DESCRIPTION:
XS GIS Cut Line= 3
      3592142.95     10176951.13      3591635.64     10176575.94
      3591202.25     10176412.09
#Sta/Elev= 30
  4278.9  236.87  4315.6  237.52  4442.2  230.41  4455.1  229.07  4501.3  225.84
  4583.4  222.64  4678.7  220.21  4793.5  221.64  4801.9  219.83  4808.2  221.30
  4822.8  218.14  4829.0  219.60  4837.4  218.66  4843.6  220.32  4872.9  221.46
  4887.5  220.89  4893.7  218.90  4901.8  219.00  4914.4  217.16  4938.3  216.26
  4963.1  217.05  4996.2  215.12  4998.9  214.62  5002.2  215.12  5023.4  216.28
  5031.3  221.67  5116.8  223.40  5133.5  224.97  5295.7  231.72  5373.2  235.03
#Mann=7,-1,0
  4278.9    0.05       0  4442.2     0.1       0  4455.1    0.16       0
  4583.4    0.12       0  4996.2    0.07       0  5002.2    0.12       0
  5295.7     0.1       0
Bank Sta=4996.2,5002.2
Exp/Cntr=0.3,0.1

Type RM Length L Ch R = 1,6096,562,562,562
BEGIN DESCRIPTION:
PEACH CREEK SOUTH TRIB 6 12.0
END DESCRIPTION:
XS GIS Cut Line= 3
      3592142.11     10176691.65      3591842.11     10176291.64
      3591492.12     10175891.66
#Sta/Elev= 30
  4513.2  230.36  4541.3  230.29  4549.7  228.86  4555.9  229.08  4570.5  227.24
  4655.9  224.80  4670.5  223.70  4676.8  223.85  4709.7  222.25  4726.8  221.19
  4763.2  217.04  4776.8  216.38  4813.2  216.02  4923.8  215.03  4926.5  214.53
  4929.8  215.03  4939.7  215.07  5069.7  215.17  5077.3  215.35  5098.2  219.00
  5133.3  220.19  5197.8  220.31  5261.4  221.22  5308.5  222.97  5340.5  224.10
  5445.5  227.90  5494.9  228.87  5516.7  230.85  5531.0  230.96  5544.7  231.84
#Mann=9,-1,0
  4513.2     0.1       0  4555.9    0.05       0  4709.7    0.16       0
  4813.2    0.12       0  4923.8    0.03       0  4929.8    0.12       0
  4939.7    0.05       0  5308.5    0.16       0  5340.5    0.05       0
Bank Sta=4923.8,4929.8
Exp/Cntr=0.3,0.1

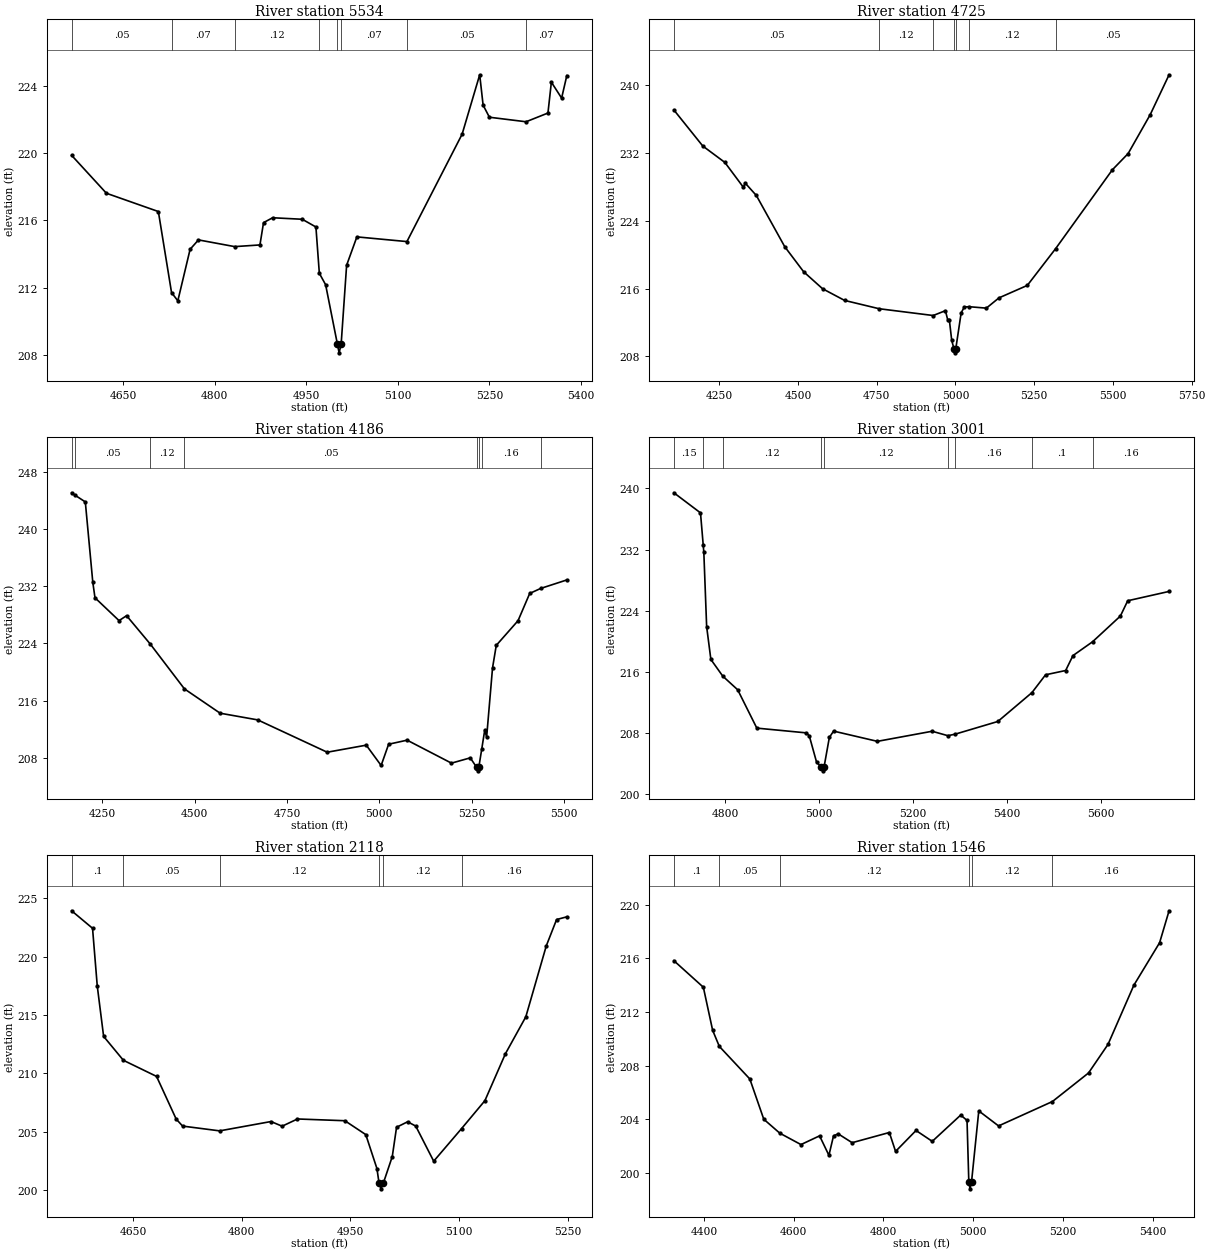
Type RM Length L Ch R = 1,5534,809,809,809
BEGIN DESCRIPTION:
PEACH CREEK SOUTH TRIB 6 11.0
END DESCRIPTION:
XS GIS Cut Line= 3
      3592363.66     10176328.24      3592263.66     10175978.22
      3592063.67     10175578.26
#Sta/Elev= 30
  4565.5  219.88  4622.5  217.62  4707.6  216.53  4729.2  211.70  4739.5  211.21
  4759.6  214.28  4773.3  214.84  4832.6  214.44  4874.0  214.54  4879.9  215.87
  4894.8  216.16  4943.3  216.07  4965.7  215.61  4971.3  212.85  4981.6  212.17
  5001.0  208.61  5003.7  208.11  5007.0  208.61  5016.0  213.33  5032.8  215.02
  5114.8  214.74  5205.2  221.14  5234.0  224.68  5239.6  222.87  5249.9  222.15
  5309.9  221.88  5345.8  222.40  5351.4  224.24  5368.2  223.29  5376.7  224.63
#Mann=8,-1,0
  4565.5    0.05       0  4729.2    0.07       0  4832.6    0.12       0
  4971.3    0.07       0  5001.0    0.07       0  5007.0    0.07       0
  5114.8    0.05       0  5309.9    0.07       0
Bank Sta=5001,5007
Exp/Cntr=0.3,0.1

Type RM Length L Ch R = 1,4725,539,539,539
BEGIN DESCRIPTION:
PEACH CREEK SOUTH TRIB 6 9.0
END DESCRIPTION:
XS GIS Cut Line= 3
      3592771.88     10176713.38      3592792.11     10175841.64
      3592792.11     10175141.62
#Sta/Elev= 30
  4106.3  237.05  4198.1  232.80  4268.1  230.87  4327.3  227.92  4332.3  228.45
  4368.1  226.97  4458.1  220.94  4518.2  217.98  4578.2  215.98  4648.2  214.60
  4757.8  213.62  4929.5  212.82  4968.3  213.39  4975.8  212.28  4980.8  212.28
  4988.3  209.89  4995.3  208.92  4998.0  208.42  5001.3  208.92  5018.3  213.14
  5028.3  213.82  5042.9  213.86  5098.3  213.69  5138.3  214.90  5228.3  216.37
  5318.5  220.72  5498.3  230.00  5548.3  231.91  5618.3  236.49  5678.3  241.20
#Mann=7,-1,0
  4106.3    0.05       0  4757.8    0.12       0  4929.5    0.05       0
  4995.3    0.03       0  5001.3    0.05       0  5042.9    0.12       0
  5318.5    0.05       0
Bank Sta=4995.3,5001.3
Exp/Cntr=0.3,0.1

Type RM Length L Ch R = 1,4186,1185,1185,1185
BEGIN DESCRIPTION:
PEACH CREEK SOUTH TRIB 6 8.0
END DESCRIPTION:
XS GIS Cut Line= 3
      3593448.34     10176618.20      3593321.50     10175904.76
      3593252.80     10175291.73
#Sta/Elev= 30
  4166.5  245.12  4176.6  244.75  4203.6  243.84  4223.9  232.57  4229.8  230.40
  4295.0  227.20  4315.4  227.89  4379.8  223.90  4472.1  217.63  4568.8  214.22
  4670.8  213.28  4858.9  208.75  4964.7  209.74  5005.0  206.89  5025.3  209.87
  5075.4  210.44  5195.5  207.22  5246.5  207.96  5263.6  206.64  5266.3  206.14
  5269.6  206.64  5277.7  209.24  5285.7  211.87  5290.8  210.86  5306.8  220.58
  5316.9  223.73  5375.9  227.19  5407.5  231.01  5437.2  231.71  5508.0  232.90
#Mann=8,-1,0
  4166.5     0.1       0  4176.6    0.05       0  4379.8    0.12       0
  4472.1    0.05       0  5263.6    0.03       0  5269.6    0.05       0
  5277.7    0.16       0  5437.2     0.1       0
Bank Sta=5263.6,5269.6
Exp/Cntr=0.3,0.1

Type RM Length L Ch R = 1,3001,883,883,883
BEGIN DESCRIPTION:
PEACH CREEK SOUTH TRIB 6 6.0
END DESCRIPTION:
XS GIS Cut Line= 3
      3594153.09     10176038.80      3594053.09     10175888.79
      3593603.10     10175138.82
#Sta/Elev= 30
  4690.1  239.43  4746.8  236.80  4752.5  232.66  4753.9  231.64  4759.9  221.91
  4768.9  217.62  4794.3  215.43  4826.0  213.65  4866.8  208.63  4972.0  208.01
  4978.5  207.63  4994.1  204.17  5004.0  203.54  5006.8  203.04  5010.0  203.54
  5021.3  207.41  5030.3  208.24  5123.6  206.90  5240.2  208.22  5273.8  207.64
  5289.3  207.84  5380.2  209.50  5452.9  213.28  5481.9  215.61  5524.7  216.17
  5540.2  218.12  5582.0  219.93  5641.3  223.30  5656.9  225.30  5745.0  226.52
#Mann=9,-1,0
  4690.1    0.15       0  4752.5    0.05       0  4794.3    0.12       0
  5004.0    0.07       0  5010.0    0.12       0  5273.8     0.1       0
  5289.3    0.16       0  5452.9     0.1       0  5582.0    0.16       0
Bank Sta=5004,5010
Exp/Cntr=0.3,0.1

Type RM Length L Ch R = 1,2118,572,572,572
BEGIN DESCRIPTION:
PEACH CREEK SOUTH TRIB 6 4.0
END DESCRIPTION:
XS GIS Cut Line= 3
      3594492.09     10175641.62      3594242.11     10175241.64
      3594092.11     10175091.65
#Sta/Elev= 30
  4565.1  223.94  4594.0  222.44  4600.5  217.50  4609.3  213.17  4636.6  211.12
  4682.4  209.74  4709.5  206.08  4718.4  205.48  4769.5  205.07  4840.4  205.87
  4855.8  205.47  4877.0  206.09  4942.4  205.94  4971.3  204.75  4986.7  201.84
  4989.6  200.60  4992.3  200.10  4995.6  200.60  5007.9  202.87  5013.8  205.38
  5029.1  205.85  5040.3  205.48  5065.1  202.47  5103.5  205.26  5135.8  207.66
  5164.1  211.68  5192.3  214.85  5220.6  220.94  5234.8  223.19  5248.9  223.42
#Mann=6,-1,0
  4565.1     0.1       0  4636.6    0.05       0  4769.5    0.12       0
  4989.6    0.07       0  4995.6    0.12       0  5103.5    0.16       0
Bank Sta=4989.6,4995.6
Exp/Cntr=0.3,0.1

Type RM Length L Ch R = 1,1546,491,491,491
BEGIN DESCRIPTION:
PEACH CREEK SOUTH TRIB 6 3.0
END DESCRIPTION:
XS GIS Cut Line= 3
      3594716.71     10175445.01      3594574.01     10174921.78
      3594042.12     10174741.65
#Sta/Elev= 30
  4333.0  215.83  4398.7  213.85  4419.4  210.64  4434.3  209.44  4502.3  207.01
  4533.4  204.01  4569.1  202.97  4616.3  202.12  4657.8  202.77  4678.6  201.32
  4688.9  202.77  4699.3  202.92  4730.4  202.26  4813.3  203.02  4827.2  201.61
  4872.8  203.17  4909.0  202.36  4972.4  204.32  4986.5  203.92  4990.5  199.32
  4993.2  198.82  4996.5  199.32  5012.7  204.63  5056.8  203.51  5176.9  205.33
  5257.4  207.46  5300.8  209.59  5358.4  214.00  5415.8  217.17  5436.9  219.55
#Mann=6,-1,0
  4333.0     0.1       0  4434.3    0.05       0  4569.1    0.12       0
  4990.5    0.07       0  4996.5    0.12       0  5176.9    0.16       0
Bank Sta=4990.5,4996.5
Exp/Cntr=0.3,0.1

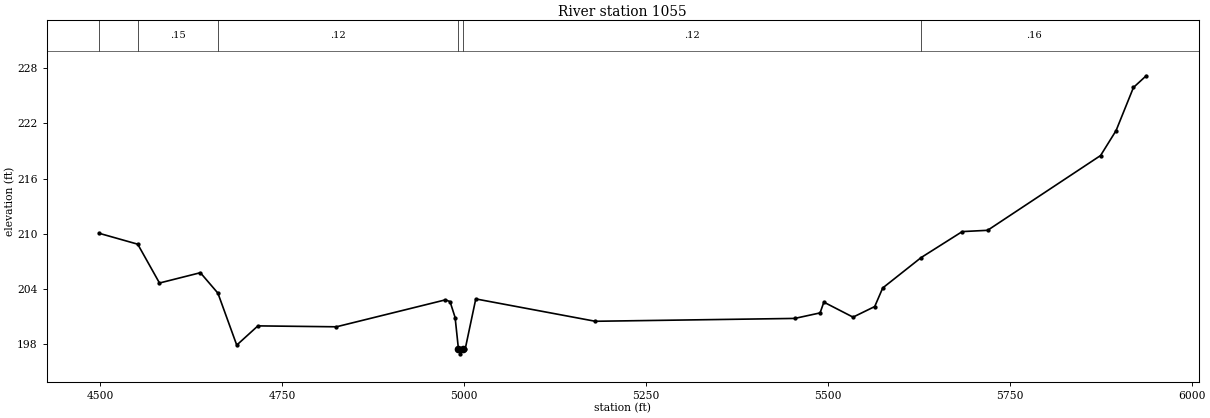
Type RM Length L Ch R = 1,1055,0,0,0
BEGIN DESCRIPTION:
PEACH CREEK SOUTH TRIB 6 1.0
END DESCRIPTION:
XS GIS Cut Line= 3
      3595181.75     10174937.63      3594473.27     10174400.00
      3593942.11     10174541.64
#Sta/Elev= 30
  4498.4  210.04  4551.2  208.86  4581.1  204.64  4637.3  205.76  4661.4  203.54
  4687.3  197.89  4716.4  199.98  4824.3  199.88  4974.2  202.81  4980.5  202.62
  4987.5  200.89  4992.1  197.44  4994.8  196.94  4998.1  197.44  5001.3  197.44
  5015.9  202.91  5180.2  200.48  5454.3  200.79  5489.2  201.39  5494.4  202.56
  5534.5  200.93  5564.3  202.08  5575.3  204.10  5628.2  207.41  5684.6  210.23
  5719.5  210.37  5874.8  218.50  5896.1  221.21  5920.0  225.90  5937.5  227.17
#Mann=6,-1,0
  4498.4     0.1       0  4551.2    0.15       0  4661.4    0.12       0
  4992.1    0.07       0  4998.1    0.12       0  5628.2    0.16       0
Bank Sta=4992.1,4998.1
Exp/Cntr=0.3,0.1

Chan Stop Cuts=-1