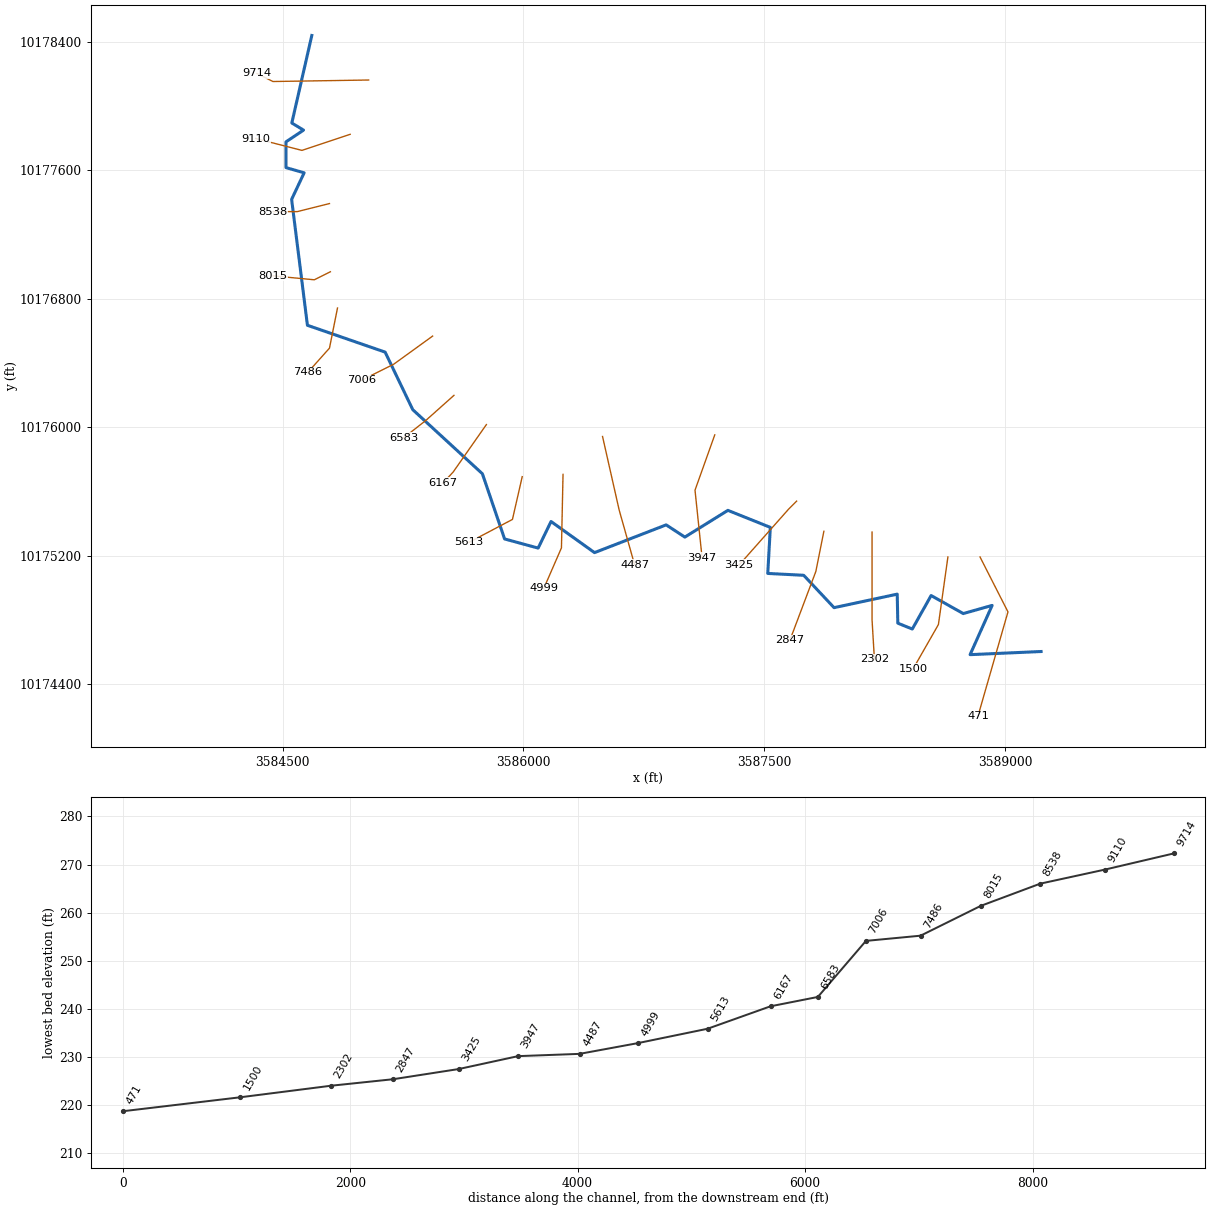
--- PEACH CREEK SOUTH TRIB 7 2.prj (project) ---

Proj Title=PEACH CREEK SOUTH TRIB 7 2 Base Level Engineering
Current Plan=p01
Default Exp/Contr=0.3,0.1
English Units
Geom File=g01
Flow File=f01
Plan File=p01
Y Axis Title=Elevation
X Axis Title(PF)=Main Channel Distance
X Axis Title(XS)=Station
BEGIN DESCRIPTION:
PEACH CREEK SOUTH TRIB 7 2
END DESCRIPTION:
DSS Export Rating Curves= 0
DSS Export Rating Curve Sorted= 0
DSS Export Volume Flow Curves= 0
DXF OffsetX= 0
DXF OffsetY= 0
DXF ScaleX= 1
DXF ScaleY= 10

--- PEACH CREEK SOUTH TRIB 7 2.p01 (plan) ---

Plan Title=Multiple Run
Short Identifier=Multiple
Geom File=g01
Flow File=f01
Subcritical Flow
K Sum by GR= 0
Std Step Tol= 0.01
Critical Tol= 0.01
Num of Std Step Trials= 20
Max Error Tol= 0.3
Flow Tol Ratio= 0.001
Split Flow NTrial= 30
Split Flow Tol= 0.02
Split Flow Ratio= 0.02
Log Output Level= 0
Friction Slope Method= 1
Unsteady Friction Slope Method= 2
Unsteady Bridges Friction Slope Method= 1
Parabolic Critical Depth
Global Vel Dist=  1 , 1 , 1
Global Log Level= 0
CheckData=True
Encroach Param= -1, 0, 0, 0
BEGIN DESCRIPTION:
Multiple Run
END DESCRIPTION:

--- PEACH CREEK SOUTH TRIB 7 2.f01 (steady flow) ---

Flow Title=Multiple
Number of Profiles=7
Profile Names=10-year,25-year,50-year,1pct_min,100-year,1pct_plu,500-year
River Rch & RM= PEACH CREEK SOUT,Reach-1,9714
     394     518     617     540     730     987    1021
Boundary for River Rch & Prof#=PEACH CREEK SOUT,Reach-1,1
Up Type=0
Dn Type=3
Dn Slope=0.005
Boundary for River Rch & Prof#=PEACH CREEK SOUT,Reach-1,2
Up Type=0
Dn Type=3
Dn Slope=0.005
Boundary for River Rch & Prof#=PEACH CREEK SOUT,Reach-1,3
Up Type=0
Dn Type=3
Dn Slope=0.005
Boundary for River Rch & Prof#=PEACH CREEK SOUT,Reach-1,4
Up Type=0
Dn Type=3
Dn Slope=0.005
Boundary for River Rch & Prof#=PEACH CREEK SOUT,Reach-1,5
Up Type=0
Dn Type=3
Dn Slope=0.005
Boundary for River Rch & Prof#=PEACH CREEK SOUT,Reach-1,6
Up Type=0
Dn Type=3
Dn Slope=0.005
Boundary for River Rch & Prof#=PEACH CREEK SOUT,Reach-1,7
Up Type=0
Dn Type=3
Dn Slope=0.005

--- PEACH CREEK SOUTH TRIB 7 2.g01 (geometry) ---

Geom Title=Existing Conditions
Program Version=4.10

River Reach=PEACH CREEK SOUT,Reach-1
Reach XY= 30
      3584682.11     10178437.96      3584557.69     10177893.18
       3584630.6     10177848.96       3584521.3     10177775.76
       3584521.3     10177615.58      3584634.42     10177583.17
      3584556.46     10177417.69      3584654.85       10176634.
      3585138.65     10176466.88      3585310.69     10176108.45
      3585744.09     10175709.61      3585882.33     10175303.74
      3586091.21     10175246.84      3586171.45     10175412.37
      3586442.17     10175218.66      3586888.05     10175391.38
      3587004.55     10175315.34      3587272.53     10175481.77
      3587536.69     10175375.77       3587520.7     10175089.05
       3587744.6     10175077.47      3587933.47     10174876.04
      3588326.66      10174960.1      3588330.33     10174779.46
      3588420.43     10174742.95      3588537.68     10174951.38
      3588737.84     10174839.25      3588917.59       10174890.
      3588780.31     10174583.47      3589222.11     10174602.96

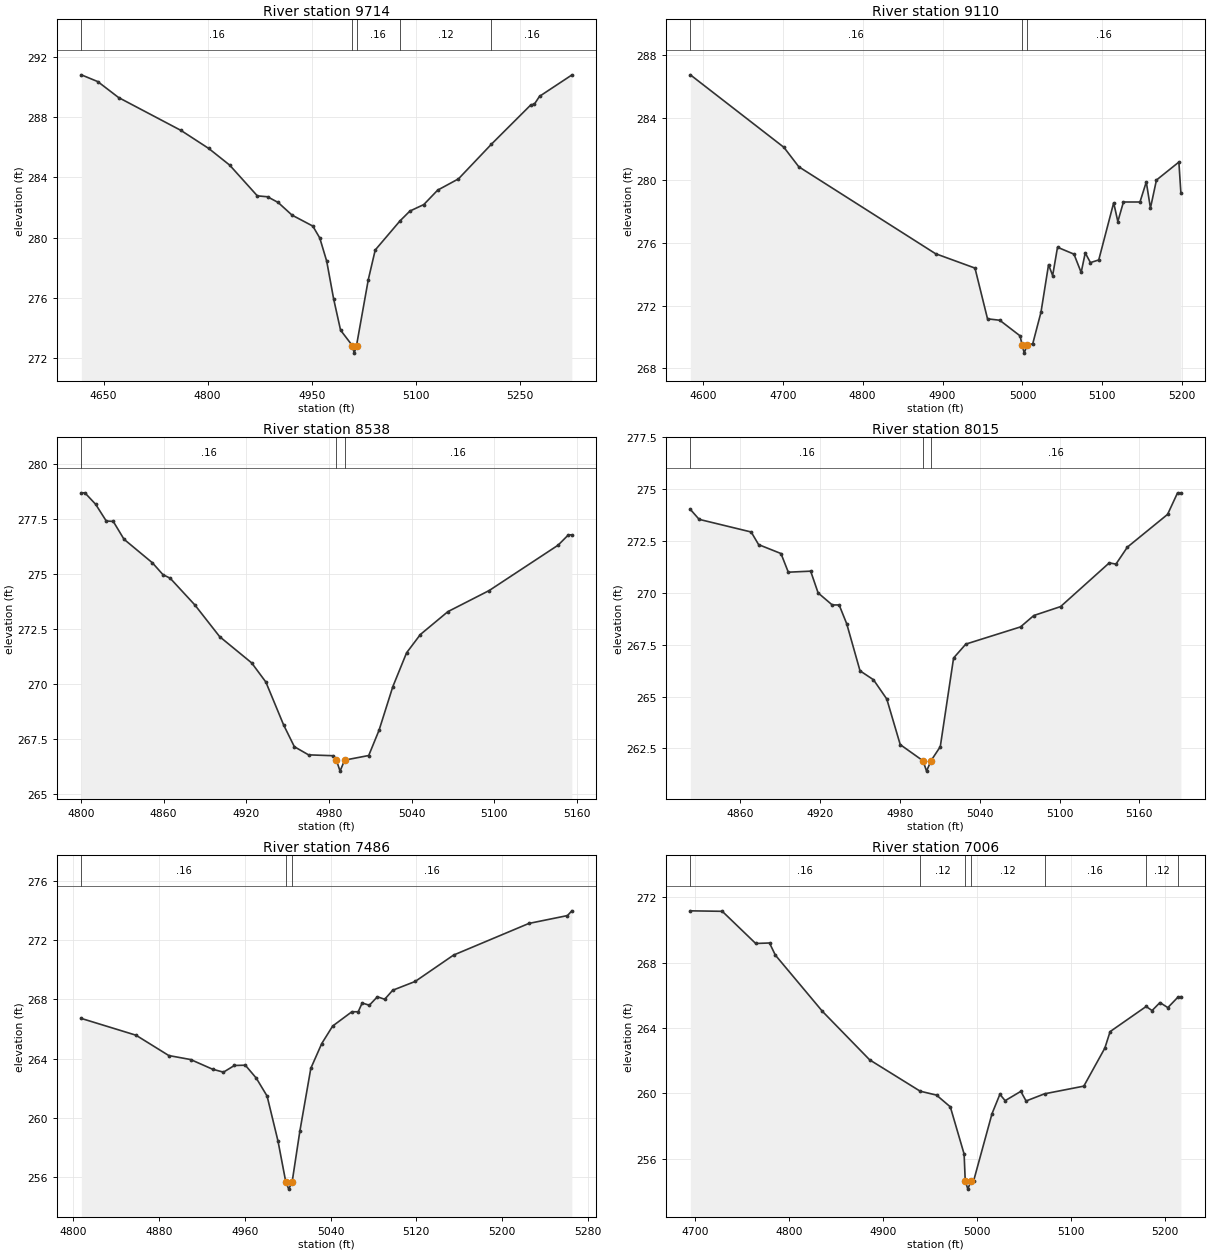
Type RM Length L Ch R = 1 ,9714    ,604,604,604
BEGIN DESCRIPTION:
PEACH CREEK SOUTH TRIB 7.2 19.0
END DESCRIPTION:
XS GIS Cut Line= 3
      3585035.84     10178160.87      3584440.38     10178151.48
      3584340.41     10178201.47
#Sta/Elev= 30
  4617.8  290.82  4641.5  290.37  4671.5  289.31  4761.6  287.12  4801.6  285.92
  4831.6  284.82  4871.6  282.77  4886.3  282.71  4901.6  282.33  4921.6  281.49
  4951.6  280.76  4961.6  279.97  4971.6  278.43  4981.6  275.92  4991.6  273.84
  5008.6  272.81  5011.3  272.31  5014.6  272.81  5031.6   277.2  5041.6  279.17
  5077.4  281.11  5091.6  281.76  5111.6  282.19  5131.6  283.15  5161.6   283.9
  5209.2  286.21  5265.7  288.81  5271.2  288.88  5278.5  289.39  5325.1  290.81
#Mann= 5 ,-1 , 0
  4617.8     .16       0  5008.6     .07       0  5014.6     .16       0
  5077.4     .12       0  5209.2     .16       0
Bank Sta=5008.6,5014.6
XS Rating Curve= 0 ,0
Exp/Cntr=0.3,0.1

Type RM Length L Ch R = 1 ,9110    ,572,572,572
BEGIN DESCRIPTION:
PEACH CREEK SOUTH TRIB 7.2 18.0
END DESCRIPTION:
XS GIS Cut Line= 3
      3584920.84     10177822.77      3584620.83     10177722.76
       3584332.5     10177796.72
#Sta/Elev= 30
  4584.4  286.73  4701.5   282.1  4720.1  280.86  4891.2  275.31  4940.6  274.39
  4956.3  271.15  4971.6  271.06  4997.1  270.06  4999.6  269.46  5002.3  268.96
  5005.6  269.46  5012.9  269.56  5023.2  271.57  5032.7  274.61  5037.8  273.91
  5043.9  275.72  5064.5  275.28  5073.5  274.11  5078.6  275.36  5085.1  274.74
  5095.5  274.91  5114.2  278.56  5119.4  277.36  5126.4  278.61  5147.1  278.61
    5155  279.89  5160.2  278.22  5167.7  280.01  5195.8  281.16  5198.3  279.18
#Mann= 3 ,-1 , 0
  4584.4     .16       0  4999.6     .07       0  5005.6     .16       0
Bank Sta=4999.6,5005.6
XS Rating Curve= 0 ,0
Exp/Cntr=0.3,0.1

Type RM Length L Ch R = 1 ,8538    ,523,523,523
BEGIN DESCRIPTION:
PEACH CREEK SOUTH TRIB 7.2 17.0
END DESCRIPTION:
XS GIS Cut Line= 3
      3584792.15     10177391.65      3584592.11     10177341.64
      3584442.11     10177341.64
#Sta/Elev= 30
  4800.2  278.67  4802.8  278.67  4810.6  278.15  4818.3  277.39  4823.4  277.37
  4831.2  276.56  4851.8  275.49  4859.5  274.95  4864.7  274.79  4882.7  273.57
  4900.7  272.13  4923.9  270.94  4934.2  270.07  4947.1  268.12  4954.9  267.13
  4965.2  266.76  4983.2  266.72  4985.4  266.52  4988.1  266.02  4991.4  266.52
  5008.9  266.73  5016.4  267.88  5026.4  269.86  5036.4   271.4  5046.4  272.23
  5066.4  273.27  5096.4  274.23  5146.4  276.29  5153.9  276.76  5156.4  276.76
#Mann= 3 ,-1 , 0
  4800.2     .16       0  4985.4     .07       0  4991.4     .16       0
Bank Sta=4985.4,4991.4
XS Rating Curve= 0 ,0
Exp/Cntr=0.3,0.1

Type RM Length L Ch R = 1 ,8015    ,529,529,529
BEGIN DESCRIPTION:
PEACH CREEK SOUTH TRIB 7.2 16.0
END DESCRIPTION:
XS GIS Cut Line= 3
      3584797.75     10176967.19      3584697.73     10176917.18
      3584442.13     10176941.64
#Sta/Elev= 30
  4822.6  274.03  4829.2  273.55  4868.3  272.94  4873.9  272.33  4890.7   271.9
  4896.2     271    4913  271.05  4918.6     270  4929.2  269.42  4934.4  269.42
  4940.1  268.51  4950.1  266.24  4960.2  265.81  4970.2  264.88  4980.3  262.68
  4997.4   261.9  5000.1   261.4  5003.4   261.9  5010.4  262.58  5020.4  266.86
  5029.6  267.53  5070.7  268.36  5080.7  268.91  5100.8  269.34  5137.4  271.45
  5142.4  271.39    5151  272.21  5181.2  273.79  5188.7  274.83  5191.2  274.83
#Mann= 3 ,-1 , 0
  4822.6     .16       0  4997.4     .07       0  5003.4     .16       0
Bank Sta=4997.4,5003.4
XS Rating Curve= 0 ,0
Exp/Cntr=0.3,0.1

Type RM Length L Ch R = 1 ,7486    ,480,480,480
BEGIN DESCRIPTION:
PEACH CREEK SOUTH TRIB 7.2 15.0
END DESCRIPTION:
XS GIS Cut Line= 3
       3584842.1     10176741.63      3584792.11     10176491.64
      3584657.04     10176340.55
#Sta/Elev= 30
  4807.5  266.71  4858.5  265.58  4889.1  264.21  4909.5  263.94  4929.9  263.29
  4940.1  263.09  4950.3  263.54  4960.5  263.56  4970.7  262.69  4980.8  261.48
    4991  258.44  4998.2  255.71    5001  255.21  5004.2  255.71  5011.4  259.13
  5021.6  263.35  5031.8  265.02    5042   266.2  5059.9  267.16  5065.8  267.16
  5069.5  267.75  5076.2   267.6  5083.7  268.17  5090.5     268    5098  268.61
  5118.9   269.2  5154.8  270.98    5225  273.11    5261  273.64  5265.1  273.96
#Mann= 3 ,-1 , 0
  4807.5     .16       0  4998.2     .07       0  5004.2     .16       0
Bank Sta=4998.2,5004.2
XS Rating Curve= 0 ,0
Exp/Cntr=0.3,0.1

Type RM Length L Ch R = 1 ,7006    ,423,423,423
BEGIN DESCRIPTION:
PEACH CREEK SOUTH TRIB 7.2 14.0
END DESCRIPTION:
XS GIS Cut Line= 3
      3585434.34      10176566.8      3585192.11     10176391.64
      3584992.13     10176291.66
#Sta/Elev= 30
  4694.7  271.18  4728.7  271.15  4764.3  269.18    4779  269.21  4785.2  268.47
  4835.4  265.02  4885.7  262.05  4939.5  260.13  4956.9  259.89  4971.6  259.17
  4986.3  256.28  4987.5  254.63  4990.3  254.13  4993.5  254.63  4996.4  254.63
    5016  258.75  5024.4  259.94    5030  259.55  5046.7  260.12  5052.3  259.53
    5072  259.97  5113.8  260.44  5136.2  262.77  5141.8  263.78  5180.2  265.32
  5186.5  265.07  5194.9  265.56  5203.3  265.25  5214.2   265.9  5217.2  265.92
#Mann= 7 ,-1 , 0
  4694.7     .16       0  4939.5     .12       0  4987.5     .07       0
  4993.5     .12       0    5072     .16       0  5180.2     .12       0
  5214.2     .16       0
Bank Sta=4987.5,4993.5
XS Rating Curve= 0 ,0
Exp/Cntr=0.3,0.1

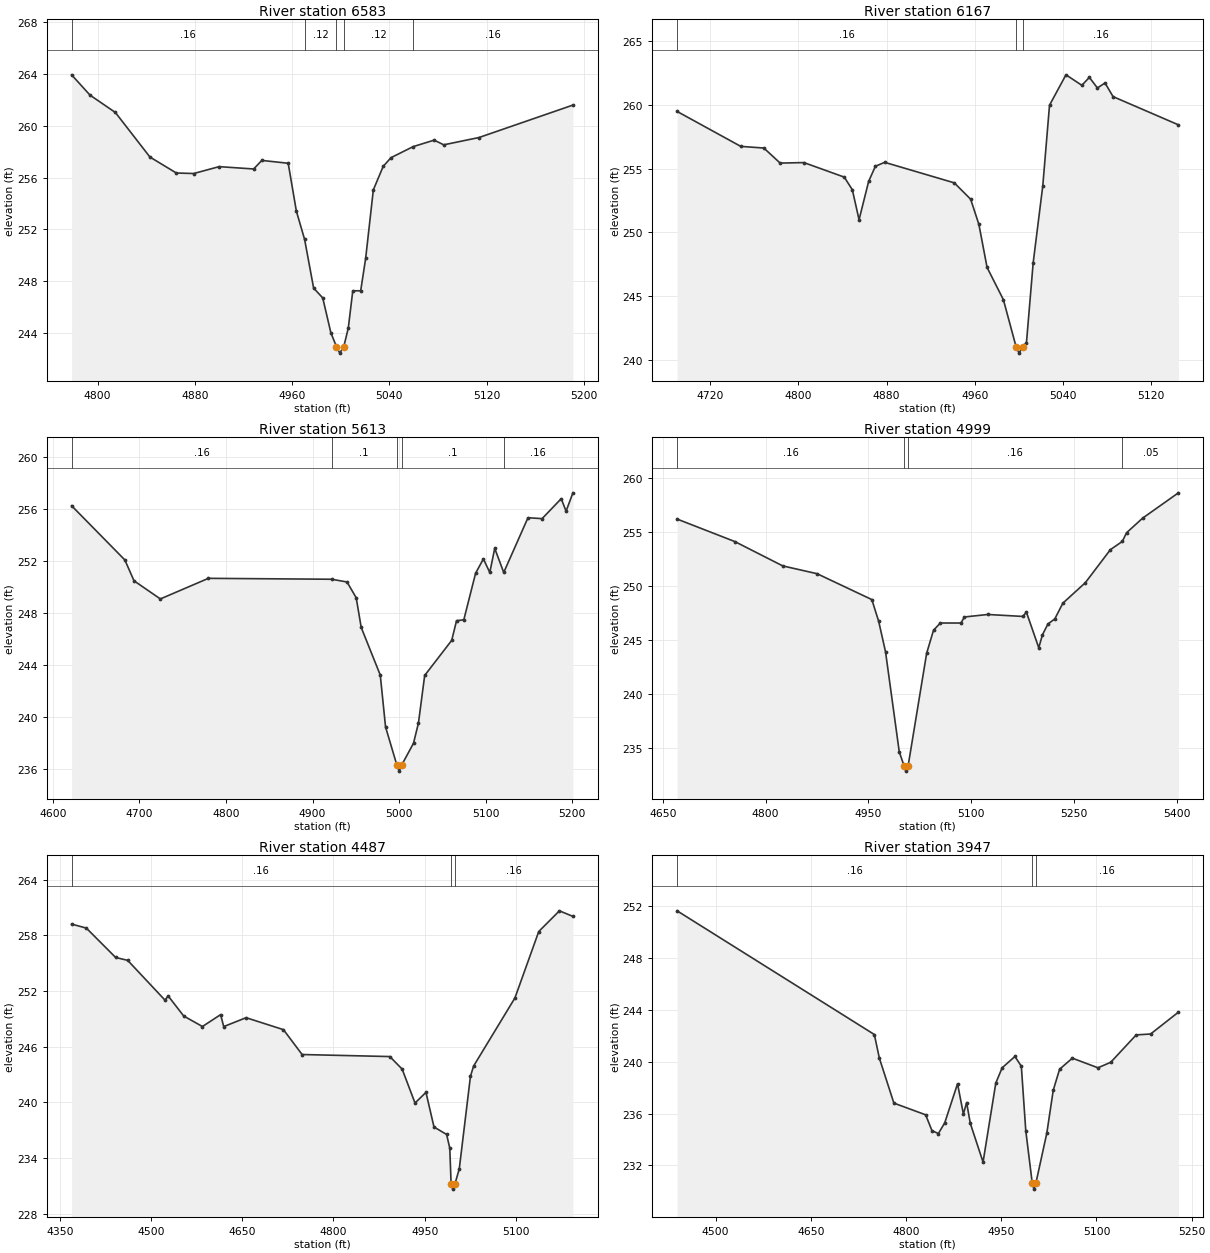
Type RM Length L Ch R = 1 ,6583    ,416,416,416
BEGIN DESCRIPTION:
PEACH CREEK SOUTH TRIB 7.2 13.0
END DESCRIPTION:
XS GIS Cut Line= 3
      3585567.15     10176197.77      3585392.11     10176041.64
      3585252.27     10175932.09
#Sta/Elev= 30
  4778.7  263.91  4793.8  262.35  4814.7  261.01  4843.1  257.58  4864.8  256.35
  4879.1  256.31    4900  256.84  4928.4  256.66  4935.1  257.32  4956.8   257.1
  4963.5  253.42  4970.3  251.23  4977.7  247.49  4985.2  246.73  4991.9  244.04
  4996.5  242.98  4999.2  242.48  5002.5  242.98  5006.2  244.41  5009.9  247.28
  5016.4  247.28  5020.5  249.79  5026.8  255.05  5034.9  256.86  5041.3  257.53
  5059.5  258.38  5076.8  258.88  5084.7  258.52  5113.6  259.08  5190.9  261.58
#Mann= 5 ,-1 , 0
  4778.7     .16       0  4970.3     .12       0  4996.5     .07       0
  5002.5     .12       0  5059.5     .16       0
Bank Sta=4996.5,5002.5
XS Rating Curve= 0 ,0
Exp/Cntr=0.3,0.1

Type RM Length L Ch R = 1 ,6167    ,554,554,554
BEGIN DESCRIPTION:
PEACH CREEK SOUTH TRIB 7.2 12.0
END DESCRIPTION:
XS GIS Cut Line= 3
      3585768.88     10176015.73      3585562.24     10175720.54
       3585498.3     10175651.68
#Sta/Elev= 30
  4690.2  259.49  4747.9  256.75  4768.8  256.62  4783.6  255.44  4805.1  255.48
  4841.7  254.34    4849  253.35  4855.1     251  4863.8  254.01  4869.9  255.19
  4878.3   255.5  4941.4  253.89  4956.2  252.61  4963.7  250.63  4971.1  247.26
  4985.9  244.73  4997.4  241.04  5000.1  240.54  5003.4  241.04  5006.8  241.36
  5012.9  247.63  5021.6  253.66  5027.7  259.98  5042.6  262.36    5057  261.54
  5063.8  262.16  5071.1  261.33    5078  261.72  5085.3  260.65  5144.5  258.44
#Mann= 3 ,-1 , 0
  4690.2     .16       0  4997.4     .07       0  5003.4     .16       0
Bank Sta=4997.4,5003.4
XS Rating Curve= 0 ,0
Exp/Cntr=0.3,0.1

Type RM Length L Ch R = 1 ,5613    ,614,614,614
BEGIN DESCRIPTION:
PEACH CREEK SOUTH TRIB 7.2 11.0
END DESCRIPTION:
XS GIS Cut Line= 3
       3585992.1      10175691.6      3585931.25     10175425.34
      3585660.68     10175282.68
#Sta/Elev= 30
  4621.7  256.23  4683.2  252.07  4693.8  250.47  4724.2  249.08  4779.7  250.66
  4922.1  250.59  4939.8  250.38  4950.4  249.17  4956.2  246.89  4978.2  243.24
  4984.3  239.26  4997.2  236.37    5000  235.87  5003.2  236.37  5016.6  238.01
  5022.3  239.56  5029.5  243.21  5060.7   245.9  5066.3  247.41  5074.7  247.48
  5088.3  251.05  5097.3  252.15  5104.7  251.11  5110.4  252.96  5120.8  251.11
  5148.8  255.31  5165.1  255.24  5187.2  256.77  5192.8  255.81  5200.7  257.22
#Mann= 5 ,-1 , 0
  4621.7     .16       0  4922.1      .1       0  4997.2     .07       0
  5003.2      .1       0  5120.8     .16       0
Bank Sta=4997.2,5003.2
XS Rating Curve= 0 ,0
Exp/Cntr=0.3,0.1

Type RM Length L Ch R = 1 ,4999    ,512,512,512
BEGIN DESCRIPTION:
PEACH CREEK SOUTH TRIB 7.2 9.0
END DESCRIPTION:
XS GIS Cut Line= 3
      3586246.13     10175705.77      3586236.29     10175248.22
      3586126.93     10174997.05
#Sta/Elev= 30
  4670.8  256.23  4754.9  254.15    4825  251.89    4875  251.17    4955  248.77
    4965  246.75    4975  243.93    4995  234.67    5002  233.38  5004.8  232.88
    5008  233.38    5035   243.8    5045  245.93    5055   246.6    5085   246.6
  5090.2  247.16  5124.2  247.39  5175.2  247.21  5180.6   247.6  5198.6  244.31
    5204  245.51    5212  246.51    5222  246.98  5233.8  248.44  5266.5  250.33
  5303.2   253.4  5320.6  254.16  5326.7  254.96  5350.1  256.31  5402.4  258.66
#Mann= 4 ,-1 , 0
  4670.8     .16       0    5002     .07       0    5008     .16       0
  5320.6     .05       0
Bank Sta=5002,5008
XS Rating Curve= 0 ,0
Exp/Cntr=0.3,0.1

Type RM Length L Ch R = 1 ,4487    ,540,540,540
BEGIN DESCRIPTION:
PEACH CREEK SOUTH TRIB 7.2 8.0
END DESCRIPTION:
XS GIS Cut Line= 3
      3586492.11     10175941.64      3586595.45     10175484.38
      3586692.11     10175141.64
#Sta/Elev= 30
  4369.1  259.22  4393.3  258.79  4441.6  255.62  4461.4  255.31  4522.8  251.02
  4527.9  251.48  4553.6  249.31  4584.4  248.18  4614.3  249.46  4619.4  248.17
  4656.2  249.13  4717.7  247.84  4748.4  245.16  4892.7  244.94    4913  243.59
  4934.2  239.93  4952.2  241.08  4965.4  237.35  4986.2  236.54  4991.4  235.06
  4993.6  231.15  4996.3  230.65  4999.6  231.15    5007  232.83  5025.4  242.81
  5030.6  243.92  5098.6  251.26  5137.8  258.42  5171.8  260.65    5194  260.05
#Mann= 3 ,-1 , 0
  4369.1     .16       0  4993.6     .07       0  4999.6     .16       0
Bank Sta=4993.6,4999.6
XS Rating Curve= 0 ,0
Exp/Cntr=0.3,0.1

Type RM Length L Ch R = 1 ,3947    ,522,522,522
BEGIN DESCRIPTION:
PEACH CREEK SOUTH TRIB 7.2 7.0
END DESCRIPTION:
XS GIS Cut Line= 3
      3587190.77     10175951.78      3587067.77     10175607.38
      3587111.92     10175185.49
#Sta/Elev= 30
  4439.2   251.6    4750  242.08  4757.9  240.26  4780.8   236.8  4830.8   235.9
  4840.8  234.68  4850.9  234.46  4860.9  235.28  4881.1  238.29  4890.3  235.96
  4895.4  236.84  4901.2  235.24  4921.3  232.26  4941.4  238.35  4951.4  239.52
  4971.5  240.39  4981.6  239.64  4988.6  234.68  4998.7  230.68  5001.5  230.18
  5004.7  230.68  5021.8   234.5  5031.9  237.79  5041.9  239.41    5062  240.26
  5102.3  239.52  5122.4  239.94  5162.6  242.05  5185.3  242.12  5229.1   243.8
#Mann= 3 ,-1 , 0
  4439.2     .16       0  4998.7     .07       0  5004.7     .16       0
Bank Sta=4998.7,5004.7
XS Rating Curve= 0 ,0
Exp/Cntr=0.3,0.1

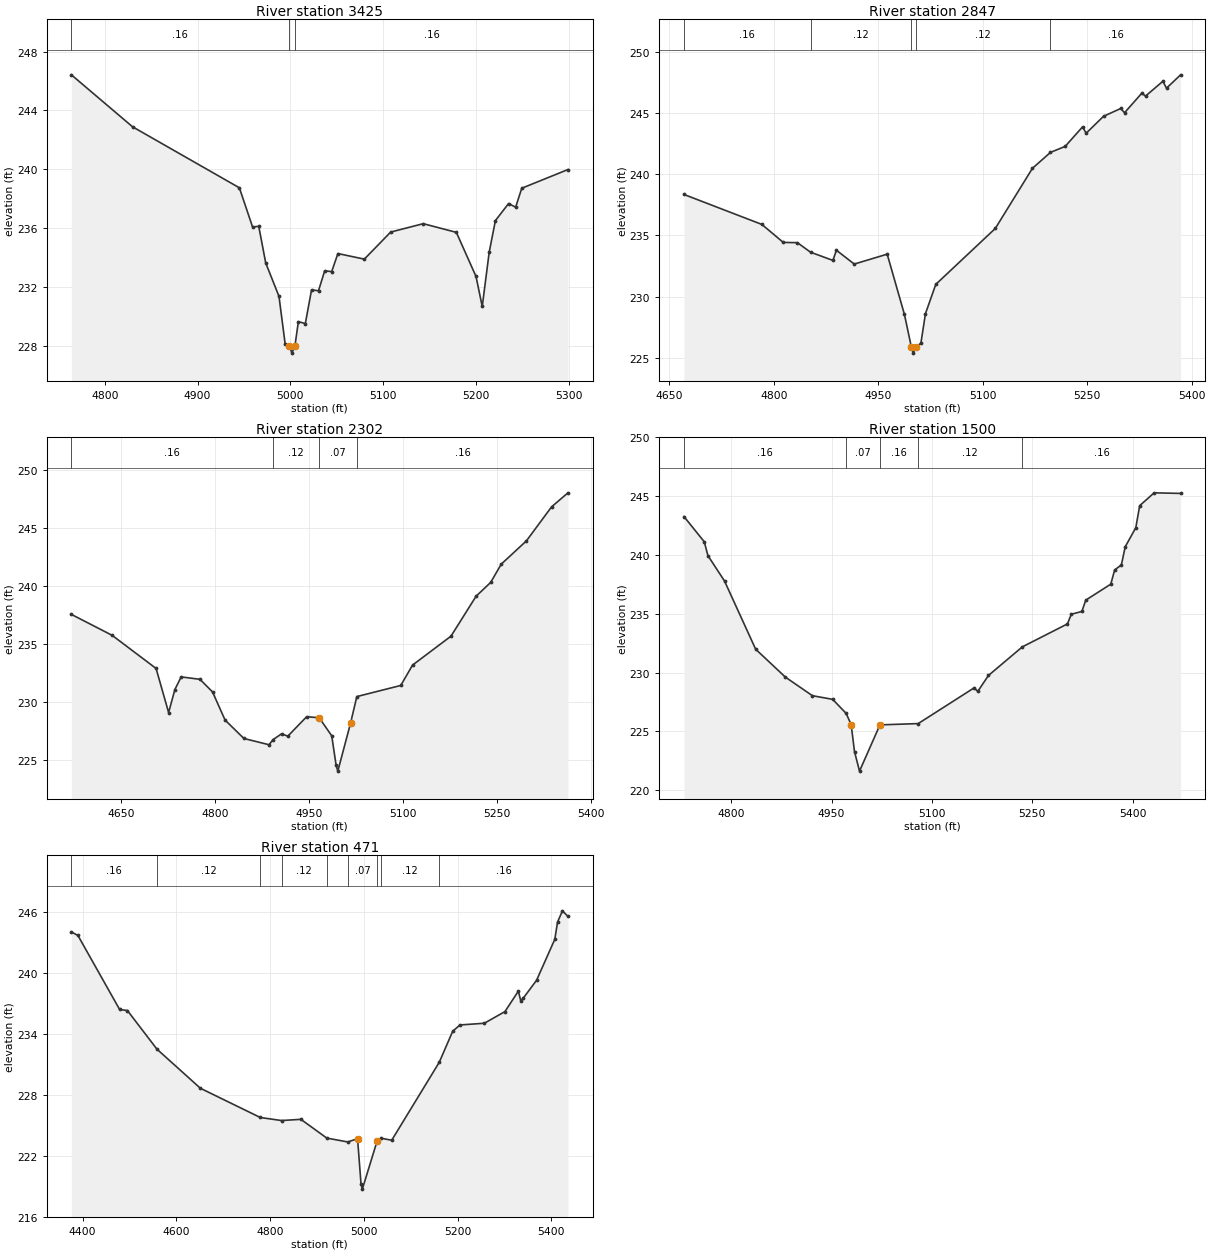
Type RM Length L Ch R = 1 ,3425    ,578,578,578
BEGIN DESCRIPTION:
PEACH CREEK SOUTH TRIB 7.2 6.0
END DESCRIPTION:
XS GIS Cut Line= 3
      3587700.35     10175539.25      3587650.35     10175489.24
      3587342.11     10175141.64
#Sta/Elev= 30
    4764  246.42  4829.9  242.89  4945.1  238.74  4959.3  236.08    4966  236.12
  4973.5  233.63  4987.8  231.36  4994.4  228.15    4999     228  5001.7   227.5
    5005     228  5008.7  229.64  5016.2  229.51  5022.9   231.8  5030.4  231.74
  5037.1   233.1  5044.6  233.04  5051.3  234.27  5079.8  233.89  5108.2  235.73
  5143.3   236.3    5179  235.71  5200.2  232.71  5206.9  230.67  5214.4  234.36
  5221.1  236.51  5235.3  237.67  5242.9  237.42  5249.5  238.71  5299.3  239.98
#Mann= 3 ,-1 , 0
    4764     .16       0    4999     .07       0    5005     .16       0
Bank Sta=4999,5005
XS Rating Curve= 0 ,0
Exp/Cntr=0.3,0.1

Type RM Length L Ch R = 1 ,2847    ,545,545,545
BEGIN DESCRIPTION:
PEACH CREEK SOUTH TRIB 7.2 5.0
END DESCRIPTION:
XS GIS Cut Line= 3
      3587870.03     10175351.51      3587820.03     10175101.48
      3587658.18     10174672.58
#Sta/Elev= 30
  4670.9  238.35  4782.8   235.9  4813.5  234.43  4833.8  234.41  4852.7  233.63
  4884.8  232.96  4889.9  233.79  4915.5  232.66  4962.8  233.47  4987.6  228.54
  4997.5  225.88  5000.3  225.38  5003.5  225.88  5011.2  226.18  5017.8  228.61
  5032.6     231  5118.1  235.57  5171.5  240.49  5197.4  241.79  5218.5  242.28
  5243.4  243.87  5248.7  243.36  5273.6  244.74  5298.4  245.38  5303.8  245.03
  5328.6  246.63  5333.9  246.39  5358.8   247.6  5364.1  247.04  5384.3  248.13
#Mann= 5 ,-1 , 0
  4670.9     .16       0  4852.7     .12       0  4997.5     .07       0
  5003.5     .12       0  5197.4     .16       0
Bank Sta=4997.5,5003.5
XS Rating Curve= 0 ,0
Exp/Cntr=0.3,0.1

Type RM Length L Ch R = 1 ,2302    ,802,802,802
BEGIN DESCRIPTION:
PEACH CREEK SOUTH TRIB 7.2 4.0
END DESCRIPTION:
XS GIS Cut Line= 3
      3588169.86     10175346.61      3588170.03     10174798.96
      3588184.55     10174555.54
#Sta/Elev= 30
  4571.2  237.57  4636.2  235.76  4706.2   232.9  4726.2  229.09  4736.2  231.08
  4746.2  232.17  4776.2  231.96  4796.2  230.87  4816.2  228.44  4846.2  226.85
  4886.2  226.31  4892.9  226.76  4906.2  227.25  4916.2  227.05  4946.2  228.73
  4966.2  228.64  4986.2  227.08  4993.2  224.53  4995.9  224.03  5016.2  228.18
  5026.2  230.47  5096.2  231.43    5115  233.19  5176.3  235.69  5216.3  239.14
  5239.5  240.33  5256.4  241.91  5296.5  243.92  5336.6  246.86  5362.7  248.07
#Mann= 4 ,-1 , 0
  4571.2     .16       0  4892.9     .12       0  4966.2     .07       0
  5026.2     .16       0
Bank Sta=4966.2,5016.2
XS Rating Curve= 0 ,0
Exp/Cntr=0.3,0.1

Type RM Length L Ch R = 1 ,1500    ,1029,1029,1029
BEGIN DESCRIPTION:
PEACH CREEK SOUTH TRIB 7.2 2.0
END DESCRIPTION:
XS GIS Cut Line= 3
      3588642.11     10175191.65      3588583.14     10174770.97
      3588425.71     10174495.47
#Sta/Elev= 30
  4729.5  243.25  4759.8  241.11  4765.2  239.94  4790.1  237.77  4836.6  231.98
    4881  229.61  4921.4  228.03  4951.7  227.72  4971.9  226.52  4979.3  225.57
  4984.3  223.28  4991.8  221.62  5022.3  225.55  5079.5  225.66  5162.9  228.69
  5168.6   228.4  5184.5  229.75  5235.1  232.18  5302.5  234.13  5308.3  234.95
  5324.1  235.19  5329.9  236.15  5367.3  237.51  5373.1  238.72  5383.1  239.14
  5388.9  240.69  5404.7  242.31  5410.5  244.18  5432.1  245.27  5471.6  245.22
#Mann= 5 ,-1 , 0
  4729.5     .16       0  4971.9     .07       0  5022.3     .16       0
  5079.5     .12       0  5235.1     .16       0
Bank Sta=4979.3,5022.3
XS Rating Curve= 0 ,0
Exp/Cntr=0.3,0.1

Type RM Length L Ch R = 1 ,471     ,0,0,0
BEGIN DESCRIPTION:
PEACH CREEK SOUTH TRIB 7.2 1.0
END DESCRIPTION:
XS GIS Cut Line= 3
      3588842.09     10175191.67       3589016.1     10174849.69
      3588829.15     10174200.27
#Sta/Elev= 30
  4375.9  244.08  4389.9  243.73  4478.8  236.44  4495.5  236.33  4558.6  232.52
  4651.2  228.67    4779  225.79  4824.4  225.49  4865.6  225.61  4920.9  223.76
  4965.7  223.38  4986.5   223.7  4993.9  219.23  4996.7  218.73  5028.1  223.45
  5037.2  223.74  5059.4  223.55  5160.8  231.23  5189.6   234.3    5205  234.91
    5257  235.08    5301  236.23  5329.5  238.24  5334.7   237.3  5340.3  237.57
  5368.4  239.31  5407.3  243.35  5413.2  245.05  5423.6  246.16  5435.4  245.61
#Mann= 9 ,-1 , 0
  4375.9     .16       0  4558.6     .12       0    4779     .16       0
  4824.4     .12       0  4920.9     .16       0  4965.7     .07       0
  5028.1     .16       0  5037.2     .12       0  5160.8     .16       0
Bank Sta=4986.5,5028.1
XS Rating Curve= 0 ,0
Exp/Cntr=0.3,0.1

Chan Stop Cuts=-1
Use User Specified Reach Order=0
Composite Channel Slope=5