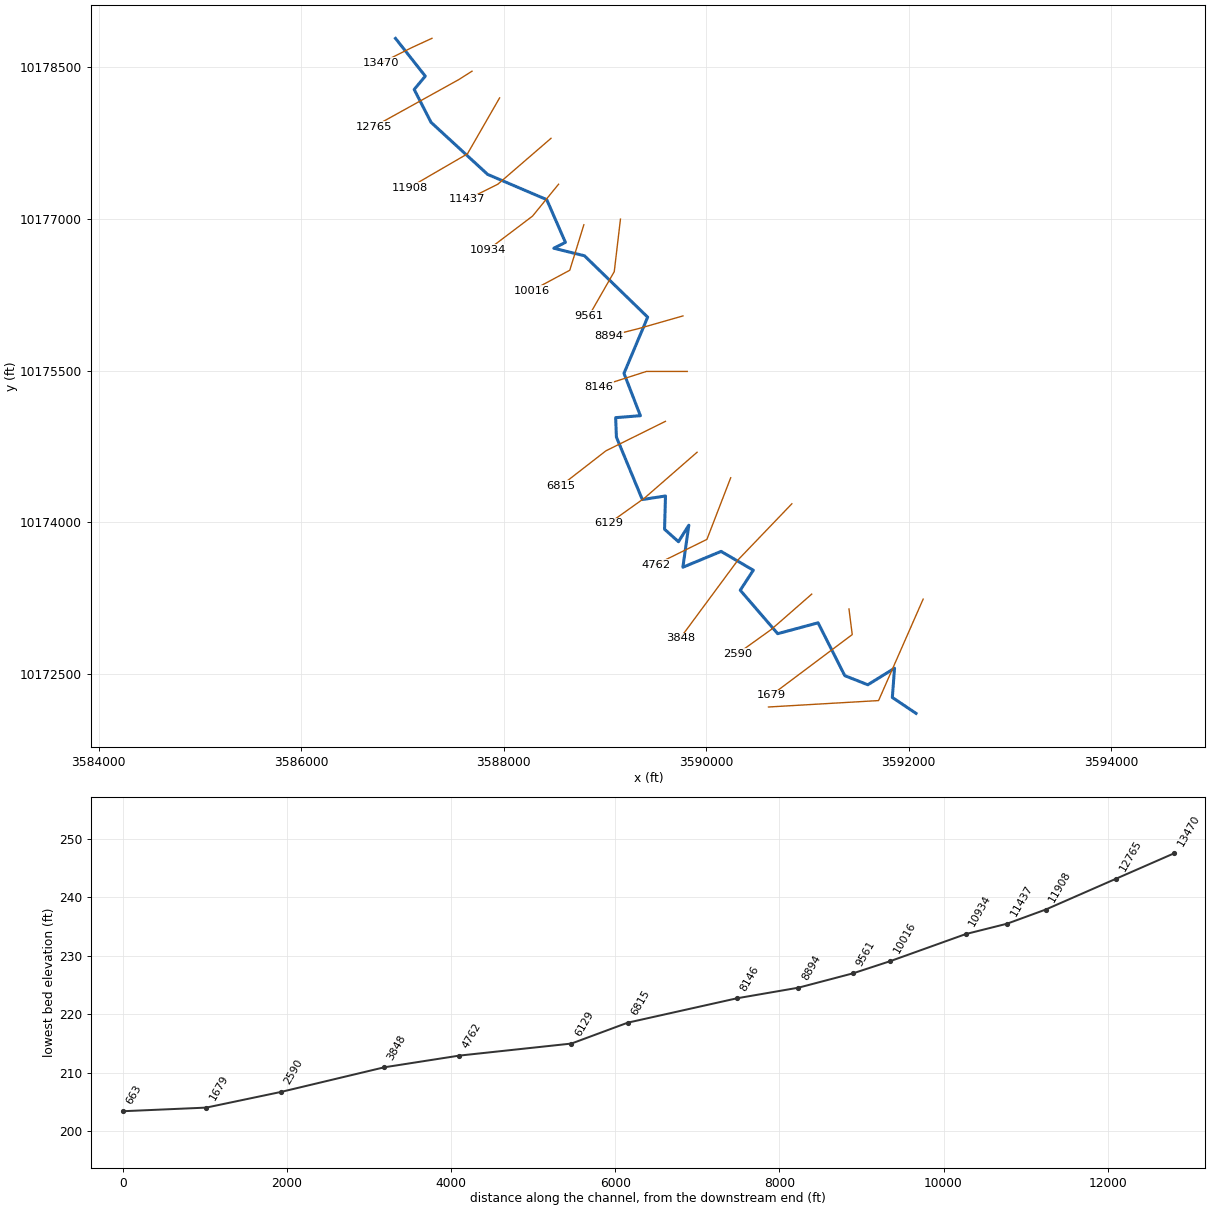
--- PEACH CREEK SOUTH TRIB 7.prj (project) ---

Proj Title=PEACH CREEK SOUTH TRIB 7 Base Level Engineering
Current Plan=p01
Default Exp/Contr=0.3,0.1
English Units
Geom File=g01
Flow File=f01
Plan File=p01
Y Axis Title=Elevation
X Axis Title(PF)=Main Channel Distance
X Axis Title(XS)=Station
BEGIN DESCRIPTION:
PEACH CREEK SOUTH TRIB 7
END DESCRIPTION:
DSS Export Rating Curves= 0
DSS Export Rating Curve Sorted= 0
DSS Export Volume Flow Curves= 0
DXF OffsetX= 0
DXF OffsetY= 0
DXF ScaleX= 1
DXF ScaleY= 10

--- PEACH CREEK SOUTH TRIB 7.p01 (plan) ---

Plan Title=Multiple Run
Short Identifier=Multiple
Geom File=g01
Flow File=f01
Subcritical Flow
K Sum by GR= 0
Std Step Tol= 0.01
Critical Tol= 0.01
Num of Std Step Trials= 20
Max Error Tol= 0.3
Flow Tol Ratio= 0.001
Split Flow NTrial= 30
Split Flow Tol= 0.02
Split Flow Ratio= 0.02
Log Output Level= 0
Friction Slope Method= 1
Unsteady Friction Slope Method= 2
Unsteady Bridges Friction Slope Method= 1
Parabolic Critical Depth
Global Vel Dist=  1 , 1 , 1
Global Log Level= 0
CheckData=True
Encroach Param= -1, 0, 0, 0
BEGIN DESCRIPTION:
Multiple Run
END DESCRIPTION:

--- PEACH CREEK SOUTH TRIB 7.f01 (steady flow) ---

Flow Title=Multiple
Program Version=4.10
Number of Profiles= 7
Profile Names=10-year,25-year,50-year,1pct_min,100-year,1pct_plu,500-year
River Rch & RM=PEACH CREEK SOUT,Reach-1         ,13470
     446     592     710     624     844    1142    1196
River Rch & RM=PEACH CREEK SOUT,Reach-1         ,6815
     756    1032    1260    1125    1522    2058    2227
River Rch & RM=PEACH CREEK SOUT,Reach-1         ,6129
     756    1032    1260    1125    1522    2058    2227
Boundary for River Rch & Prof#=PEACH CREEK SOUT,Reach-1         , 1
Up Type= 0
Dn Type= 3
Dn Slope=0.005
Boundary for River Rch & Prof#=PEACH CREEK SOUT,Reach-1         , 2
Up Type= 0
Dn Type= 3
Dn Slope=0.005
Boundary for River Rch & Prof#=PEACH CREEK SOUT,Reach-1         , 3
Up Type= 0
Dn Type= 3
Dn Slope=0.005
Boundary for River Rch & Prof#=PEACH CREEK SOUT,Reach-1         , 4
Up Type= 0
Dn Type= 3
Dn Slope=0.005
Boundary for River Rch & Prof#=PEACH CREEK SOUT,Reach-1         , 5
Up Type= 0
Dn Type= 3
Dn Slope=0.005
Boundary for River Rch & Prof#=PEACH CREEK SOUT,Reach-1         , 6
Up Type= 0
Dn Type= 3
Dn Slope=0.005
Boundary for River Rch & Prof#=PEACH CREEK SOUT,Reach-1         , 7
Up Type= 0
Dn Type= 3
Dn Slope=0.005
DSS Import GetInterval= 0
DSS Import GetPeak= 0
DSS Import FillOption= 0

--- PEACH CREEK SOUTH TRIB 7.g01 (geometry) ---

Geom Title=Existing Conditions
Program Version=4.10

River Reach=PEACH CREEK SOUT,Reach-1
Reach XY= 30
      3586932.11     10178782.96      3587226.11     10178409.97
      3587116.54     10178278.52      3587282.67     10177953.94
       3587841.3     10177439.59      3588425.46     10177189.49
      3588609.75     10176767.53      3588495.62     10176709.31
      3588797.82     10176634.94      3589422.12     10176028.33
       3589188.2     10175472.95      3589350.07      10175054.7
      3589105.85     10175035.16      3589113.43     10174843.28
      3589369.34     10174225.95      3589598.09     10174261.21
      3589588.82     10173932.43      3589726.33     10173809.38
      3589828.34     10173972.24      3589769.84     10173557.07
      3590147.18     10173713.64      3590465.02     10173527.64
       3590336.3     10173329.83      3590706.15     10172900.48
      3591104.66     10173007.86      3591368.29     10172485.87
      3591595.79     10172395.61      3591859.88     10172559.37
      3591837.92     10172270.22      3592072.11     10172112.96

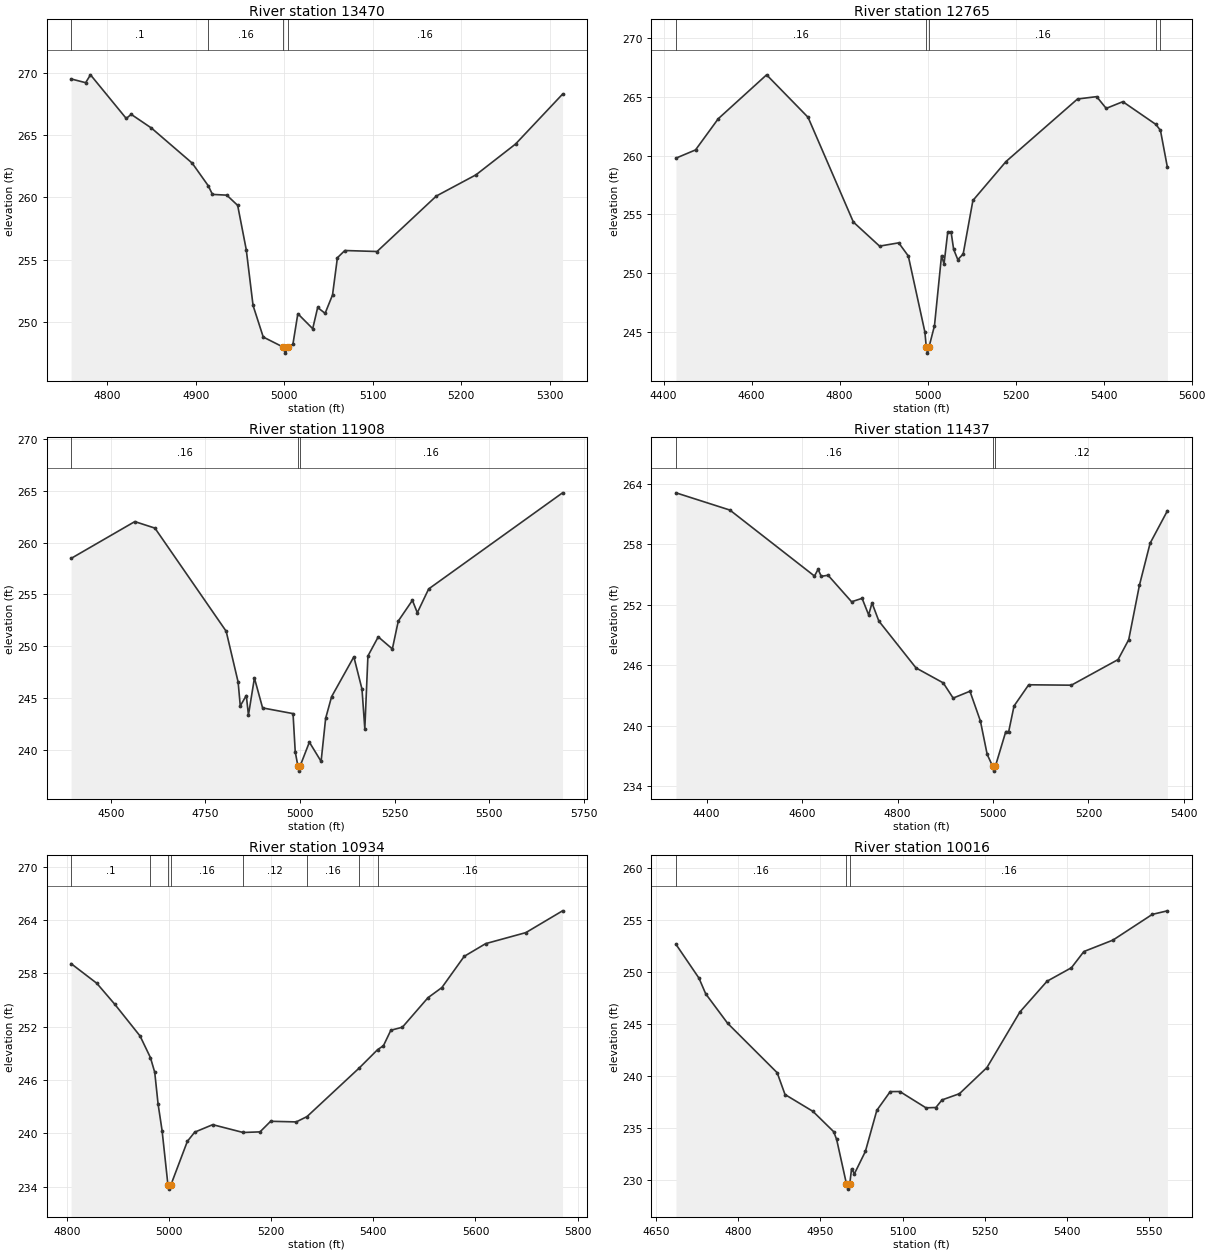
Type RM Length L Ch R = 1 ,13470   ,705,705,705
BEGIN DESCRIPTION:
PEACH CREEK SOUTH TRIB 7 22.0
END DESCRIPTION:
XS GIS Cut Line= 3
      3587291.84     10178783.59      3587092.11     10178691.64
       3586792.1     10178541.64
#Sta/Elev= 30
  4759.3   269.5  4775.7   269.2  4781.2  269.83  4821.6  266.33  4827.2  266.66
  4850.1  265.56  4896.1  262.75  4914.3  260.93    4919  260.24  4935.2  260.18
  4947.5  259.36  4957.2  255.81  4964.9  251.33  4976.4   248.8  4998.5  248.01
  5001.3  247.51  5004.5  248.01  5009.9  248.21  5015.5  250.67  5032.3  249.47
  5037.9  251.17  5046.3   250.7  5054.7  252.18  5060.2  255.16  5068.6  255.74
    5105  255.66    5172  260.11  5216.8  261.81  5261.5  264.28  5314.6  268.28
#Mann= 4 ,-1 , 0
  4759.3      .1       0  4914.3     .16       0  4998.5     .07       0
  5004.5     .16       0
Bank Sta=4998.5,5004.5
XS Rating Curve= 0 ,0
Exp/Cntr=0.3,0.1

Type RM Length L Ch R = 1 ,12765   ,857,857,857
BEGIN DESCRIPTION:
PEACH CREEK SOUTH TRIB 7 20.0
END DESCRIPTION:
XS GIS Cut Line= 3
      3587687.44     10178458.67      3587556.56     10178375.58
      3586715.57     10177909.15
#Sta/Elev= 30
  4428.2   259.8  4472.6   260.5  4524.3  263.16  4634.1   266.9  4728.3  263.28
  4831.3  254.35  4890.8   252.3  4934.3  252.58  4956.1  251.46  4993.8  244.98
    4997  243.68  4999.7  243.18    5003  243.68  5015.6  245.52  5031.6  251.49
  5037.3  250.78  5045.7  253.49  5053.3  253.51  5059.1  252.03  5068.6  251.15
  5080.8  251.63  5102.9  256.19  5178.1  259.51  5340.6  264.84  5384.1  265.04
  5405.8  264.04  5443.6  264.61  5518.8  262.67  5529.1  262.16  5544.9  259.01
#Mann= 5 ,-1 , 0
  4428.2     .16       0    4997     .07       0    5003     .16       0
  5518.8     .07       0  5529.1     .16       0
Bank Sta=4997,5003
XS Rating Curve= 0 ,0
Exp/Cntr=0.3,0.1

Type RM Length L Ch R = 1 ,11908   ,471,471,471
BEGIN DESCRIPTION:
PEACH CREEK SOUTH TRIB 7 19.0
END DESCRIPTION:
XS GIS Cut Line= 3
      3587959.77     10178194.78      3587642.11     10177641.64
      3587070.05      10177309.4
#Sta/Elev= 30
  4394.9  258.47  4563.3  262.03  4616.5   261.4  4804.9  251.43  4836.5  246.52
  4842.2  244.21  4858.1  245.22  4863.8  243.33  4879.6  246.91  4901.2  244.02
  4981.7  243.47  4987.5  239.78  4994.5  238.41  4997.3  237.91  5000.5  238.41
  5024.9  240.71  5055.9  238.85  5067.9  243.01  5083.7  245.11  5142.5  248.96
    5164  245.84  5171.5     242  5179.7  249.04    5207  250.89  5244.3  249.72
    5260  252.42  5297.3  254.42  5310.3  253.22  5340.3  255.52  5694.3  264.81
#Mann= 3 ,-1 , 0
  4394.9     .16       0  4994.5     .07       0  5000.5     .16       0
Bank Sta=4994.5,5000.5
XS Rating Curve= 0 ,0
Exp/Cntr=0.3,0.1

Type RM Length L Ch R = 1 ,11437   ,503,503,503
BEGIN DESCRIPTION:
PEACH CREEK SOUTH TRIB 7 18.0
END DESCRIPTION:
XS GIS Cut Line= 3
      3588467.61     10177795.52      3587942.11     10177341.64
      3587642.09     10177191.64
#Sta/Elev= 30
  4335.7  263.08  4448.7  261.37  4625.9  254.83  4633.5   255.5  4640.1   254.8
  4654.4  254.91  4703.7  252.28  4725.7  252.62  4739.4  250.98  4746.5  252.16
  4760.8  250.37  4838.7  245.72  4895.7  244.24  4916.5  242.73  4951.7  243.41
  4973.6  240.46  4987.8  237.15  4999.1  235.99  5001.8  235.49  5005.1  235.99
  5026.8  239.41  5032.9  239.41  5044.1  241.95  5074.8  244.05  5164.2  244.01
  5262.1  246.55  5284.4  248.52  5306.8  253.91  5329.2  258.08  5365.5   261.3
#Mann= 3 ,-1 , 0
  4335.7     .16       0  4999.1     .07       0  5005.1     .12       0
Bank Sta=4999.1,5005.1
XS Rating Curve= 0 ,0
Exp/Cntr=0.3,0.1

Type RM Length L Ch R = 1 ,10934   ,918,918,918
BEGIN DESCRIPTION:
PEACH CREEK SOUTH TRIB 7 17.0
END DESCRIPTION:
XS GIS Cut Line= 3
      3588542.14     10177341.68      3588284.85     10177026.62
      3587842.07     10176691.61
#Sta/Elev= 30
  4808.5  259.08  4858.8  256.87    4894  254.51  4943.5  250.94  4963.8  248.51
  4972.2  246.86  4978.7  243.31  4986.6   240.3    4998  234.22  5000.7  233.72
    5004  234.22  5036.1   239.1  5050.5  240.13  5085.7  240.97  5145.3  240.09
  5178.3  240.16  5199.1  241.35  5249.2  241.28  5270.3  241.88  5372.8  247.36
  5408.5  249.41  5419.9  249.85  5434.4  251.59    5457  251.93  5507.1  255.25
  5534.3  256.39    5578   259.9    5620  261.33  5698.7  262.57  5770.5  265.02
#Mann= 8 ,-1 , 0
  4808.5      .1       0  4963.8     .16       0    4998     .07       0
    5004     .16       0  5145.3     .12       0  5270.3     .16       0
  5372.8     .12       0  5408.5     .16       0
Bank Sta=4998,5004
XS Rating Curve= 0 ,0
Exp/Cntr=0.3,0.1

Type RM Length L Ch R = 1 ,10016   ,455,455,455
BEGIN DESCRIPTION:
PEACH CREEK SOUTH TRIB 7 16.0
END DESCRIPTION:
XS GIS Cut Line= 3
      3588792.11     10176941.65      3588652.91      10176491.9
      3588277.87     10176290.49
#Sta/Elev= 30
  4686.7  252.67  4728.6  249.42  4740.9  247.91  4780.9  245.07  4871.3  240.31
  4885.6  238.21  4936.5  236.59  4974.4  234.63  4979.8  233.88  4997.7   229.6
  5000.5   229.1  5003.7   229.6    5007  231.06  5012.2  230.58  5032.2  232.73
  5053.1  236.69  5077.5  238.49    5095   238.5  5142.7  236.93  5160.8  236.96
    5172  237.69  5203.8  238.29    5254  240.81  5314.1  246.16  5363.6  249.12
  5408.1  250.42  5430.8  251.98  5483.8  253.08  5555.7  255.56  5583.2   255.9
#Mann= 3 ,-1 , 0
  4686.7     .16       0  4997.7     .07       0  5003.7     .16       0
Bank Sta=4997.7,5003.7
XS Rating Curve= 0 ,0
Exp/Cntr=0.3,0.1

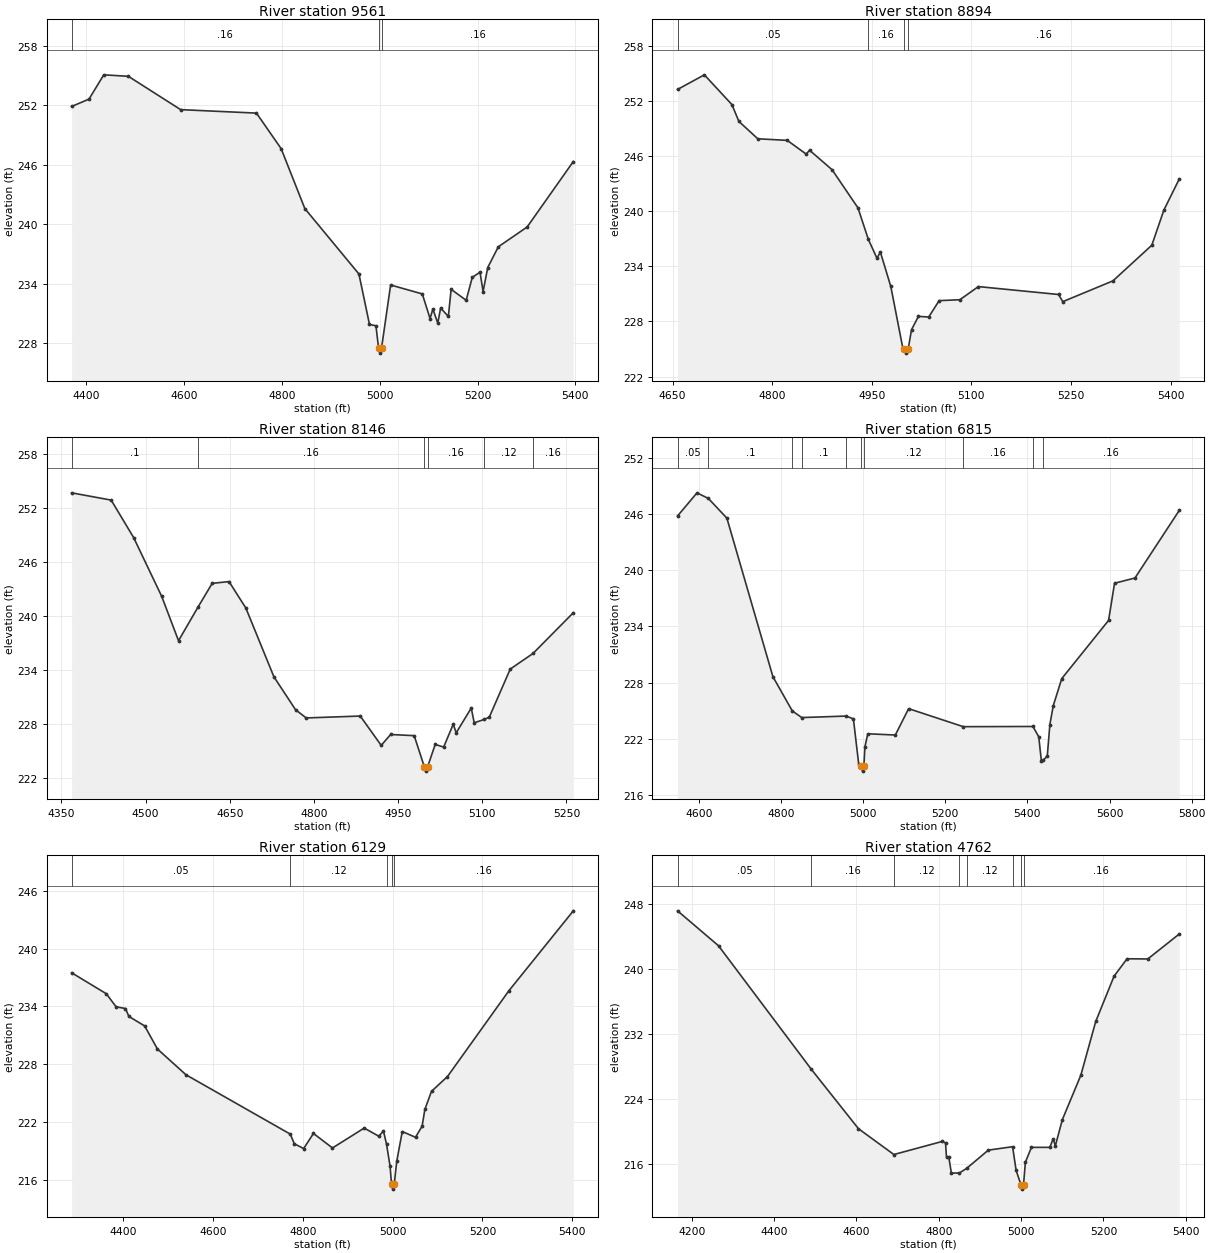
Type RM Length L Ch R = 1 ,9561    ,667,667,667
BEGIN DESCRIPTION:
PEACH CREEK SOUTH TRIB 7 14.0
END DESCRIPTION:
XS GIS Cut Line= 3
      3589153.36     10176996.85      3589092.11     10176478.01
      3588842.08      10176041.6
#Sta/Elev= 30
  4370.3  251.88  4405.8  252.62    4436  255.07  4486.3  254.92  4593.1  251.56
  4748.1  251.21  4798.5  247.63  4846.9  241.59  4957.5  234.99  4979.1   229.9
  4992.3  229.77  4997.7  227.51  5000.5  227.01  5003.7  227.51  5022.3  233.88
    5087  232.98  5102.9   230.5  5108.6  231.45  5118.7  230.04  5124.5  231.55
  5140.3  230.71    5146  233.44  5176.7  232.34  5189.2  234.65    5205  235.17
  5211.3  233.22  5220.8  235.64  5242.4  237.73  5301.4  239.73  5395.7  246.33
#Mann= 3 ,-1 , 0
  4370.3     .16       0  4997.7     .07       0  5003.7     .16       0
Bank Sta=4997.7,5003.7
XS Rating Curve= 0 ,0
Exp/Cntr=0.3,0.1

Type RM Length L Ch R = 1 ,8894    ,748,748,748
BEGIN DESCRIPTION:
PEACH CREEK SOUTH TRIB 7 13.0
END DESCRIPTION:
XS GIS Cut Line= 3
      3589770.98     10176040.51      3589333.47     10175915.51
       3589042.1     10175841.64
#Sta/Elev= 30
  4657.5  253.24  4697.9  254.83  4739.4  251.59  4749.9  249.76  4778.4  247.87
  4822.7   247.7  4851.2  246.21  4856.4  246.62  4890.2  244.51  4929.2  240.36
  4944.9  236.92  4957.8  234.88    4963  235.54  4978.7   231.8  4996.8  225.09
    4999  225.05  5001.7  224.55    5005  225.05  5009.9   227.1  5020.3  228.55
  5035.8  228.48  5051.5  230.26  5082.7  230.36  5110.6  231.79  5231.3  230.93
  5237.7  230.15  5313.2  232.41  5371.8  236.29    5390  240.12  5413.1  243.49
#Mann= 4 ,-1 , 0
  4657.5     .05       0  4944.9     .16       0    4999     .07       0
    5005     .16       0
Bank Sta=4999,5005
XS Rating Curve= 0 ,0
Exp/Cntr=0.3,0.1

Type RM Length L Ch R = 1 ,8146    ,1331,1331,1331
BEGIN DESCRIPTION:
PEACH CREEK SOUTH TRIB 7 11.0
END DESCRIPTION:
XS GIS Cut Line= 3
      3589812.62      10175491.9      3589409.85      10175491.9
      3588942.07     10175341.63
#Sta/Elev= 30
  4368.1  253.66  4438.6  252.85  4478.6  248.69  4528.6  242.16  4558.6  237.23
  4593.2  240.95  4618.6   243.6  4648.6   243.8  4678.6  240.86  4728.6  233.22
  4767.2  229.56  4786.2  228.65  4882.5  228.86  4919.8   225.6  4936.6  226.81
  4978.6  226.68  4996.6  223.24  4999.3  222.74  5002.6  223.24  5016.1  225.71
  5031.1  225.41  5048.2  227.95  5053.5     227  5080.3  229.75  5085.6  228.11
  5103.7  228.49  5112.4  228.73  5149.8  234.08  5190.3  235.81  5262.2  240.34
#Mann= 6 ,-1 , 0
  4368.1      .1       0  4593.2     .16       0  4996.6     .07       0
  5002.6     .16       0  5103.7     .12       0  5190.3     .16       0
Bank Sta=4996.6,5002.6
XS Rating Curve= 0 ,0
Exp/Cntr=0.3,0.1

Type RM Length L Ch R = 1 ,6815    ,686,686,686
BEGIN DESCRIPTION:
PEACH CREEK SOUTH TRIB 7 10.0
END DESCRIPTION:
XS GIS Cut Line= 3
      3589597.32     10174998.82      3589009.73     10174707.36
      3588562.64     10174359.96
#Sta/Elev= 30
  4547.7  245.77  4595.1  248.24  4622.8  247.64  4667.9  245.54    4780  228.64
  4827.2  224.99  4850.3  224.28  4958.4  224.44  4976.1  224.14  4988.9  219.36
  4995.6  219.07  4998.3  218.57  5001.6  219.07  5004.1  221.16  5011.2  222.55
  5078.2  222.42  5110.6  225.23  5243.7  223.31  5413.5  223.33  5427.6  222.23
  5433.9  219.67  5438.4  219.72  5448.4  220.19  5454.7  223.54  5462.9  225.54
  5483.7  228.44  5597.7  234.64  5612.2   238.6    5662  239.16  5769.8  246.36
#Mann= 10 ,-1 , 0
  4547.7     .05       0  4622.8      .1       0  4827.2     .16       0
  4850.3      .1       0  4958.4     .12       0  4995.6     .07       0
  5001.6     .12       0  5243.7     .16       0  5413.5     .12       0
  5438.4     .16       0
Bank Sta=4995.6,5001.6
XS Rating Curve= 0 ,0
Exp/Cntr=0.3,0.1

Type RM Length L Ch R = 1 ,6129    ,1367,1367,1367
BEGIN DESCRIPTION:
PEACH CREEK SOUTH TRIB 7 9.0
END DESCRIPTION:
XS GIS Cut Line= 3
      3589909.89     10174693.32      3589392.11     10174241.64
      3589042.12     10173991.65
#Sta/Elev= 30
  4285.3   237.5  4362.5  235.32  4384.3  233.96  4405.2  233.78  4412.8  232.96
  4447.9  231.97  4476.4  229.57    4540  226.89  4772.2  220.72  4781.1  219.72
    4802  219.22  4823.8  220.79  4866.2  219.28  4936.8  221.35  4969.1  220.51
  4979.8  221.03  4986.5  219.69  4994.5  217.36  4997.7   215.5  5000.4     215
  5003.7   215.5  5009.3   217.9  5021.6  220.99  5051.1  220.39  5065.8  221.55
  5071.9  223.29  5086.7  225.17  5122.3  226.71  5258.7  235.61  5402.5  243.94
#Mann= 5 ,-1 , 0
  4285.3     .05       0  4772.2     .12       0  4986.5     .16       0
  4997.7     .07       0  5003.7     .16       0
Bank Sta=4997.7,5003.7
XS Rating Curve= 0 ,0
Exp/Cntr=0.3,0.1

Type RM Length L Ch R = 1 ,4762    ,914,914,914
BEGIN DESCRIPTION:
PEACH CREEK SOUTH TRIB 7 8.0
END DESCRIPTION:
XS GIS Cut Line= 3
      3590242.11     10174441.64      3590007.08     10173832.18
      3589500.18      10173582.2
#Sta/Elev= 30
  4165.7  247.12  4265.2  242.83  4490.7  227.65  4605.1  220.36  4691.1  217.19
  4808.8   218.8  4816.5  218.62  4818.9  216.86  4824.5  216.86  4830.7  214.91
  4850.2  214.92  4868.3  215.51  4920.5  217.73  4979.4  218.15  4987.9  215.26
  4999.9  213.44  5002.6  212.94  5005.9  213.44  5010.4  216.24  5025.2  218.07
  5069.8  218.07  5077.7   219.1  5083.3  218.27  5100.2  221.47  5145.1  226.92
  5181.3  233.53  5225.9   239.1  5257.4  241.23  5307.8  241.21  5384.1  244.27
#Mann= 8 ,-1 , 0
  4165.7     .05       0  4490.7     .16       0  4691.1     .12       0
  4850.2     .16       0  4868.3     .12       0  4979.4     .16       0
  4999.9     .07       0  5005.9     .16       0
Bank Sta=4999.9,5005.9
XS Rating Curve= 0 ,0
Exp/Cntr=0.3,0.1

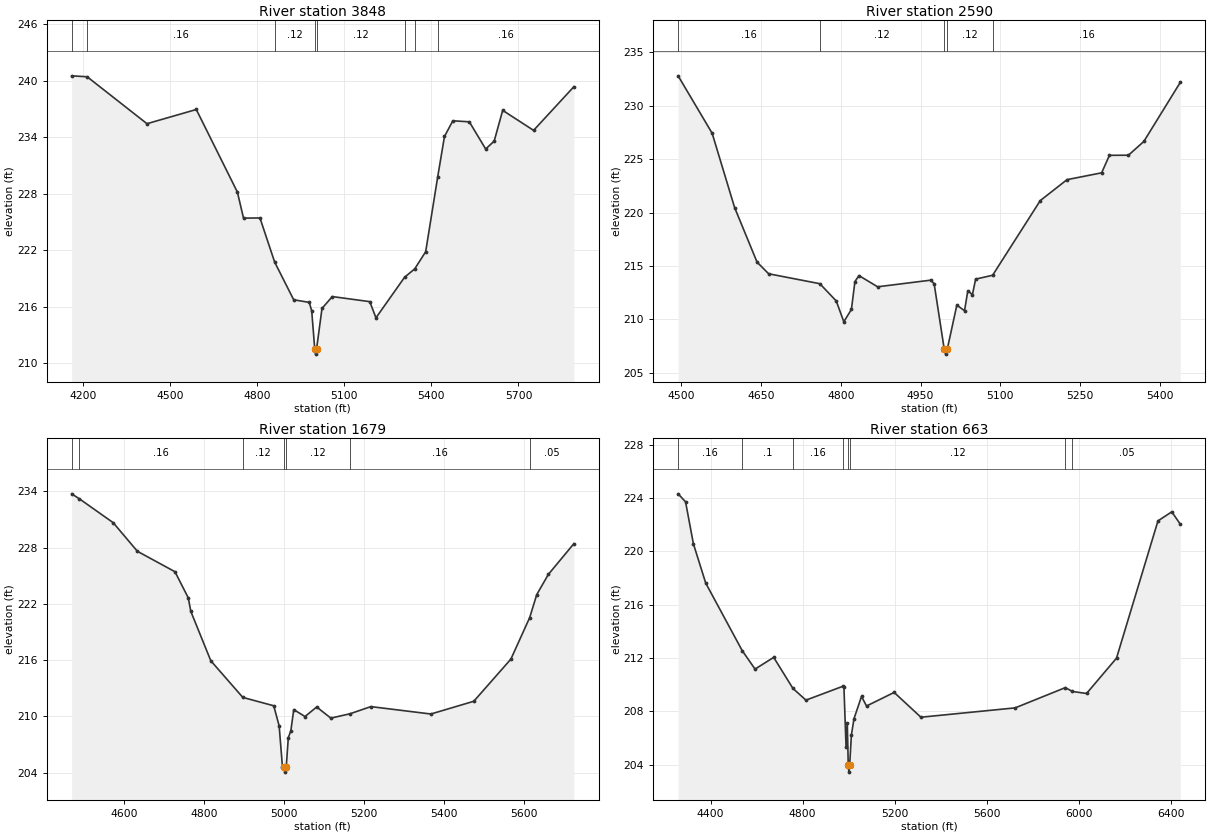
Type RM Length L Ch R = 1 ,3848    ,1258,1258,1258
BEGIN DESCRIPTION:
PEACH CREEK SOUTH TRIB 7 6.0
END DESCRIPTION:
XS GIS Cut Line= 3
      3590846.07     10174184.39      3590316.89     10173632.28
      3589743.79     10172856.47
#Sta/Elev= 30
  4161.4  240.53  4214.8  240.43  4420.8  235.44  4590.6  236.95  4732.1  228.17
  4753.2   225.4  4809.8  225.42  4860.4  220.73    4926  216.72  4979.6  216.44
    4988  215.55  4998.6  211.44  5001.3  210.94  5004.6  211.44  5023.5   215.8
    5059  217.06    5188  216.52  5209.3   214.8    5308  219.12  5342.7     220
  5380.5  221.83  5421.7  229.75  5445.2  234.08    5474  235.75  5530.8  235.64
  5587.1  232.75  5616.4  233.59  5645.7  236.86  5752.1  234.73  5890.7  239.37
#Mann= 8 ,-1 , 0
  4161.4      .1       0  4214.8     .16       0  4860.4     .12       0
  4998.6     .07       0  5004.6     .12       0    5308     .16       0
  5342.7     .12       0  5421.7     .16       0
Bank Sta=4998.6,5004.6
XS Rating Curve= 0 ,0
Exp/Cntr=0.3,0.1

Type RM Length L Ch R = 1 ,2590    ,911,911,911
BEGIN DESCRIPTION:
PEACH CREEK SOUTH TRIB 7 4.0
END DESCRIPTION:
XS GIS Cut Line= 3
      3591042.07     10173291.61      3590642.11     10172941.64
      3590306.37     10172700.72
#Sta/Elev= 30
  4493.9  232.81  4557.9  227.43  4600.2  220.46  4642.4  215.35  4664.2  214.26
  4760.5  213.33  4791.4  211.71  4805.6  209.76  4819.9  210.92  4826.5  213.53
  4834.1  214.09  4869.2  213.04  4968.9  213.66  4975.5  213.34  4994.4  207.23
  4997.1  206.73  5000.4  207.23  5018.2  211.32  5032.7   210.8  5038.9  212.67
  5047.5   212.3  5053.6  213.76  5085.5  214.12  5175.2  221.12  5225.5  223.08
  5290.6  223.72  5305.3  225.36    5341  225.37    5370  226.66  5438.6   232.2
#Mann= 5 ,-1 , 0
  4493.9     .16       0  4760.5     .12       0  4994.4     .07       0
  5000.4     .12       0  5085.5     .16       0
Bank Sta=4994.4,5000.4
XS Rating Curve= 0 ,0
Exp/Cntr=0.3,0.1

Type RM Length L Ch R = 1 ,1679    ,1016,1016,1016
BEGIN DESCRIPTION:
PEACH CREEK SOUTH TRIB 7 2.0
END DESCRIPTION:
XS GIS Cut Line= 3
      3591409.86     10173144.66      3591442.11     10172891.64
      3590642.08     10172291.62
#Sta/Elev= 30
  4468.8  233.74  4488.4   233.2  4572.7  230.66  4633.1  227.61    4727  225.43
  4760.3  222.64  4766.6   221.2  4816.6  215.93  4896.6  212.02  4973.9  211.13
  4987.4  208.98  4995.7   204.6    4999  204.55  5001.7  204.05    5005  204.55
  5010.3  207.73  5016.6  208.46  5023.9  210.72    5052  209.98  5081.2     211
  5116.6  209.81  5164.8  210.28  5216.6  211.04  5366.6  210.25  5473.9  211.61
  5566.6  216.11  5613.6  220.54  5631.2  222.99  5660.3  225.15  5723.9  228.42
#Mann= 7 ,-1 , 0
  4468.8     .05       0  4488.4     .16       0  4896.6     .12       0
    4999     .07       0    5005     .12       0  5164.8     .16       0
  5613.6     .05       0
Bank Sta=4999,5005
XS Rating Curve= 0 ,0
Exp/Cntr=0.3,0.1

Type RM Length L Ch R = 1 ,663     ,0,0,0
BEGIN DESCRIPTION:
PEACH CREEK SOUTH TRIB 7 1.0
END DESCRIPTION:
XS GIS Cut Line= 3
      3592142.11     10173241.65      3591702.12     10172239.44
      3590615.21       10172176.
#Sta/Elev= 30
  4258.7  224.31    4291  223.71  4325.3  220.55  4378.8  217.61  4537.2  212.55
  4593.2  211.16  4674.2  212.04  4757.5  209.72  4814.3  208.83  4974.9  209.87
  4979.5  209.85  4988.8  205.35  4994.2  207.13  4998.4  203.93  5001.1  203.43
  5004.4  203.93  5012.1  206.22  5023.2  207.43    5056  209.11  5077.8  208.39
  5197.9  209.41  5314.3  207.55  5723.9  208.25  5942.1  209.77  5973.3  209.48
  6034.4  209.33  6164.6  211.98  6344.9  222.28    6405  222.96    6442  222.03
#Mann= 8 ,-1 , 0
  4258.7     .16       0  4537.2      .1       0  4757.5     .16       0
  4974.9     .12       0  4998.4     .07       0  5004.4     .12       0
  5942.1     .16       0  5973.3     .05       0
Bank Sta=4998.4,5004.4
XS Rating Curve= 0 ,0
Exp/Cntr=0.3,0.1

Chan Stop Cuts=-1
Use User Specified Reach Order=0
Composite Channel Slope=5