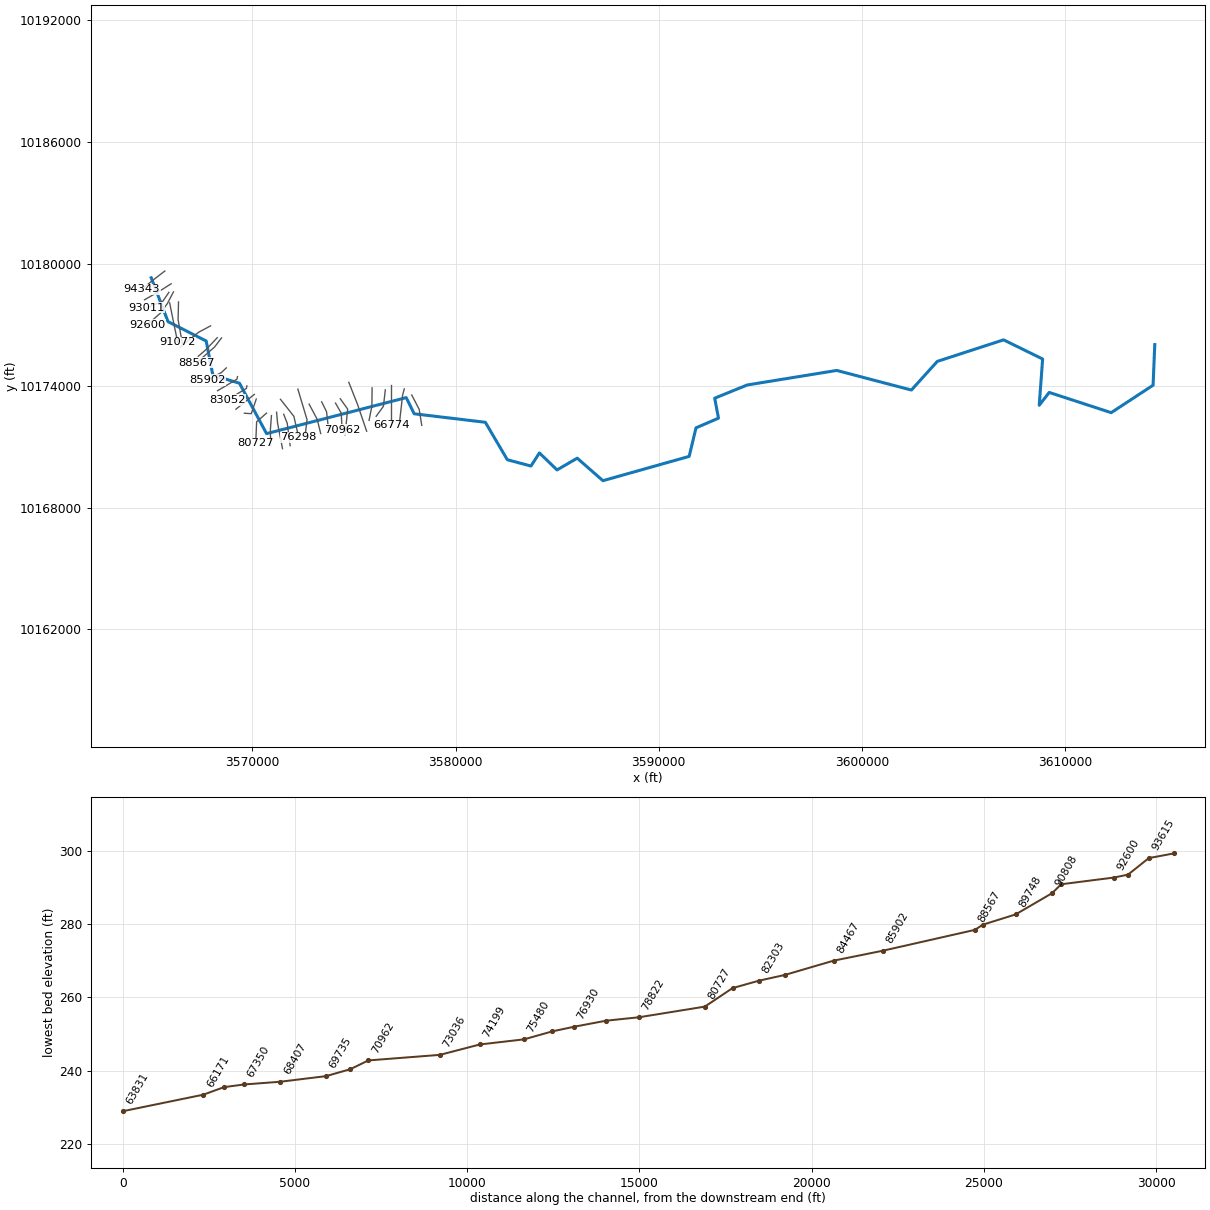
--- PEACH CREEK SOUTH.prj (project) ---

Proj Title=PEACH CREEK SOUTH Base Level Engineering
Current Plan=p01
Default Exp/Contr=0.3,0.1
English Units
Geom File=g01
Flow File=f01
Plan File=p01
Y Axis Title=Elevation
X Axis Title(PF)=Main Channel Distance
X Axis Title(XS)=Station
BEGIN DESCRIPTION:
PEACH CREEK SOUTH
END DESCRIPTION:
DSS Export Rating Curves= 0
DSS Export Rating Curve Sorted= 0
DSS Export Volume Flow Curves= 0
DXF OffsetX= 0
DXF OffsetY= 0
DXF ScaleX= 1
DXF ScaleY= 10

--- PEACH CREEK SOUTH.p01 (plan) ---

Plan Title=Multiple Run
Short Identifier=Multiple
Geom File=g01
Flow File=f01
Subcritical Flow
K Sum by GR= 0
Std Step Tol= 0.01
Critical Tol= 0.01
Num of Std Step Trials= 20
Max Error Tol= 0.3
Flow Tol Ratio= 0.001
Split Flow NTrial= 30
Split Flow Tol= 0.02
Split Flow Ratio= 0.02
Log Output Level= 0
Friction Slope Method= 1
Unsteady Friction Slope Method= 2
Unsteady Bridges Friction Slope Method= 1
Parabolic Critical Depth
Global Vel Dist=  1 , 1 , 1
Global Log Level= 0
CheckData=True
Encroach Param= -1, 0, 0, 0
BEGIN DESCRIPTION:
Multiple Run
END DESCRIPTION:

--- PEACH CREEK SOUTH.f01 (steady flow) ---

Flow Title=Multiple
Program Version=4.10
Number of Profiles= 7
Profile Names=10-year,25-year,50-year,1pct_min,100-year,1pct_plu,500-year
River Rch & RM=PEACH CREEK SOUT,Reach-1         ,94343
     722     974    1179    1044    1411    1909    2028
River Rch & RM=PEACH CREEK SOUT,Reach-1         ,80727
    1322    1834    2261    2034    2751    3721    4088
River Rch & RM=PEACH CREEK SOUT,Reach-1         ,78822
    1322    1834    2261    2034    2751    3721    4088
River Rch & RM=PEACH CREEK SOUT,Reach-1         ,70439
    1559    2175    2693    2432    3289    4448    4922
River Rch & RM=PEACH CREEK SOUT,Reach-1         ,62594
    2139    3021    3769    3427    4635    6268    7032
River Rch & RM=PEACH CREEK SOUT,Reach-1         ,61915
    2139    3021    3769    3427    4635    6268    7032
River Rch & RM=PEACH CREEK SOUT,Reach-1         ,57478
    2287    3231    4033    3668    4960    6708    7528
River Rch & RM=PEACH CREEK SOUT,Reach-1         ,53098
    2259    3182    3963    3596    4864    6577    7348
River Rch & RM=PEACH CREEK SOUT,Reach-1         ,50452
    2259    3182    3963    3596    4864    6577    7348
River Rch & RM=PEACH CREEK SOUT,Reach-1         ,48602
    2585    3664    4582    4175    5646    7635    8596
River Rch & RM=PEACH CREEK SOUT,Reach-1         ,47643
    2585    3664    4582    4175    5646    7635    8596
River Rch & RM=PEACH CREEK SOUT,Reach-1         ,44332
    2913    4144    5195    4743    6415    8676    9810
River Rch & RM=PEACH CREEK SOUT,Reach-1         ,41636
    2916    4137    5179    4720    6383    8632    9725
River Rch & RM=PEACH CREEK SOUT,Reach-1         ,36900
    3155    4491    5632    5143    6955    9406   10638
River Rch & RM=PEACH CREEK SOUT,Reach-1         ,34974
    3155    4491    5632    5143    6955    9406   10638
River Rch & RM=PEACH CREEK SOUT,Reach-1         ,32432
    3370    4801    6025    5503    7442   10064   11387
River Rch & RM=PEACH CREEK SOUT,Reach-1         ,31368
    3370    4801    6025    5503    7442   10064   11387
River Rch & RM=PEACH CREEK SOUT,Reach-1         ,29682
    3610    5156    6483    5932    8022   10849   12319
River Rch & RM=PEACH CREEK SOUT,Reach-1         ,28731
    3643    5188    6510    5944    8039   10872   12291
River Rch & RM=PEACH CREEK SOUT,Reach-1         ,6699
    3973    5652    7086    6461    8738   11817   13324
Boundary for River Rch & Prof#=PEACH CREEK SOUT,Reach-1         , 1
Up Type= 0
Dn Type= 3
Dn Slope=0.005
Boundary for River Rch & Prof#=PEACH CREEK SOUT,Reach-1         , 2
Up Type= 0
Dn Type= 3
Dn Slope=0.005
Boundary for River Rch & Prof#=PEACH CREEK SOUT,Reach-1         , 3
Up Type= 0
Dn Type= 3
Dn Slope=0.005
Boundary for River Rch & Prof#=PEACH CREEK SOUT,Reach-1         , 4
Up Type= 0
Dn Type= 3
Dn Slope=0.005
Boundary for River Rch & Prof#=PEACH CREEK SOUT,Reach-1         , 5
Up Type= 0
Dn Type= 3
Dn Slope=0.005
Boundary for River Rch & Prof#=PEACH CREEK SOUT,Reach-1         , 6
Up Type= 0
Dn Type= 3
Dn Slope=0.005
Boundary for River Rch & Prof#=PEACH CREEK SOUT,Reach-1         , 7
Up Type= 0
Dn Type= 3
Dn Slope=0.005
DSS Import GetInterval= 0
DSS Import GetPeak= 0
DSS Import FillOption= 0

--- PEACH CREEK SOUTH.g01 (geometry) ---

Geom Title=Existing Conditions
Program Version=4.10

River Reach=PEACH CREEK SOUT,Reach-1
Reach XY= 30
       3565023.4     10179307.03      3565848.88     10177150.88
      3567726.08     10176197.87       3568057.5     10174510.53
      3569365.82     10174120.41      3570699.05     10171638.69
      3577571.74     10173411.49      3577963.02     10172615.21
      3581464.67      10172197.3       3582547.4     10170353.78
      3583711.48     10170043.46      3584125.13     10170688.93
      3584994.06     10169853.05      3585986.61     10170431.07
        3587251.     10169323.03        3591495.     10170518.36
      3591832.36     10171922.99      3592937.61     10172400.07
       3592752.5     10173383.04      3594351.58     10174033.39
      3598756.87     10174749.07      3602432.05     10173784.05
      3603707.22     10175194.58      3606967.85      10176253.7
      3608889.87     10175312.03      3608722.56     10173036.04
      3609214.75     10173666.25      3612264.23     10172671.45
      3614325.47      10174021.8      3614408.31     10176021.31

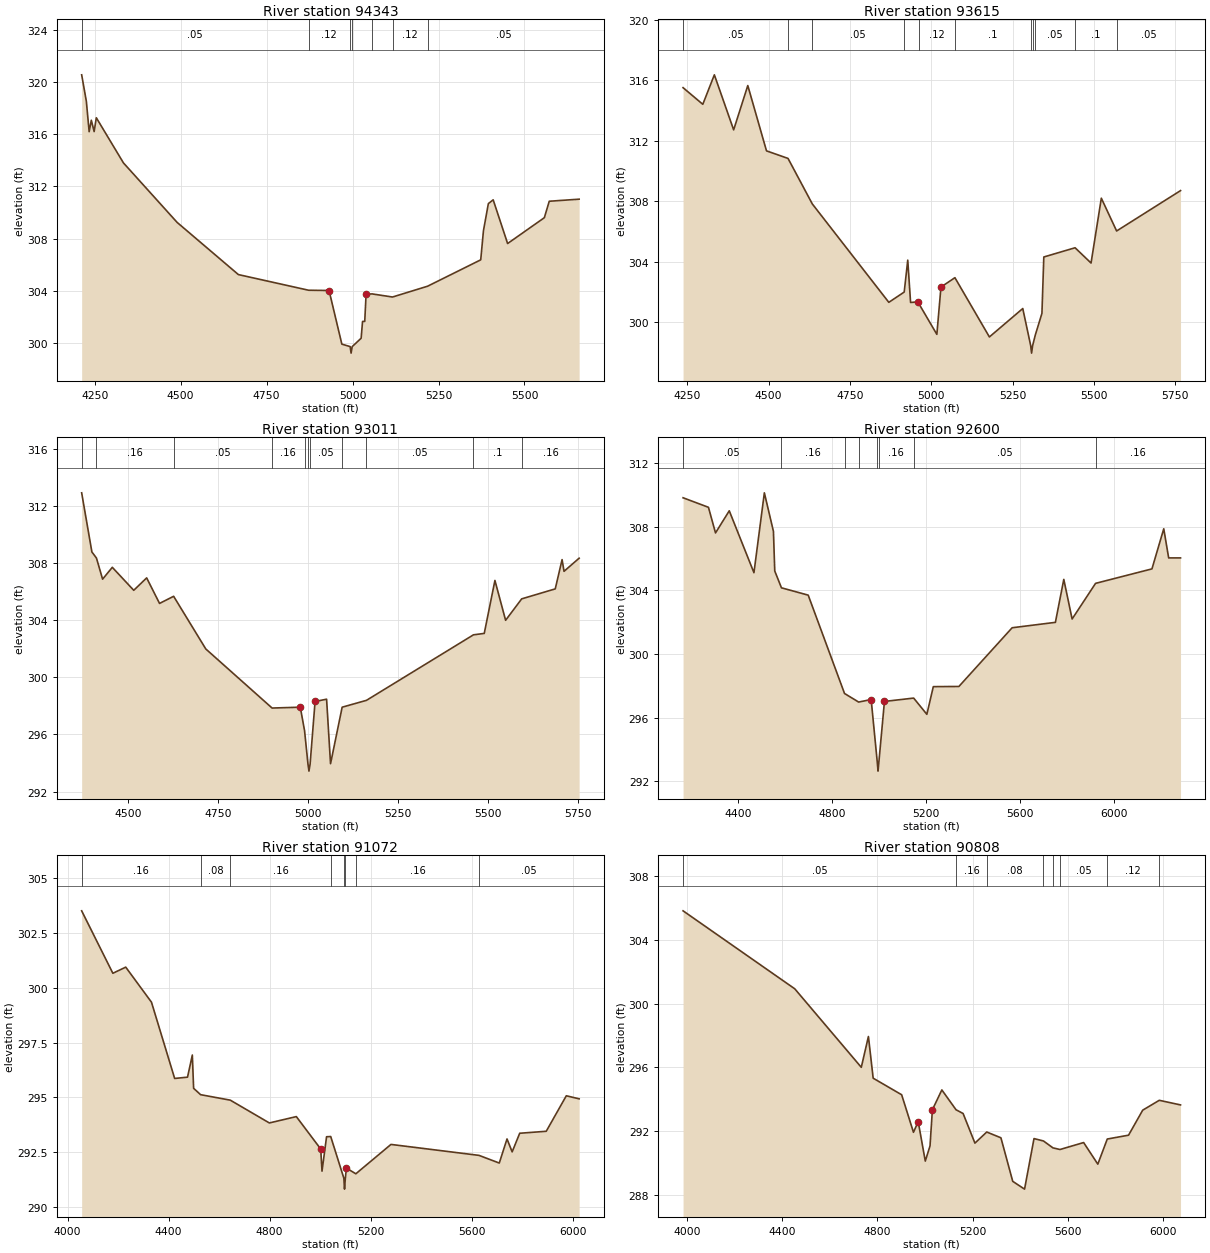
Type RM Length L Ch R = 1 ,94343   ,728,728,728
BEGIN DESCRIPTION:
PEACH CREEK SOUTH 93.0
END DESCRIPTION:
XS GIS Cut Line= 3
      3565692.12     10179641.65      3565042.11     10179141.64
      3564559.64     10178741.63
#Sta/Elev= 30
  4212.2  320.55  4225.8  318.53    4234  316.19  4240.3  317.07  4248.5   316.2
  4254.8  317.26  4333.7   313.8  4489.8  309.24    4668  305.24  4872.2  304.04
  4931.7  304.02  4968.9  299.91    4993  299.72  4995.8  299.22    4999  299.72
    5025  300.36  5029.1  301.65  5035.5  301.65  5039.4  303.73  5056.7  303.76
  5116.2  303.52  5218.4  304.35  5372.8  306.37  5380.7   308.6    5395  310.68
    5409  310.97    5451  307.62  5557.8   309.6  5572.1  310.86    5659  311.02
#Mann= 7 ,-1 , 0
  4212.2     .05       0  4872.2     .12       0    4993     .07       0
    4999     .12       0  5056.7     .05       0  5116.2     .12       0
  5218.4     .05       0
Bank Sta=4931.7,5039.4
XS Rating Curve= 0 ,0
Exp/Cntr=0.3,0.1

Type RM Length L Ch R = 1 ,93615   ,604,604,604
BEGIN DESCRIPTION:
PEACH CREEK SOUTH 92.0
END DESCRIPTION:
XS GIS Cut Line= 3
       3566003.3     10179014.53      3565453.31     10178664.53
      3564692.72     10178227.15
#Sta/Elev= 30
  4236.8   315.5  4297.5   314.4    4333  316.35  4392.3  312.71  4435.8  315.64
  4493.3  311.32  4559.5  310.82  4634.1  307.81  4869.3   301.3  4916.6  301.98
  4927.5  304.09  4936.2  301.29  4959.1  301.33  4961.2  301.23    5017  299.18
  5029.6  302.31  5072.5  302.93  5178.5  299.01  5281.1  300.89  5305.4  298.44
  5308.2  297.94  5311.4  298.44  5319.8  299.15    5340  300.57  5345.8   304.3
  5441.9  304.91    5491   303.9  5522.6  308.19  5569.6  306.02  5766.1  308.69
#Mann= 11 ,-1 , 0
  4236.8     .05       0  4559.5     .16       0  4634.1     .05       0
  4916.6     .07       0  4961.2     .12       0  5072.5      .1       0
  5305.4     .07       0  5311.4      .1       0  5319.8     .05       0
  5441.9      .1       0  5569.6     .05       0
Bank Sta=4959.1,5029.6
XS Rating Curve= 0 ,0
Exp/Cntr=0.3,0.1

Type RM Length L Ch R = 1 ,93011   ,411,411,411
BEGIN DESCRIPTION:
PEACH CREEK SOUTH 90.0
END DESCRIPTION:
XS GIS Cut Line= 3
       3565892.1     10178591.63       3565590.9     10178153.22
      3564799.25     10177840.73
#Sta/Elev= 30
  4371.5  312.93  4399.9  308.79  4412.6  308.36  4429.7  306.88  4456.7  307.71
  4516.3   306.1  4552.2  306.97    4588  305.18  4627.2  305.68  4716.6  301.99
  4900.9  297.85  4979.3  297.91  4991.2  296.26  5000.6  293.93  5003.4  293.43
  5006.6  293.93  5020.4  298.31  5052.4  298.47  5063.4  293.95  5095.7  297.91
  5163.3  298.39  5460.7  302.98  5490.7  303.08  5520.4  306.79  5550.1     304
  5594.8   305.5  5688.1   306.2  5707.1  308.25  5712.5  307.43  5754.5  308.35
#Mann= 11 ,-1 , 0
  4371.5     .05       0  4412.6     .16       0  4627.2     .05       0
  4900.9     .16       0  4991.2     .05       0  5000.6     .03       0
  5006.6     .05       0  5095.7     .16       0  5163.3     .05       0
  5460.7      .1       0  5594.8     .16       0
Bank Sta=4979.3,5020.4
XS Rating Curve= 0 ,0
Exp/Cntr=0.3,0.1

Type RM Length L Ch R = 1 ,92600   ,1528,1528,1528
BEGIN DESCRIPTION:
PEACH CREEK SOUTH 89.0
END DESCRIPTION:
XS GIS Cut Line= 4
      3566115.98     10178614.17      3565824.31     10178051.66
      3565486.69      10177581.4      3564810.39     10176982.19
#Sta/Elev= 30
  4166.5  309.82  4274.5  309.22  4304.5  307.61    4363     309    4468  305.11
  4512.3  310.13  4550.9  307.71  4556.5  305.22    4585  304.16  4698.8   303.7
  4853.3  297.52  4913.4  296.98  4966.6  297.14    4993  293.14  4995.8  292.64
    4999  293.14  5023.1  297.02  5147.4  297.23  5203.5  296.21    5231  297.95
  5339.8  297.96  5566.3  301.65  5750.3  301.99    5786  304.69  5821.4   302.2
  5921.1  304.44    6161  305.35  6211.2  307.87  6232.1  306.04  6282.6  306.04
#Mann= 8 ,-1 , 0
  4166.5     .05       0    4585     .16       0  4853.3     .05       0
  4913.4     .16       0    4993     .07       0    4999     .16       0
  5147.4     .05       0  5921.1     .16       0
Bank Sta=4966.6,5023.1
XS Rating Curve= 0 ,0
Exp/Cntr=0.3,0.1

Type RM Length L Ch R = 1 ,91072   ,266,266,266
BEGIN DESCRIPTION:
PEACH CREEK SOUTH 87.0
END DESCRIPTION:
XS GIS Cut Line= 3
      3565929.93     10178072.77      3566157.64     10176940.55
      3566324.31     10176141.95
#Sta/Elev= 30
  4055.5  303.51  4179.1  300.66  4230.1  300.94  4332.1  299.34  4423.9  295.86
  4474.9  295.92  4493.9  296.93    4499  295.41  4526.7  295.12  4644.3  294.87
    4799  293.83  4905.9  294.12  5002.5  292.64  5007.6  291.63  5025.7   293.2
  5042.1  293.21  5094.1  291.31  5096.8  290.81  5100.1  291.31  5104.2  291.77
  5141.6  291.51  5280.8  292.85  5629.5  292.35  5709.8     292  5740.5   293.1
  5760.9  292.51  5790.8  293.36  5895.9  293.45  5975.4  295.07  6026.2  294.93
#Mann= 8 ,-1 , 0
  4055.5     .16       0  4526.7     .08       0  4644.3     .16       0
  5042.1     .05       0  5094.1     .07       0  5100.1     .05       0
  5141.6     .16       0  5629.5     .05       0
Bank Sta=5002.5,5104.2
XS Rating Curve= 0 ,0
Exp/Cntr=0.3,0.1

Type RM Length L Ch R = 1 ,90808   ,1058,1058,1058
BEGIN DESCRIPTION:
PEACH CREEK SOUTH 86.0
END DESCRIPTION:
XS GIS Cut Line= 4
      3566365.98      10178121.1      3566345.14     10177246.11
      3566539.51     10176156.253566558.45841053  10176050.00359
#Sta/Elev= 30
  3983.2305.81954452.472300.92984732.038296.00764761.991297.9392 4781.96295.3251
4901.666294.28614951.316291.93224971.177   292.65000.967290.12725020.827291.0809
5030.757293.34475070.478294.58955130.059 293.3475159.849  293.11  5209.5291.2528
5259.151291.94965318.732291.58795368.382288.85675418.033288.36915457.754291.5379
5497.475291.38865537.195290.95685566.985290.85355666.287291.28955725.868289.9348
5765.588291.51015854.959291.75065914.541293.32055984.052293.93816073.423 293.649
#Mann= 8 ,-1 , 0
  3983.2     .05       05130.059     .16       05259.151     .08       0
5497.475     .05       05537.195     .03       05566.985     .05       0
5765.588     .12       05984.052     .05       0
Bank Sta=4971.177,5030.757
XS Rating Curve= 0 ,0
Exp/Cntr=0.3,0.1

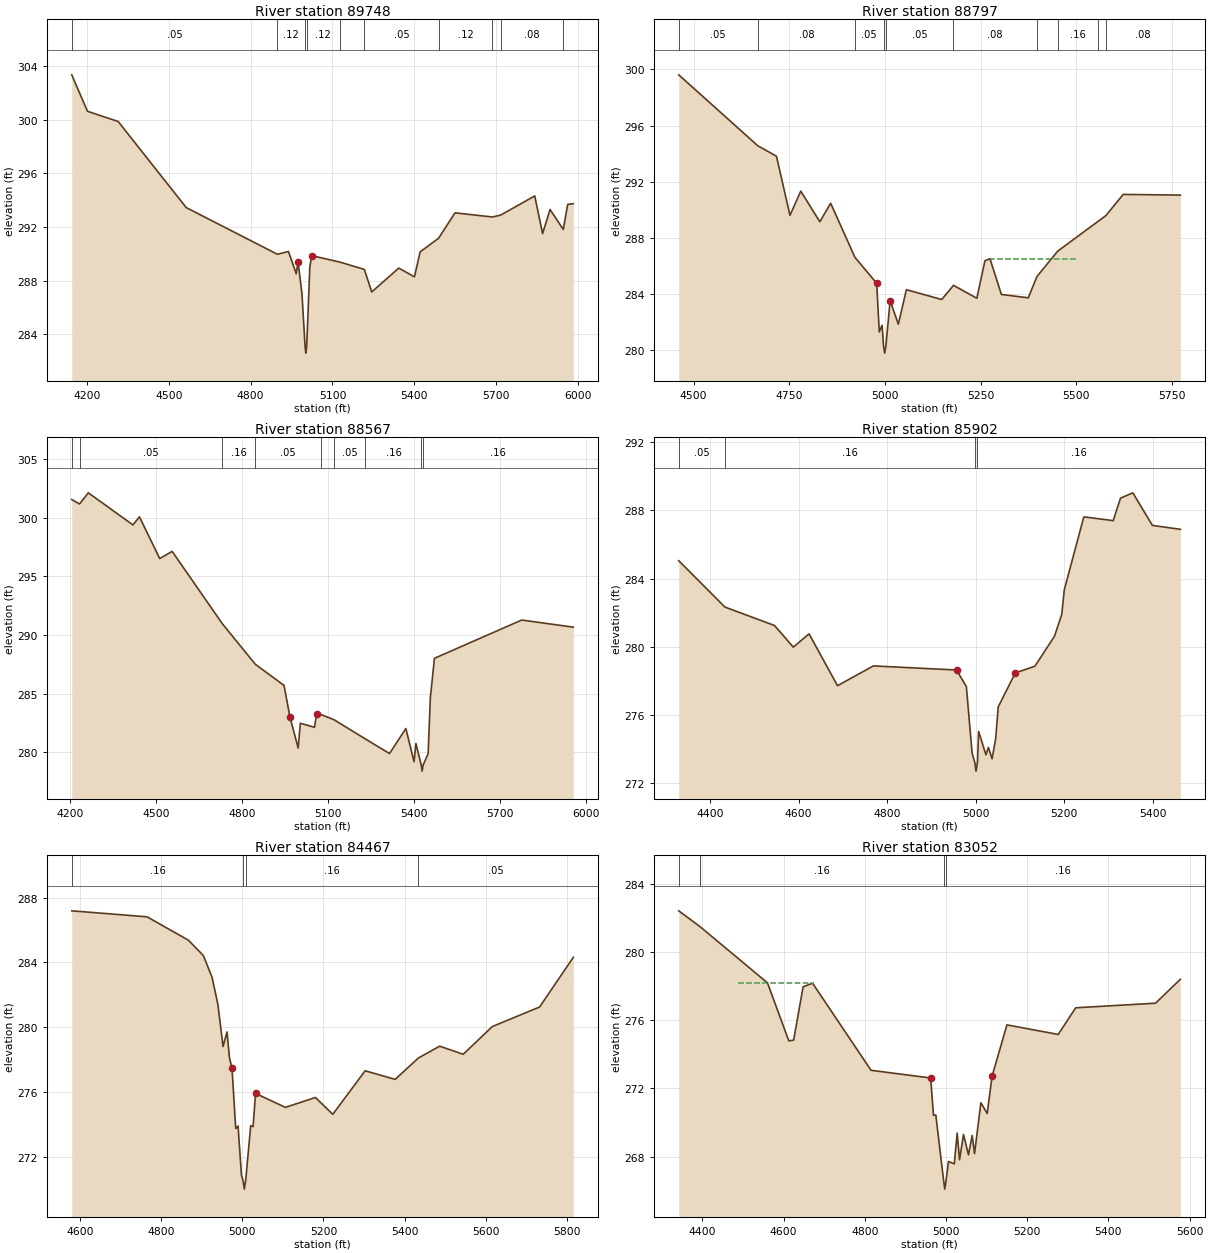
Type RM Length L Ch R = 1 ,89748   ,951,951,951
BEGIN DESCRIPTION:
PEACH CREEK SOUTH 85.0
END DESCRIPTION:
XS GIS Cut Line= 3
      3567942.07     10176941.62      3567344.28      10176622.8
      3566446.08     10175888.42
#Sta/Elev= 30
  4144.7  303.34  4202.4  300.62  4314.7  299.86  4564.3  293.44  4898.2  289.96
  4938.7  290.17  4967.1  288.51  4973.8  289.39  4988.2  287.01  4999.5  283.09
  5002.3  282.59  5005.5  283.09  5016.9  288.99  5023.4  289.86  5126.7  289.38
  5216.7  288.83  5243.7  287.15  5342.8  288.93  5400.2  288.28  5421.1  290.14
    5489  291.16  5548.8  293.05  5685.9  292.74  5715.9  292.88    5841  294.31
  5869.7   291.5  5897.1   293.3  5945.6  291.81  5961.7  293.68  5982.4  293.73
#Mann= 10 ,-1 , 0
  4144.7     .05       0  4898.2     .12       0  4999.5     .07       0
  5005.5     .12       0  5126.7     .16       0  5216.7     .05       0
    5489     .12       0  5685.9     .05       0  5715.9     .08       0
  5945.6     .05       0
Bank Sta=4973.8,5023.4
XS Rating Curve= 0 ,0
Exp/Cntr=0.3,0.1

Type RM Length L Ch R = 1 ,88797   ,230,230,230
BEGIN DESCRIPTION:
PEACH CREEK SOUTH 84.0
END DESCRIPTION:
XS GIS Cut Line= 3
      3568273.21     10176361.57      3567712.55     10175768.16
      3567337.44     10175446.38
#Sta/Elev= 30
  4461.1  299.62  4667.5  294.57  4716.5  293.82  4751.7  289.61    4780  291.33
  4829.8  289.15  4858.1  290.47  4921.4  286.62  4978.3  284.77  4985.1   281.3
  4992.4  281.78  4996.3  280.29  4999.1  279.79  5002.3  280.29  5013.5  283.53
  5034.9  281.85  5055.9  284.31  5148.2  283.61    5179  284.62    5240   283.7
  5261.1  286.37  5274.2  286.52  5304.2  283.97  5374.4  283.73  5397.1  285.25
  5451.4  287.06  5555.3  289.15  5577.2  289.59  5622.5   291.1  5771.7  291.05
#Mann= 10 ,-1 , 0
  4461.1     .05       0  4667.5     .08       0  4921.4     .05       0
  4996.3     .04       0  5002.3     .05       0    5179     .08       0
  5397.1     .05       0  5451.4     .16       0  5555.3     .05       0
  5577.2     .08       0
#XS Ineff= 1 ,-1
  5275.8 5498.52  286.48
Permanent Ineff=
       F
Bank Sta=4978.3,5013.5
XS Rating Curve= 0 ,0
Exp/Cntr=0.3,0.1

Type RM Length L Ch R = 1 ,88567   ,2665,2665,2665
BEGIN DESCRIPTION:
PEACH CREEK SOUTH 83.0
END DESCRIPTION:
XS GIS Cut Line= 3
      3568484.03     10176350.28      3568136.81     10175898.89
      3567247.93     10175121.12
#Sta/Elev= 30
  4206.4  301.57  4233.7  301.19  4264.2  302.14    4420   299.4  4442.7  300.09
  4513.4  296.53  4556.9  297.14  4731.8  290.97  4846.8  287.51  4947.3   285.7
  4968.2  282.97  4996.6  280.35  5004.2  282.47  5053.6  282.12  5061.2  283.26
  5075.3  283.22  5122.4  282.76  5231.6  281.12  5315.5  279.88  5372.5  282.02
    5401  279.18  5407.6  280.74  5426.4  278.88  5429.2  278.38  5432.4  278.88
  5450.3  279.88  5457.9  284.64  5472.2  288.01  5776.8  291.28    5957  290.67
#Mann= 9 ,-1 , 0
  4206.4      .1       0  4233.7     .05       0  4731.8     .16       0
  4846.8     .05       0  5075.3     .12       0  5122.4     .05       0
  5231.6     .16       0  5426.4     .03       0  5432.4     .16       0
Bank Sta=4968.2,5061.2
XS Rating Curve= 0 ,0
Exp/Cntr=0.3,0.1

Type RM Length L Ch R = 1 ,85902   ,1435,1435,1435
BEGIN DESCRIPTION:
PEACH CREEK SOUTH 83.1
END DESCRIPTION:
XS GIS Cut Line= 3
      3568715.99     10174873.86      3568476.47     10174645.08
      3567764.58     10174275.79
#Sta/Elev= 30
  4329.2  285.05  4433.6  282.33  4545.6  281.25  4588.1  279.98  4623.6  280.76
  4687.9  277.72    4769  278.88  4956.8  278.64    4979  277.67    4992  273.76
  4998.1  273.21  5000.8  272.71  5004.1  273.21  5006.7  275.04  5023.2  273.67
  5028.8   274.1  5037.1  273.44  5045.3  274.63    5051  276.48  5089.6  278.47
  5133.8  278.86  5178.1  280.62  5194.6  281.91  5200.2  283.34  5244.4  287.62
  5310.8   287.4  5327.3  288.72  5355.1  289.03  5399.3  287.12  5462.4  286.89
#Mann= 4 ,-1 , 0
  4329.2     .05       0  4433.6     .16       0  4998.1     .07       0
  5004.1     .16       0
Bank Sta=4956.8,5089.6
XS Rating Curve= 0 ,0
Exp/Cntr=0.3,0.1

Type RM Length L Ch R = 1 ,84467   ,1415,1415,1415
BEGIN DESCRIPTION:
PEACH CREEK SOUTH 82.0
END DESCRIPTION:
XS GIS Cut Line= 3
      3569267.99     10174444.93      3569241.94     10174319.89
      3568288.84     10173752.19
#Sta/Elev= 30
  4579.2  287.18  4764.9  286.81  4866.7  285.37  4903.7  284.42  4925.2  283.08
  4939.5  281.42  4952.4   278.8  4962.2   279.7    4968  278.13  4974.5  277.45
  4983.6  273.73  4989.4  273.89  4997.7  270.86    5002  270.49  5004.7  269.99
    5008  270.49  5020.6  273.91  5026.4  273.85  5032.6   275.9  5106.2  275.04
  5180.2  275.65    5223  274.61  5302.8   277.3  5376.8  276.77  5434.2  278.09
  5486.6  278.82  5544.8  278.32  5616.3  280.03  5733.1  281.24  5816.3  284.31
#Mann= 4 ,-1 , 0
  4579.2     .16       0    5002     .07       0    5008     .16       0
  5434.2     .05       0
Bank Sta=4974.5,5032.6
XS Rating Curve= 0 ,0
Exp/Cntr=0.3,0.1

Type RM Length L Ch R = 1 ,83052   ,749,749,749
BEGIN DESCRIPTION:
PEACH CREEK SOUTH 82.1
END DESCRIPTION:
XS GIS Cut Line= 3
      3569731.69     10173988.02      3569705.65       10173863.
      3568753.63     10173295.95
#Sta/Elev= 30
  4341.5   282.4  4393.7  281.48  4560.2  278.18  4612.8  274.78  4624.6  274.83
  4647.9  277.95  4671.2  278.16  4815.3  273.06  4962.2  272.61  4969.1  270.43
  4974.9  270.44  4994.1   266.6  4996.9   266.1  5000.1   266.6  5006.1  267.72
  5020.4  267.58  5027.5  269.38  5033.3  267.82  5043.1   269.3  5055.3  268.11
  5064.5  269.24  5070.3  268.18  5085.9  271.16  5101.5  270.53  5113.5  272.71
  5150.1  275.72  5276.4  275.16  5319.5  276.72  5516.2  276.99  5577.3  278.39
#Mann= 4 ,-1 , 0
  4341.5     .05       0  4393.7     .16       0  4994.1     .07       0
  5000.1     .16       0
#XS Ineff= 1 ,-1
 4487.16  4671.7  278.17
Permanent Ineff=
       F
Bank Sta=4962.2,5113.5
XS Rating Curve= 0 ,0
Exp/Cntr=0.3,0.1

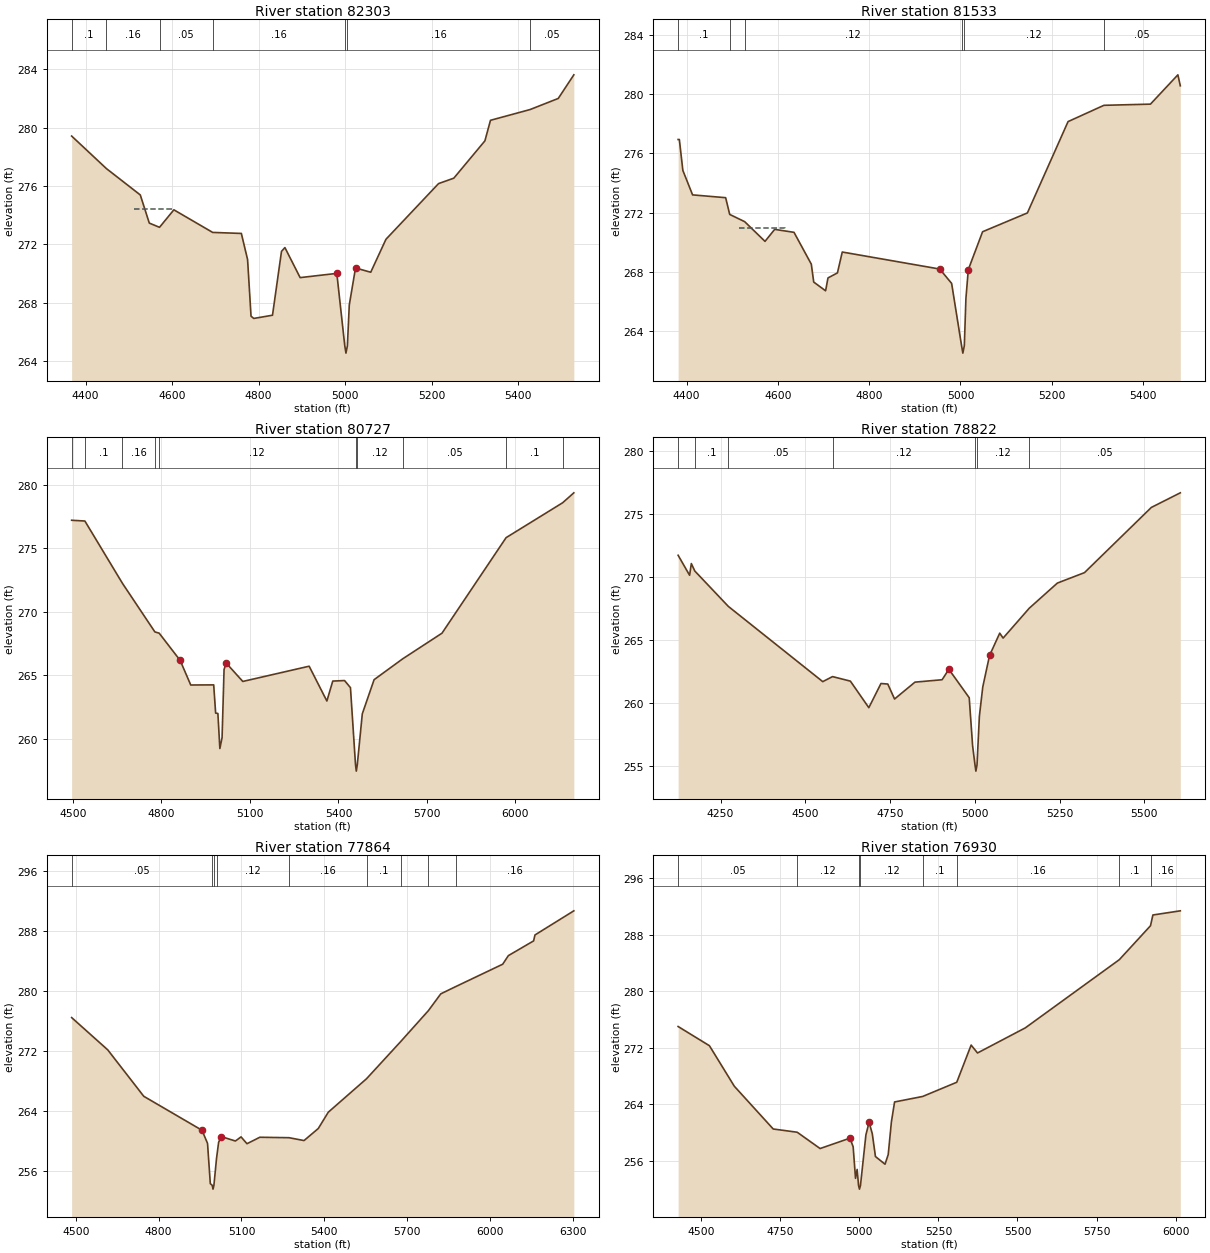
Type RM Length L Ch R = 1 ,82303   ,770,770,770
BEGIN DESCRIPTION:
PEACH CREEK SOUTH 80.0
END DESCRIPTION:
XS GIS Cut Line= 3
      3570096.13     10173569.91      3569502.76     10173091.93
      3569192.09     10172841.63
#Sta/Elev= 30
  4367.8  279.43  4448.1   277.2  4526.5  275.39  4547.3  273.46  4570.9  273.17
  4604.1  274.37  4693.8  272.82  4760.1  272.75  4774.5  270.96  4782.5  267.07
  4788.9  266.92  4832.1  267.14  4852.9  271.52  4860.8  271.78    4896  269.72
  4980.8  270.01  4999.2  265.04  5001.9  264.54  5005.2  265.04  5009.6  267.84
    5024  270.38  5059.2  270.09  5094.4  272.35    5216  276.17  5251.2  276.54
  5323.1   279.1    5336  280.51  5427.7  281.25  5492.7  282.01  5528.7  283.63
#Mann= 7 ,-1 , 0
  4367.8      .1       0  4448.1     .16       0  4570.9     .05       0
  4693.8     .16       0  4999.2     .07       0  5005.2     .16       0
  5427.7     .05       0
#XS Ineff= 1 ,-1
 4511.02  4603.3  274.46
Permanent Ineff=
       F
Bank Sta=4980.8,5024
XS Rating Curve= 0 ,0
Exp/Cntr=0.3,0.1

Type RM Length L Ch R = 1 ,81533   ,806,806,806
BEGIN DESCRIPTION:
PEACH CREEK SOUTH 79.0
END DESCRIPTION:
XS GIS Cut Line= 3
      3570192.11     10173341.65      3569945.07     10172621.97
      3569606.81     10172642.79
#Sta/Elev= 30
  4381.6  276.94  4384.3  276.94    4392  274.85  4413.3   273.2  4485.7  273.01
  4494.6  271.88  4527.4  271.39  4571.9  270.06  4593.1  270.87  4635.4  270.67
  4673.3  268.52  4678.6  267.31  4704.6  266.72  4709.8  267.59  4730.5  267.93
  4741.1  269.34  4954.6  268.19  4980.6  267.22  5002.4  263.01  5005.2  262.51
  5008.4  263.01  5011.9   266.2  5017.1  268.15  5048.4  270.71  5146.5  271.98
  5235.6  278.15  5314.1  279.25    5416  279.33  5476.1  281.31  5481.4  280.57
#Mann= 6 ,-1 , 0
  4381.6      .1       0  4494.6     .16       0  4527.4     .12       0
  5002.4     .07       0  5008.4     .12       0  5314.1     .05       0
#XS Ineff= 1 ,-1
    4515 4615.23  270.95
Permanent Ineff=
       F
Bank Sta=4954.6,5017.1
XS Rating Curve= 0 ,0
Exp/Cntr=0.3,0.1

Type RM Length L Ch R = 1 ,80727   ,1905,1905,1905
BEGIN DESCRIPTION:
PEACH CREEK SOUTH 78.0
END DESCRIPTION:
XS GIS Cut Line= 3
      3570695.05       10172648.      3570210.69     10172220.93
      3570163.88     10171165.12
#Sta/Elev= 30
  4495.5  277.21  4540.4  277.15  4667.6  272.25  4777.7  268.42  4792.3  268.32
  4863.3  266.18  4899.3  264.24  4977.1  264.25  4983.7  262.03  4991.3     262
    4998  259.24  5005.5   260.1  5012.2  265.45  5019.4  265.97  5075.8  264.52
  5300.7  265.72  5360.8  262.98  5380.8  264.55  5420.8  264.59  5440.8  264.03
  5457.9  257.96  5460.6  257.46  5463.9  257.96  5480.9  261.97  5520.9  264.66
  5617.8   266.3  5751.1  268.32  5968.4  275.84  6160.3  278.59  6198.1  279.37
#Mann= 10 ,-1 , 0
  4495.5     .16       0  4540.4      .1       0  4667.6     .16       0
  4777.7      .1       0  4792.3     .12       0  5457.9     .07       0
  5463.9     .12       0  5617.8     .05       0  5968.4      .1       0
  6160.3     .05       0
Bank Sta=4863.3,5019.4
XS Rating Curve= 0 ,0
Exp/Cntr=0.3,0.1

Type RM Length L Ch R = 1 ,78822   ,958,958,958
BEGIN DESCRIPTION:
PEACH CREEK SOUTH 77.0
END DESCRIPTION:
XS GIS Cut Line= 3
      3570939.86     10172528.24      3570887.78     10171845.93
      3570898.19     10171049.09
#Sta/Elev= 30
  4124.9  271.72  4158.8  270.13  4163.9  271.06  4174.1  270.47  4272.9  267.66
  4551.5  261.68  4580.4  262.08    4633  261.72  4687.4  259.61  4723.2  261.53
  4743.3  261.49  4763.3   260.3  4823.5  261.64  4903.5  261.83  4923.5  262.66
  4983.5   260.4  4993.5  256.59  5000.5  255.07  5003.2  254.57  5006.5  255.07
  5013.5  258.94  5023.5  261.26  5043.5  263.76  5073.5  265.53  5083.5  265.14
  5160.5  267.51  5243.5  269.51  5323.5  270.34  5520.7  275.52  5606.1  276.68
#Mann= 7 ,-1 , 0
  4124.9     .16       0  4174.1      .1       0  4272.9     .05       0
  4580.4     .12       0  5000.5     .07       0  5006.5     .12       0
  5160.5     .05       0
Bank Sta=4923.5,5043.5
XS Rating Curve= 0 ,0
Exp/Cntr=0.3,0.1

Type RM Length L Ch R = 1 ,77864   ,934,934,934
BEGIN DESCRIPTION:
PEACH CREEK SOUTH 76.0
END DESCRIPTION:
XS GIS Cut Line= 3
       3571192.1     10172691.67      3571242.11     10172141.64
      3571484.04     10170898.86
#Sta/Elev= 30
  4485.2  276.45  4615.8  272.16  4746.3  265.98  4957.2  261.46  4977.2  259.72
  4987.3  254.36  4994.3  254.13  4997.1  253.63  5000.3  254.13  5009.8  257.72
  5017.4  259.86  5027.4  260.61  5078.2  260.03  5098.6  260.58    5120  259.67
  5166.6  260.53  5272.6  260.47  5326.6  260.09  5378.2  261.69  5414.4  263.86
  5553.1  268.32  5677.7   273.3  5777.1  277.38  5821.9  279.61  5876.4  280.58
  6046.1  283.55  6066.5  284.69  6157.9  286.65  6162.9  287.44  6303.6  290.65
#Mann= 9 ,-1 , 0
  4485.2     .05       0  4994.3     .03       0  5000.3     .05       0
  5009.8     .12       0  5272.6     .16       0  5553.1      .1       0
  5677.7     .16       0  5777.1      .1       0  5876.4     .16       0
Bank Sta=4957.2,5027.4
XS Rating Curve= 0 ,0
Exp/Cntr=0.3,0.1

Type RM Length L Ch R = 1 ,76930   ,632,632,632
BEGIN DESCRIPTION:
PEACH CREEK SOUTH 75.0
END DESCRIPTION:
XS GIS Cut Line= 3
      3571542.11     10172591.63       3571715.9     10172148.01
       3571858.9      10171045.7
#Sta/Elev= 30
    4427  275.01    4526  272.29  4604.7  266.55  4727.7  260.49  4803.6  260.03
    4876  257.72  4970.4  259.19  4980.5  257.97    4988   253.5  4993.1  254.76
  4997.6  252.47  5000.4  251.97  5003.6  252.47  5020.8  259.65  5030.9  261.44
    5041  259.82    5051  256.59  5081.3   255.5  5091.4  256.87  5101.5  261.52
  5111.5  264.32  5200.4   265.1  5308.1  267.11  5353.6  272.38  5373.7  271.26
    5525  274.82  5822.2  284.48  5920.8  289.29  5928.3  290.81    6015   291.4
#Mann= 8 ,-1 , 0
    4427     .05       0  4803.6     .12       0  4997.6     .07       0
  5003.6     .12       0  5200.4      .1       0  5308.1     .16       0
  5822.2      .1       0  5920.8     .16       0
Bank Sta=4970.4,5030.9
XS Rating Curve= 0 ,0
Exp/Cntr=0.3,0.1

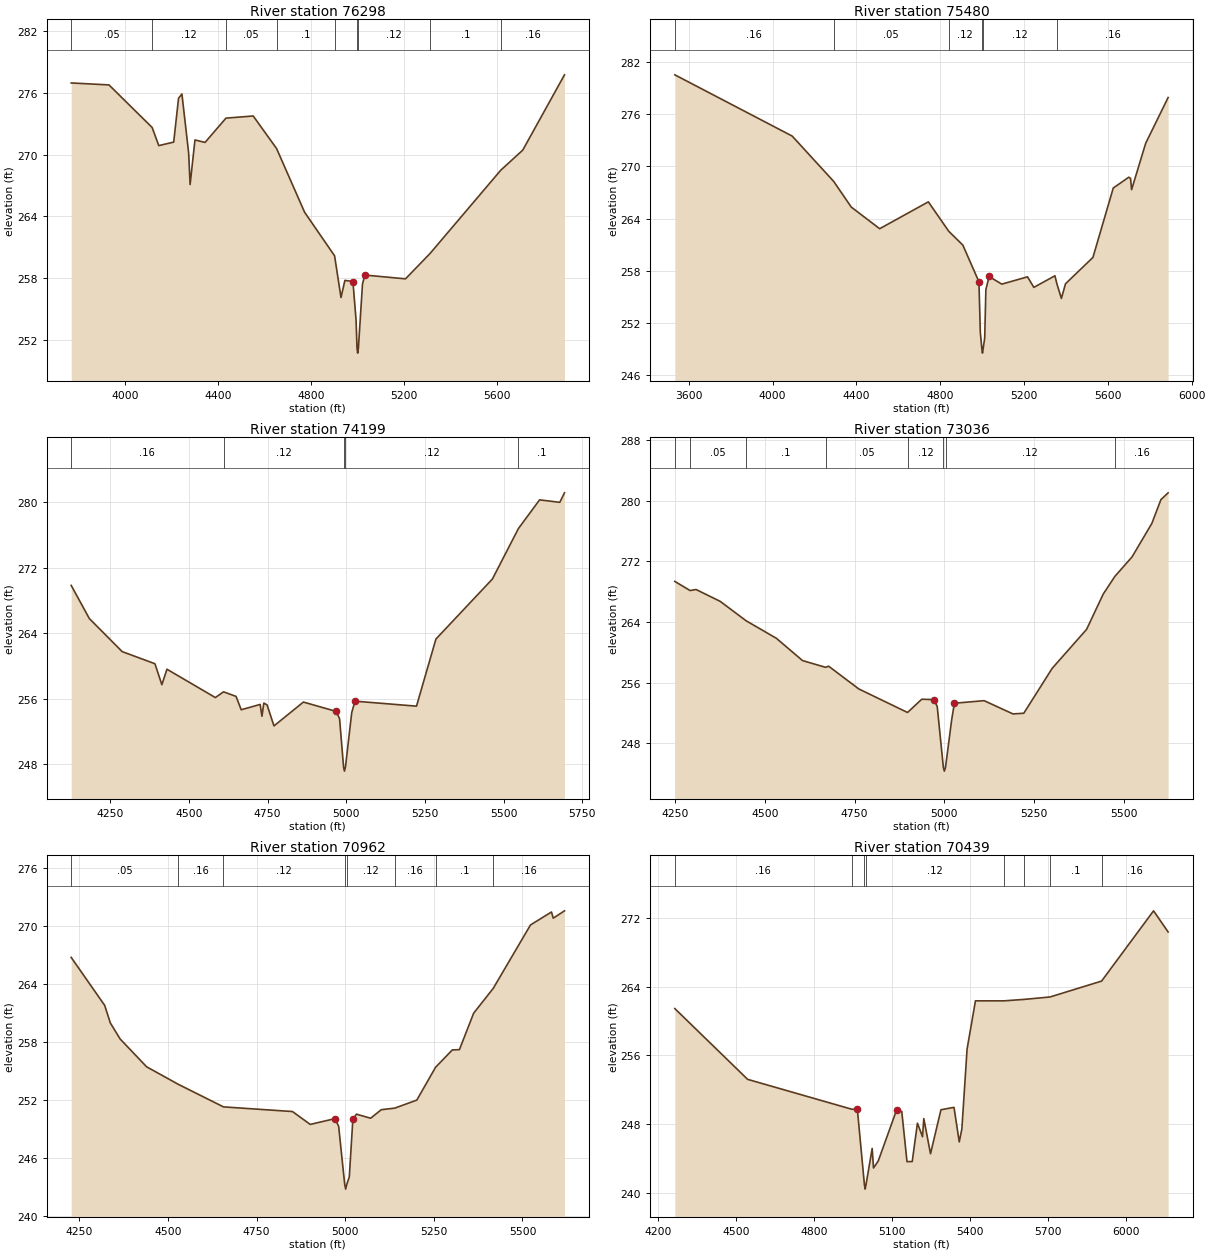
Type RM Length L Ch R = 1 ,76298   ,818,818,818
BEGIN DESCRIPTION:
PEACH CREEK SOUTH 73.0
END DESCRIPTION:
XS GIS Cut Line= 3
      3571382.01     10173329.04      3572042.44     10172490.97
      3572278.29     10171466.18
#Sta/Elev= 30
  3769.7  276.97  3931.9  276.78  4117.4  272.64  4145.8  270.88  4209.9  271.22
  4230.7  275.48  4245.2   275.9    4274  270.19  4280.4   267.1  4301.2  271.43
  4344.5  271.19  4434.4  273.55  4551.4  273.76  4651.9  270.59  4772.2   264.4
  4900.9  260.17  4928.4  256.12  4945.2  257.78  4979.7  257.67  4993.2   253.9
  4997.2  251.21    5000  250.71  5003.2  251.21  5020.7  257.42  5030.9   258.3
  5205.4  257.93  5310.7  260.39  5614.6  268.49    5709  270.44  5888.3  277.76
#Mann= 9 ,-1 , 0
  3769.7     .05       0  4117.4     .12       0  4434.4     .05       0
  4651.9      .1       0  4900.9     .12       0  4997.2     .07       0
  5003.2     .12       0  5310.7      .1       0  5614.6     .16       0
Bank Sta=4979.7,5030.9
XS Rating Curve= 0 ,0
Exp/Cntr=0.3,0.1

Type RM Length L Ch R = 1 ,75480   ,1281,1281,1281
BEGIN DESCRIPTION:
PEACH CREEK SOUTH 72.0
END DESCRIPTION:
XS GIS Cut Line= 3
      3572239.25     10173828.11      3572689.86      10172330.3
      3572596.28     10171545.28
#Sta/Elev= 30
  3532.9  280.53  4093.1  273.49  4291.6  268.27  4375.1  265.33  4510.8  262.84
  4743.1  265.93  4840.4  262.55  4907.7  260.96  4984.6  256.74  4991.2   250.9
  4998.6  249.04  5001.4  248.54  5004.6  249.04  5012.1  250.28  5017.7  255.84
    5033  257.35  5093.7  256.47  5216.5  257.31  5246.7   256.1  5347.4  257.43
  5357.2  256.46  5378.2  254.83  5397.8  256.51  5528.7  259.54  5625.8  267.52
  5699.9  268.76  5708.3  268.63  5713.3  267.33  5780.5  272.66  5887.6  277.92
#Mann= 6 ,-1 , 0
  3532.9     .16       0  4291.6     .05       0  4840.4     .12       0
  4998.6     .07       0  5004.6     .12       0  5357.2     .16       0
Bank Sta=4984.6,5033
XS Rating Curve= 0 ,0
Exp/Cntr=0.3,0.1

Type RM Length L Ch R = 1 ,74199   ,1163,1163,1163
BEGIN DESCRIPTION:
PEACH CREEK SOUTH 70.0
END DESCRIPTION:
XS GIS Cut Line= 3
       3572792.1     10173091.66      3573192.11     10172341.64
      3573361.27      10171644.7
#Sta/Elev= 30
  4126.1  269.82  4183.8  265.77    4288  261.74  4392.1  260.26  4414.1   257.7
  4430.3  259.59  4584.1  256.13    4610  256.83  4649.9  256.27  4666.2  254.64
  4726.4  255.29  4732.1  253.85  4738.1  255.46  4748.4  255.23  4770.3  252.67
  4863.8  255.58    4968  254.44  4978.7  253.55  4991.4  247.65  4994.2  247.15
  4997.4  247.65  5017.3  254.28  5027.6  255.69  5223.1  255.08  5284.8  263.27
  5464.3   270.6  5546.8  276.75  5614.1  280.26  5678.3  279.96  5693.3  281.12
#Mann= 5 ,-1 , 0
  4126.1     .16       0    4610     .12       0  4991.4     .07       0
  4997.4     .12       0  5546.8      .1       0
Bank Sta=4968,5027.6
XS Rating Curve= 0 ,0
Exp/Cntr=0.3,0.1

Type RM Length L Ch R = 1 ,73036   ,2074,2074,2074
BEGIN DESCRIPTION:
PEACH CREEK SOUTH 69.0
END DESCRIPTION:
XS GIS Cut Line= 3
      3573408.63     10173205.27       3573651.2     10172716.62
       3573742.1     10171891.66
#Sta/Elev= 30
  4248.8  269.35  4291.4  268.14    4308  268.28  4375.2  266.72  4447.7  264.15
    4532  261.84  4604.9   258.9  4669.2  258.01  4677.7  258.16  4761.7  255.16
  4897.7  252.05  4937.4   253.8  4970.4  253.75  4980.4  252.87  4997.6  244.81
  5000.3  244.31  5003.6  244.81  5020.7  251.07  5028.3  253.27  5111.2  253.61
  5191.7  251.86  5221.9  251.95  5301.1  257.88    5397  263.02  5443.2  267.66
  5475.8  270.01  5523.7  272.58  5578.9     277  5604.2  280.14  5624.3  281.04
#Mann= 8 ,-1 , 0
  4248.8     .16       0  4291.4     .05       0  4447.7      .1       0
  4669.2     .05       0  4897.7     .12       0  4997.6     .07       0
  5003.6     .12       0  5475.8     .16       0
Bank Sta=4970.4,5028.3
XS Rating Curve= 0 ,0
Exp/Cntr=0.3,0.1

Type RM Length L Ch R = 1 ,70962   ,523,523,523
BEGIN DESCRIPTION:
PEACH CREEK SOUTH 67.0
END DESCRIPTION:
XS GIS Cut Line= 3
      3574092.11     10173141.64      3574371.26     10172650.89
      3574418.98     10171825.86
#Sta/Elev= 30
  4227.5  266.72  4321.9  261.77  4337.8  259.96  4365.5   258.3  4440.1  255.43
  4528.9  253.63  4656.9  251.29  4851.4  250.81  4901.5  249.48  4971.6  250.08
  4981.7  249.28  4998.7   243.3  5001.4   242.8  5004.7   243.3  5011.7  244.07
  5021.7  249.99  5031.7  250.54  5071.8  250.12  5101.9     251  5139.8  251.16
    5202  251.99    5255  255.38  5302.2  257.17  5322.2   257.2  5362.3  260.96
  5417.8  263.54  5522.6  270.07  5581.8  271.41  5586.8  270.77  5618.5  271.53
#Mann= 8 ,-1 , 0
  4227.5     .05       0  4528.9     .16       0  4656.9     .12       0
  4998.7     .07       0  5004.7     .12       0  5139.8     .16       0
    5255      .1       0  5417.8     .16       0
Bank Sta=4971.6,5021.7
XS Rating Curve= 0 ,0
Exp/Cntr=0.3,0.1

Type RM Length L Ch R = 1 ,70439   ,704,704,704
BEGIN DESCRIPTION:
PEACH CREEK SOUTH 66.0
END DESCRIPTION:
XS GIS Cut Line= 3
      3574325.28     10173356.34       3574690.7     10172845.95
      3574561.29     10171582.08
#Sta/Elev= 30
  4264.3  261.43  4544.5  253.19  4945.4  249.71  4966.7  249.71  4993.9  240.91
  4996.6  240.41  4999.9  240.91  5023.7  245.15  5028.8  242.87  5047.1  243.69
  5117.5  249.61  5137.6  249.45  5157.7  243.61  5177.8  243.62  5197.9  248.09
  5217.4  246.51  5222.4  248.62  5248.2  244.53  5288.4  249.65  5338.6  249.93
  5358.8  245.91  5368.8   247.4  5388.9  256.71  5421.1  262.33  5531.8  262.33
  5608.9   262.5  5708.1  262.78  5906.5  264.63  6106.5  272.81  6162.5  270.35
#Mann= 8 ,-1 , 0
  4264.3     .16       0  4945.4     .12       0  4993.9     .07       0
  4999.9     .12       0  5531.8      .1       0  5608.9     .12       0
  5708.1      .1       0  5906.5     .16       0
Bank Sta=4966.7,5117.5
XS Rating Curve= 0 ,0
Exp/Cntr=0.3,0.1

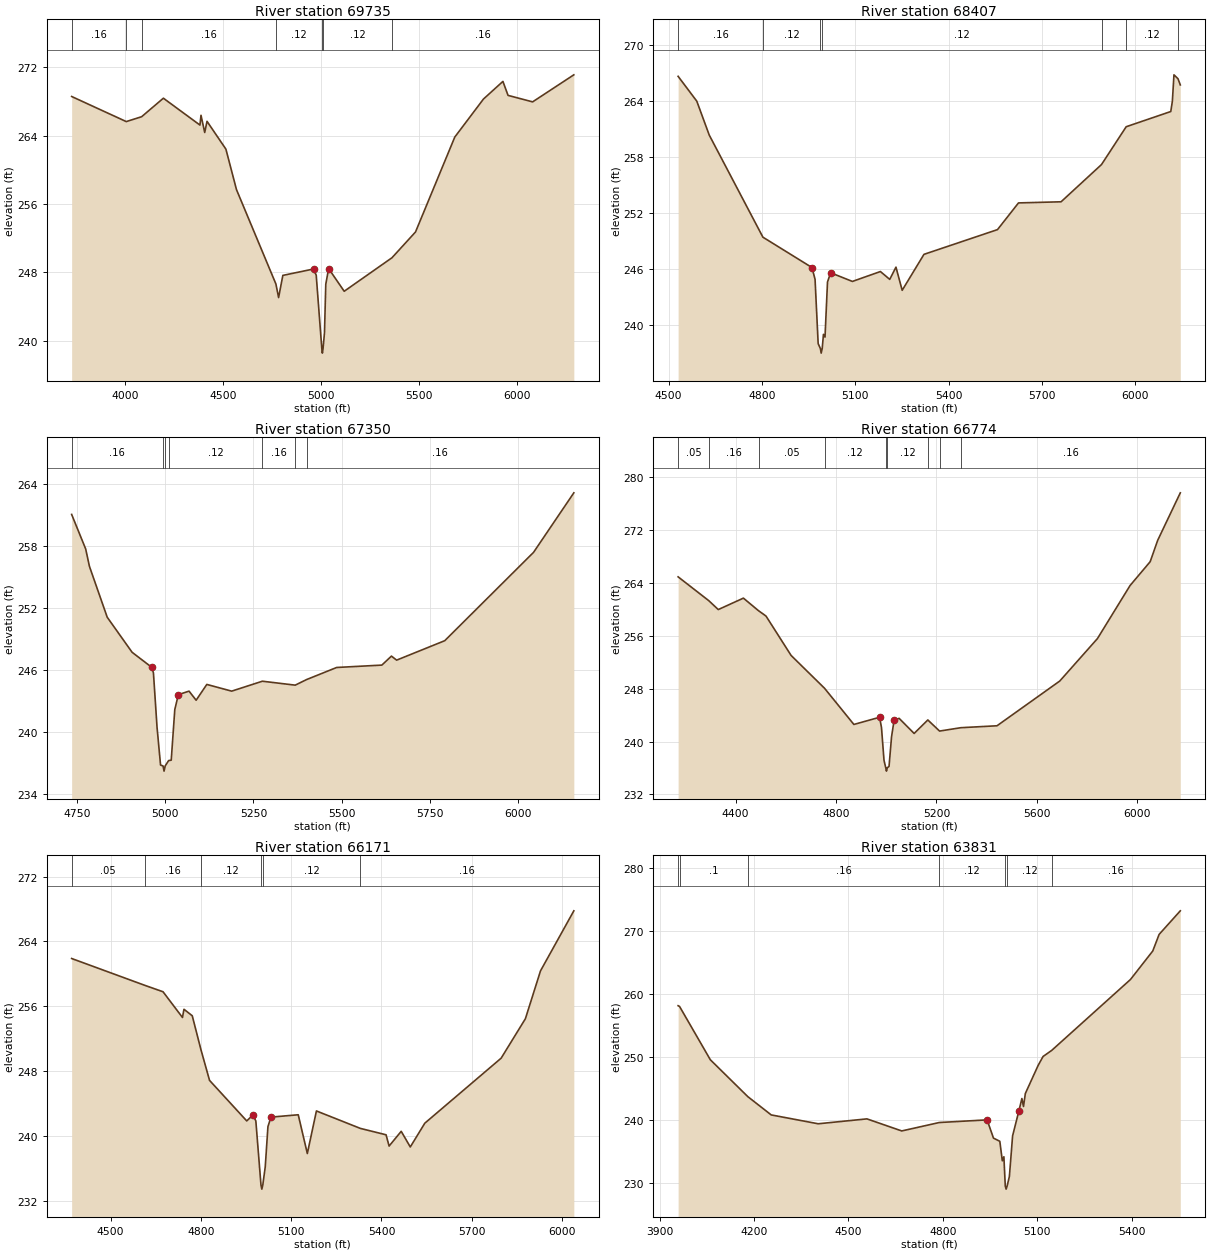
Type RM Length L Ch R = 1 ,69735   ,1328,1328,1328
BEGIN DESCRIPTION:
PEACH CREEK SOUTH 64.0
END DESCRIPTION:
XS GIS Cut Line= 3
      3574745.75     10174164.52      3575174.23      10173080.3
      3575624.48     10171756.17
#Sta/Elev= 30
  3727.1   268.6    4006  265.66  4084.5  266.23  4195.6   268.4  4382.3  265.25
  4387.6   266.4  4406.6  264.38  4418.4  265.69  4514.8  262.43  4568.9  257.68
  4770.2  246.62  4783.9  245.03  4805.5  247.63  4962.1  248.38    4976  247.65
  5004.7  239.02  5007.4  238.52  5010.7  239.02  5018.2  240.91  5024.8  246.59
  5039.4  248.43  5118.9  245.77  5362.9   249.7    5483  252.72  5683.7  263.85
    5830   268.3  5929.4  270.37  5955.5  268.73    6081  267.97  6291.5  271.14
#Mann= 7 ,-1 , 0
  3727.1     .16       0    4006      .1       0  4084.5     .16       0
  4770.2     .12       0  5004.7     .07       0  5010.7     .12       0
  5362.9     .16       0
Bank Sta=4962.1,5039.4
XS Rating Curve= 0 ,0
Exp/Cntr=0.3,0.1

Type RM Length L Ch R = 1 ,68407   ,1057,1057,1057
BEGIN DESCRIPTION:
PEACH CREEK SOUTH 63.0
END DESCRIPTION:
XS GIS Cut Line= 3
      3575892.11     10173891.67      3575882.57     10172996.97
      3575742.11     10172291.67
#Sta/Elev= 30
  4530.7  266.64  4590.7  263.98  4630.7  260.35  4803.2  249.41  4960.8  246.16
  4970.8   244.9  4980.8  238.01  4987.8  237.49  4990.5  236.99  4993.8  237.49
  4997.8     239  5002.8  238.71  5010.8  244.61  5020.8   245.6  5090.8  244.67
  5180.8  245.73  5210.8  244.89  5230.8   246.2  5250.8  243.72  5320.8  247.57
  5557.1  250.22  5624.6  253.08  5761.4   253.2  5891.4  257.19  5970.7  261.24
    6114  262.87  6119.1  263.97  6124.2   266.8  6137.2  266.38  6144.6  265.72
#Mann= 7 ,-1 , 0
  4530.7     .16       0  4803.2     .12       0  4987.8     .07       0
  4993.8     .12       0  5891.4     .16       0  5970.7     .12       0
  6137.2     .16       0
Bank Sta=4960.8,5020.8
XS Rating Curve= 0 ,0
Exp/Cntr=0.3,0.1

Type RM Length L Ch R = 1 ,67350   ,576,576,576
BEGIN DESCRIPTION:
PEACH CREEK SOUTH 62.0
END DESCRIPTION:
XS GIS Cut Line= 3
      3576542.11     10173791.66      3576450.28     10172986.55
      3576092.13     10172491.68
#Sta/Elev= 30
  4735.5  261.08  4775.2  257.74  4785.8  256.06  4836.2  251.13  4906.6  247.74
    4962  246.29    4967  245.74  4977.1  240.51  4987.1  236.83  4994.2  236.74
    4997  236.24  5000.2  236.74  5009.9  237.26  5017.3   237.3  5027.4   242.2
  5037.5  243.64  5067.7  243.98  5087.8   243.1    5118  244.63  5188.4  243.98
  5275.3  244.94  5368.2  244.56  5400.4   245.1  5485.5  246.27  5613.4   246.5
  5640.5  247.37  5655.2  246.98  5791.3  248.86  6042.7  257.41  6156.7  263.17
#Mann= 7 ,-1 , 0
  4735.5     .16       0  4994.2     .07       0  5000.2     .16       0
  5009.9     .12       0  5275.3     .16       0  5368.2     .12       0
  5400.4     .16       0
Bank Sta=4962,5037.5
XS Rating Curve= 0 ,0
Exp/Cntr=0.3,0.1

Type RM Length L Ch R = 1 ,66774   ,603,603,603
BEGIN DESCRIPTION:
PEACH CREEK SOUTH 61.0
END DESCRIPTION:
XS GIS Cut Line= 3
      3576842.11      10174041.6      3576842.11     10173241.64
      3576842.11      10172041.6
#Sta/Elev= 30
  4171.4  264.91  4293.7   261.3  4331.4  259.96  4431.4  261.69  4491.6  259.79
  4521.4  258.98  4621.4  253.02  4754.4  248.06  4871.4  242.58  4973.9  243.67
  4981.4   242.1  4991.4  237.15  4998.4  236.02  5001.1  235.52  5004.4  236.02
  5011.4  236.24  5021.4  240.71  5031.4  243.18  5051.4  243.51  5111.4  241.22
  5165.9  243.26  5212.6  241.58  5297.6  242.09  5441.4  242.38  5691.4  249.15
  5841.4  255.57  5971.4   263.6  6051.4   267.2  6081.4  270.44  6171.4  277.62
#Mann= 9 ,-1 , 0
  4171.4     .05       0  4293.7     .16       0  4491.6     .05       0
  4754.4     .12       0  4998.4     .07       0  5004.4     .12       0
  5165.9     .16       0  5212.6     .12       0  5297.6     .16       0
Bank Sta=4973.9,5031.4
XS Rating Curve= 0 ,0
Exp/Cntr=0.3,0.1

Type RM Length L Ch R = 1 ,66171   ,2340,2340,2340
BEGIN DESCRIPTION:
PEACH CREEK SOUTH 59.0
END DESCRIPTION:
XS GIS Cut Line= 3
      3577476.31      10173840.7      3577392.98     10173533.43
      3577242.11     10172191.65
#Sta/Elev= 30
  4370.5   261.9  4613.7  258.59  4674.1   257.8  4738.7  254.63  4743.7  255.64
  4771.2  254.84  4799.8   250.7  4828.7  246.87  4952.3  241.87  4972.4  242.59
  4982.5  241.87  4999.6  233.96  5002.4  233.46  5005.6  233.96  5013.8  236.22
  5022.7  241.17  5032.8  242.34  5123.4  242.63  5153.6  237.85  5183.8   243.1
  5329.7  240.95  5415.2  240.16  5425.3  238.77  5465.5  240.59  5495.7  238.66
  5543.9  241.59  5797.6  249.61  5878.1  254.47  5928.4  260.38  6039.1  267.78
#Mann= 6 ,-1 , 0
  4370.5     .05       0  4613.7     .16       0  4799.8     .12       0
  4999.6     .07       0  5005.6     .12       0  5329.7     .16       0
Bank Sta=4972.4,5032.8
XS Rating Curve= 0 ,0
Exp/Cntr=0.3,0.1

Type RM Length L Ch R = 1 ,63831   ,1237,1237,1237
BEGIN DESCRIPTION:
PEACH CREEK SOUTH 58.0
END DESCRIPTION:
XS GIS Cut Line= 3
      3577842.11     10173541.63      3578210.69      10172830.3
      3578335.48      10172045.2
#Sta/Elev= 30
    3959  258.14  3963.6  258.02  4061.4  249.54  4180.5  243.67  4254.9  240.76
  4404.2  239.35  4559.1  240.13  4669.8  238.21  4789.1  239.55    4941  239.97
  4961.3  237.07  4981.5  236.56  4989.4  233.46  4994.4   234.1  4998.8  229.45
  5001.5  228.95  5004.8  229.45  5011.9  230.98  5022.1  237.43  5042.3  241.44
  5051.6  243.37  5056.7   242.1  5062.6  244.17  5103.1  248.62  5118.9  250.06
  5146.2  251.02  5396.7  262.31  5467.6  266.85  5487.8  269.49  5555.1  273.24
#Mann= 7 ,-1 , 0
    3959     .05       0  3963.6      .1       0  4180.5     .16       0
  4789.1     .12       0  4998.8     .07       0  5004.8     .12       0
  5146.2     .16       0
Bank Sta=4941,5042.3
XS Rating Curve= 0 ,0
Exp/Cntr=0.3,0.1