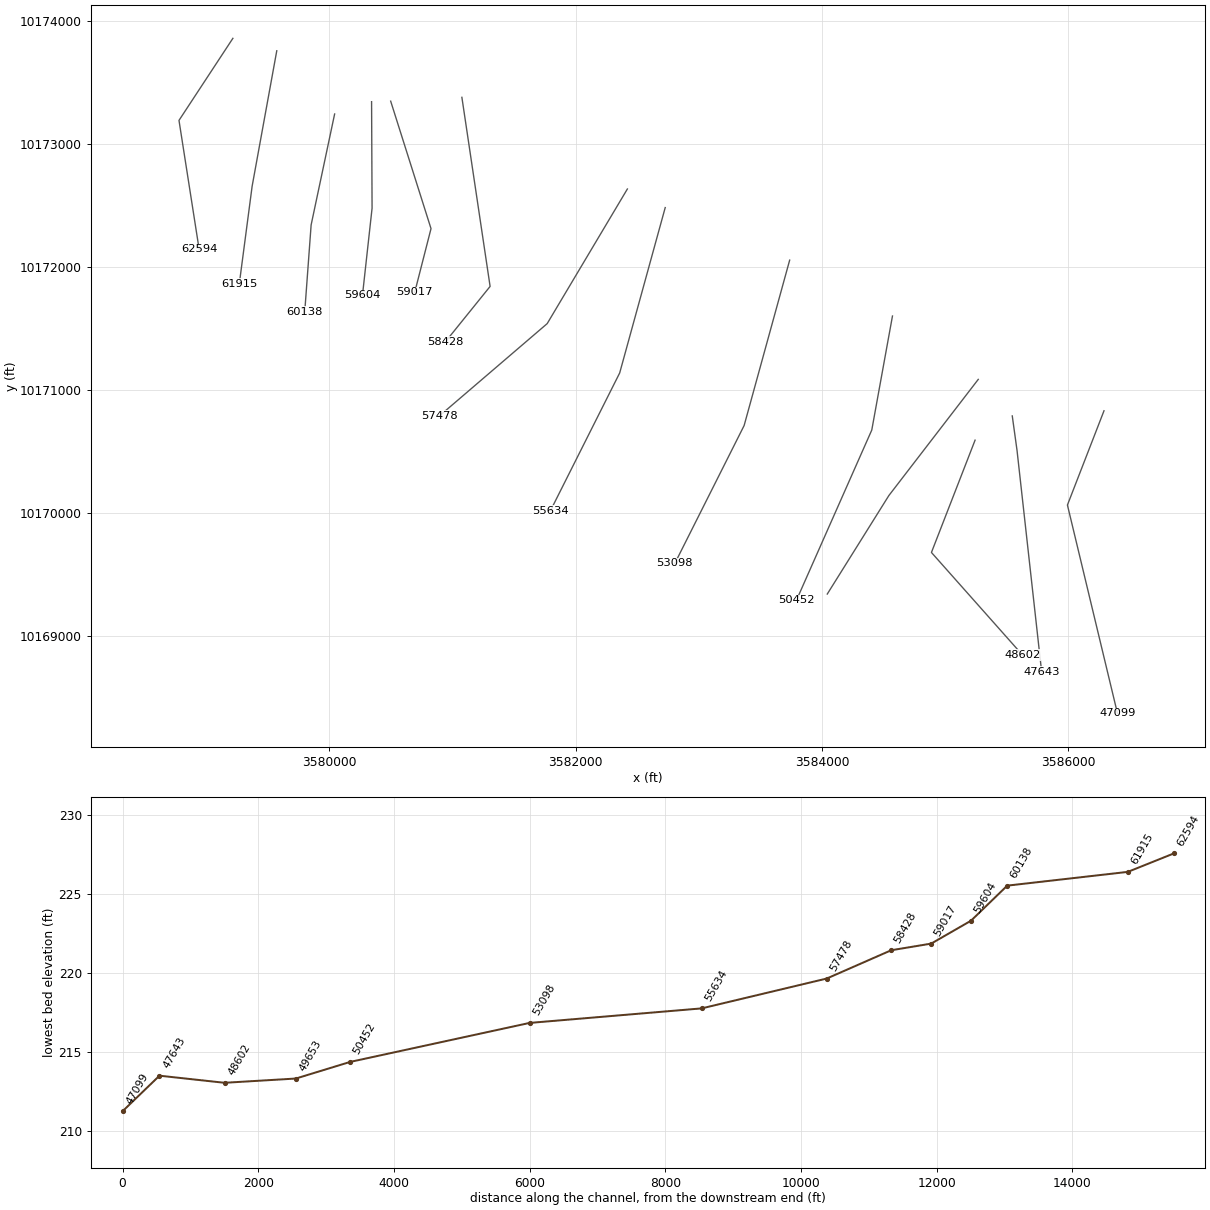
HEC-RAS study PEACH CREEK SOUTH.prj: PEACH CREEK SOUTH Base Level Engineering

--- PEACH CREEK SOUTH.g01 (geometry) --- (continued)

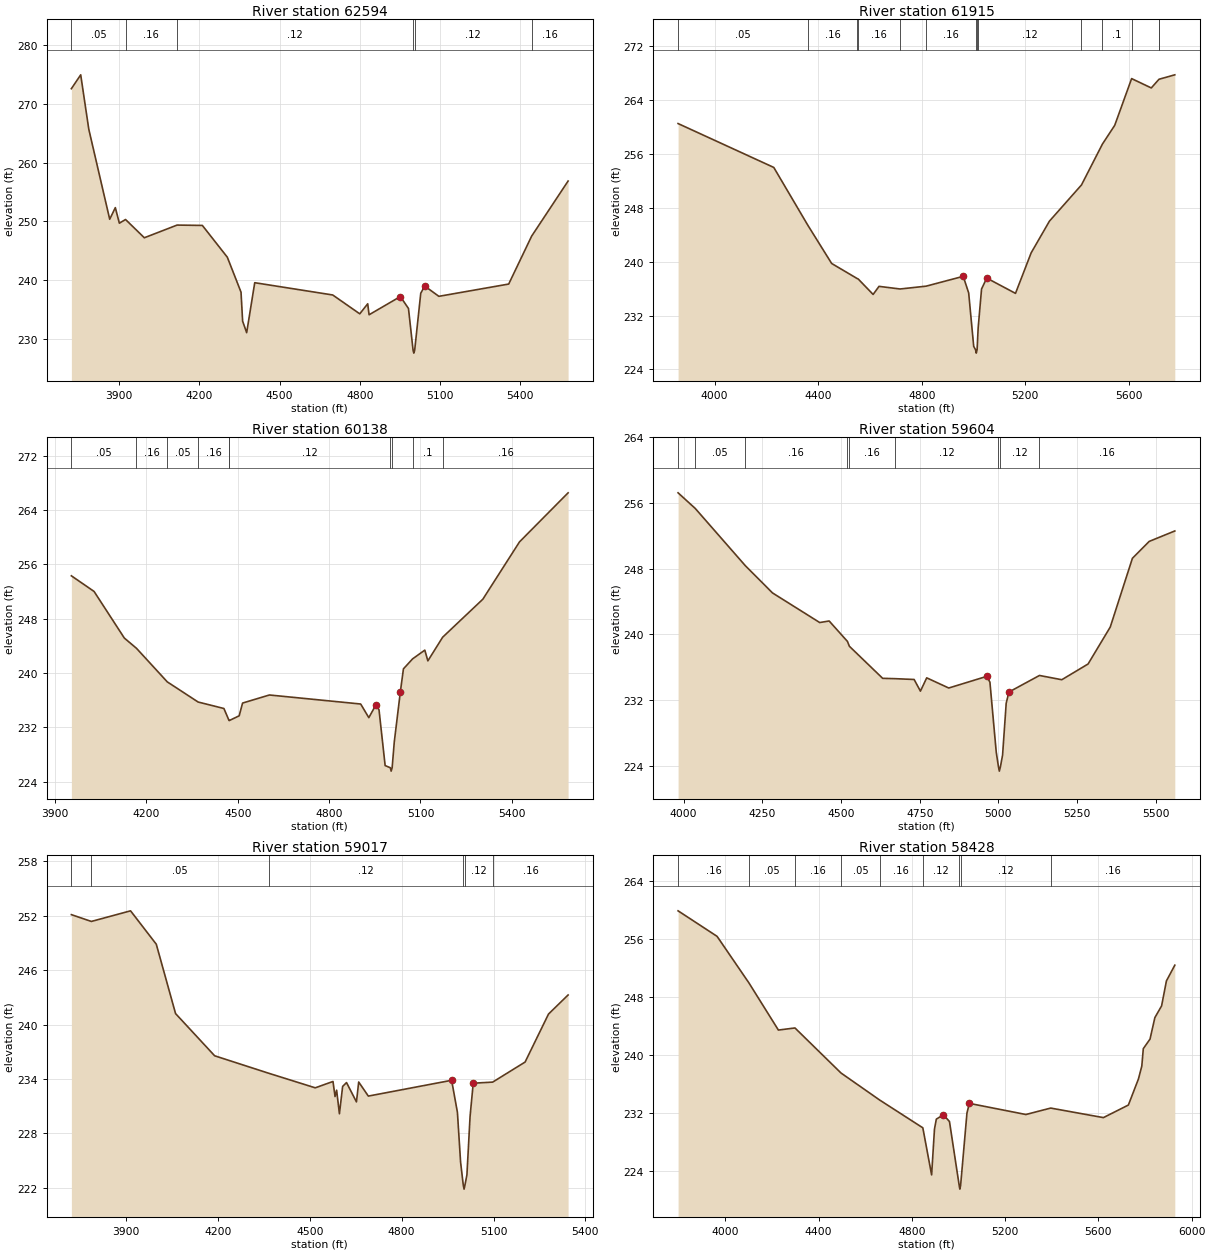
Type RM Length L Ch R = 1 ,62594   ,679,679,679
BEGIN DESCRIPTION:
PEACH CREEK SOUTH 57.0
END DESCRIPTION:
XS GIS Cut Line= 3
      3579215.89     10173856.32       3578778.4     10173189.68
       3578942.1     10172141.66
#Sta/Elev= 30
  3720.8   272.6  3755.7  274.96  3785.9  265.71  3864.2  250.37  3885.2  252.35
  3900.3   249.7  3923.4  250.33  3993.7  247.22  4116.2  249.38  4210.8  249.32
  4304.2  243.91  4355.4  237.96  4361.4  233.02  4376.5  231.06  4406.7  239.57
  4698.4  237.48  4799.6  234.27  4829.3  235.98  4834.4  234.11  4951.4  237.21
  4981.8  235.18    4999  228.08  5001.8  227.58    5005  228.08  5027.7  237.77
  5042.5     239  5095.5  237.25  5356.7  239.34  5442.7  247.51  5578.9  256.88
#Mann= 6 ,-1 , 0
  3720.8     .05       0  3923.4     .16       0  4116.2     .12       0
    4999     .07       0    5005     .12       0  5442.7     .16       0
Bank Sta=4951.4,5042.5
XS Rating Curve= 0 ,0
Exp/Cntr=0.3,0.1

Type RM Length L Ch R = 1 ,61915   ,1777,1777,1777
BEGIN DESCRIPTION:
PEACH CREEK SOUTH 56.0
END DESCRIPTION:
XS GIS Cut Line= 3
      3579572.32     10173755.22      3579372.31     10172655.18
      3579267.99     10171861.58
#Sta/Elev= 30
  3858.7  260.52  4228.3     254  4360.2  245.39  4451.9  239.73  4551.4  237.47
  4554.5  237.42    4612  235.13  4634.8  236.33  4716.2  235.94  4816.8  236.36
    4960  237.82  4981.1  235.35  5000.5  227.41  5007.6  226.91  5010.3  226.41
  5013.6  226.91  5017.7  230.15  5030.8  235.94  5050.9  237.56  5161.9  235.29
  5222.4  241.31    5293  246.02  5416.8   251.4  5497.5  257.46  5545.2  260.26
  5610.4   267.2  5686.4  265.81  5715.2  267.06    5717  267.11  5777.2  267.76
#Mann= 14 ,-1 , 0
  3858.7     .05       0  4360.2     .16       0  4551.4     .05       0
  4554.5     .16       0  4716.2     .05       0  4816.8     .16       0
  5007.6     .07       0  5013.6     .16       0  5017.7     .12       0
  5416.8     .16       0  5497.5      .1       0  5610.4     .16       0
  5715.2      .1       0    5717     .16       0
Bank Sta=4960,5050.9
XS Rating Curve= 0 ,0
Exp/Cntr=0.3,0.1

Type RM Length L Ch R = 1 ,60138   ,534,534,534
BEGIN DESCRIPTION:
PEACH CREEK SOUTH 54.0
END DESCRIPTION:
XS GIS Cut Line= 3
       3580042.1     10173241.63      3579851.32     10172340.72
      3579799.24     10171632.43
#Sta/Elev= 30
  3953.6  254.32  4028.1  252.02  4127.5  245.15  4167.3  243.64  4268.6  238.69
  4369.9  235.72  4454.5  234.77  4471.2  233.01    4472  232.99  4504.6  233.69
  4515.8  235.57  4603.9  236.76  4903.6  235.43  4930.3  233.42  4953.8  235.32
  4963.8  234.58  4983.9  226.36  5000.9  226.04  5003.7  225.54  5006.9  226.04
  5013.9  229.84    5034  237.27    5044  240.61    5074  242.08  5114.2  243.37
  5124.2  241.79  5172.9  245.28  5304.7  250.87  5425.1  259.32  5584.7  266.55
#Mann= 10 ,-1 , 0
  3953.6     .05       0  4167.3     .16       0  4268.6     .05       0
  4369.9     .16       0  4471.2     .05       0    4472     .12       0
  5000.9     .07       0  5006.9     .12       0    5074      .1       0
  5172.9     .16       0
Bank Sta=4953.8,5034
XS Rating Curve= 0 ,0
Exp/Cntr=0.3,0.1

Type RM Length L Ch R = 1 ,59604   ,587,587,587
BEGIN DESCRIPTION:
PEACH CREEK SOUTH 52.0
END DESCRIPTION:
XS GIS Cut Line= 3
      3580342.11     10173341.68      3580346.11     10172476.14
      3580267.98     10171767.78
#Sta/Elev= 30
  3982.2  257.24  4036.9  255.33  4195.4  248.38  4282.2  245.04  4432.2  241.43
  4462.2  241.62  4520.3  239.13  4526.4  238.54  4632.2  234.63  4670.7  234.59
  4732.2  234.49  4752.2  233.07  4772.2  234.69  4842.2  233.45  4962.9  234.87
    4973  234.16  4993.1  225.63  5000.2  223.82  5002.9  223.32  5006.2  223.82
  5013.2  225.28  5024.7   231.6  5033.4  232.96  5130.4  234.98  5201.4  234.46
  5284.9  236.38  5355.3  240.88  5425.7  249.26  5479.1  251.32  5560.4  252.59
#Mann= 9 ,-1 , 0
  3982.2     .16       0  4036.9     .05       0  4195.4     .16       0
  4520.3     .05       0  4526.4     .16       0  4670.7     .12       0
  5000.2     .07       0  5006.2     .12       0  5130.4     .16       0
Bank Sta=4962.9,5033.4
XS Rating Curve= 0 ,0
Exp/Cntr=0.3,0.1

Type RM Length L Ch R = 1 ,59017   ,589,589,589
BEGIN DESCRIPTION:
PEACH CREEK SOUTH 51.0
END DESCRIPTION:
XS GIS Cut Line= 3
      3580497.16      10173345.9      3580824.66     10172310.26
       3580692.1     10171791.62
#Sta/Elev= 30
    3722  252.11  3787.2  251.36  3915.2  252.53  3999.2  248.85  4062.1  241.21
  4189.7  236.56  4365.8  234.64  4518.1  233.03    4576  233.73  4582.7  232.07
  4587.9  232.77    4597  230.17  4607.5  233.18  4620.2  233.61  4652.6  231.48
  4659.9  233.67  4691.4  232.12  4963.3  233.86  4982.2  230.33  4992.5  224.86
  5001.1  222.37  5003.9  221.87  5007.1  222.37  5013.2  223.44  5023.5  229.88
  5033.8  233.54  5097.3  233.66  5203.1  235.87  5279.6  241.16  5343.5  243.26
#Mann= 6 ,-1 , 0
    3722     .16       0  3787.2     .05       0  4365.8     .12       0
  5001.1     .07       0  5007.1     .12       0  5097.3     .16       0
Bank Sta=4963.3,5033.8
XS Rating Curve= 0 ,0
Exp/Cntr=0.3,0.1

Type RM Length L Ch R = 1 ,58428   ,950,950,950
BEGIN DESCRIPTION:
PEACH CREEK SOUTH 50.0
END DESCRIPTION:
XS GIS Cut Line= 3
      3581075.28     10173377.13      3581304.44     10171840.72
      3580942.13     10171391.67
#Sta/Elev= 30
  3797.4  259.94  3964.7  256.41  4101.1  249.98  4227.6  243.45  4298.7  243.74
  4496.2  237.51  4662.1  233.77  4847.1  229.93  4884.8  223.42  4897.1  229.76
    4905  231.13  4935.3  231.73  4961.4   230.8  5003.1  221.95  5005.9  221.45
  5009.1  221.95  5036.4  231.98  5046.6  233.31  5289.2  231.77  5395.5  232.66
  5621.6  231.34  5728.7  233.08  5771.9  236.69  5786.3  238.47  5792.7  240.88
  5821.5   242.2  5842.3  245.17  5871.1  246.79  5891.9  250.25  5927.8  252.42
#Mann= 9 ,-1 , 0
  3797.4     .16       0  4101.1     .05       0  4298.7     .16       0
  4496.2     .05       0  4662.1     .16       0  4847.1     .12       0
  5003.1     .07       0  5009.1     .12       0  5395.5     .16       0
Bank Sta=4935.3,5046.6
XS Rating Curve= 0 ,0
Exp/Cntr=0.3,0.1

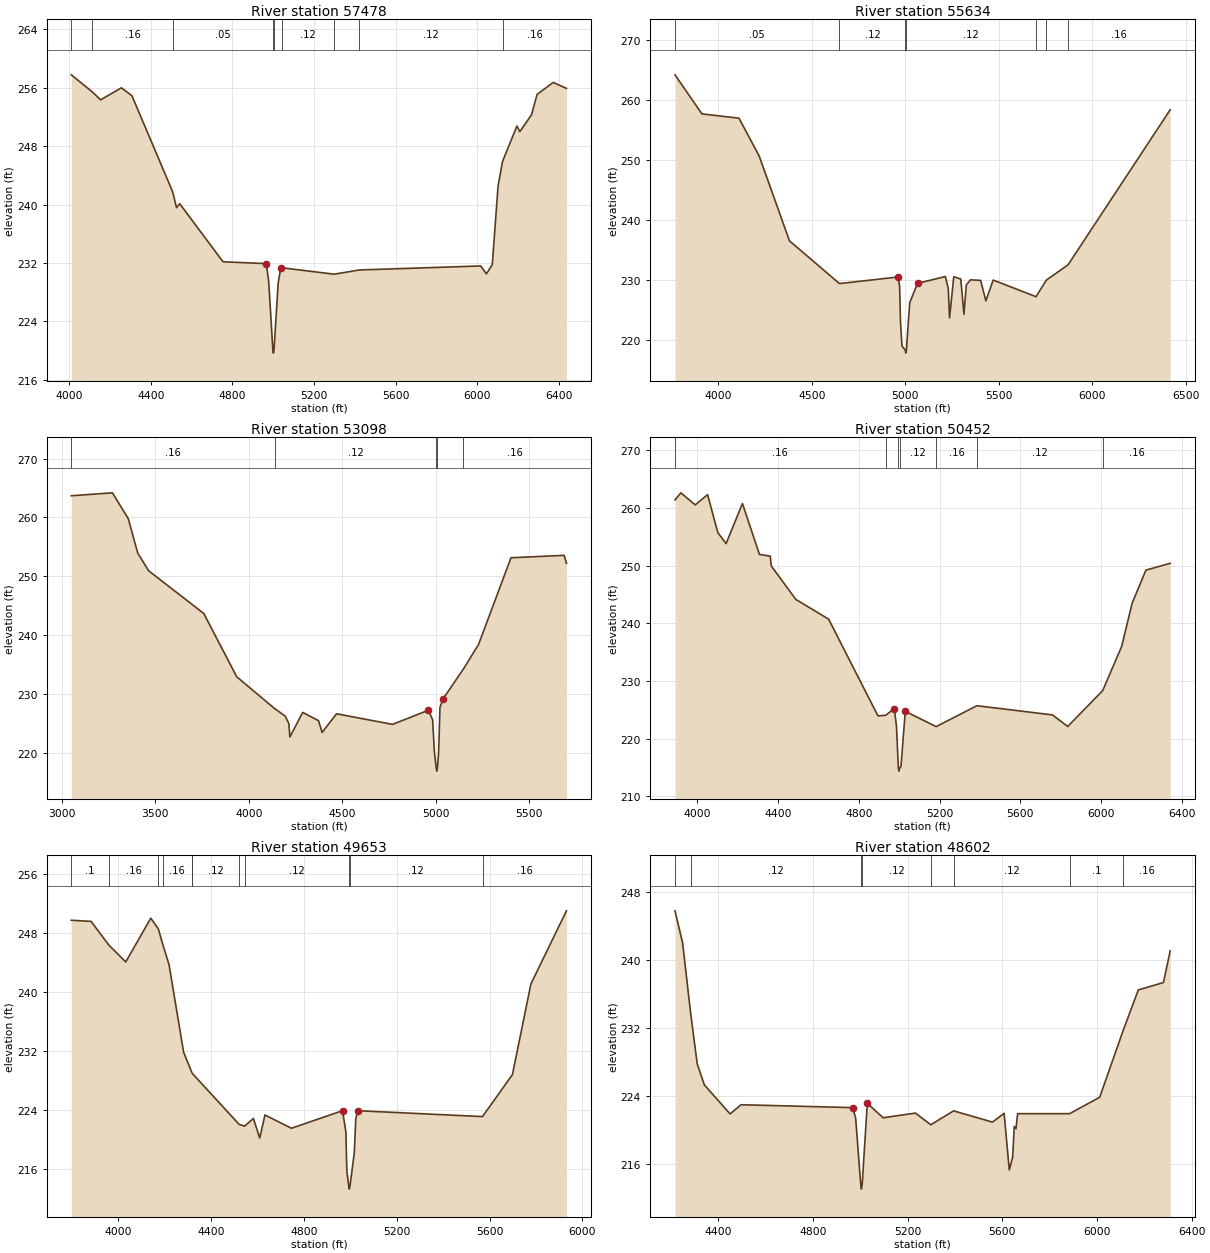
Type RM Length L Ch R = 1 ,57478   ,1844,1844,1844
BEGIN DESCRIPTION:
PEACH CREEK SOUTH 49.0
END DESCRIPTION:
XS GIS Cut Line= 3
      3582419.01     10172632.36      3581767.98     10171538.64
      3580892.96     10170788.62
#Sta/Elev= 30
  4010.8  257.78    4113  255.46  4154.2  254.35    4256     256  4307.8  254.92
  4507.2  241.76  4526.2  239.58  4541.8  240.13    4754  232.17  4965.9  231.92
  4977.9  229.42  4997.8  220.16  5000.6  219.66  5003.8  220.16  5024.1  229.27
  5036.4  231.28  5042.7  231.35    5298  230.47  5421.6  231.05  6015.8   231.6
  6044.2  230.52  6072.7  231.79  6101.2  242.58  6123.2  245.93  6193.4  250.77
  6207.7     250  6264.8   252.3  6292.3   255.1  6371.2  256.74  6436.1  255.92
#Mann= 9 ,-1 , 0
  4010.8     .05       0    4113     .16       0  4507.2     .05       0
  4997.8     .04       0  5003.8     .05       0  5042.7     .12       0
    5298     .16       0  5421.6     .12       0  6123.2     .16       0
Bank Sta=4965.9,5036.4
XS Rating Curve= 0 ,0
Exp/Cntr=0.3,0.1

Type RM Length L Ch R = 1 ,55634   ,2536,2536,2536
BEGIN DESCRIPTION:
PEACH CREEK SOUTH 48.0
END DESCRIPTION:
XS GIS Cut Line= 3
      3582726.31     10172481.31      3582356.53      10171137.6
      3581794.03      10170017.8
#Sta/Elev= 30
  3769.4  264.23  3913.1  257.71  4111.3  256.99  4219.4  250.67    4381  236.52
  4648.5  229.38  4961.8  230.48  4969.7  229.02  4974.9  222.82  4982.6  218.96
  5000.3  218.27    5003  217.77  5006.3  218.27    5024   226.2  5065.5  229.41
  5214.5  230.56  5229.9  228.56  5236.9  223.65  5259.3  230.53  5296.9  230.13
  5313.7  224.25  5326.4  229.15  5348.8  230.01    5403  229.91  5430.9   226.5
    5470  229.97  5698.9  227.19  5754.4  229.96  5870.3  232.51  6416.2   258.4
#Mann= 7 ,-1 , 0
  3769.4     .05       0  4648.5     .12       0  5000.3     .07       0
  5006.3     .12       0  5698.9     .16       0  5754.4     .12       0
  5870.3     .16       0
Bank Sta=4961.8,5065.5
XS Rating Curve= 0 ,0
Exp/Cntr=0.3,0.1

Type RM Length L Ch R = 1 ,53098   ,2646,2646,2646
BEGIN DESCRIPTION:
PEACH CREEK SOUTH 48.1
END DESCRIPTION:
XS GIS Cut Line= 3
      3583736.73     10172054.26      3583366.94     10170710.51
      3582804.46     10169590.75
#Sta/Elev= 30
  3051.4  263.67  3271.4  264.17  3355.8  259.79  3406.8   253.9  3464.2  250.94
  3759.4  243.66  3935.7  232.89  4138.5  227.48    4195   226.2  4214.5  224.92
  4219.6  222.66  4288.4  226.83  4372.8  225.43  4392.1  223.43  4469.4   226.6
  4768.4   224.8  4960.7  227.21    4983  225.55  4992.2  220.07  5002.3  217.35
  5005.1  216.85  5008.3  217.35  5014.6  219.83  5022.1  227.69  5036.9  229.06
  5147.3  234.21  5228.6  238.41  5401.7  253.13    5686  253.54  5698.2  252.18
#Mann= 5 ,-1 , 0
  3051.4     .16       0  4138.5     .12       0  5002.3     .07       0
  5008.3     .12       0  5147.3     .16       0
Bank Sta=4960.7,5036.9
XS Rating Curve= 0 ,0
Exp/Cntr=0.3,0.1

Type RM Length L Ch R = 1 ,50452   ,799,799,799
BEGIN DESCRIPTION:
PEACH CREEK SOUTH 47.0
END DESCRIPTION:
XS GIS Cut Line= 3
      3584571.39     10171600.31       3584403.4     10170674.05
      3583792.11     10169291.65
#Sta/Elev= 30
  3889.6  261.36  3918.7  262.59  3989.9   260.5  4050.9  262.28  4101.7   255.7
  4142.6   253.8  4223.6  260.73  4307.9  251.92  4361.4  251.62  4366.5  249.92
  4487.9  244.13  4650.5  240.71  4894.9  223.95  4932.6  224.05  4975.7   225.2
  4986.7  222.17    4996  214.88  4998.7  214.38    5002  214.88  5008.6  215.16
  5030.4  224.74  5183.1  222.09    5385  225.71  5759.5  224.12  5834.8  222.11
  6008.4  228.34    6102  235.98  6154.1  243.47  6222.2   249.2  6342.5  250.38
#Mann= 7 ,-1 , 0
  3889.6     .16       0  4932.6     .12       0    4996     .07       0
    5002     .12       0  5183.1     .16       0    5385     .12       0
  6008.4     .16       0
Bank Sta=4975.7,5030.4
XS Rating Curve= 0 ,0
Exp/Cntr=0.3,0.1

Type RM Length L Ch R = 1 ,49653   ,1051,1051,1051
BEGIN DESCRIPTION:
PEACH CREEK SOUTH 46.0
END DESCRIPTION:
XS GIS Cut Line= 3
      3585267.98      10171085.5      3584542.11     10170141.64
       3584042.1     10169341.64
#Sta/Elev= 30
  3797.1  249.77  3882.3  249.62  3959.2   246.4  4031.8  244.12  4139.6  250.05
  4172.1  248.61  4190.9  246.54  4218.3  243.76  4281.3  231.87  4317.2   229.1
  4318.7  229.01  4520.3  222.11  4543.8  221.86  4581.9   222.9  4609.3  220.26
  4631.7  223.38  4745.9  221.58    4966  223.96  4980.5  221.09  4984.6  215.85
  4992.5  213.83  4995.2  213.33  4998.5  213.83  5016.7  218.23  5023.2  222.87
    5032  223.96  5569.3  223.16  5698.3  228.85  5777.9  241.14  5931.2  251.05
#Mann= 11 ,-1 , 0
  3797.1      .1       0  3959.2     .16       0  4172.1      .1       0
  4190.9     .16       0  4317.2      .1       0  4318.7     .12       0
  4520.3     .16       0  4543.8     .12       0  4992.5     .07       0
  4998.5     .12       0  5569.3     .16       0
Bank Sta=4966,5032
XS Rating Curve= 0 ,0
Exp/Cntr=0.3,0.1

Type RM Length L Ch R = 1 ,48602   ,959,959,959
BEGIN DESCRIPTION:
PEACH CREEK SOUTH 45.0
END DESCRIPTION:
XS GIS Cut Line= 3
       3585242.1     10170591.62      3584887.78     10169679.26
      3585626.94      10168846.4
#Sta/Elev= 30
    4217  245.74  4249.2  241.96    4283  233.71  4310.9  227.76  4340.8  225.31
  4449.7  221.89  4495.9  222.97  4967.9  222.63  4980.3  221.41  5001.8  213.56
  5004.6  213.06  5007.8  213.56  5029.4  223.13  5096.6  221.44  5232.7  221.99
  5297.8  220.62  5394.2  222.25  5558.3  220.93  5607.6  221.96  5629.4  215.31
  5643.6  216.81  5650.3  220.42  5657.8  220.15  5664.5  221.92  5884.3  221.92
  6011.5  223.85    6111  231.72  6174.6  236.45  6280.8  237.32  6309.3  241.04
#Mann= 8 ,-1 , 0
    4217      .1       0    4283     .12       0  5001.8     .07       0
  5007.8     .12       0  5297.8     .16       0  5394.2     .12       0
  5884.3      .1       0    6111     .16       0
Bank Sta=4967.9,5029.4
XS Rating Curve= 0 ,0
Exp/Cntr=0.3,0.1

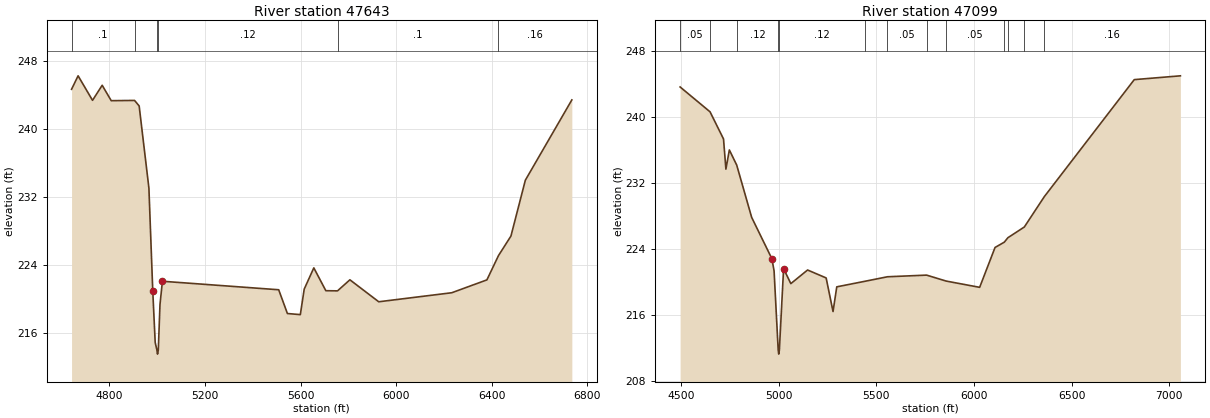
Type RM Length L Ch R = 1 ,47643   ,544,544,544
BEGIN DESCRIPTION:
PEACH CREEK SOUTH 44.0
END DESCRIPTION:
XS GIS Cut Line= 3
      3585544.03     10170788.65      3585582.73     10170508.31
      3585782.73     10168708.28
#Sta/Elev= 30
  4641.3  244.62  4668.7   246.2  4729.1  243.32  4769.5  245.09  4807.4  243.28
    4905  243.31  4924.3  242.66  4965.1  233.01  4981.3  220.88  4991.4  214.88
  4998.4  214.01  5001.2  213.51  5004.4  214.01  5011.5  219.35  5021.6  222.07
  5508.4  221.07  5544.8  218.28  5598.9  218.15  5615.2  221.15  5655.4  223.64
  5705.7  220.96  5754.5  220.94  5806.4  222.24  5927.1  219.66  6232.8  220.72
  6379.9  222.23  6428.3  225.08  6480.5  227.38  6540.8  233.94  6735.4  243.37
#Mann= 6 ,-1 , 0
  4641.3      .1       0    4905     .12       0  4998.4     .07       0
  5004.4     .12       0  5754.5      .1       0  6428.3     .16       0
Bank Sta=4981.3,5021.6
XS Rating Curve= 0 ,0
Exp/Cntr=0.3,0.1

Type RM Length L Ch R = 1 ,47099   ,2767,2767,2767
BEGIN DESCRIPTION:
PEACH CREEK SOUTH 43.0
END DESCRIPTION:
XS GIS Cut Line= 3
      3586288.83     10170830.33      3585991.94     10170064.68
       3586398.2     10168371.94
#Sta/Elev= 30
  4495.6  243.62  4648.9  240.61  4717.9  237.32  4730.1  233.67  4747.8  235.99
  4785.4  234.16  4862.1  227.82  4965.7  222.81  4976.8  221.34  4997.9  211.76
  5000.7  211.26  5003.9  211.76  5025.5  221.61  5062.6   219.8  5148.4  221.45
  5243.4  220.49  5278.7  216.42  5297.9  219.41  5443.5  220.09  5557.5  220.63
  5757.8  220.83  5857.9  220.11  6029.6  219.35  6108.4  224.18  6155.7  224.82
  6174.2  225.36  6258.4  226.66  6360.8  230.34  6821.4  244.51  7057.6  244.97
#Mann= 13 ,-1 , 0
  4495.6     .05       0  4648.9     .16       0  4785.4     .12       0
  4997.9     .07       0  5003.9     .12       0  5443.5     .16       0
  5557.5     .05       0  5757.8      .1       0  5857.9     .05       0
  6155.7      .1       0  6174.2     .05       0  6258.4      .1       0
  6360.8     .16       0
Bank Sta=4965.7,5025.5
XS Rating Curve= 0 ,0
Exp/Cntr=0.3,0.1