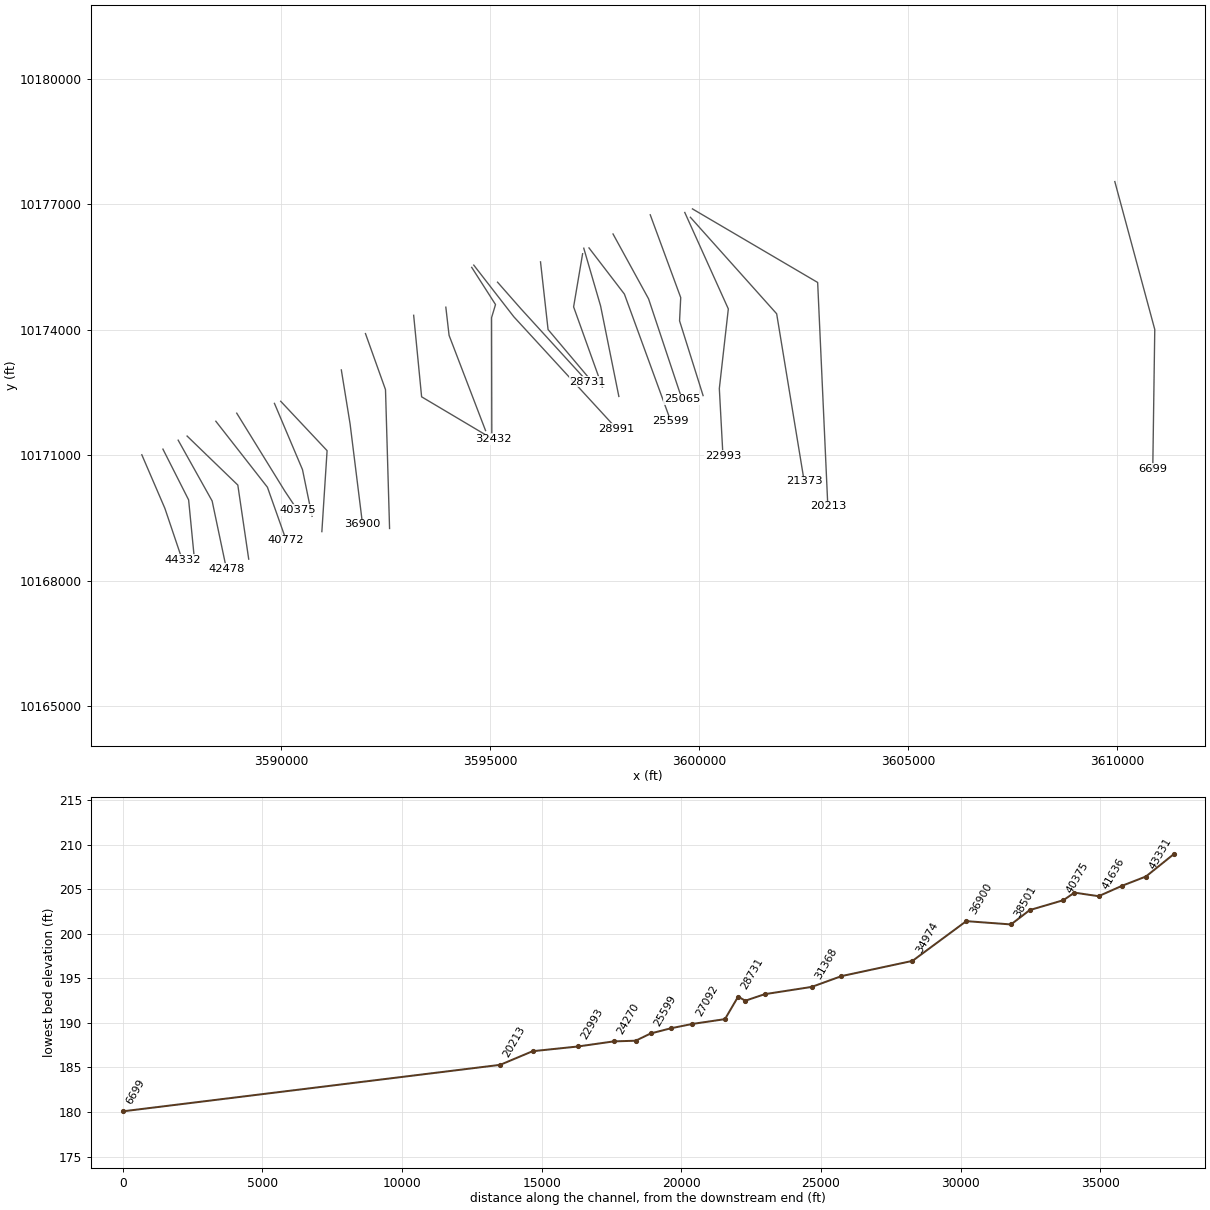
HEC-RAS study PEACH CREEK SOUTH.prj: PEACH CREEK SOUTH Base Level Engineering

--- PEACH CREEK SOUTH.g01 (geometry) --- (continued)

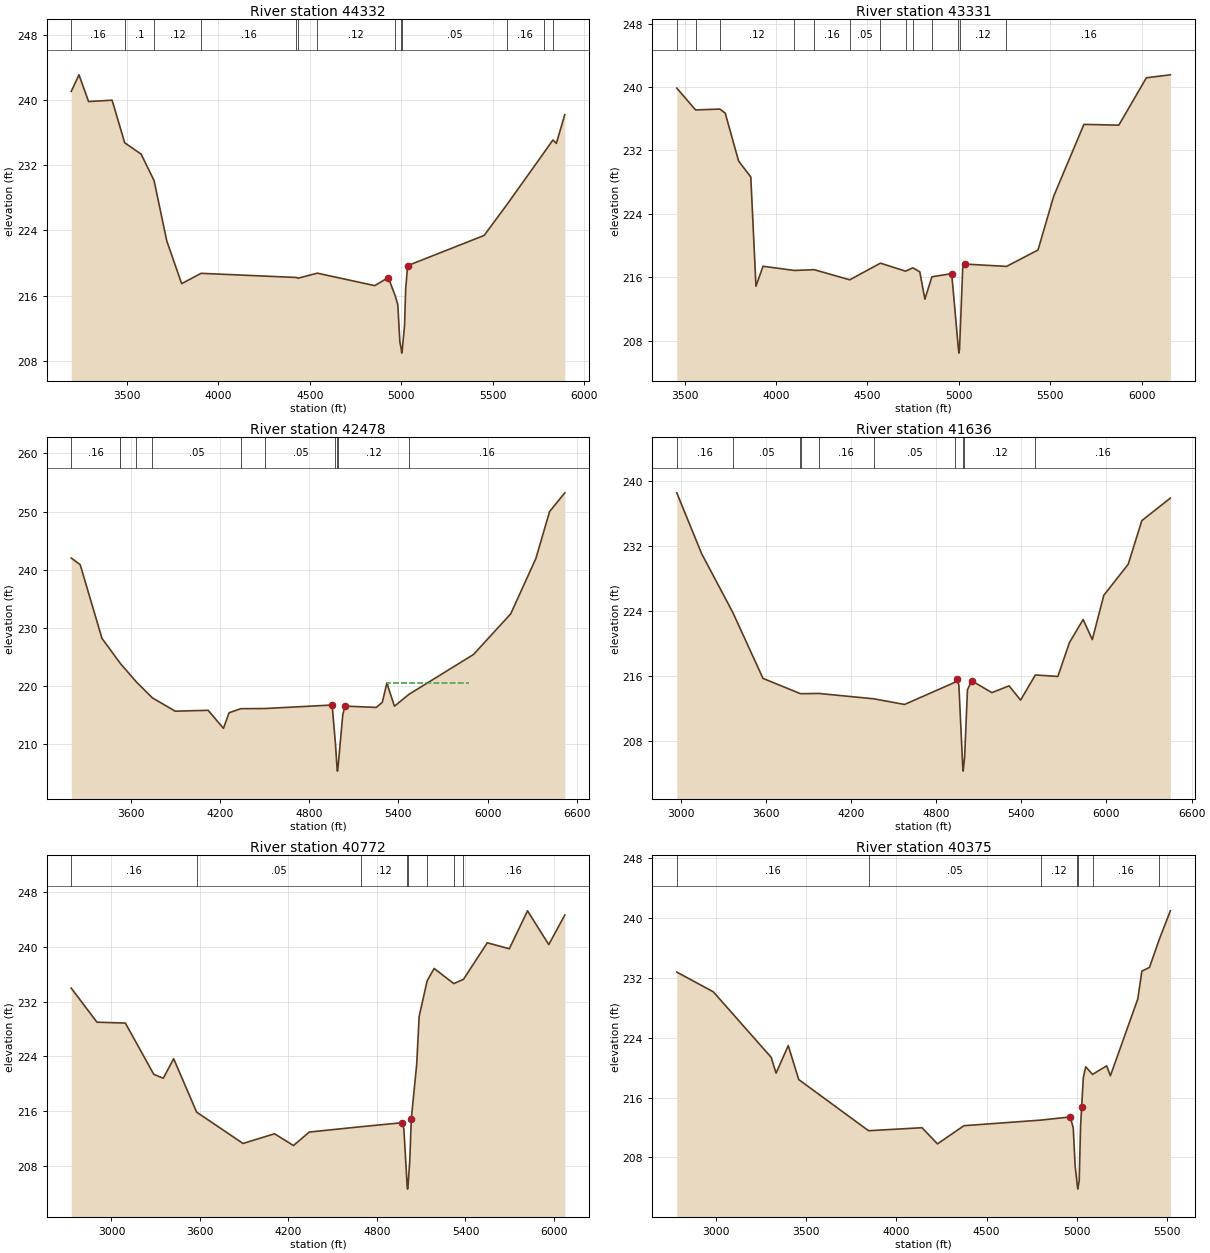
Type RM Length L Ch R = 1 ,44332   ,1001,1001,1001
BEGIN DESCRIPTION:
PEACH CREEK SOUTH 42.0
END DESCRIPTION:
XS GIS Cut Line= 3
      3586669.03      10171012.6      3587221.11     10169731.35
      3587637.45     10168497.95
#Sta/Elev= 30
  3196.5  241.05  3238.9  243.09  3291.4  239.81  3419.9  239.98  3488.8  234.75
  3578.6  233.36  3649.2  230.12  3718.5  222.73    3800  217.47  3905.9  218.74
  4426.9  218.23  4435.9  218.14  4541.2  218.76  4855.2  217.23  4929.1  218.22
  4967.3  215.96  4981.1  214.88  4992.4  210.29  4999.9  209.45  5002.7  208.95
  5005.9  209.45  5017.8  212.31    5024  216.79  5034.6  219.68    5453  223.39
  5577.3  227.17  5778.3   233.5  5828.7   235.1  5847.3  234.68  5893.4   238.2
#Mann= 13 ,-1 , 0
  3196.5     .16       0  3488.8      .1       0  3649.2     .12       0
  3905.9     .16       0  4426.9     .05       0  4435.9     .16       0
  4541.2     .12       0  4967.3     .05       0  4999.9     .03       0
  5005.9     .05       0  5577.3     .16       0  5778.3     .05       0
  5828.7     .16       0
Bank Sta=4929.1,5034.6
XS Rating Curve= 0 ,0
Exp/Cntr=0.3,0.1

Type RM Length L Ch R = 1 ,43331   ,853,853,853
BEGIN DESCRIPTION:
PEACH CREEK SOUTH 40.0
END DESCRIPTION:
XS GIS Cut Line= 3
      3587174.23     10171148.02      3587788.82     10169934.47
      3587919.03     10168601.11
#Sta/Elev= 30
  3457.2  239.87  3560.1  237.11  3692.9  237.22  3722.2  236.71  3795.3  230.67
  3862.1  228.65  3890.3  214.87  3928.9  217.39  4100.2  216.86  4208.3  216.96
  4403.4  215.68  4571.1  217.78  4708.9  216.77  4748.4  217.19  4786.5  216.69
  4814.4  213.24  4852.9  216.06    4961  216.46  4997.9  206.93  5000.7  206.43
  5003.9  206.93  5021.3  217.15  5031.3  217.67  5260.8  217.37  5433.2  219.44
  5519.4  226.25  5684.4  235.29  5875.3  235.19  6026.1  241.17  6157.2  241.54
#Mann= 13 ,-1 , 0
  3457.2      .1       0  3560.1     .16       0  3692.9     .12       0
  4100.2     .05       0  4208.3     .16       0  4403.4     .05       0
  4571.1     .16       0  4708.9     .05       0  4748.4     .16       0
  4852.9     .12       0  4997.9     .07       0  5003.9     .12       0
  5260.8     .16       0
Bank Sta=4961,5031.3
XS Rating Curve= 0 ,0
Exp/Cntr=0.3,0.1

Type RM Length L Ch R = 1 ,42478   ,842,842,842
BEGIN DESCRIPTION:
PEACH CREEK SOUTH 39.0
END DESCRIPTION:
XS GIS Cut Line= 3
      3587538.82     10171361.55      3588351.32     10169908.43
      3588692.11      10168291.6
#Sta/Elev= 30
  3201.3  242.01  3261.7  240.86  3407.9  228.21  3528.8  223.99  3529.6  223.95
  3639.8   220.7  3746.3  217.99  3900.1  215.69  4121.7  215.84  4224.5  212.74
  4262.1  215.42  4341.1  216.12  4506.7  216.15  4954.8  216.75  4977.3  210.08
  4987.9  205.89  4990.6  205.39  4993.9  205.89  5026.4  215.07  5040.7  216.56
  5251.2  216.34  5292.1  217.21  5322.7  220.52  5373.8  216.55  5470.4  218.57
  5905.3  225.44  6155.2  232.42  6324.3  241.93  6416.3  249.99  6518.5  253.21
#Mann= 11 ,-1 , 0
  3201.3     .16       0  3528.8     .05       0  3529.6     .16       0
  3639.8     .12       0  3746.3     .05       0  4341.1     .16       0
  4506.7     .05       0  4977.3     .12       0  4987.9     .07       0
  4993.9     .12       0  5470.4     .16       0
#XS Ineff= 1 ,-1
 5329.55    5875  220.58
Permanent Ineff=
       F
Bank Sta=4954.8,5040.7
XS Rating Curve= 0 ,0
Exp/Cntr=0.3,0.1

Type RM Length L Ch R = 1 ,41636   ,864,864,864
BEGIN DESCRIPTION:
PEACH CREEK SOUTH 38.0
END DESCRIPTION:
XS GIS Cut Line= 3
      3587752.35     10171460.52       3588965.9     10170288.64
      3589226.32     10168517.79
#Sta/Elev= 30
    2973  238.58  3148.9  231.04  3367.4  223.82  3580.3  215.67  3840.2  213.81
    3850  213.78    3974  213.81  4360.5  213.15  4577.4  212.45  4932.9  215.19
  4944.1  215.62  4960.2  214.84  4987.5  204.72  4990.3  204.22  4993.5  204.72
  5000.6  205.94  5020.8  214.28  5051.2  215.37  5192.7  213.91    5314  214.75
  5394.8  212.99  5498.9  216.09  5657.6  215.91  5738.5  220.07  5835.6  222.94
  5900.2  220.46  5981.1  225.93  6152.9  229.76    6249  235.15  6449.9  237.93
#Mann= 10 ,-1 , 0
    2973     .16       0  3367.4     .05       0  3840.2     .16       0
    3850     .05       0    3974     .16       0  4360.5     .05       0
  4932.9     .12       0  4987.5     .07       0  4993.5     .12       0
  5498.9     .16       0
Bank Sta=4944.1,5051.2
XS Rating Curve= 0 ,0
Exp/Cntr=0.3,0.1

Type RM Length L Ch R = 1 ,40772   ,397,397,397
BEGIN DESCRIPTION:
PEACH CREEK SOUTH 37.0
END DESCRIPTION:
XS GIS Cut Line= 3
      3588439.88     10171814.66      3589674.23     10170236.55
      3590122.16     10168970.89
#Sta/Elev= 30
  2727.1  233.99  2901.7  229.01  3094.3  228.88  3286.9  221.39  3351.1  220.82
  3421.7  223.67  3577.5  215.87  3891.9  211.29  4105.3  212.71  4233.7  210.99
  4341.3  212.96  4691.8  213.74  4969.2  214.32  4982.1  213.48  5004.6  205.12
  5007.4  204.62  5010.6  205.12  5022.2  208.75  5032.8  214.89  5069.4   222.9
  5085.9  229.84  5140.1  235.06  5187.7  236.86  5320.7  234.65  5386.3  235.27
  5547.9  240.61  5697.1  239.74  5820.7  245.28  5964.6  240.35  6073.2  244.66
#Mann= 8 ,-1 , 0
  2727.1     .16       0  3577.5     .05       0  4691.8     .12       0
  5004.6     .07       0  5010.6     .12       0  5140.1     .16       0
  5320.7      .1       0  5386.3     .16       0
Bank Sta=4969.2,5032.8
XS Rating Curve= 0 ,0
Exp/Cntr=0.3,0.1

Type RM Length L Ch R = 1 ,40375   ,1205,1205,1205
BEGIN DESCRIPTION:
PEACH CREEK SOUTH 36.0
END DESCRIPTION:
XS GIS Cut Line= 3
      3588939.86     10172007.39      3590092.11     10170141.64
       3590392.1     10169691.65
#Sta/Elev= 30
  2784.3  232.79  2986.7  230.15  3307.1  221.39  3334.3  219.28  3401.7  222.96
  3459.7  218.42  3846.4  211.58  4142.7  211.98  4228.1  209.82  4374.8  212.25
  4801.1     213  4963.6  213.42  4980.2  211.95  4990.7  206.85  5002.7  204.27
  5005.5  203.77  5008.7  204.27  5013.2   204.9  5020.7  212.21  5026.8  214.73
  5035.8  218.64  5049.3  220.13  5086.9  219.11    5165  220.25    5186  218.93
  5337.7   229.2  5360.3  232.92  5402.3  233.41  5455.5  237.09    5518  240.98
#Mann= 7 ,-1 , 0
  2784.3     .16       0  3846.4     .05       0  4801.1     .12       0
  5002.7     .07       0  5008.7     .12       0  5086.9     .16       0
  5455.5     .05       0
Bank Sta=4963.6,5026.8
XS Rating Curve= 0 ,0
Exp/Cntr=0.3,0.1

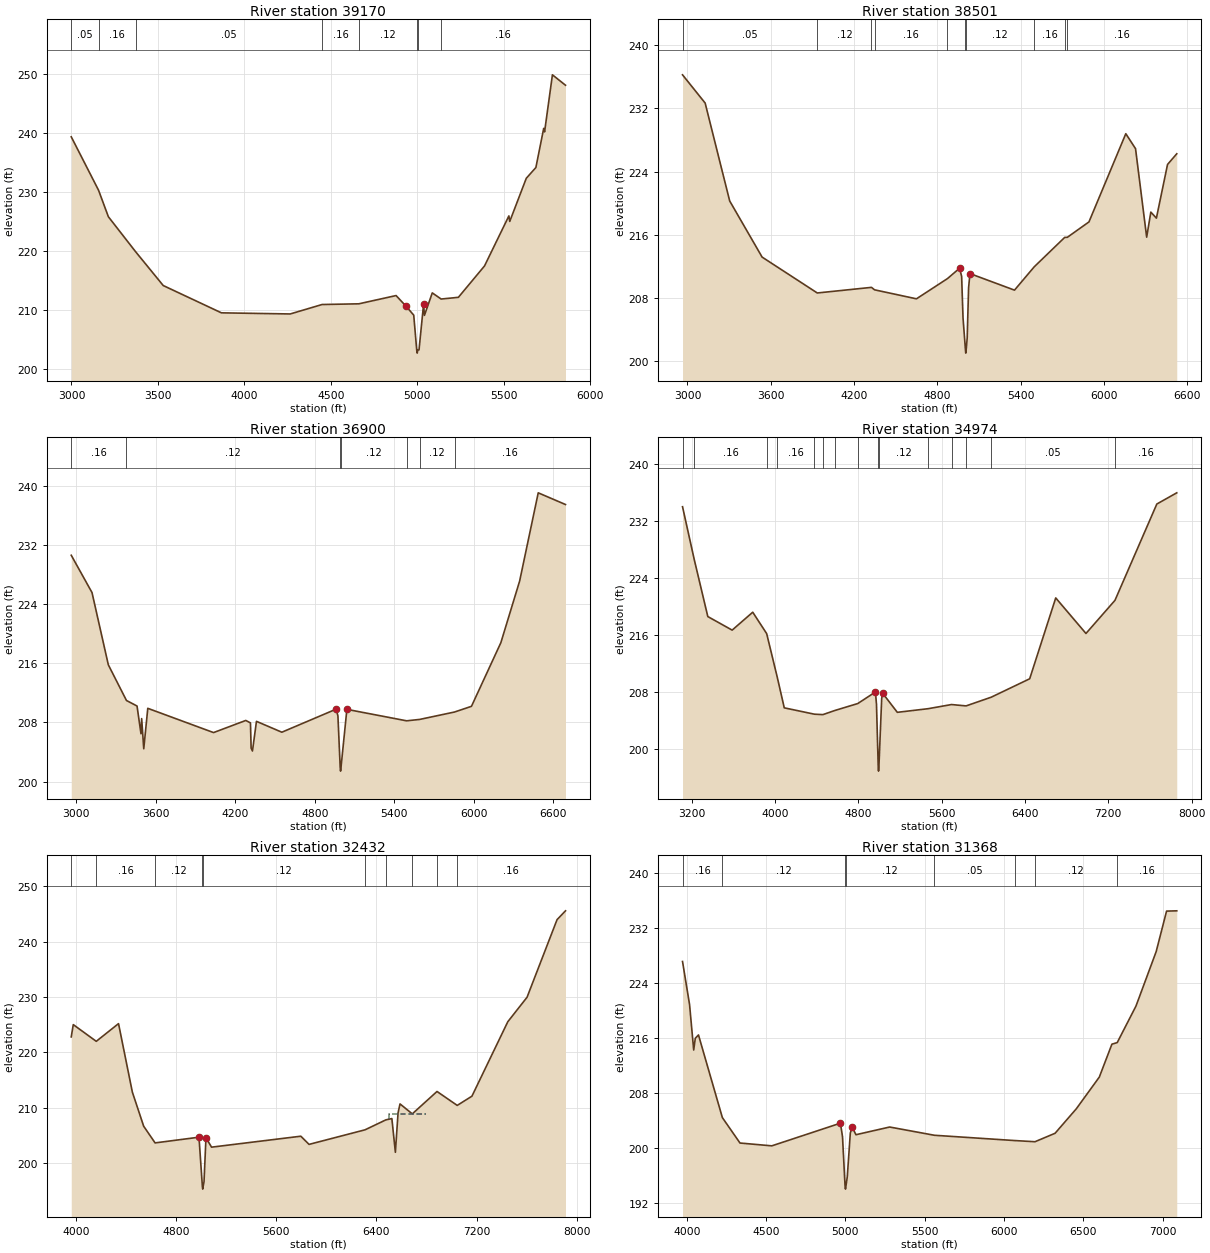
Type RM Length L Ch R = 1 ,39170   ,669,669,669
BEGIN DESCRIPTION:
PEACH CREEK SOUTH 34.0
END DESCRIPTION:
XS GIS Cut Line= 3
      3589842.12      10172241.6      3590512.78     10170658.43
      3590742.12     10169541.59
#Sta/Elev= 30
  2998.6  239.33  3156.5  230.28  3213.4  225.78  3370.5  219.87  3530.7  214.12
  3867.4  209.49  4265.7   209.3  4449.7   210.9  4662.7  211.02    4878  212.42
  4936.3  210.59  4980.1   209.1  4997.5  203.16  5000.3  202.66  5003.5  203.16
  5010.7  203.21    5037  210.92  5042.1  209.06  5087.4  212.87  5138.8  211.83
  5238.5  212.12  5389.7  217.44  5530.6  225.92  5535.7  224.99  5631.3   232.3
  5686.8  234.12  5732.1  240.76  5737.2  240.17  5782.5  249.84  5858.1  248.08
#Mann= 8 ,-1 , 0
  2998.6     .05       0  3156.5     .16       0  3370.5     .05       0
  4449.7     .16       0  4662.7     .12       0  4997.5     .07       0
  5003.5     .12       0  5138.8     .16       0
Bank Sta=4936.3,5037
XS Rating Curve= 0 ,0
Exp/Cntr=0.3,0.1

Type RM Length L Ch R = 1 ,38501   ,1601,1601,1601
BEGIN DESCRIPTION:
PEACH CREEK SOUTH 33.0
END DESCRIPTION:
XS GIS Cut Line= 3
      3589992.08     10172291.67      3591101.32     10171111.55
       3590976.4     10169175.37
#Sta/Elev= 30
  2964.4  236.26  3127.3  232.69  3304.1   220.3  3537.6   213.2    3935  208.66
  4325.3  209.37  4347.3  209.06  4649.2  207.92  4872.8  210.48  4959.9  211.79
  4974.7  210.77  4984.7  205.53  5001.8  201.55  5004.5  201.05  5007.8  201.55
  5014.8  202.97  5024.8  209.32  5034.8  211.11  5355.5  209.02  5497.6  211.97
  5717.1  215.69  5735.9   215.7  5891.8  217.65  6157.2  228.81  6227.3  226.92
  6307.5  215.72  6337.5  218.89  6377.6  218.13  6457.8  224.92  6524.2  226.27
#Mann= 10 ,-1 , 0
  2964.4     .05       0    3935     .12       0  4325.3     .05       0
  4347.3     .16       0  4872.8     .12       0  5001.8     .07       0
  5007.8     .12       0  5497.6     .16       0  5717.1      .1       0
  5735.9     .16       0
Bank Sta=4959.9,5034.8
XS Rating Curve= 0 ,0
Exp/Cntr=0.3,0.1

Type RM Length L Ch R = 1 ,36900   ,1926,1926,1926
BEGIN DESCRIPTION:
PEACH CREEK SOUTH 32.0
END DESCRIPTION:
XS GIS Cut Line= 3
       3591442.1     10173041.67      3591651.67     10171750.44
      3591950.28     10169347.65
#Sta/Elev= 30
  2962.4   230.6    3119  225.56  3242.2  215.79    3379  210.97  3458.8  210.22
  3488.6  206.47  3493.7  208.52  3509.5  204.44  3539.9  209.91  4036.3  206.63
  4279.4  208.27  4314.7  207.94  4319.7  204.53  4329.8  204.14    4360  208.15
  4551.5  206.68  4961.4   209.8  4974.7  208.88  4991.9  201.92  4994.6  201.42
  4997.9  201.92  5042.3  209.77  5493.3  208.22  5591.9  208.41  5854.7  209.41
  5982.4  210.18  6204.1  218.78    6346  227.12  6486.2  239.04  6691.8  237.46
#Mann= 7 ,-1 , 0
  2962.4     .16       0    3379     .12       0  4991.9     .07       0
  4997.9     .12       0  5493.3     .16       0  5591.9     .12       0
  5854.7     .16       0
Bank Sta=4961.4,5042.3
XS Rating Curve= 0 ,0
Exp/Cntr=0.3,0.1

Type RM Length L Ch R = 1 ,34974   ,2542,2542,2542
BEGIN DESCRIPTION:
PEACH CREEK SOUTH 31.0
END DESCRIPTION:
XS GIS Cut Line= 3
      3592019.72     10173910.16      3592498.89     10172569.89
      3592596.11     10169250.47
#Sta/Elev= 30
  3112.9  234.01  3225.1  226.63  3355.6  218.62  3589.2  216.72    3787  219.23
  3920.6  216.23  4022.1  210.13  4089.5  205.83  4378.6  204.94  4460.5  204.88
  4577.9  205.47  4794.9  206.43  4964.7  208.05  4974.7  206.33  4991.7  197.46
  4994.4  196.96  4997.7  197.46  5024.7  207.15  5034.7  207.86  5174.8   205.2
  5471.1  205.71  5694.8  206.29    5835   206.1  6076.1  207.32  6445.3   209.9
  6695.4  221.23  6985.6  216.25  7263.9  220.89  7665.8  234.39  7857.1  235.96
#Mann= 15 ,-1 , 0
  3112.9     .05       0  3225.1     .16       0  3920.6     .05       0
  4022.1     .16       0  4378.6     .05       0  4460.5     .12       0
  4577.9     .05       0  4794.9     .12       0  4991.7     .07       0
  4997.7     .12       0  5471.1     .16       0  5694.8     .05       0
    5835     .16       0  6076.1     .05       0  7263.9     .16       0
Bank Sta=4964.7,5034.7
XS Rating Curve= 0 ,0
Exp/Cntr=0.3,0.1

Type RM Length L Ch R = 1 ,32432   ,1064,1064,1064
BEGIN DESCRIPTION:
PEACH CREEK SOUTH 30.0
END DESCRIPTION:
XS GIS Cut Line= 3
       3593172.5     10174347.62      3593362.69     10172398.57
      3595075.29     10171382.38
#Sta/Elev= 30
    3961  222.78  3977.1     225  4160.9  221.98  4338.8  225.18  4449.3   212.8
  4539.7  206.63  4631.1  203.61  4981.8  204.64  5008.9  195.75  5011.7  195.25
  5014.9  195.75    5022  196.57  5037.6  204.53  5082.3  202.84  5795.7  204.82
  5861.4  203.34  6309.4  205.98  6474.7  207.77  6523.3  208.01  6551.3  201.91
  6572.7  209.04  6588.3  210.66  6686.5  208.86    6884  212.91  7045.5  210.39
  7163.2  212.06  7449.7  225.52  7603.6  229.95  7843.3  243.98  7910.7  245.58
#Mann= 10 ,-1 , 0
    3961     .05       0  4160.9     .16       0  4631.1     .12       0
  5008.9     .07       0  5014.9     .12       0  6309.4     .05       0
  6474.7     .12       0  6686.5     .16       0    6884     .05       0
  7045.5     .16       0
#XS Ineff= 1 ,-1
 6497.16 6792.61  208.92
Permanent Ineff=
       F
Bank Sta=4981.8,5037.6
XS Rating Curve= 0 ,0
Exp/Cntr=0.3,0.1

Type RM Length L Ch R = 1 ,31368   ,1686,1686,1686
BEGIN DESCRIPTION:
PEACH CREEK SOUTH 29.0
END DESCRIPTION:
XS GIS Cut Line= 3
      3593942.11     10174541.59      3594019.72      10173868.5
       3594892.1     10171591.66
#Sta/Elev= 30
  3973.6  227.17    4018   220.9    4044  214.29  4054.1     216  4074.2  216.48
  4224.8  204.45  4335.9  200.75  4536.6  200.34  4969.1  203.64  4982.2  201.67
  4998.2  194.54  5000.9  194.04  5004.2  194.54  5012.2  195.82  5031.5  202.23
    5044  203.03  5066.9  201.96  5279.6  203.08  5561.4  201.88  6067.3  201.11
  6195.6  200.94  6322.3  202.17  6456.4  205.74  6601.2  210.35  6680.6  215.14
  6714.1  215.37  6832.4  220.69  6959.6  228.61  7025.2  234.51  7089.4  234.55
#Mann= 8 ,-1 , 0
  3973.6     .16       0  4224.8     .12       0  4998.2     .07       0
  5004.2     .12       0  5561.4     .05       0  6067.3     .16       0
  6195.6     .12       0  6714.1     .16       0
Bank Sta=4969.1,5044
XS Rating Curve= 0 ,0
Exp/Cntr=0.3,0.1

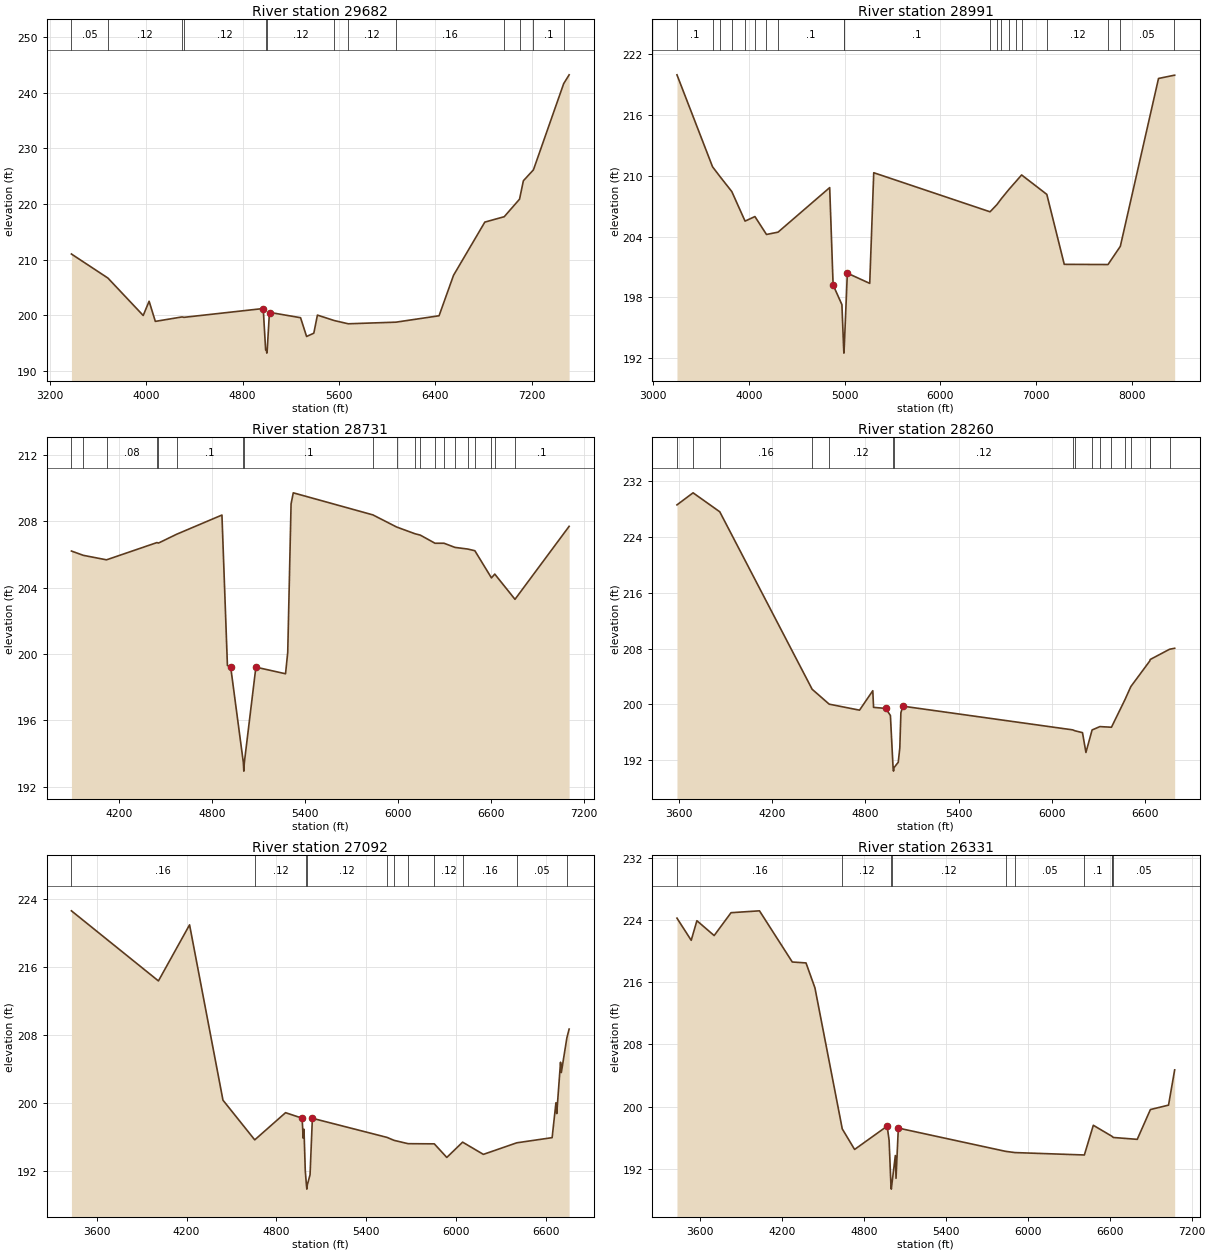
Type RM Length L Ch R = 1 ,29682   ,691,691,691
BEGIN DESCRIPTION:
PEACH CREEK SOUTH 28.0
END DESCRIPTION:
XS GIS Cut Line= 4
      3594561.41     10175493.46      3595130.83     10174604.61
      3595036.05     10174290.75      3595042.11     10171541.61
#Sta/Elev= 30
  3378.1  211.02  3681.2   206.7  3974.1  199.98  4023.2  202.54  4074.8  198.92
  4296.1  199.72    4313  199.65  4970.7  201.23  4990.7  193.79  4997.7  193.72
  5000.4  193.22  5003.7  193.72  5020.7  199.98  5030.7  200.51  5280.7  199.58
  5330.7  196.21  5390.7   196.8  5420.7  200.05  5560.6  199.07  5676.8  198.49
  6072.7  198.78  6430.7  199.93  6550.7  207.19  6810.7  216.75  6971.9  217.72
    7099  220.87  7130.7  224.17  7214.4  226.14  7465.3  241.61  7510.7   243.2
#Mann= 13 ,-1 , 0
  3378.1     .05       0  3681.2     .12       0  4296.1      .1       0
    4313     .12       0  4997.7     .07       0  5003.7     .12       0
  5560.6     .16       0  5676.8     .12       0  6072.7     .16       0
  6971.9     .05       0    7099     .16       0  7214.4      .1       0
  7465.3     .16       0
Bank Sta=4970.7,5030.7
XS Rating Curve= 0 ,0
Exp/Cntr=0.3,0.1

Type RM Length L Ch R = 1 ,28991   ,260,260,260
BEGIN DESCRIPTION:
PEACH CREEK SOUTH 27.0
END DESCRIPTION:
XS GIS Cut Line= 3
      3594610.36     10175547.52      3595568.33     10174312.94
      3598026.99     10171637.84
#Sta/Elev= 30
    3250  219.98  3621.7  210.89  3701.7   209.9  3822.4  208.45  3960.9  205.53
  4063.9  205.98  4184.6  204.21  4305.3  204.44  4844.4  208.84  4880.1  199.22
    4972  197.28    4990  192.99  4992.7  192.49    4996  192.99  5028.7  200.39
  5262.4  199.38  5304.3  210.31  6518.5  206.45  6590.3  207.16  6637.7  207.76
  6719.2   208.7  6790.1  209.46    6848  210.09  7111.2  208.17  7293.3  201.26
  7749.9  201.24  7878.7  203.04  8277.3  219.62  8441.4  219.94    8446  219.94
#Mann= 20 ,-1 , 0
    3250      .1       0  3621.7      .1       0  3701.7     .08       0
  3822.4     .08       0  3960.9      .1       0  4063.9     .15       0
  4184.6      .1       0  4305.3      .1       0    4990     .07       0
    4996      .1       0  6518.5     .15       0  6590.3      .1       0
  6637.7     .15       0  6719.2      .1       0  6790.1     .15       0
    6848     .12       0  7111.2     .12       0  7749.9     .05       0
  7878.7     .05       0  8441.4      .1       0
Bank Sta=4880.1,5028.7
XS Rating Curve= 0 ,0
Exp/Cntr=0.3,0.1

Type RM Length L Ch R = 1 ,28731   ,471,471,471
BEGIN DESCRIPTION:
PEACH CREEK SOUTH 27.1
END DESCRIPTION:
XS GIS Cut Line= 3
      3595179.48     10175139.29        3595735.     10174507.39
      3597332.23     10172757.37
#Sta/Elev= 30
  3891.4  206.21  3968.6  205.95  4117.8  205.68    4443  206.72  4452.9  206.69
  4569.5  207.22  4862.4  208.38  4897.7  199.31  4918.6  199.23  5000.7  193.44
  5003.5  192.94  5006.7  193.44  5081.4  199.21  5272.6  198.81  5286.8   200.1
  5308.4  209.06  5322.6  209.72  5836.1  208.39  5989.1  207.66  6108.5  207.25
  6142.1  207.17    6237  206.68  6295.1  206.68  6365.4  206.43  6448.1  206.33
  6493.9  206.23  6601.1  204.59  6622.4  204.82  6752.9   203.3  7102.1   207.7
#Mann= 20 ,-1 , 0
  3891.4     .08       0  3968.6     .05       0  4117.8     .08       0
    4443      .1       0  4452.9     .12       0  4569.5      .1       0
  5000.7     .07       0  5006.7      .1       0  5836.1     .08       0
  5989.1     .08       0  6108.5      .1       0  6142.1     .08       0
    6237      .1       0  6295.1     .08       0  6365.4      .1       0
  6448.1     .08       0  6493.9      .1       0  6601.1     .08       0
  6622.4      .1       0  6752.9      .1       0
Bank Sta=4918.6,5081.4
XS Rating Curve= 0 ,0
Exp/Cntr=0.3,0.1

Type RM Length L Ch R = 1 ,28260   ,1168,1168,1168
BEGIN DESCRIPTION:
PEACH CREEK SOUTH 25.0
END DESCRIPTION:
XS GIS Cut Line= 3
      3596207.23      10175625.4      3596387.78     10174007.39
      3597401.41      10172806.3
#Sta/Elev= 30
  3588.8  228.63  3692.3  230.36  3863.9  227.64  4457.8  202.17  4567.5  200.03
  4762.4  199.17  4847.7  201.96  4852.7  199.57  4930.8  199.42    4961   198.4
  4978.1  190.92  4980.9  190.42  4984.1  190.92  5011.3  191.69  5021.4  193.74
  5028.4   198.8  5041.5  199.74  6133.2  196.34  6147.3  196.21  6195.9  195.94
    6218   193.1  6257.7  196.33  6307.8  196.81  6382.1  196.72  6468.3  200.65
  6506.6  202.55  6628.8  206.24  6631.1  206.44  6755.6  207.91  6788.5  208.05
#Mann= 17 ,-1 , 0
  3588.8     .16       0  3692.3     .05       0  3863.9     .16       0
  4457.8      .1       0  4567.5     .12       0  4978.1     .07       0
  4984.1     .12       0  6133.2     .08       0  6147.3     .12       0
  6257.7     .08       0  6307.8     .12       0  6382.1     .08       0
  6468.3     .16       0  6506.6     .08       0  6628.8     .16       0
  6631.1     .08       0  6755.6      .1       0
Bank Sta=4930.8,5041.5
XS Rating Curve= 0 ,0
Exp/Cntr=0.3,0.1

Type RM Length L Ch R = 1 ,27092   ,761,761,761
BEGIN DESCRIPTION:
PEACH CREEK SOUTH 24.0
END DESCRIPTION:
XS GIS Cut Line= 3
      3597214.17     10175819.89      3596998.89     10174549.05
      3597686.39     10172632.37
#Sta/Elev= 30
  3431.1  222.64  4012.4  214.39  4220.4  220.99  4443.6  200.35  4655.9  195.68
  4861.8  198.88  4972.3  198.23  4979.5  195.88  4984.8  196.93  4993.5  192.03
  5001.1  190.38  5003.9  189.88  5007.1  190.38  5025.4  191.57  5040.9  198.22
  5539.6  195.97  5586.8  195.62  5680.4  195.23  5855.5  195.21    5939  193.61
  6044.7  195.41  6183.4  193.97    6406  195.33  6642.7  195.94  6668.2  200.05
  6673.5  198.77  6698.9  204.82  6704.2   203.6  6741.1  207.68  6756.3  208.72
#Mann= 11 ,-1 , 0
  3431.1     .16       0  4655.9     .12       0  5001.1     .07       0
  5007.1     .12       0  5539.6     .16       0  5586.8     .12       0
  5680.4     .16       0  5855.5     .12       0  6044.7     .16       0
    6406     .05       0  6741.1      .1       0
Bank Sta=4972.3,5040.9
XS Rating Curve= 0 ,0
Exp/Cntr=0.3,0.1

Type RM Length L Ch R = 1 ,26331   ,732,732,732
BEGIN DESCRIPTION:
PEACH CREEK SOUTH 22.0
END DESCRIPTION:
XS GIS Cut Line= 3
      3597241.95      10175951.8      3597644.72     10174569.89
      3598081.32     10172407.54
#Sta/Elev= 30
  3429.9  224.24  3534.2  221.39  3575.9  223.91  3702.3     222  3825.9  224.94
  4034.2  225.18  4274.6   218.6  4375.1  218.48  4440.4  215.28  4640.7  197.14
  4730.9   194.5  4969.5   197.5  4983.6  195.69  4997.1   189.9  4999.9   189.4
  5003.1   189.9  5029.3  193.72  5034.4  190.79  5051.2  197.25  5836.2  194.26
  5904.5   194.1  6413.8  193.79  6479.4  197.61  6616.2  196.19  6618.4  196.15
  6626.7  196.04  6801.1   195.8  6897.5  199.63  7030.3   200.2  7075.3  204.73
#Mann= 10 ,-1 , 0
  3429.9     .16       0  4640.7     .12       0  4997.1     .07       0
  5003.1     .12       0  5836.2      .1       0  5904.5     .05       0
  6413.8      .1       0  6616.2     .05       0  6618.4      .1       0
  6626.7     .05       0
Bank Sta=4969.5,5051.2
XS Rating Curve= 0 ,0
Exp/Cntr=0.3,0.1

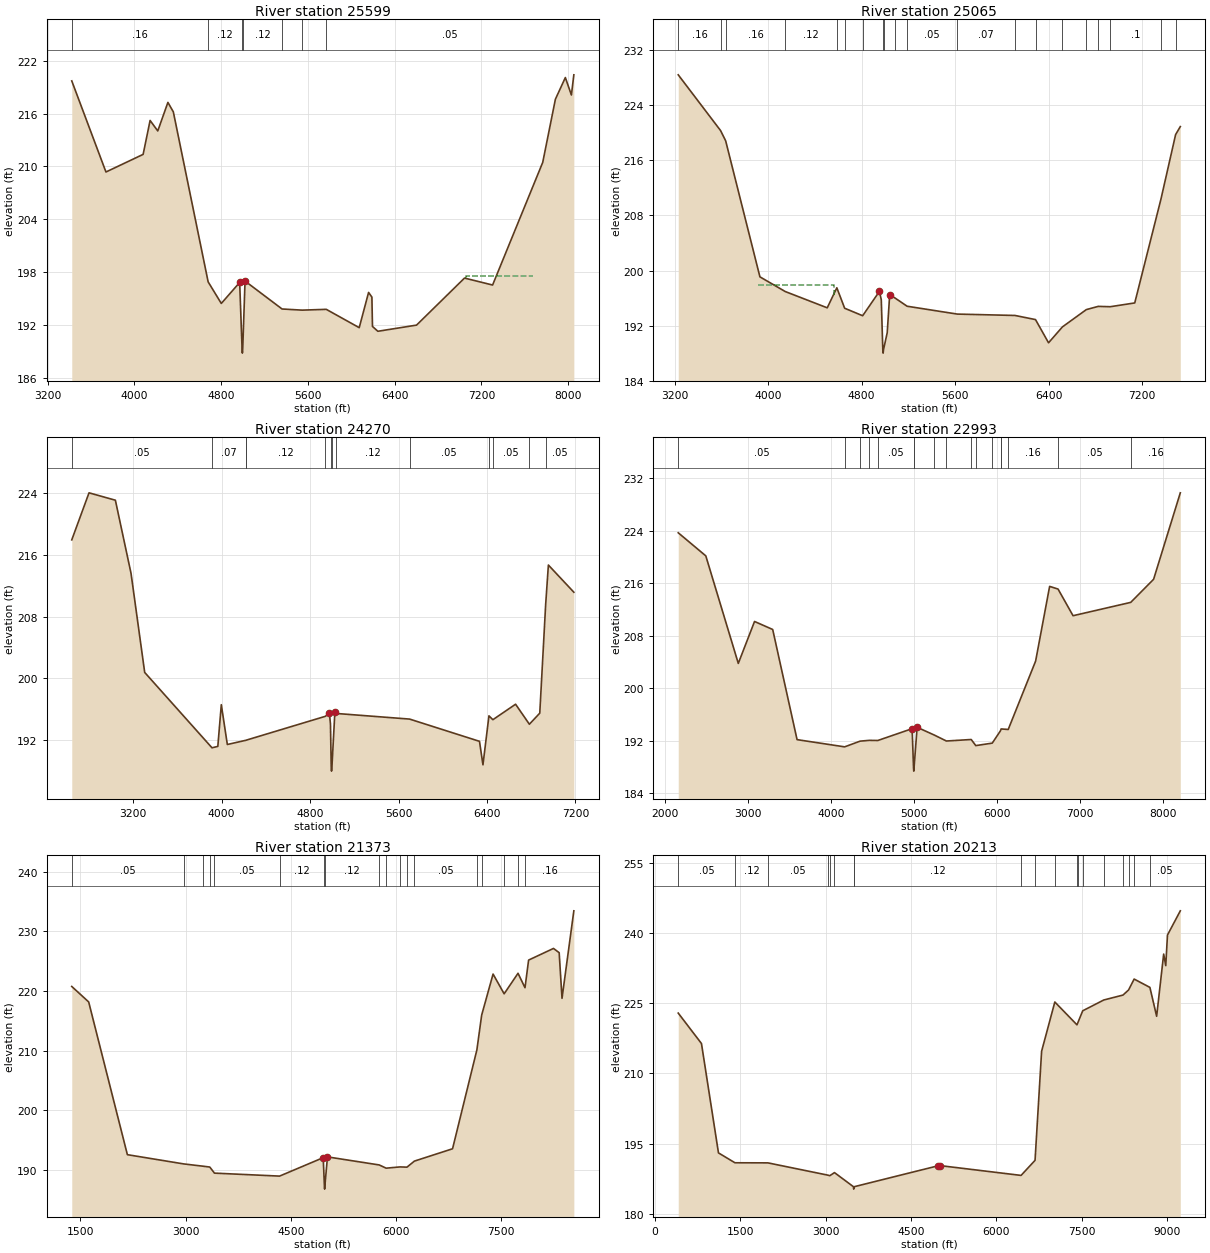
Type RM Length L Ch R = 1 ,25599   ,534,534,534
BEGIN DESCRIPTION:
PEACH CREEK SOUTH 21.0
END DESCRIPTION:
XS GIS Cut Line= 3
      3597366.92      10175958.8      3598214.17     10174854.61
      3599324.61     10171814.76
#Sta/Elev= 30
  3423.4  219.71  3738.5  209.37  4081.2  211.37  4145.5  215.22  4216.2  214.03
  4309.6  217.27  4359.5   216.2  4680.5   196.9  4801.8  194.45  4971.1  196.83
  4993.3  189.31  4996.1  188.81  4999.3  189.31  5020.6  196.99  5361.8  193.82
  5547.1  193.69  5769.5  193.78  6073.1   191.7  6159.4   195.7    6190  195.17
  6195.3  191.84  6244.9  191.29  6601.6  191.99  7043.7  197.33  7302.6  196.54
  7764.7  210.46  7881.5  217.63  7973.2  220.09  8028.9  218.11  8051.5   220.4
#Mann= 7 ,-1 , 0
  3423.4     .16       0  4680.5     .12       0  4993.3     .07       0
  4999.3     .12       0  5361.8      .1       0  5547.1     .12       0
  5769.5     .05       0
#XS Ineff= 1 ,-1
 7056.82 7670.45  197.52
Permanent Ineff=
       F
Bank Sta=4971.1,5020.6
XS Rating Curve= 0 ,0
Exp/Cntr=0.3,0.1

Type RM Length L Ch R = 1 ,25065   ,795,795,795
BEGIN DESCRIPTION:
PEACH CREEK SOUTH 20.0
END DESCRIPTION:
XS GIS Cut Line= 3
      3597942.09     10176291.68      3598792.11     10174741.64
       3599592.1     10172341.67
#Sta/Elev= 30
  3230.6  228.42  3593.2  220.32  3636.7  218.83  3929.7  199.08    4146  196.95
    4506  194.58  4588.2  197.49  4655.1  194.52  4809.3  193.43  4952.8  196.97
  4968.6  195.75  4981.7   188.5  4984.4     188  4987.7   188.5  5019.5  190.97
  5040.6  196.49  5087.5  195.99  5189.7  194.81    5619  193.67  6113.5  193.47
  6288.8  192.87  6400.4   189.5  6519.2  191.81  6723.7  194.32    6826  194.79
  6928.2  194.74  7138.2  195.29  7362.8  210.39    7488  219.74  7528.2   220.9
#Mann= 20 ,-1 , 0
  3230.6     .16       0  3593.2      .1       0  3636.7     .16       0
    4146     .12       0  4588.2     .05       0  4655.1     .12       0
  4809.3     .05       0  4981.7     .04       0  4987.7     .05       0
  5087.5     .07       0  5189.7     .05       0    5619     .07       0
  6113.5     .05       0  6288.8     .12       0  6519.2     .05       0
  6723.7      .1       0    6826     .05       0  6928.2      .1       0
  7362.8     .05       0    7488      .1       0
#XS Ineff= 1 ,-1
 3911.93 4559.66  197.96
Permanent Ineff=
       F
Bank Sta=4952.8,5040.6
XS Rating Curve= 0 ,0
Exp/Cntr=0.3,0.1

Type RM Length L Ch R = 1 ,24270   ,1277,1277,1277
BEGIN DESCRIPTION:
PEACH CREEK SOUTH 18.0
END DESCRIPTION:
XS GIS Cut Line= 4
      3598832.21     10176750.49      3599561.39     10174771.28
      3599533.61     10174215.72      3600096.42     10172427.72
#Sta/Elev= 30
  2645.2  217.96  2801.3  224.07  3039.5  223.11  3181.1  213.61  3304.7  200.74
  3913.2  190.95  3965.9  191.13  3997.4  196.55  4051.9  191.38  4224.3  191.94
  4224.7  191.95  4938.4  195.04  4974.4  195.47  4984.4  194.05  4991.4  188.42
  4994.1  187.92  4997.4  188.42  5024.4  195.61    5037  195.41  5700.1  194.68
  6331.9  191.79  6363.4  188.74  6417.5   195.1  6453.1   194.6  6658.4  196.61
  6783.1  194.01  6877.1  195.45  6930.3  209.54    6955  214.69  7185.2  211.16
#Mann= 13 ,-1 , 0
  2645.2     .05       0  3913.2     .07       0  4224.3     .05       0
  4224.7     .12       0  4938.4     .05       0  4991.4     .03       0
  4997.4     .05       0    5037     .12       0  5700.1     .05       0
  6417.5      .1       0  6453.1     .05       0  6783.1      .1       0
  6930.3     .05       0
Bank Sta=4974.4,5024.4
XS Rating Curve= 0 ,0
Exp/Cntr=0.3,0.1

Type RM Length L Ch R = 1 ,22993   ,1620,1620,1620
BEGIN DESCRIPTION:
PEACH CREEK SOUTH 16.0
END DESCRIPTION:
XS GIS Cut Line= 4
       3599658.6     10176806.03      3600700.28     10174500.44
      3600485.15     10172596.89      3600571.81     10170989.98
#Sta/Elev= 30
  2155.6  223.68  2488.1  220.16  2879.9  203.77  3075.8  210.16  3294.8  208.94
  3588.7  192.15  4162.5  191.05  4349.1  191.92  4459.9  192.04  4562.6  192.02
  4976.1  193.82  4993.4  187.85  4996.1  187.35  4999.4  187.85  5036.6  194.03
  5243.4  192.85  5389.4  191.94  5688.8  192.17  5744.1  191.24  5942.8  191.62
  6042.2  193.51    6050  193.78  6135.1   193.7  6465.6  204.12  6634.6  215.51
  6736.1   215.1    6917  211.04  7612.4  213.07  7888.4  216.59  8210.5  229.77
#Mann= 17 ,-1 , 0
  2155.6     .05       0  4162.5     .12       0  4349.1     .05       0
  4459.9      .1       0  4562.6     .05       0  4993.4     .03       0
  4999.4     .05       0  5243.4     .12       0  5389.4     .05       0
  5688.8      .1       0  5744.1     .07       0  5942.8     .12       0
  6042.2     .16       0    6050     .12       0  6135.1     .16       0
  6736.1     .05       0  7612.4     .16       0
Bank Sta=4976.1,5036.6
XS Rating Curve= 0 ,0
Exp/Cntr=0.3,0.1

Type RM Length L Ch R = 1 ,21373   ,1160,1160,1160
BEGIN DESCRIPTION:
PEACH CREEK SOUTH 15.0
END DESCRIPTION:
XS GIS Cut Line= 3
       3599792.1     10176691.65      3601856.53     10174384.12
        3602516.     10170375.22
#Sta/Elev= 30
  1376.8  220.76    1618  218.17  2169.7  192.59    2974  191.04  3248.1  190.66
  3344.4  190.52  3411.4   189.5  4339.7     189    4962  192.09  4979.3  187.32
    4982  186.82  4985.3  187.32  5022.8  192.22  5760.5  190.87  5859.5  190.33
  6057.4  190.54  6156.4   190.5    6262  191.51  6806.4  193.58  7153.1  210.13
  7221.4  215.96  7384.1  222.84  7541.9  219.53  7739.9  222.97  7839.3  220.55
  7890.8  225.18  8245.5  227.13  8326.6  226.42  8367.1  218.78  8535.8  233.43
#Mann= 18 ,-1 , 0
  1376.8     .05       0    2974     .12       0  3248.1     .05       0
  3344.4     .12       0  3411.4     .05       0  4339.7     .12       0
  4979.3     .07       0  4985.3     .12       0  5760.5     .16       0
  5859.5     .05       0  6057.4     .16       0  6156.4     .12       0
    6262     .05       0  7153.1      .1       0  7221.4     .05       0
  7541.9     .16       0  7739.9      .1       0  7839.3     .16       0
Bank Sta=4962,5022.8
XS Rating Curve= 0 ,0
Exp/Cntr=0.3,0.1

Type RM Length L Ch R = 1 ,20213   ,13514,13514,13514
BEGIN DESCRIPTION:
PEACH CREEK SOUTH 13.0
END DESCRIPTION:
XS GIS Cut Line= 3
      3599842.09     10176891.65      3602837.43     10175132.82
      3603080.46     10169786.09
#Sta/Elev= 30
   406.3   222.9   814.6   216.4  1113.7  193.03  1403.3  190.92  1982.4   190.9
  3035.3  188.28  3070.6  188.16    3153  188.82    3488  185.79  3490.7  185.29
    3494  185.79  4975.5  190.28  5012.2  190.31  6432.9  188.22  6678.6  191.44
    6794  214.75  7026.4  225.27  7415.8  220.39  7428.9  220.78  7516.4  223.39
  7887.1   225.7  8224.3  226.75  8322.5  227.84  8420.7  230.17  8697.6  228.39
  8816.1  222.22  8939.6  235.51  8976.3  233.04  9006.3  239.57  9232.1  244.75
#Mann= 19 ,-1 , 0
   406.3     .05       0  1403.3     .12       0  1982.4     .05       0
  3035.3     .12       0  3070.6     .05       0    3153     .12       0
    3488     .07       0    3494     .12       0  6432.9     .05       0
  6678.6     .16       0  7026.4     .05       0  7415.8      .1       0
  7428.9     .05       0  7516.4     .16       0  7887.1     .05       0
  8224.3      .1       0  8322.5     .16       0  8420.7      .1       0
  8697.6     .05       0
Bank Sta=4975.5,5012.2
XS Rating Curve= 0 ,0
Exp/Cntr=0.3,0.1

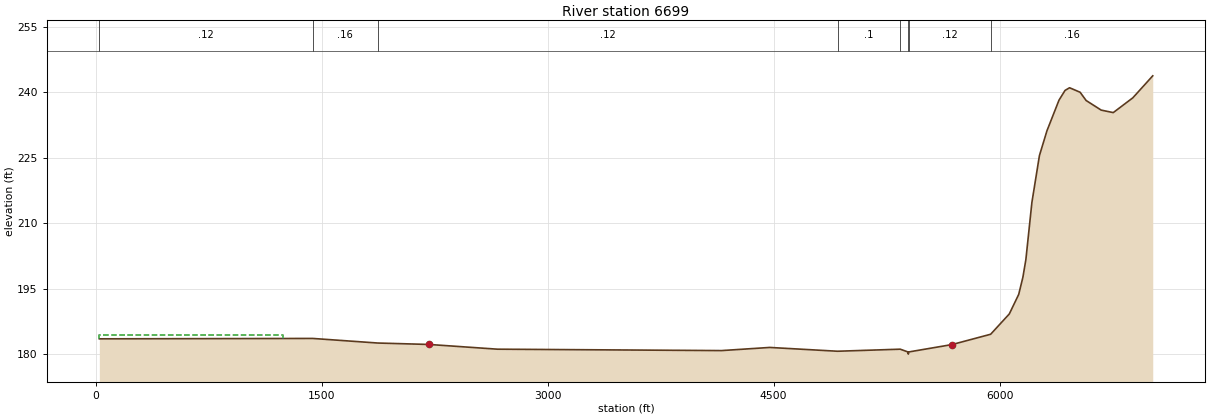
Type RM Length L Ch R = 1 ,6699    ,0,0,0
BEGIN DESCRIPTION:
PEACH CREEK SOUTH 1.0
END DESCRIPTION:
XS GIS Cut Line= 3
      3609946.39      10177544.7      3610902.08     10174008.63
       3610854.3     10170679.61
#Sta/Elev= 30
    24.6  183.57  1441.1  183.66  1872.7  182.61  2215.3  182.28    2668   181.2
  4154.6  180.88  4474.6   181.6  4924.6  180.73  5340.9   181.2  5391.7  180.57
  5394.5  180.07  5397.7  180.57  5684.7  182.26    5941  184.62  6064.8  189.27
  6127.2  193.74  6154.8  197.64  6174.8  201.71  6214.8  214.81  6264.8  225.53
  6314.8  231.21  6394.8  238.22  6434.8  240.44  6464.8  241.05  6534.8  240.02
  6574.8  238.13  6674.8  235.93  6754.8  235.36  6884.9  238.75  7016.9  243.78
#Mann= 8 ,-1 , 0
    24.6     .12       0  1441.1     .16       0  1872.7     .12       0
  4924.6      .1       0  5340.9     .12       0  5391.7     .07       0
  5397.7     .12       0    5941     .16       0
#XS Ineff= 1 ,-1
    9.09 1245.45  184.47
Permanent Ineff=
       F
Bank Sta=2215.3,5684.7
XS Rating Curve= 0 ,0
Exp/Cntr=0.3,0.1
Stream Node=PEACH CREEK SOUT,Reach-1         , 0 , 0 ,Upstream end
Stream Node=PEACH CREEK SOUT,Reach-1         , 0 , 1 ,Downstream end

Chan Stop Cuts=-1
Use User Specified Reach Order=0
Composite Channel Slope=5