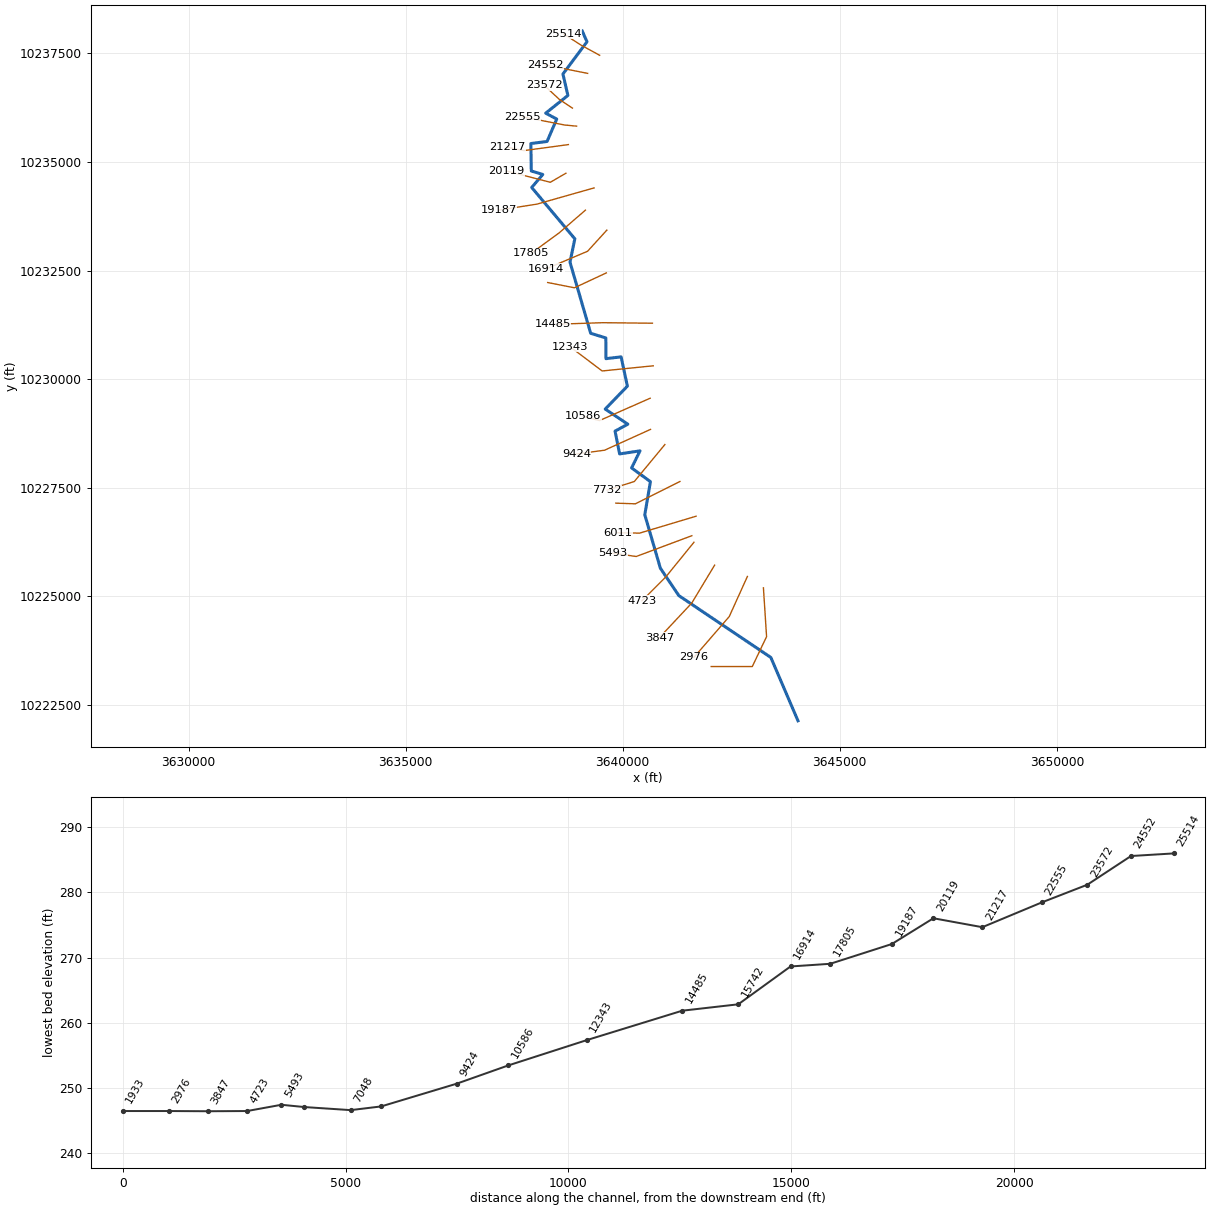
--- PLUM CREEK.prj (project) ---

Proj Title=PLUM CREEK Base Level Engineering
Current Plan=p01
Default Exp/Contr=0.3,0.1
English Units
Geom File=g01
Flow File=f01
Plan File=p01
Y Axis Title=Elevation
X Axis Title(PF)=Main Channel Distance
X Axis Title(XS)=Station
BEGIN DESCRIPTION:
PLUM CREEK
END DESCRIPTION:
DSS Export Rating Curves= 0
DSS Export Rating Curve Sorted= 0
DSS Export Volume Flow Curves= 0
DXF OffsetX= 0
DXF OffsetY= 0
DXF ScaleX= 1
DXF ScaleY= 10

--- PLUM CREEK.p01 (plan) ---

Plan Title=Multiple Run
Short Identifier=Multiple
Geom File=g01
Flow File=f01
Subcritical Flow
K Sum by GR= 0
Std Step Tol= 0.01
Critical Tol= 0.01
Num of Std Step Trials= 20
Max Error Tol= 0.3
Flow Tol Ratio= 0.001
Split Flow NTrial= 30
Split Flow Tol= 0.02
Split Flow Ratio= 0.02
Log Output Level= 0
Friction Slope Method= 1
Unsteady Friction Slope Method= 2
Unsteady Bridges Friction Slope Method= 1
Parabolic Critical Depth
Global Vel Dist=  1 , 1 , 1
Global Log Level= 0
CheckData=True
Encroach Param= -1, 0, 0, 0
BEGIN DESCRIPTION:
Multiple Run
END DESCRIPTION:

--- PLUM CREEK.f01 (steady flow) ---

Flow Title=Multiple
Program Version=4.10
Number of Profiles= 7
Profile Names=10-year,25-year,50-year,1pct_min,100-year,1pct_plu,500-year
River Rch & RM=PLUM CREEK,Reach-1         ,25514
     418     547     649     564     763    1032    1057
River Rch & RM=PLUM CREEK,Reach-1         ,24552
     808    1092    1324    1174    1588    2148    2290
River Rch & RM=PLUM CREEK,Reach-1         ,14485
    1063    1455    1779    1589    2149    2906    3143
River Rch & RM=PLUM CREEK,Reach-1         ,12343
    1063    1455    1779    1589    2149    2906    3143
River Rch & RM=PLUM CREEK,Reach-1         ,7732
    1273    1753    2152    1930    2610    3530    3846
River Rch & RM=PLUM CREEK,Reach-1         ,3847
    1279    1759    2157    1931    2612    3533    3839
Boundary for River Rch & Prof#=PLUM CREEK,Reach-1         , 1
Up Type= 0
Dn Type= 3
Dn Slope=0.005
Boundary for River Rch & Prof#=PLUM CREEK,Reach-1         , 2
Up Type= 0
Dn Type= 3
Dn Slope=0.005
Boundary for River Rch & Prof#=PLUM CREEK,Reach-1         , 3
Up Type= 0
Dn Type= 3
Dn Slope=0.005
Boundary for River Rch & Prof#=PLUM CREEK,Reach-1         , 4
Up Type= 0
Dn Type= 3
Dn Slope=0.005
Boundary for River Rch & Prof#=PLUM CREEK,Reach-1         , 5
Up Type= 0
Dn Type= 3
Dn Slope=0.005
Boundary for River Rch & Prof#=PLUM CREEK,Reach-1         , 6
Up Type= 0
Dn Type= 3
Dn Slope=0.005
Boundary for River Rch & Prof#=PLUM CREEK,Reach-1         , 7
Up Type= 0
Dn Type= 3
Dn Slope=0.005
DSS Import GetInterval= 0
DSS Import GetPeak= 0
DSS Import FillOption= 0

--- PLUM CREEK.g01 (geometry) ---

Geom Title=Existing Conditions
Program Version=4.10

River Reach=PLUM CREEK      ,Reach-1
Reach XY= 30
      3639067.78     10238019.36      3639178.06     10237770.03
      3638623.47     10237027.07      3638738.18      10236533.9
      3638226.96     10236124.92      3638481.06      10235989.5
       3638258.8     10235473.87      3637885.26     10235425.85
      3637894.72     10234793.63      3638159.63     10234713.01
      3637904.46     10234413.57      3638897.97     10233231.16
      3638786.55     10232692.95      3639263.01     10231054.87
      3639612.11     10230947.05      3639615.01     10230470.27
       3639963.7     10230512.34      3640108.15     10229837.34
      3639597.72     10229308.69      3640118.69     10228960.88
      3639824.56     10228801.42      3639929.37     10228276.14
      3640400.03     10228347.23      3640204.99     10227953.61
      3640639.27     10227637.42      3640509.49     10226875.65
      3640868.48     10225642.63      3641294.77     10225011.25
      3643412.83     10223587.64      3644037.83     10222129.31

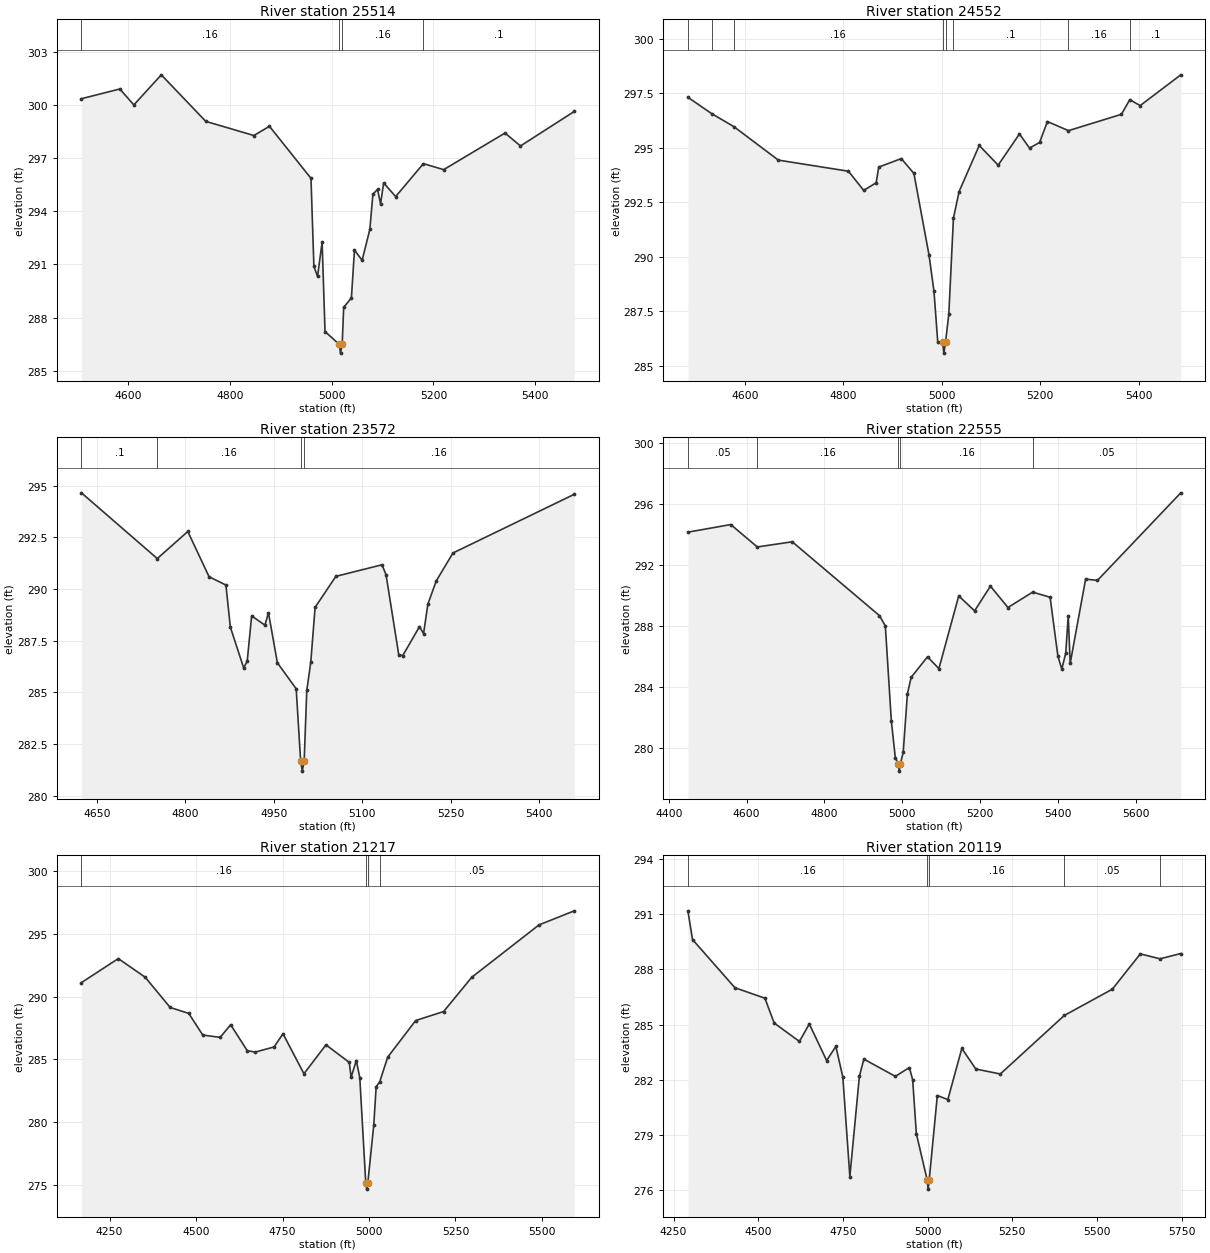
Type RM Length L Ch R = 1 ,25514   ,962,962,962
BEGIN DESCRIPTION:
PLUM CREEK 41.0
END DESCRIPTION:
XS GIS Cut Line= 3
      3639470.04     10237458.68      3639042.11     10237691.64
      3638636.91     10237953.35
#Sta/Elev= 30
  4507.5  300.37    4583  300.92  4610.6  300.02  4664.6  301.72  4752.1  299.09
  4846.7  298.29  4877.4  298.81  4959.1  295.87  4964.8   290.9    4972  290.33
    4981  292.27  4986.7  287.21  5014.5  286.49  5017.2  285.99  5020.5  286.49
  5023.4  288.58  5038.6  289.11  5044.6  291.81  5059.7  291.24  5074.9  292.99
  5080.9  294.98    5090  295.24    5096  294.43    5102  295.61  5125.7  294.84
  5180.2   296.7  5220.1  296.36  5340.8  298.43  5371.2   297.7  5477.1  299.65
#Mann= 4 ,-1 , 0
  4507.5     .16       0  5014.5     .07       0  5020.5     .16       0
  5180.2      .1       0
Bank Sta=5014.5,5020.5
XS Rating Curve= 0 ,0
Exp/Cntr=0.3,0.1

Type RM Length L Ch R = 1 ,24552   ,980,980,980
BEGIN DESCRIPTION:
PLUM CREEK 39.0
END DESCRIPTION:
XS GIS Cut Line= 3
      3639192.26     10237042.01      3638692.11     10237141.64
      3638211.38     10237241.66
#Sta/Elev= 30
  4484.2  297.32  4532.5  296.57  4577.2  295.98  4667.9  294.44  4810.3  293.93
  4841.2  293.05  4866.5   293.4  4871.8  294.12  4917.6  294.51  4943.2  293.83
  4973.8   290.1    4984  288.42  4991.6  286.11  5001.4  286.09  5004.1  285.59
  5007.4  286.09  5014.1  287.38  5023.5  291.78    5035     293  5075.9  295.11
  5114.3  294.21  5157.6  295.64    5178  294.99  5198.5  295.25  5214.4  296.21
  5257.1  295.79  5364.7  296.54  5381.6  297.21  5402.8  296.94  5485.2  298.35
#Mann= 8 ,-1 , 0
  4484.2     .16       0  4532.5      .1       0  4577.2     .16       0
  5001.4     .07       0  5007.4     .16       0  5023.5      .1       0
  5257.1     .16       0  5381.6      .1       0
Bank Sta=5001.4,5007.4
XS Rating Curve= 0 ,0
Exp/Cntr=0.3,0.1

Type RM Length L Ch R = 1 ,23572   ,1017,1017,1017
BEGIN DESCRIPTION:
PLUM CREEK 37.0
END DESCRIPTION:
XS GIS Cut Line= 3
      3638842.07     10236241.67      3638542.11     10236441.64
      3638194.01     10236764.23
#Sta/Elev= 30
    4624  294.65  4752.5  291.47  4804.2  292.78  4840.3  290.59  4868.8  290.19
  4876.3  288.16  4898.9  286.18  4904.9  286.51  4912.4   288.7  4934.9  288.25
  4940.9  288.85    4956  286.43  4987.9  285.17  4995.4  281.69  4998.2  281.19
  5001.4  281.69  5005.8  285.09  5012.6  286.46  5019.9  289.11  5055.1  290.61
  5133.3  291.17  5140.1  290.69  5161.7  286.81  5168.5  286.78  5196.8  288.18
  5203.7  287.84    5211  289.27  5225.2  290.39  5253.5  291.74  5459.1  294.58
#Mann= 4 ,-1 , 0
    4624      .1       0  4752.5     .16       0  4995.4     .07       0
  5001.4     .16       0
Bank Sta=4995.4,5001.4
XS Rating Curve= 0 ,0
Exp/Cntr=0.3,0.1

Type RM Length L Ch R = 1 ,22555   ,1338,1338,1338
BEGIN DESCRIPTION:
PLUM CREEK 35.0
END DESCRIPTION:
XS GIS Cut Line= 3
      3638939.02     10235826.37      3638662.77     10235852.77
      3637692.08     10236041.65
#Sta/Elev= 30
  4449.3  294.16  4559.5  294.66  4627.6  293.19  4717.4  293.53  4941.4  288.69
  4956.6  288.01    4972  281.79  4982.2  279.38  4989.4  278.99  4992.1  278.49
  4995.4  278.99  5002.5  279.72  5013.3  283.55  5022.9  284.64    5065  285.99
  5094.2  285.21  5145.2  289.98  5185.9     289  5226.7  290.62  5271.6  289.22
  5335.2  290.23    5380  289.89  5399.9  286.04    5410  285.18  5420.2  286.24
  5426.5  288.69  5431.6  285.56  5471.2  291.08  5501.7     291  5715.7  296.74
#Mann= 5 ,-1 , 0
  4449.3     .05       0  4627.6     .16       0  4989.4     .07       0
  4995.4     .16       0  5335.2     .05       0
Bank Sta=4989.4,4995.4
XS Rating Curve= 0 ,0
Exp/Cntr=0.3,0.1

Type RM Length L Ch R = 1 ,21217   ,1098,1098,1098
BEGIN DESCRIPTION:
PLUM CREEK 34.0
END DESCRIPTION:
XS GIS Cut Line= 3
      3638749.61     10235401.39      3637725.27     10235262.49
      3637342.08     10235341.65
#Sta/Elev= 30
  4168.6  291.11  4275.2  293.02  4352.8  291.54  4425.3  289.13  4478.9  288.66
  4519.3  286.94  4569.7  286.75    4600  287.76  4647.9   285.7  4670.7  285.58
  4725.5  285.99  4751.4  287.04  4811.9  283.86  4875.6  286.16  4943.1  284.76
  4948.2  283.57  4963.3  284.91  4973.4  283.55  4990.6  275.18  4993.3  274.68
  4996.6  275.18  5013.8  279.79  5020.7  282.82  5031.3  283.24  5054.1  285.18
  5134.9  288.09  5215.8  288.81  5297.4  291.54  5491.5   295.7  5593.6  296.82
#Mann= 4 ,-1 , 0
  4168.6     .16       0  4990.6     .07       0  4996.6     .16       0
  5031.3     .05       0
Bank Sta=4990.6,4996.6
XS Rating Curve= 0 ,0
Exp/Cntr=0.3,0.1

Type RM Length L Ch R = 1 ,20119   ,932,932,932
BEGIN DESCRIPTION:
PLUM CREEK 33.0
END DESCRIPTION:
XS GIS Cut Line= 3
      3638692.06     10234741.62      3638332.91     10234533.33
       3637326.5      10234793.6
#Sta/Elev= 30
  4292.4  291.18    4306  289.62  4431.1     287  4519.7  286.43    4547  285.08
  4621.5  284.08  4650.7  285.03  4701.9  283.04  4729.1  283.81  4749.7  282.14
  4770.4  276.73  4798.5  282.18  4811.7  283.12  4904.7  282.18    4946  282.66
  4955.8     282  4966.6  279.07  4998.6  276.55  5001.3  276.05  5004.6  276.55
  5028.6  281.14  5059.6  280.92  5100.9   283.7  5142.2  282.58  5214.5  282.31
  5403.2  285.49  5545.1  286.92  5627.7  288.84  5685.9  288.57  5747.1  288.86
#Mann= 5 ,-1 , 0
  4292.4     .16       0  4998.6     .07       0  5004.6     .16       0
  5403.2     .05       0  5685.9     .16       0
Bank Sta=4998.6,5004.6
XS Rating Curve= 0 ,0
Exp/Cntr=0.3,0.1

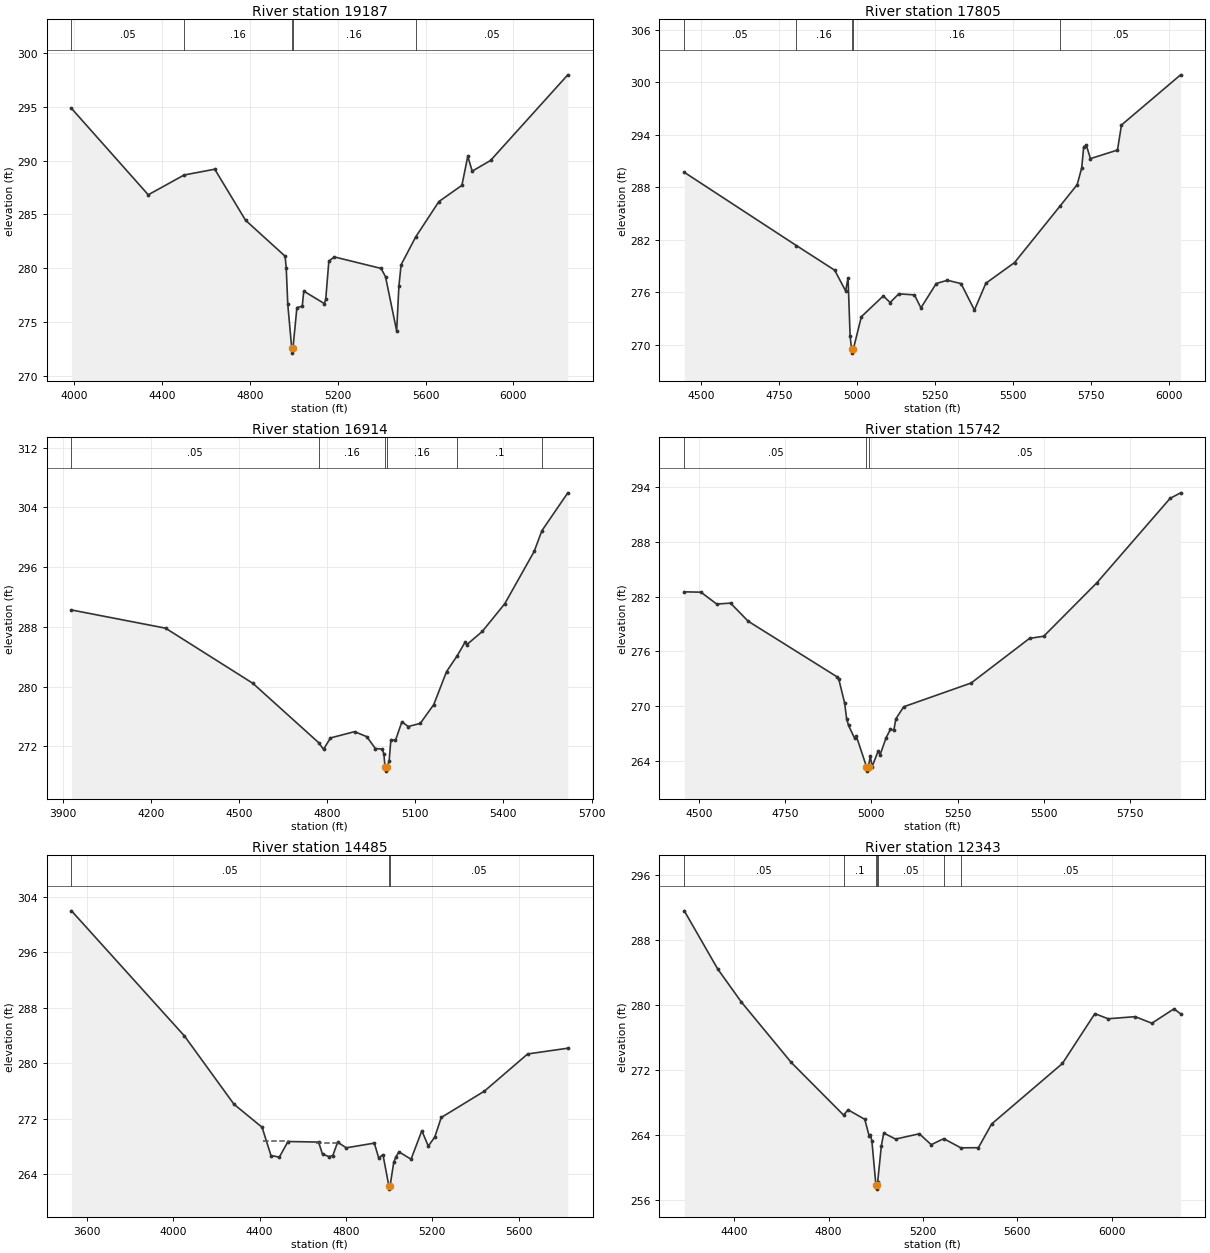
Type RM Length L Ch R = 1 ,19187   ,1382,1382,1382
BEGIN DESCRIPTION:
PLUM CREEK 31.0
END DESCRIPTION:
XS GIS Cut Line= 3
      3639339.81      10234403.1      3638026.87     10234030.49
      3637142.08     10233891.64
#Sta/Elev= 30
    3987  294.87  4336.6  286.83  4499.9  288.67  4639.5  289.21  4779.8  284.46
  4959.8  281.12    4965  280.05  4972.1  276.63  4989.9   272.6  4992.7   272.1
  4995.9   272.6  5013.7  276.34    5038  276.46  5044.9  277.87  5138.4  276.71
  5144.9  277.09  5159.2  280.67    5184  281.05  5397.1  279.98  5417.3   279.2
    5468  274.16  5478.1  278.31  5488.2  280.32  5554.1  282.89  5660.3   286.2
  5765.1  287.71  5791.9  290.41  5812.1  289.03  5895.4  290.02  6247.4  297.99
#Mann= 5 ,-1 , 0
    3987     .05       0  4499.9     .16       0  4989.9     .07       0
  4995.9     .16       0  5554.1     .05       0
Bank Sta=4989.9,4995.9
XS Rating Curve= 0 ,0
Exp/Cntr=0.3,0.1

Type RM Length L Ch R = 1 ,17805   ,891,891,891
BEGIN DESCRIPTION:
PLUM CREEK 29.0
END DESCRIPTION:
XS GIS Cut Line= 3
      3639142.14     10233891.67      3638537.17      10233368.5
      3637898.86     10232901.36
#Sta/Elev= 30
  4446.6  289.72  4805.7  281.36  4928.7  278.54  4963.8  276.17  4971.5  277.68
  4978.1  271.02  4982.7  269.57  4985.5  269.07  4988.7  269.57  5014.2  273.23
  5084.5   275.6  5106.4  274.85  5134.1  275.84  5184.2  275.72  5205.1  274.24
  5254.2  277.02  5289.9  277.39  5333.7  277.01  5376.6  273.99  5413.2  277.05
  5505.1  279.41    5652  285.91  5705.9  288.31  5720.5  290.23  5726.7  292.62
  5735.2  292.82  5748.4  291.28  5835.1  292.26  5847.9  295.12  6037.4  300.85
#Mann= 5 ,-1 , 0
  4446.6     .05       0  4805.7     .16       0  4982.7     .07       0
  4988.7     .16       0    5652     .05       0
Bank Sta=4982.7,4988.7
XS Rating Curve= 0 ,0
Exp/Cntr=0.3,0.1

Type RM Length L Ch R = 1 ,16914   ,1172,1172,1172
BEGIN DESCRIPTION:
PLUM CREEK 25.0
END DESCRIPTION:
XS GIS Cut Line= 3
      3639635.01     10233430.92      3639192.28     10232944.78
      3638242.09     10232541.64
#Sta/Elev= 30
  3929.5  290.26  4249.8  287.82    4547  280.43  4770.6  272.49  4787.6  271.58
  4811.3  273.11  4893.2  273.95  4934.8  273.28  4964.1  271.69  4987.8  271.62
  4993.2  270.92    4997  269.16  4999.8  268.66    5003  269.16  5010.9  269.98
  5016.9  272.88  5032.6  272.79  5054.3  275.27    5076  274.64    5117  275.06
  5162.9  277.58  5206.4     282  5242.8  284.13  5269.8  285.96  5275.3  285.61
    5328  287.38  5404.5  291.09  5504.6   298.1  5531.1  300.89  5619.2  305.96
#Mann= 6 ,-1 , 0
  3929.5     .05       0  4770.6     .16       0    4997     .07       0
    5003     .16       0  5242.8      .1       0  5531.1     .05       0
Bank Sta=4997,5003
XS Rating Curve= 0 ,0
Exp/Cntr=0.3,0.1

Type RM Length L Ch R = 1 ,15742   ,1257,1257,1257
BEGIN DESCRIPTION:
PLUM CREEK 24.0
END DESCRIPTION:
XS GIS Cut Line= 3
      3639623.58     10232445.84      3638888.46     10232102.77
      3638272.17     10232224.29
#Sta/Elev= 30
  4457.3  282.53  4505.6  282.49  4551.4  281.19  4591.4  281.29  4642.8   279.3
  4899.8  273.22  4905.3  272.96  4922.4  270.32  4928.1  268.62  4933.7  267.87
    4951  266.49  4956.5  266.68  4985.6  263.36  4988.4  262.86  4991.6  263.36
  4996.7  264.52  5002.2  263.36  5019.6  265.07  5025.1  264.64  5042.4   266.5
  5054.8  267.43  5065.3  267.38  5070.8  268.59  5093.7  269.92  5289.4  272.53
  5458.5  277.42  5499.8  277.66  5653.8  283.52  5866.2  292.78  5896.7  293.39
#Mann= 3 ,-1 , 0
  4457.3     .05       0  4985.6     .03       0  4991.6     .05       0
Bank Sta=4985.6,4991.6
XS Rating Curve= 0 ,0
Exp/Cntr=0.3,0.1

Type RM Length L Ch R = 1 ,14485   ,2142,2142,2142
BEGIN DESCRIPTION:
PLUM CREEK 23.0
END DESCRIPTION:
XS GIS Cut Line= 3
      3640685.36      10231286.8      3639543.49     10231299.01
      3638386.06     10231260.79
#Sta/Elev= 30
  3528.2  301.97  4051.5  283.95  4281.5   274.1  4411.5  270.79  4452.6  266.72
  4491.5  266.49  4531.5  268.74  4673.3  268.66  4691.5  266.91  4721.6  266.57
  4739.2  266.72  4761.6  268.64  4801.6  267.83  4931.7  268.51  4951.7  266.39
  4971.7  266.84  4998.7  262.38  5001.5  261.88  5004.7  262.38  5021.7  265.75
  5031.7  266.53  5045.8  267.25  5101.8  266.19  5151.8  270.29  5181.8  268.08
  5211.8  269.39  5241.8   272.2  5441.9     276  5642.1  281.35  5828.2  282.18
#Mann= 3 ,-1 , 0
  3528.2     .05       0  4998.7     .03       0  5004.7     .05       0
#XS Ineff= 3 ,-1
 4416.19 4532.67  268.76 4659.09 4765.62  268.57 5151.99 5291.19   270.2
Permanent Ineff=
       F       F       F
Bank Sta=4998.7,5004.7
XS Rating Curve= 0 ,0
Exp/Cntr=0.3,0.1

Type RM Length L Ch R = 1 ,12343   ,1757,1757,1757
BEGIN DESCRIPTION:
PLUM CREEK 22.0
END DESCRIPTION:
XS GIS Cut Line= 3
      3640702.68     10230305.89      3639527.41     10230186.93
      3638792.15     10230741.61
#Sta/Elev= 30
  4188.9  291.61  4330.2  284.47  4430.7  280.39  4641.8  272.96  4863.4  266.49
    4883  267.12  4953.4  265.96  4972.1   263.9  4977.2  264.08  4983.5   263.3
  5000.6  257.87  5003.4  257.37  5006.6  257.87  5007.8  258.19  5023.7  262.71
  5033.8  264.27    5084  263.53  5184.5  264.18  5234.8  262.84    5288  263.58
  5360.4  262.45  5434.7  262.47  5490.9  265.39  5790.6  272.83    5928  278.96
  5984.2  278.33  6098.7  278.59  6169.5  277.78  6263.1  279.55  6291.2  278.94
#Mann= 7 ,-1 , 0
  4188.9     .05       0  4863.4      .1       0  5000.6     .07       0
  5006.6      .1       0  5007.8     .05       0    5288      .1       0
  5360.4     .05       0
Bank Sta=5000.6,5006.6
XS Rating Curve= 0 ,0
Exp/Cntr=0.3,0.1

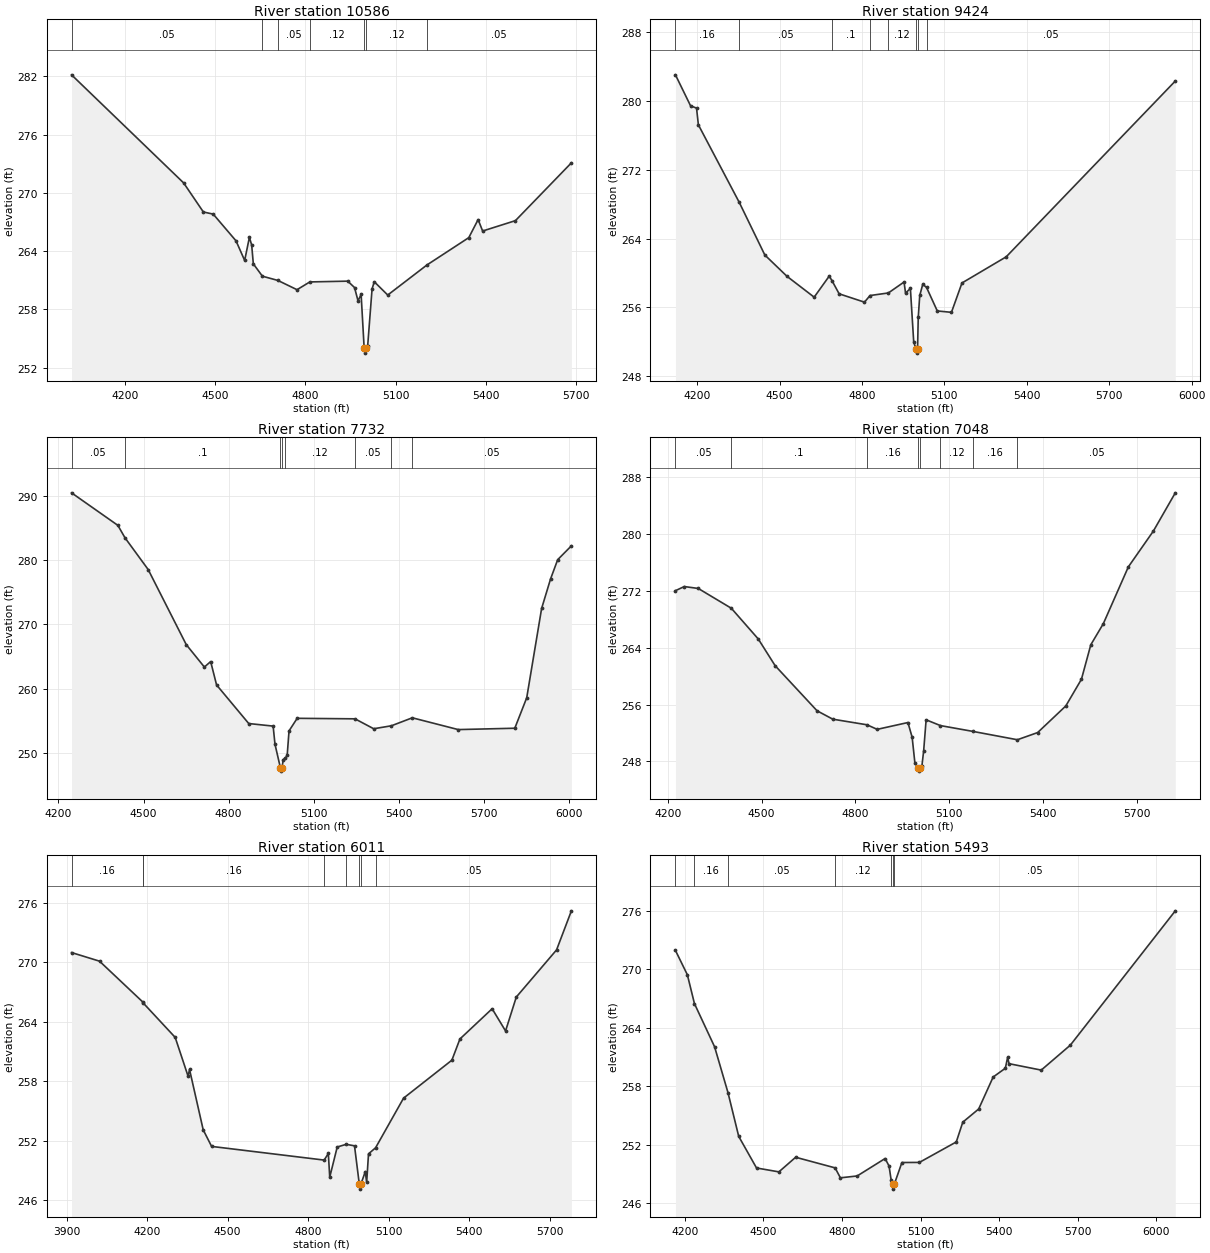
Type RM Length L Ch R = 1 ,10586   ,1162,1162,1162
BEGIN DESCRIPTION:
PLUM CREEK 20.0
END DESCRIPTION:
XS GIS Cut Line= 3
      3640633.23     10229559.36      3639465.01     10229043.91
      3639092.09     10229141.65
#Sta/Elev= 30
  4022.4  282.15  4395.3  271.02  4460.8  268.03  4493.6  267.81  4569.4  265.06
  4598.2  263.04  4613.9  265.42  4621.5  264.63    4627  262.69  4657.2  261.42
  4708.9  260.98  4772.3  260.03  4814.9  260.83    4941  260.91  4963.6  260.25
  4975.2  258.88  4985.5  259.55  4995.6     254  4998.3   253.5  5001.6     254
  5007.3  254.26  5021.9  260.11  5029.2  260.85    5074  259.48  5204.6  262.58
  5343.6  265.39  5374.6  267.25  5389.6  266.07  5498.7  267.14  5684.8  273.09
#Mann= 7 ,-1 , 0
  4022.4     .05       0  4657.2      .1       0  4708.9     .05       0
  4814.9     .12       0  4995.6     .07       0  5001.6     .12       0
  5204.6     .05       0
Bank Sta=4995.6,5001.6
XS Rating Curve= 0 ,0
Exp/Cntr=0.3,0.1

Type RM Length L Ch R = 1 ,9424    ,1692,1692,1692
BEGIN DESCRIPTION:
PLUM CREEK 18.0
END DESCRIPTION:
XS GIS Cut Line= 3
      3640642.09     10228841.63      3639582.91     10228361.45
      3638931.91     10228274.65
#Sta/Elev= 30
  4120.8  283.02  4175.7  279.43  4197.6  279.15  4204.3  277.21    4353  268.21
  4446.2  262.09    4527  259.61  4625.8  257.19  4680.7  259.64  4690.5  259.12
  4716.7  257.58    4809  256.61  4829.1  257.38  4895.9  257.68    4953  258.95
  4958.5  257.66  4976.1  258.21  4988.2  251.99  4996.2  251.19  4998.9  250.69
  5002.2  251.19  5004.7  254.85  5010.2  257.39  5021.1  258.68  5034.8  258.33
    5074  255.59  5125.6  255.43  5163.9  258.84    5325  261.88  5940.5   282.3
#Mann= 8 ,-1 , 0
  4120.8     .16       0    4353     .05       0  4690.5      .1       0
  4829.1     .16       0  4895.9     .12       0  4996.2     .07       0
  5002.2     .12       0  5034.8     .05       0
Bank Sta=4996.2,5002.2
XS Rating Curve= 0 ,0
Exp/Cntr=0.3,0.1

Type RM Length L Ch R = 1 ,7732    ,684,684,684
BEGIN DESCRIPTION:
PLUM CREEK 16.0
END DESCRIPTION:
XS GIS Cut Line= 3
      3640971.77     10228491.62      3640268.67     10227640.96
      3639642.12     10227441.65
#Sta/Elev= 30
  4246.4  290.42  4409.6  285.37  4434.7  283.44  4516.4  278.51  4650.6  266.85
  4714.4  263.37  4736.6  264.22  4757.4  260.59  4870.7   254.6  4956.7   254.2
  4963.2  251.38  4982.4  247.71  4985.2  247.21  4988.4  247.71  4991.9     249
  4999.8  249.23  5006.2  249.68  5012.7  253.46  5041.4  255.41  5245.1  255.33
    5311  253.79  5373.3  254.25    5447  255.49  5608.8  253.66  5808.1  253.87
  5850.1   258.6  5902.6  272.47  5934.1  277.05  5959.2  280.04  6007.5  282.19
#Mann= 8 ,-1 , 0
  4246.4     .05       0  4434.7      .1       0  4982.4     .07       0
  4988.4      .1       0  4999.8     .12       0  5245.1     .05       0
  5373.3     .12       0    5447     .05       0
Bank Sta=4982.4,4988.4
XS Rating Curve= 0 ,0
Exp/Cntr=0.3,0.1

Type RM Length L Ch R = 1 ,7048    ,1037,1037,1037
BEGIN DESCRIPTION:
PLUM CREEK 13.0
END DESCRIPTION:
XS GIS Cut Line= 3
      3641319.02     10227640.97      3640292.65     10227127.14
      3639842.09     10227141.64
#Sta/Elev= 30
  4224.2     272  4252.5  272.58  4297.2  272.31  4402.9  269.53  4489.1  265.21
    4543  261.46  4677.1  255.12  4727.4  253.94  4836.9  253.15  4869.4  252.51
  4967.7  253.47  4981.2   251.4  4990.1  247.74  5000.6  247.14  5003.3  246.64
  5006.6  247.14  5012.4  247.37    5018  249.48  5025.9  253.85  5071.7  253.04
  5174.6  252.23  5317.7  251.05  5382.6  252.06  5472.6   255.8  5522.6  259.55
  5552.6   264.4  5592.7  267.37  5672.7  275.35  5752.7  280.38  5822.8  285.75
#Mann= 8 ,-1 , 0
  4224.2     .05       0  4402.9      .1       0  4836.9     .16       0
  5000.6     .07       0  5006.6     .16       0  5071.7     .12       0
  5174.6     .16       0  5317.7     .05       0
Bank Sta=5000.6,5006.6
XS Rating Curve= 0 ,0
Exp/Cntr=0.3,0.1

Type RM Length L Ch R = 1 ,6011    ,518,518,518
BEGIN DESCRIPTION:
PLUM CREEK 12.0
END DESCRIPTION:
XS GIS Cut Line= 3
      3641692.06     10226841.63       3640390.2     10226451.73
      3639886.87     10226460.41
#Sta/Elev= 30
  3918.7  270.98    4023  270.11  4184.6  265.98  4186.8  265.86  4304.9  262.42
  4353.1  258.49  4358.3  259.19  4409.3  253.09  4440.6  251.42    4860  250.04
  4875.5  250.71  4880.7  248.32  4908.6  251.36    4942  251.63    4973  251.48
  4990.9  247.61  4993.6  247.11  4996.9  247.61  5013.1  248.88  5018.3   247.8
  5025.2  250.67  5051.5  251.28  5155.8  256.29  5335.8  260.12  5365.8  262.26
  5485.8  265.31  5535.8  263.07  5575.8  266.49  5725.9  271.25  5781.1  275.19
#Mann= 8 ,-1 , 0
  3918.7     .16       0  4184.6     .05       0  4186.8     .16       0
    4860     .12       0    4942     .16       0  4990.9     .07       0
  4996.9     .16       0  5051.5     .05       0
Bank Sta=4990.9,4996.9
XS Rating Curve= 0 ,0
Exp/Cntr=0.3,0.1

Type RM Length L Ch R = 1 ,5493    ,770,770,770
BEGIN DESCRIPTION:
PLUM CREEK 10.0
END DESCRIPTION:
XS GIS Cut Line= 3
      3641592.11     10226391.64      3640312.07     10225913.53
      3639775.51     10225991.42
#Sta/Elev= 30
  4164.1  271.95  4209.6  269.45  4236.7  266.49  4313.6  262.06  4364.6  257.37
  4405.7  252.87  4473.7  249.63  4559.1  249.23  4623.1  250.73  4773.8  249.64
  4793.9  248.62    4858  248.81  4964.7   250.6  4979.7  249.83  4987.8  248.38
  4993.7  247.96  4996.5  247.46  4999.7  247.96  5028.8  250.19  5095.5   250.2
  5236.4   252.3  5261.3  254.33  5321.9  255.68  5377.2  258.96  5423.7  259.86
  5432.5  260.98  5437.8  260.33  5560.8  259.67  5671.9  262.23  6072.7  276.01
#Mann= 7 ,-1 , 0
  4164.1     .05       0  4236.7     .16       0  4364.6     .05       0
  4773.8     .12       0  4987.8     .05       0  4993.7     .03       0
  4999.7     .05       0
Bank Sta=4993.7,4999.7
XS Rating Curve= 0 ,0
Exp/Cntr=0.3,0.1

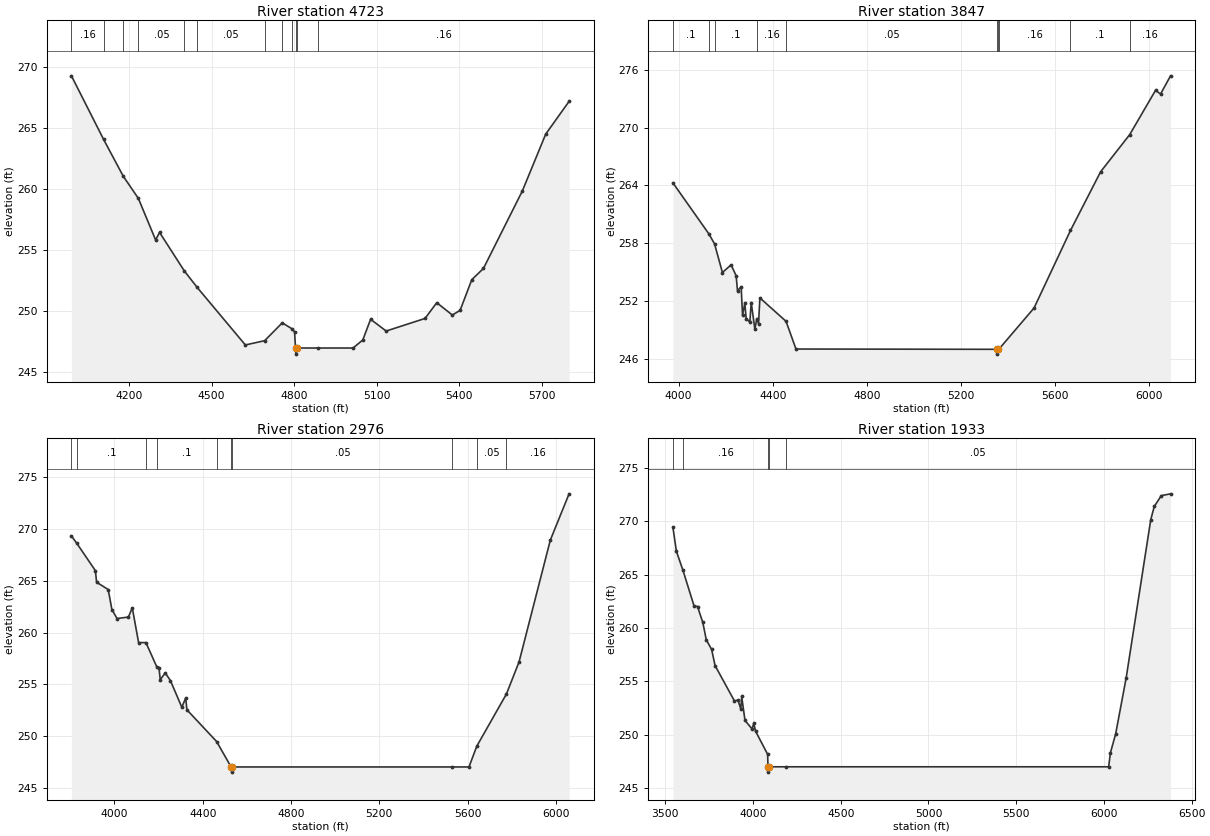
Type RM Length L Ch R = 1 ,4723    ,876,876,876
BEGIN DESCRIPTION:
PLUM CREEK 8.0
END DESCRIPTION:
XS GIS Cut Line= 3
      3641642.08     10226241.61      3640992.11     10225441.64
      3640442.07     10224891.61
#Sta/Elev= 30
  3990.7  269.27  4107.6  264.07  4178.7  261.07    4234  259.24  4296.7  255.84
    4311  256.46  4400.9  253.31  4447.3  251.97  4622.8  247.25  4692.9   247.6
    4757  249.06  4793.9  248.55  4801.7  248.31  4805.1     247  4807.8   246.5
  4811.1     247  4887.7     247  5014.2     247  5049.7  247.66    5078  249.35
  5134.6  248.39    5276  249.42  5318.4  250.71    5375   249.7  5403.3  250.08
  5445.7  252.59  5488.1  253.51  5629.5  259.85  5714.4   264.5  5799.3  267.18
#Mann= 12 ,-1 , 0
  3990.7     .16       0  4107.6     .05       0  4178.7     .16       0
    4234     .05       0  4400.9     .16       0  4447.3     .05       0
  4692.9     .12       0    4757     .05       0  4793.9     .12       0
  4805.1     .07       0  4811.1     .12       0  4887.7     .16       0
Bank Sta=4805.1,4811.1
XS Rating Curve= 0 ,0
Exp/Cntr=0.3,0.1

Type RM Length L Ch R = 1 ,3847    ,871,871,871
BEGIN DESCRIPTION:
PLUM CREEK 6.0
END DESCRIPTION:
XS GIS Cut Line= 3
      3642117.62     10225713.86      3641592.11     10224841.64
      3640842.09     10224041.63
#Sta/Elev= 30
  3975.6  264.27  4128.4  258.97  4152.6  257.93  4186.1  254.95    4223  255.75
  4244.4  254.61  4250.2  253.05  4265.7  253.48  4271.6   250.5  4281.3  251.78
  4287.1  250.15  4302.6  249.82  4308.5  251.83    4324  249.06  4332.2  250.17
  4339.5  249.64  4345.4  252.31  4456.5  249.88  4498.7     247  5351.6  246.97
  5354.4  246.47  5357.6  246.97  5360.5  246.97  5510.4  251.26  5665.3  259.32
  5793.3  265.42    5917  269.28  6026.7  273.88  6048.2   273.5  6090.5  275.39
#Mann= 10 ,-1 , 0
  3975.6      .1       0  4128.4     .16       0  4152.6      .1       0
  4332.2     .16       0  4456.5     .05       0  5351.6    .033       0
  5357.6     .05       0  5360.5     .16       0  5665.3      .1       0
    5917     .16       0
Bank Sta=5351.6,5357.6
XS Rating Curve= 0 ,0
Exp/Cntr=0.3,0.1

Type RM Length L Ch R = 1 ,2976    ,1043,1043,1043
BEGIN DESCRIPTION:
PLUM CREEK 4.0
END DESCRIPTION:
XS GIS Cut Line= 3
      3642872.84     10225453.48      3642454.47     10224529.03
      3641642.13     10223591.67
#Sta/Elev= 30
    3805  269.35  3828.5  268.66  3913.6  265.99  3919.1  264.87  3971.7  264.16
  3988.4  262.23  4011.5  261.36  4063.2   261.5  4080.8  262.39  4109.4  259.03
  4142.7  259.03  4191.7  256.69  4201.8   256.6  4207.3  255.45  4230.4  256.09
  4253.5  255.36  4305.2  252.78  4322.8  253.66  4328.3  252.53    4463  249.46
  4528.5     247  4531.2   246.5  4534.5     247  5530.6     247  5606.6     247
  5641.7     249  5776.3  254.06  5833.6  257.17  5975.1  268.94  6060.1  273.42
#Mann= 10 ,-1 , 0
    3805     .16       0  3828.5      .1       0  4142.7     .05       0
  4191.7      .1       0    4463     .05       0  4528.5    .033       0
  4534.5     .05       0  5530.6      .1       0  5641.7     .05       0
  5776.3     .16       0
Bank Sta=4528.5,4534.5
XS Rating Curve= 0 ,0
Exp/Cntr=0.3,0.1

Type RM Length L Ch R = 1 ,1933    ,0,0,0
BEGIN DESCRIPTION:
PLUM CREEK 1.0
END DESCRIPTION:
XS GIS Cut Line= 4
       3643242.1     10225191.68      3643314.64     10224067.32
      3642985.68     10223378.81      3642039.54     10223378.81
#Sta/Elev= 30
  3543.7  269.46  3563.8  267.19  3601.3   265.4    3664  262.09    3684  262.02
  3714.1  260.53  3734.1  258.89  3764.2  258.01  3784.2  256.48  3894.5  253.17
  3914.5  253.25  3930.8  252.41  3935.8  253.59  3954.6  251.34  3994.7  250.55
  4004.7  251.07  4014.7  250.34  4083.6  248.17  4085.6     247  4088.4   246.5
  4091.6     247  4185.9     247    6027     247    6037  248.31    6067  250.09
    6127  255.35    6267  270.17    6287   271.4    6327  272.41  6379.6  272.58
#Mann= 5 ,-1 , 0
  3543.7      .1       0  3601.3     .16       0  4085.6    .033       0
  4091.6     .16       0  4185.9     .05       0
Bank Sta=4085.6,4091.6
XS Rating Curve= 0 ,0
Exp/Cntr=0.3,0.1

Chan Stop Cuts=-1
Use User Specified Reach Order=0
Composite Channel Slope=5