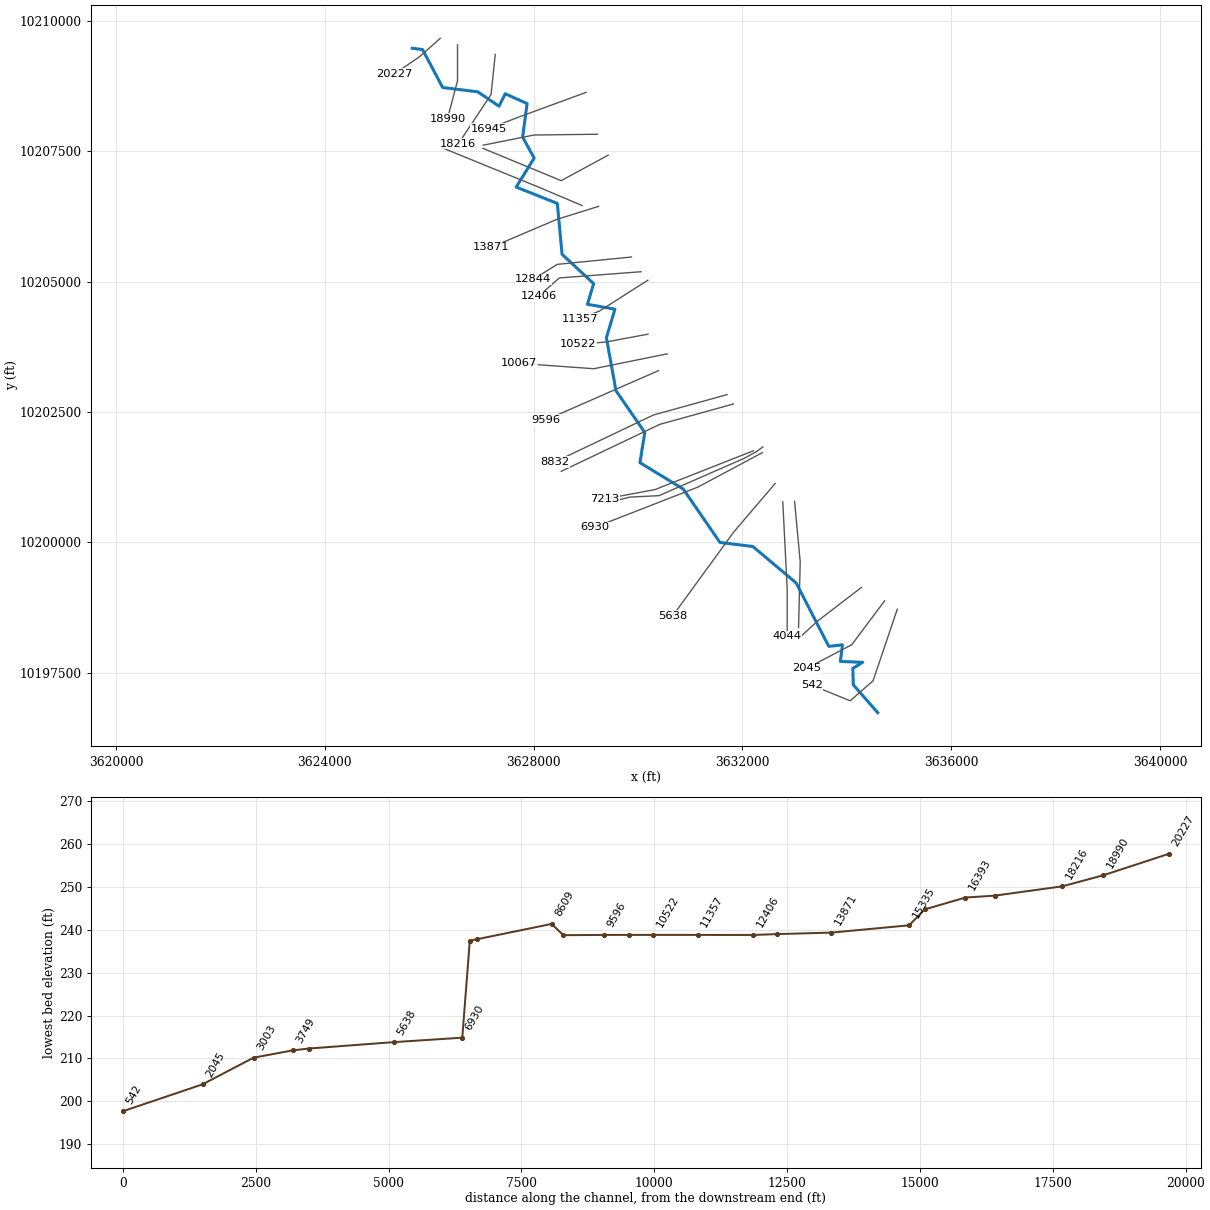
--- ROCK LAKE CREEK.prj (project) ---

Proj Title=ROCK LAKE CREEK Base Level Engineering
Current Plan=p01
Default Exp/Contr=0.3,0.1
English Units
Geom File=g01
Flow File=f01
Plan File=p01
Y Axis Title=Elevation
X Axis Title(PF)=Main Channel Distance
X Axis Title(XS)=Station
BEGIN DESCRIPTION:
ROCK LAKE CREEK
END DESCRIPTION:
DSS Export Rating Curves= 0
DSS Export Rating Curve Sorted= 0
DSS Export Volume Flow Curves= 0
DXF OffsetX= 0
DXF OffsetY= 0
DXF ScaleX= 1
DXF ScaleY= 10

--- ROCK LAKE CREEK.p01 (plan) ---

Plan Title=Multiple Run
Short Identifier=Multiple
Geom File=g01
Flow File=f01
Subcritical Flow
K Sum by GR= 0
Std Step Tol= 0.01
Critical Tol= 0.01
Num of Std Step Trials= 20
Max Error Tol= 0.3
Flow Tol Ratio= 0.001
Split Flow NTrial= 30
Split Flow Tol= 0.02
Split Flow Ratio= 0.02
Log Output Level= 0
Friction Slope Method= 1
Unsteady Friction Slope Method= 2
Unsteady Bridges Friction Slope Method= 1
Parabolic Critical Depth
Global Vel Dist=  1 , 1 , 1
Global Log Level= 0
CheckData=True
Encroach Param= -1, 0, 0, 0
BEGIN DESCRIPTION:
Multiple Run
END DESCRIPTION:

--- ROCK LAKE CREEK.f01 (steady flow) ---

Flow Title=Multiple
Number of Profiles=7
Profile Names=10-year,25-year,50-year,1pct_min,100-year,1pct_plu,500-year
River Rch & RM= ROCK LAKE CREEK,Reach-1,20227
     399     523     621     542     733     991    1019
River Rch & RM= ROCK LAKE CREEK,Reach-1,18990
     908    1242    1517    1356    1834    2480    2685
River Rch & RM= ROCK LAKE CREEK,Reach-1,15335
    1078    1481    1816    1627    2200    2975    3237
River Rch & RM= ROCK LAKE CREEK,Reach-1,9596
    1189    1632    1998    1787    2417    3268    3543
River Rch & RM= ROCK LAKE CREEK,Reach-1,6930
    1529    2137    2650    2399    3244    4387    4874
Boundary for River Rch & Prof#=ROCK LAKE CREEK,Reach-1,1
Up Type=0
Dn Type=3
Dn Slope=0.005
Boundary for River Rch & Prof#=ROCK LAKE CREEK,Reach-1,2
Up Type=0
Dn Type=3
Dn Slope=0.005
Boundary for River Rch & Prof#=ROCK LAKE CREEK,Reach-1,3
Up Type=0
Dn Type=3
Dn Slope=0.005
Boundary for River Rch & Prof#=ROCK LAKE CREEK,Reach-1,4
Up Type=0
Dn Type=3
Dn Slope=0.005
Boundary for River Rch & Prof#=ROCK LAKE CREEK,Reach-1,5
Up Type=0
Dn Type=3
Dn Slope=0.005
Boundary for River Rch & Prof#=ROCK LAKE CREEK,Reach-1,6
Up Type=0
Dn Type=3
Dn Slope=0.005
Boundary for River Rch & Prof#=ROCK LAKE CREEK,Reach-1,7
Up Type=0
Dn Type=3
Dn Slope=0.005

--- ROCK LAKE CREEK.g01 (geometry) ---

Geom Title=Existing Conditions
Program Version=4.10

River Reach=ROCK LAKE CREEK ,Reach-1
Reach XY= 30
      3625674.72     10209475.11       3625873.4     10209448.39
      3626256.71      10208722.5      3626930.42      10208638.8
      3627337.55     10208363.61      3627455.13     10208602.35
      3627875.06     10208413.54      3627789.12     10207770.31
      3628010.48     10207369.27      3627666.33     10206811.82
      3628453.94     10206498.95      3628544.73     10205523.43
      3629149.35     10204960.81      3629031.29     10204564.97
      3629557.33     10204469.49      3629394.14     10203924.35
       3629577.4     10202906.67      3630129.61     10202106.39
      3630036.57     10201527.11      3630866.83     10201020.49
      3631568.87       10199997.      3632200.25     10199918.67
      3633028.99     10199220.65      3633654.15     10198003.31
      3633914.95     10198033.86      3633876.43     10197714.87
      3634304.37     10197698.47       3634114.6     10197580.84
      3634123.16     10197267.13      3634591.59     10196732.16

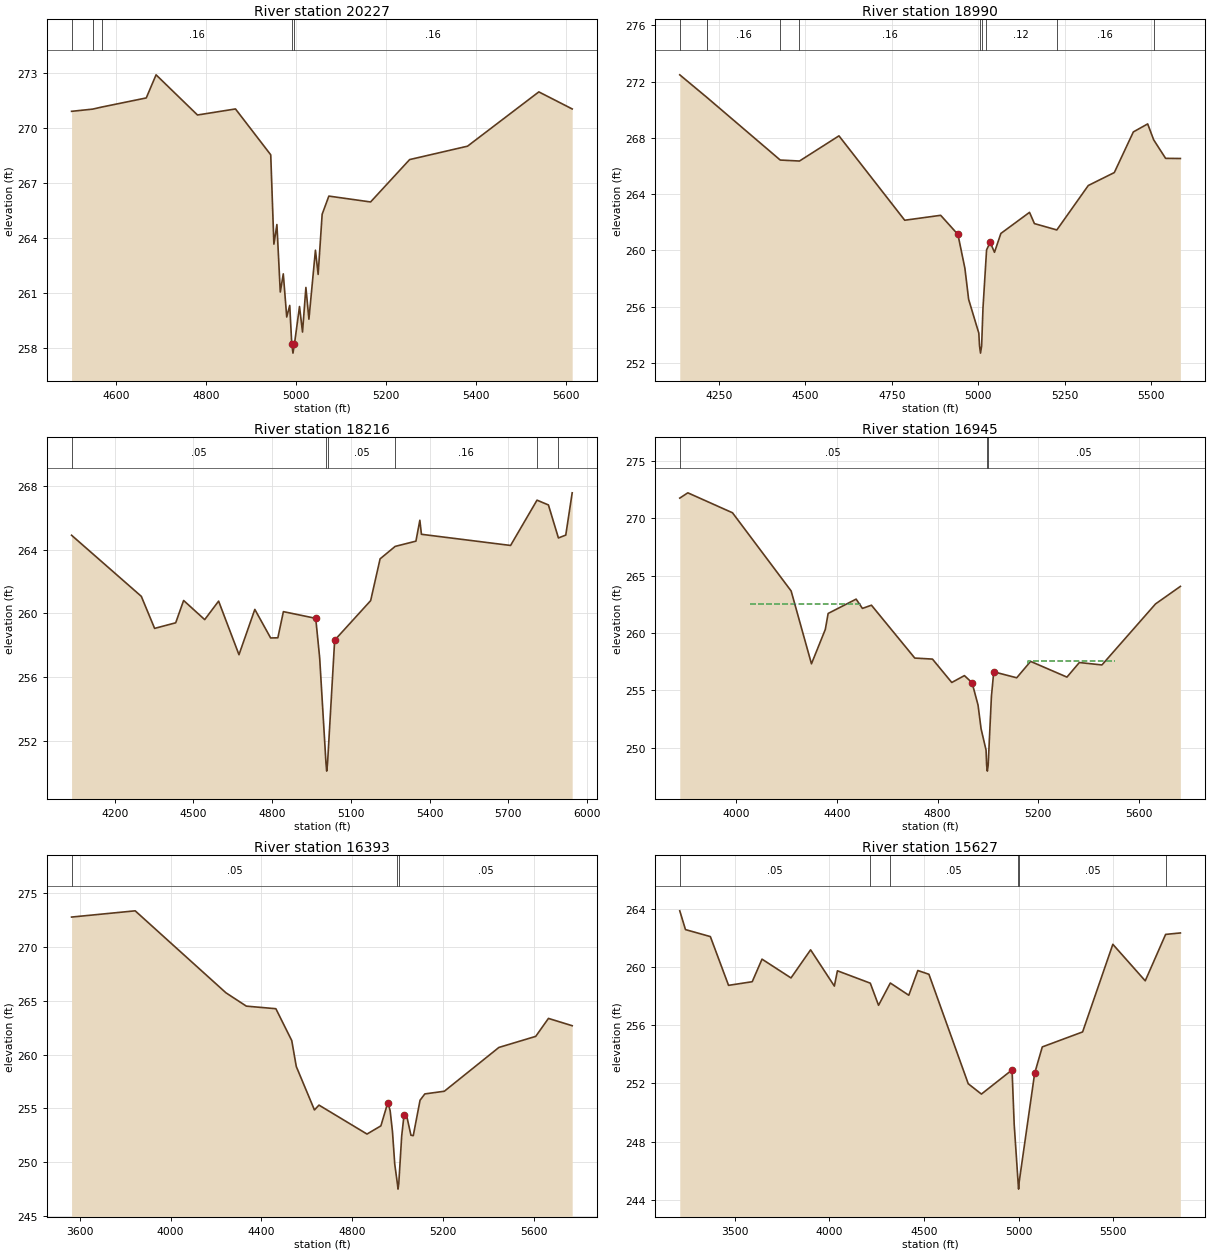
Type RM Length L Ch R = 1 ,20227   ,1237,1237,1237
BEGIN DESCRIPTION:
ROCK LAKE CREEK 39.0
END DESCRIPTION:
XS GIS Cut Line= 3
      3626212.84     10209665.37      3625816.24       10209313.
      3625336.59     10208984.28
#Sta/Elev= 30
    4502  270.89  4548.7  271.01  4568.5  271.12  4667.9  271.62  4689.7  272.88
  4781.7  270.69  4866.1  271.02  4944.4  268.52  4951.4  263.65  4958.1  264.72
  4965.6  261.04  4972.3  262.03  4979.9  259.68  4986.6  260.31  4991.1  258.21
  4993.8  257.71  4997.1  258.21  5008.3  260.25    5015  258.86  5022.5  261.29
  5029.2  259.56  5043.7  263.32  5049.7     262  5058.6  265.28  5073.5  266.27
  5166.2  265.95  5252.9  268.26  5381.5  268.99  5539.9  271.95    5614  271.02
#Mann= 5 ,-1 , 0
    4502     .16       0  4548.7      .1       0  4568.5     .16       0
  4991.1     .07       0  4997.1     .16       0
Bank Sta=4991.1,4997.1
XS Rating Curve= 0 ,0
Exp/Cntr=0.3,0.1

Type RM Length L Ch R = 1 ,18990   ,774,774,774
BEGIN DESCRIPTION:
ROCK LAKE CREEK 37.0
END DESCRIPTION:
XS GIS Cut Line= 3
      3626542.11      10209541.6      3626542.11     10208849.51
      3626348.63     10208120.33
#Sta/Elev= 30
  4137.3  272.49  4215.9  270.88  4427.6  266.43  4483.2  266.36  4597.3  268.15
  4787.3  262.15  4891.2   262.5    4941  261.14  4961.2  258.73    4972  256.52
  5001.4  254.12  5003.5   253.2  5006.3   252.7  5009.5   253.2  5013.4  255.89
  5021.3  259.04  5023.8  260.04  5034.1  260.58  5046.7  259.87  5065.1  261.21
  5147.9  262.71  5162.1  261.91  5226.8  261.46  5317.7  264.62  5392.9  265.54
  5447.9  268.43  5489.3     269  5506.6  267.87  5541.1  266.55  5583.8  266.54
#Mann= 9 ,-1 , 0
  4137.3      .1       0  4215.9     .16       0  4427.6      .1       0
  4483.2     .16       0  5003.5     .07       0  5009.5     .16       0
  5021.3     .12       0  5226.8     .16       0  5506.6      .1       0
Bank Sta=4941,5034.1
XS Rating Curve= 0 ,0
Exp/Cntr=0.3,0.1

Type RM Length L Ch R = 1 ,18216   ,1271,1271,1271
BEGIN DESCRIPTION:
ROCK LAKE CREEK 35.0
END DESCRIPTION:
XS GIS Cut Line= 3
      3627265.31     10209356.49      3627184.73      10208587.7
      3626557.01     10207641.24
#Sta/Elev= 30
  4035.2   264.9  4301.1  261.07  4351.8  259.06  4432.2  259.41  4462.4  260.81
  4542.8  259.61  4595.8  260.77  4673.5  257.41  4733.9  260.25  4794.2  258.46
  4821.7  258.47  4842.8  260.11  4966.1  259.69  4981.1  257.22  5005.2  250.61
  5007.9  250.11  5011.2  250.61  5038.3  258.32  5175.5   260.8  5211.5  263.42
  5268.9   264.2  5348.1  264.53  5363.1  265.84  5369.1  264.96    5709  264.26
  5809.8   267.1  5853.3   266.8  5891.4  264.73  5919.4  264.91  5943.9  267.56
#Mann= 6 ,-1 , 0
  4035.2     .05       0  5005.2     .03       0  5011.2     .05       0
  5268.9     .16       0  5809.8     .05       0  5891.4     .08       0
Bank Sta=4966.1,5038.3
XS Rating Curve= 0 ,0
Exp/Cntr=0.3,0.1

Type RM Length L Ch R = 1 ,16945   ,552,552,552
BEGIN DESCRIPTION:
ROCK LAKE CREEK 34.0
END DESCRIPTION:
XS GIS Cut Line= 3
      3629005.44      10208628.4      3627716.69     10208155.06
      3627140.27     10207932.83
#Sta/Elev= 30
  3774.8  271.75  3806.9  272.21  3984.5  270.47  4217.7  263.65  4298.5   257.3
  4353.6   260.3  4364.8  261.69  4476.1  262.94  4501.2  262.13    4537  262.41
  4709.3   257.8  4779.7  257.71  4856.4  255.67  4906.7  256.27  4937.2  255.65
  4960.9   253.7    4973  251.63  4992.8  249.77  4995.1  248.44  4997.9  247.94
  5001.1  248.44  5014.1  254.45  5023.3   256.6  5114.7  256.08  5169.9  257.51
  5314.4  256.14  5363.7  257.41  5453.6   257.2  5666.6  262.52  5765.5  264.05
#Mann= 3 ,-1 , 0
  3774.8     .05       0  4995.1     .03       0  5001.1     .05       0
#XS Ineff= 2 ,-1
 4053.98 4491.48  262.53 5160.51 5505.68  257.58
Permanent Ineff=
       F       F
Bank Sta=4937.2,5023.3
XS Rating Curve= 0 ,0
Exp/Cntr=0.3,0.1

Type RM Length L Ch R = 1 ,16393   ,766,766,766
BEGIN DESCRIPTION:
ROCK LAKE CREEK 33.0
END DESCRIPTION:
XS GIS Cut Line= 3
       3629222.5     10207825.45      3628007.49     10207810.45
      3627035.24       10207616.
#Sta/Elev= 30
  3563.5  272.79  3843.9  273.37  4243.9  265.75  4333.9  264.51    4464  264.27
    4534  261.31    4554   258.9    4634  254.86    4654  255.31  4865.7  252.62
  4926.9  253.38  4957.5  255.55  4967.7  254.79  4977.9  252.86    4988  249.82
  4999.7     248  5002.4   247.5  5005.7     248  5018.6  252.45  5028.8  254.35
    5039  254.46  5059.4  252.51  5069.6  252.47  5099.5  255.76  5120.6  256.35
  5206.6   256.6    5447  260.67  5609.4   261.7  5665.5  263.37  5770.1  262.69
#Mann= 3 ,-1 , 0
  3563.5     .05       0  4999.7     .03       0  5005.7     .05       0
Bank Sta=4957.5,5028.8
XS Rating Curve= 0 ,0
Exp/Cntr=0.3,0.1

Type RM Length L Ch R = 1 ,15627   ,292,292,292
BEGIN DESCRIPTION:
ROCK LAKE CREEK 31.0
END DESCRIPTION:
XS GIS Cut Line= 3
      3629428.63     10207423.98      3628528.01     10206935.69
      3627030.59     10207554.19
#Sta/Elev= 30
  3209.6  263.85  3239.8  262.56  3371.2  262.08  3467.3  258.73  3592.4  258.98
  3644.1  260.53  3797.2  259.24  3900.8  261.17  4026.3  258.68  4042.5  259.73
  4216.1  258.88  4259.7  257.36  4321.9  258.89  4419.5  258.05  4467.3  259.75
  4525.9  259.49  4733.5  251.97  4803.1  251.26    4965  252.92  4976.2  249.19
  4996.7  245.23  4999.5  244.73  5002.7  245.23  5084.4  252.69  5124.7   254.5
  5337.7  255.53  5497.4  261.55  5668.6  259.04  5776.2  262.23  5854.2  262.33
#Mann= 6 ,-1 , 0
  3209.6     .05       0  4216.1     .08       0  4321.9     .05       0
  4996.7     .04       0  5002.7     .05       0  5776.2     .08       0
Bank Sta=4965,5084.4
XS Rating Curve= 0 ,0
Exp/Cntr=0.3,0.1

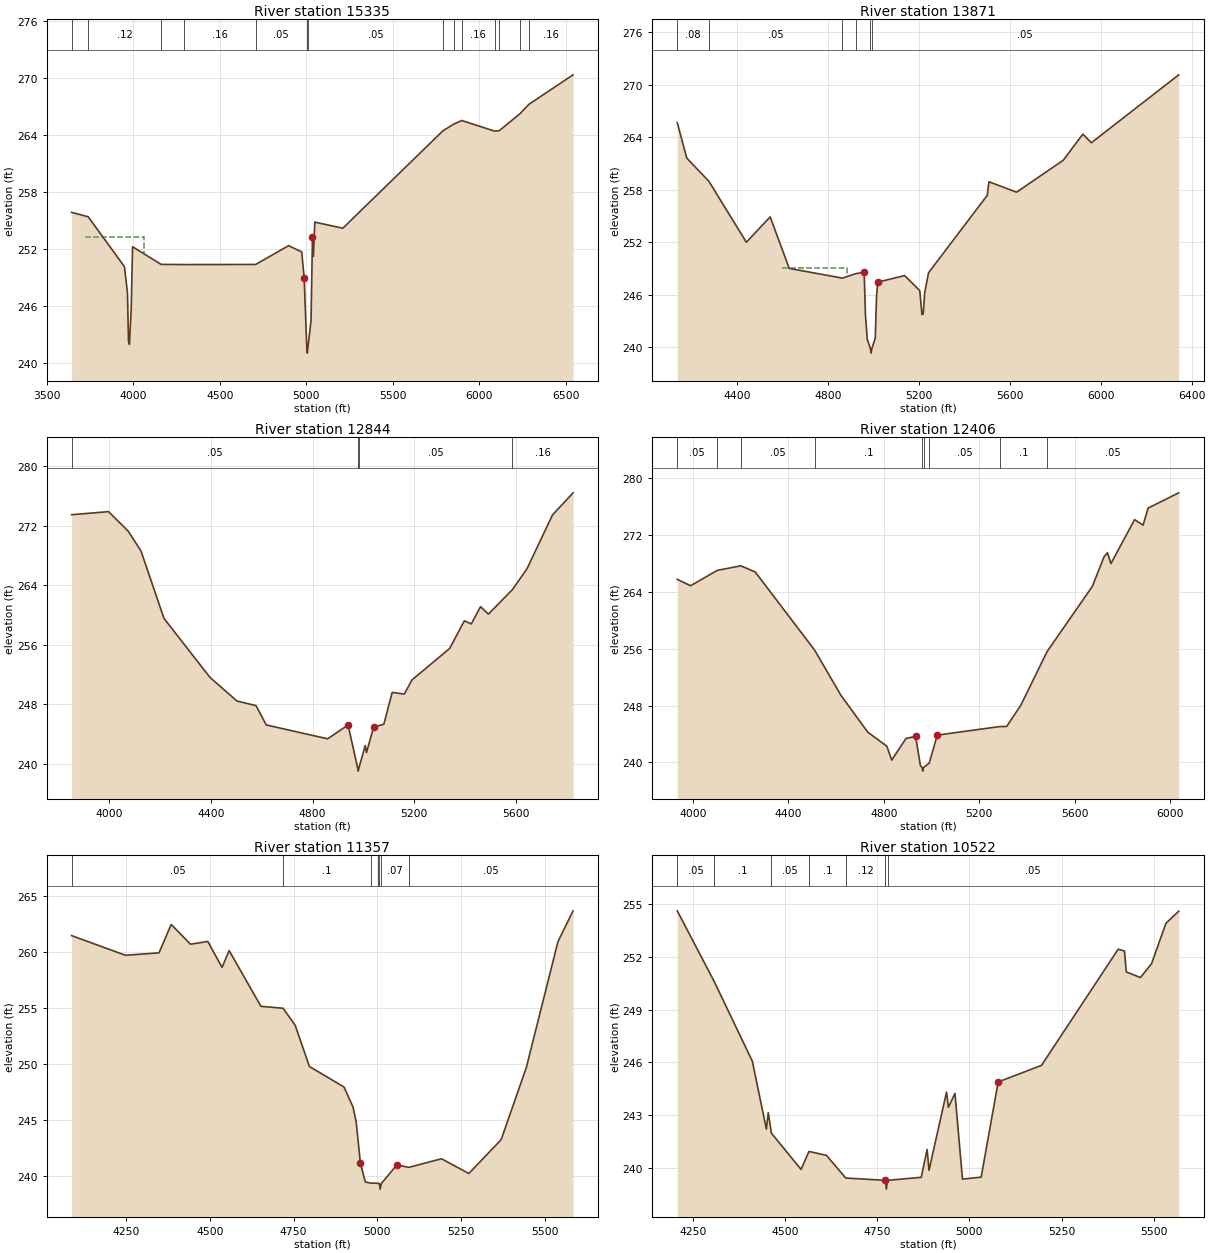
Type RM Length L Ch R = 1 ,15335   ,1464,1464,1464
BEGIN DESCRIPTION:
ROCK LAKE CREEK 30.0
END DESCRIPTION:
XS GIS Cut Line= 3
       3628929.5     10206458.26      3628092.91     10206812.61
      3626249.38     10207565.03
#Sta/Elev= 30
    3643  255.86  3739.1  255.39  3948.1  250.15    3966   247.4  3971.8  242.36
  3977.2  241.95  3987.7  245.76  3995.5  252.24  4160.3  250.38  4294.4  250.36
    4707  250.37    4898  252.35  4973.6  251.69  4987.7  248.99    5003  241.53
  5005.8  241.03    5009  241.53  5027.6  244.48  5035.8  253.31  5041.2  251.22
  5049.2  254.83  5211.3  254.19  5790.6  264.46  5851.4  265.14  5898.9  265.54
  6088.7  264.42  6115.6  264.46  6235.6  266.25  6287.1  267.24  6542.7  270.35
#Mann= 14 ,-1 , 0
    3643     .05       0  3739.1     .12       0  4160.3     .08       0
  4294.4     .16       0    4707     .05       0    5003     .03       0
    5009     .05       0  5790.6     .16       0  5851.4      .1       0
  5898.9     .16       0  6088.7      .1       0  6115.6     .16       0
  6235.6      .1       0  6287.1     .16       0
#XS Ineff= 1 ,-1
 3720.74  4060.8  253.27
Permanent Ineff=
       F
Bank Sta=4987.7,5035.8
XS Rating Curve= 0 ,0
Exp/Cntr=0.3,0.1

Type RM Length L Ch R = 1 ,13871   ,1027,1027,1027
BEGIN DESCRIPTION:
ROCK LAKE CREEK 28.0
END DESCRIPTION:
XS GIS Cut Line= 3
      3629242.14     10206441.65      3628442.11     10206191.64
       3627184.1     10205655.98
#Sta/Elev= 30
  4137.7  265.67  4179.6  261.61    4277  258.96  4441.6     252  4546.3   254.9
  4630.2  249.01  4864.1   247.9  4923.8  248.42  4959.7  248.56  4965.4  243.67
  4973.3   240.9  4987.4  239.83  4990.2  239.33  4993.4  239.83  5008.5  241.04
  5014.1  245.79  5019.5  247.44  5137.7  248.19  5204.1  246.48    5214  243.73
  5219.4   243.8  5225.9  246.22    5243  248.52  5501.1  257.36  5508.5  258.91
  5630.1  257.72  5835.5  261.37  5921.5  264.36  5959.1  263.37  6343.2  271.13
#Mann= 6 ,-1 , 0
  4137.7     .08       0    4277     .05       0  4864.1     .12       0
  4923.8     .05       0  4987.4     .03       0  4993.4     .05       0
#XS Ineff= 1 ,-1
 4599.43 4886.36  249.07
Permanent Ineff=
       F
Bank Sta=4959.7,5019.5
XS Rating Curve= 0 ,0
Exp/Cntr=0.3,0.1

Type RM Length L Ch R = 1 ,12844   ,438,438,438
BEGIN DESCRIPTION:
ROCK LAKE CREEK 27.0
END DESCRIPTION:
XS GIS Cut Line= 3
      3629873.46     10205470.84      3628452.06     10205329.79
      3627992.14     10205041.66
#Sta/Elev= 30
  3852.8   273.5  3998.2  273.92  4075.2  271.29  4125.5  268.62  4215.9  259.54
  4396.7   251.6  4502.6  248.42  4577.7   247.8  4617.9   245.2  4859.1  243.33
  4939.5  245.19  4976.7  239.48  4979.4  238.98  4982.7  239.48    5007  242.43
    5012  241.48    5040  244.91  5080.2   245.3  5112.9  249.58  5160.5  249.35
  5190.7  251.26  5338.9   255.5  5396.7  259.22  5423.8   258.8  5460.3  261.12
    5491  260.12  5585.6  263.42    5643  266.24  5743.2  273.48  5823.9  276.45
#Mann= 4 ,-1 , 0
  3852.8     .05       0  4976.7     .03       0  4982.7     .05       0
  5585.6     .16       0
Bank Sta=4939.5,5040
XS Rating Curve= 0 ,0
Exp/Cntr=0.3,0.1

Type RM Length L Ch R = 1 ,12406   ,1049,1049,1049
BEGIN DESCRIPTION:
ROCK LAKE CREEK 25.0
END DESCRIPTION:
XS GIS Cut Line= 3
      3630057.94     10205188.73      3628492.97     10205069.94
      3628092.95     10204719.92
#Sta/Elev= 30
  3934.7  265.74  3990.7  264.84  4102.2     267  4200.9  267.64  4261.5  266.77
  4510.4  255.78  4620.2  249.45  4732.8  244.26    4813  242.27  4833.1  240.33
  4893.3  243.38  4933.4  243.66  4953.5  239.55  4960.5  239.28  4963.2  238.78
  4966.5  239.28  4990.6  239.92    5024  243.84  5286.7  245.05  5314.5  245.05
  5374.7  248.08  5484.1  255.58  5673.8  264.75  5723.2  268.94  5737.4  269.47
  5751.6  267.95  5850.8  274.13  5886.4  273.36  5907.3  275.75  6035.7   277.9
#Mann= 9 ,-1 , 0
  3934.7     .05       0  4102.2     .08       0  4200.9     .05       0
  4510.4      .1       0  4960.5    .035       0  4966.5      .1       0
  4990.6     .05       0  5286.7      .1       0  5484.1     .05       0
Bank Sta=4933.4,5024
XS Rating Curve= 0 ,0
Exp/Cntr=0.3,0.1

Type RM Length L Ch R = 1 ,11357   ,835,835,835
BEGIN DESCRIPTION:
ROCK LAKE CREEK 23.0
END DESCRIPTION:
XS GIS Cut Line= 3
      3630188.15     10205025.96      3629258.36     10204432.84
       3628892.1     10204291.64
#Sta/Elev= 30
  4088.1  261.48  4248.9  259.72  4348.7  259.94  4385.1  262.48  4442.7  260.71
  4494.3  260.96  4536.6  258.64  4557.9  260.14  4652.8  255.15  4718.8  254.98
  4754.9  253.45  4797.2  249.77  4900.4  247.93  4927.5  246.12  4936.8   244.8
  4949.3  241.12  4963.9  239.43  4979.8  239.33    5001  239.31  5005.6  239.29
  5008.3  238.79  5011.6  239.29  5057.9  240.95  5094.5  240.74    5191  241.51
  5272.7  240.19  5369.1  243.22  5444.2  249.68  5538.5  260.95  5583.5   263.7
#Mann= 7 ,-1 , 0
  4088.1     .05       0  4718.8      .1       0  4979.8     .05       0
    5001     .07       0  5005.6    .033       0  5011.6     .07       0
  5094.5     .05       0
Bank Sta=4949.3,5057.9
XS Rating Curve= 0 ,0
Exp/Cntr=0.3,0.1

Type RM Length L Ch R = 1 ,10522   ,455,455,455
BEGIN DESCRIPTION:
ROCK LAKE CREEK 21.0
END DESCRIPTION:
XS GIS Cut Line= 3
      3630192.07     10203991.64      3629392.11     10203841.64
       3628848.6     10203793.95
#Sta/Elev= 30
  4207.9  254.61  4308.4  250.58  4411.4  246.07  4449.5  242.21  4454.6  243.15
  4463.1  241.98  4543.6  239.92    4565  240.94  4612.3  240.72  4664.7  239.43
  4772.1   239.3  4774.8   238.8  4778.1   239.3  4869.2  239.47  4885.3  241.05
  4890.4  239.87  4937.9  244.31    4943  243.45  4960.8  244.24  4981.1  239.37
  5031.8  239.48    5078  244.89  5195.4  245.83  5403.3  252.43  5420.3  252.33
  5425.3  251.14  5463.5  250.82  5493.6   251.6  5532.7   253.9  5567.4  254.59
#Mann= 7 ,-1 , 0
  4207.9     .05       0  4308.4      .1       0  4463.1     .05       0
    4565      .1       0  4664.7     .12       0  4772.1    .035       0
  4778.1     .05       0
Bank Sta=4772.1,5078
XS Rating Curve= 0 ,0
Exp/Cntr=0.3,0.1

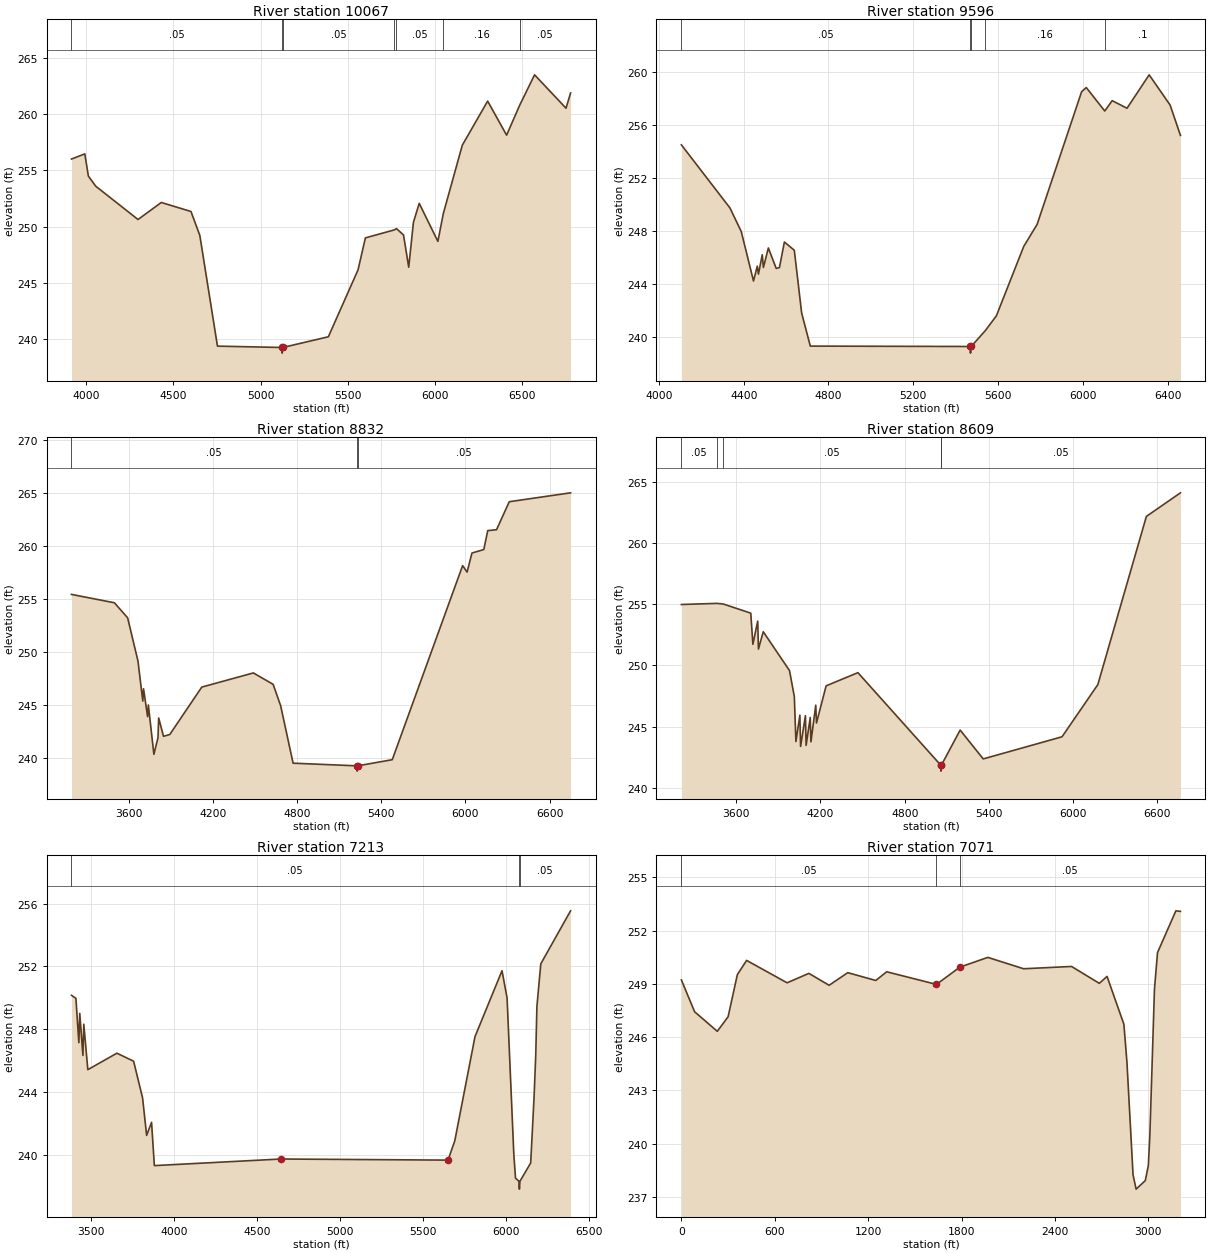
Type RM Length L Ch R = 1 ,10067   ,471,471,471
BEGIN DESCRIPTION:
ROCK LAKE CREEK 20.0
END DESCRIPTION:
XS GIS Cut Line= 3
      3630556.96      10203613.4      3629154.19     10203328.68
      3627726.12     10203430.84
#Sta/Elev= 30
    3915     256  3991.4  256.46  4011.8  254.49  4053.6   253.6  4296.6  250.64
  4430.2  252.15  4600.5  251.35  4651.2  249.23  4752.4  239.41    5121  239.29
  5123.8  238.79    5127  239.29  5388.6  240.24    5559  246.18  5601.1  249.01
  5767.4  249.72  5779.4  249.83  5819.7  249.27  5849.7  246.41  5876.6  250.39
  5909.9  252.07  6016.9   248.7  6048.3  251.18  6157.1  257.23  6302.4  261.14
  6411.2  258.12  6485.8  260.76  6571.6  263.47    6752  260.51  6778.1  261.86
#Mann= 7 ,-1 , 0
    3915     .05       0    5121    .033       0    5127     .05       0
  5767.4     .16       0  5779.4     .05       0  6048.3     .16       0
  6485.8     .05       0
Bank Sta=5121,5127
XS Rating Curve= 0 ,0
Exp/Cntr=0.3,0.1

Type RM Length L Ch R = 1 ,9596    ,764,764,764
BEGIN DESCRIPTION:
ROCK LAKE CREEK 19.0
END DESCRIPTION:
XS GIS Cut Line= 3
      3630392.09     10203291.64      3629592.11     10202941.64
      3628235.03     10202345.84
#Sta/Elev= 30
  4105.8   254.5    4335  249.74  4388.4  247.96  4446.1  244.23    4464  245.35
  4469.5  244.75  4487.4  246.21  4492.9  245.25  4516.3  246.72  4553.3  245.18
  4568.5  245.24  4591.9  247.17  4638.7  246.55  4673.4  241.81  4714.3  239.32
  5467.5  239.29  5470.2  238.79  5473.5  239.29  5540.8   240.5  5592.3   241.6
  5721.6  246.84  5784.6   248.5  5994.7  258.51  6016.7  258.82  6103.8  257.05
  6138.9  257.83    6209  257.26  6313.4  259.78  6412.3   257.5  6461.1  255.21
#Mann= 5 ,-1 , 0
  4105.8     .05       0  5467.5    .033       0  5473.5     .05       0
  5540.8     .16       0  6103.8      .1       0
Bank Sta=5467.5,5473.5
XS Rating Curve= 0 ,0
Exp/Cntr=0.3,0.1

Type RM Length L Ch R = 1 ,8832    ,223,223,223
BEGIN DESCRIPTION:
ROCK LAKE CREEK 17.1
END DESCRIPTION:
XS GIS Cut Line= 3
      3631706.59     10202832.24      3630295.95      10202441.6
      3628407.97     10201541.01
#Sta/Elev= 30
  3193.1  255.43  3498.7  254.64    3593  253.22  3666.8  249.13  3701.1  245.35
  3706.3  246.51  3735.4  243.88  3740.6  244.98  3780.1  240.32  3809.2  241.88
  3814.4  243.75  3848.7  242.02  3893.3  242.19  4121.2  246.67  4488.8  248.01
  4629.7  246.93  4683.2  244.91  4771.9  239.48  5225.7  239.23  5228.5  238.73
  5231.7  239.23  5478.4  239.81  5979.5  258.15  6011.4  257.54    6046  259.34
  6130.4  259.67  6158.6  261.46  6221.1  261.54  6311.9  264.19  6748.6  265.03
#Mann= 3 ,-1 , 0
  3193.1     .05       0  5225.7    .033       0  5231.7     .05       0
Bank Sta=5225.7,5231.7
XS Rating Curve= 0 ,0
Exp/Cntr=0.3,0.1

Type RM Length L Ch R = 1 ,8609    ,1396,1396,1396
BEGIN DESCRIPTION:
ROCK LAKE CREEK 17.0
END DESCRIPTION:
XS GIS Cut Line= 3
      3631828.46     10202652.49      3630417.82     10202261.85
      3628529.84     10201361.26
#Sta/Elev= 30
    3209  254.99    3461  255.08  3507.5  255.03  3703.3  254.28  3718.4  251.73
  3752.7  253.63  3757.9  251.34  3792.2  252.76  3979.3  249.58  4013.6  247.45
  4024.9  243.77  4053.1  245.93  4058.3  243.37  4092.6  245.89  4097.7  243.46
  4126.9  245.74    4132  243.75  4166.3  246.75  4171.5  245.29  4240.1  248.33
  4466.7  249.41  5055.9  241.85  5058.6  241.35  5061.9  241.85    5195  244.71
  5359.4  242.35  5920.7  244.16  6175.8  248.43  6521.8   262.2  6764.5  264.13
#Mann= 5 ,-1 , 0
    3209     .05       0    3461      .1       0  3507.5     .05       0
  5055.9     .03       0  5061.9     .05       0
Bank Sta=5055.9,5061.9
XS Rating Curve= 0 ,0
Exp/Cntr=0.3,0.1

Type RM Length L Ch R = 1 ,7213    ,142,142,142
BEGIN DESCRIPTION:
ROCK LAKE CREEK 16.0
END DESCRIPTION:
XS GIS Cut Line= 3
      3632206.86     10201753.54      3630322.12     10201009.95
      3629355.79     10200829.81
#Sta/Elev= 30
  3382.1  250.16  3408.7  249.97  3426.5  247.14  3431.9  249.01  3450.9  246.33
  3456.2  248.32  3480.6  245.42    3656  246.47  3756.6  245.96  3810.7  243.62
  3835.1  241.23  3864.8  242.06  3881.7   239.3    4645  239.72  5652.4  239.65
  5693.1  240.88  5815.1  247.53  5977.9  251.73  6008.4  249.99  6049.1  240.01
  6059.3   238.5  6079.9   238.3  6082.6   237.8  6085.9   238.3  6150.8  239.47
  6171.2  243.68  6181.3  246.37  6188.3  249.45  6211.8  252.17  6391.2  255.55
#Mann= 3 ,-1 , 0
  3382.1     .05       0  6079.9    .033       0  6085.9     .05       0
Bank Sta=4645,5652.4
XS Rating Curve= 0 ,0
Exp/Cntr=0.3,0.1

Type RM Length L Ch R = 1 ,7071    ,141,141,141
XS GIS Cut Line= 6
     3632390.334    10201828.287     3632265.334    10201738.009
     3632032.695    10201609.537      3630400.75    10200894.259
     3629845.195    10200866.481     3629397.278     10200755.37
#Sta/Elev= 30
       0  249.22   85.01  247.43  230.83  246.33  300.17  247.15  359.61  249.52
  419.13  250.32  679.07  249.06  819.03  249.59     949  248.92 1068.97  249.63
 1248.93  249.19 1318.91  249.68 1638.84  248.97  1788.8  249.94 1968.76  250.49
  2198.7  249.85 2506.36  249.98    2685  249.03 2734.62  249.42 2842.79  246.73
 2862.44   244.6 2901.74  238.25 2921.39  237.45 2980.33  237.93 2999.98  238.78
  3009.8  240.51 3039.28   248.7 3058.93  250.76 3176.82  253.11 3206.29  253.08
#Mann= 3 , 0 , 0
       0     .05       0 1638.84     .03       0  1788.8     .05       0
Bank Sta=1638.84,1788.8
XS Rating Curve= 0 ,0
Exp/Cntr=0.3,0.1

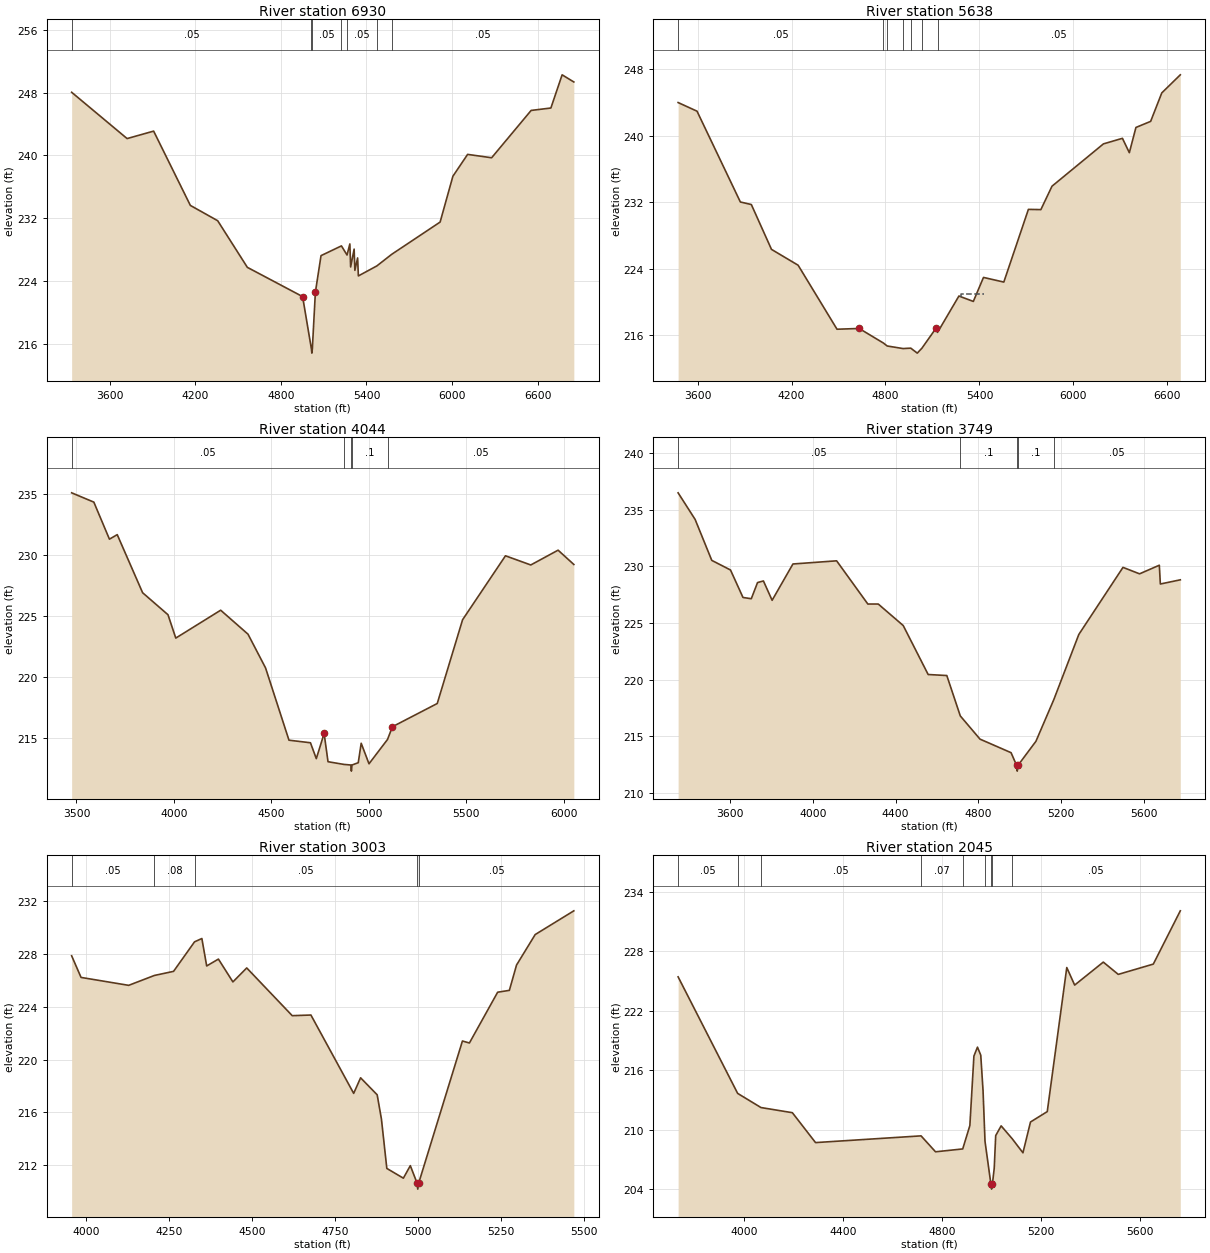
Type RM Length L Ch R = 1 ,6930    ,1292,1292,1292
BEGIN DESCRIPTION:
ROCK LAKE CREEK 14.0
END DESCRIPTION:
XS GIS Cut Line= 3
      3632381.76      10201719.3      3631144.82     10201057.42
      3629169.96     10200287.01
#Sta/Elev= 30
  3332.1  248.03  3721.1  242.14  3907.2  243.09  4164.8  233.64  4356.6  231.69
  4564.7  225.76  4952.2  222.04  5014.3  215.35  5017.1  214.85  5020.3  215.35
  5041.8   222.6  5081.4  227.25  5224.5  228.49  5263.9  227.33  5283.7  228.74
  5289.1  225.81  5313.6  228.08  5318.9  225.38  5338.1  226.96  5343.4  224.67
  5472.9  225.94  5577.3  227.42  5916.8  231.52  6006.4  237.35  6109.7  240.13
  6278.1   239.7  6555.2  245.72  6693.8  246.03  6772.6  250.25  6854.8  249.34
#Mann= 7 ,-1 , 0
  3332.1     .05       0  5014.3     .03       0  5020.3     .05       0
  5224.5      .1       0  5263.9     .05       0  5472.9      .1       0
  5577.3     .05       0
Bank Sta=4952.2,5041.8
XS Rating Curve= 0 ,0
Exp/Cntr=0.3,0.1

Type RM Length L Ch R = 1 ,5638    ,1594,1594,1594
BEGIN DESCRIPTION:
ROCK LAKE CREEK 12.0
END DESCRIPTION:
XS GIS Cut Line= 3
      3632626.41     10201127.28      3631835.57     10200199.59
      3630666.36     10198592.55
#Sta/Elev= 30
    3476     244  3596.7  242.96  3873.4  232.02  3943.6  231.71  4072.1  226.31
  4242.3   224.4  4490.5  216.69  4632.1  216.78  4787.2  215.02    4811  214.67
  4912.3  214.36  4961.4  214.41  5002.9  213.81  5032.5   214.4  5125.3  216.88
  5132.5  216.31  5268.9  220.69  5360.9  220.04  5425.8  222.93  5555.6  222.37
  5712.5  231.13  5792.1   231.1  5863.2  233.92  6191.6  239.02  6312.9  239.69
    6357  237.96  6399.1     241    6493  241.73  6564.1  245.16  6682.4  247.34
#Mann= 7 ,-1 , 0
    3476     .05       0  4787.2     .12       0    4811     .07       0
  4912.3     .12       0  4961.4     .07       0  5032.5     .12       0
  5132.5     .05       0
#XS Ineff= 1 ,-1
 5284.09 5427.27  220.91
Permanent Ineff=
       F
Bank Sta=4632.1,5125.3
XS Rating Curve= 0 ,0
Exp/Cntr=0.3,0.1

Type RM Length L Ch R = 1 ,4044    ,295,295,295
BEGIN DESCRIPTION:
ROCK LAKE CREEK 10.0
END DESCRIPTION:
XS GIS Cut Line= 3
      3632773.12     10200775.27      3632857.44     10199101.49
      3632857.44     10198200.89
#Sta/Elev= 30
  3475.5  235.08  3589.3  234.32  3669.4  231.29  3709.4  231.66  3839.6  226.91
  3969.8  225.11  4009.8   223.2  4240.1  225.48  4380.3  223.52  4470.4  220.76
  4590.5  214.85  4700.7  214.64  4730.7  213.34  4770.8   215.4  4790.8  213.09
  4872.1  212.87  4907.9  212.82  4910.7  212.32  4913.9  212.82    4946  213.01
    4961   214.6  5001.1  212.92  5096.1  214.91  5121.2  215.95  5351.2  217.85
  5481.2   224.7  5701.2  229.93  5831.2  229.18  5971.2  230.39    6052  229.22
#Mann= 5 ,-1 , 0
  3475.5     .05       0  4872.1      .1       0  4907.9     .07       0
  4913.9      .1       0  5096.1     .05       0
Bank Sta=4770.8,5121.2
XS Rating Curve= 0 ,0
Exp/Cntr=0.3,0.1

Type RM Length L Ch R = 1 ,3749    ,746,746,746
BEGIN DESCRIPTION:
ROCK LAKE CREEK 8.0
END DESCRIPTION:
XS GIS Cut Line= 3
       3632998.5     10200783.35      3633107.01     10199622.32
      3633074.49     10198365.13
#Sta/Elev= 30
  3350.4  236.51  3432.5  234.16  3512.8  230.54  3603.2  229.69  3663.5  227.26
  3703.6  227.15  3733.8  228.58  3762.1  228.72  3804.1  227.01  3904.5  230.22
  4115.4   230.5  4266.1  226.68  4316.3  226.68  4436.8  224.78  4557.2  220.45
  4647.2  220.36  4712.3  216.79  4807.3  214.74  4957.3  213.54  4984.3  212.41
  4987.1  211.91  4990.3  212.41  5077.4  214.55  5163.6  218.23  5284.3  223.99
  5497.5  229.92  5577.5  229.35  5672.8  230.11  5677.8  228.45  5774.1  228.82
#Mann= 5 ,-1 , 0
  3350.4     .05       0  4712.3      .1       0  4984.3     .07       0
  4990.3      .1       0  5163.6     .05       0
Bank Sta=4984.3,4990.3
XS Rating Curve= 0 ,0
Exp/Cntr=0.3,0.1

Type RM Length L Ch R = 1 ,3003    ,958,958,958
BEGIN DESCRIPTION:
ROCK LAKE CREEK 6.0
END DESCRIPTION:
XS GIS Cut Line= 3
      3634279.16     10199134.21      3633442.11     10198491.64
      3633106.31     10198183.51
#Sta/Elev= 30
  3957.5  227.88  3985.8  226.24  4129.1  225.64  4206.5  226.39  4264.1   226.7
  4327.3  228.94  4349.3  229.19  4363.8  227.11  4399.1  227.63  4442.7   225.9
  4484.3  226.96  4621.2  223.34  4677.4  223.39  4806.1  217.45  4826.9  218.63
  4876.8  217.34  4889.6   215.5  4905.8  211.76  4955.6  211.02  4976.5  211.97
  4996.2  210.69  4998.9  210.19  5002.2  210.69  5133.3  221.42  5154.3  221.27
  5239.3  225.12  5274.5  225.26  5296.1  227.18  5352.2  229.49  5468.5  231.29
#Mann= 5 ,-1 , 0
  3957.5     .05       0  4206.5     .08       0  4327.3     .05       0
  4996.2     .03       0  5002.2     .05       0
Bank Sta=4996.2,5002.2
XS Rating Curve= 0 ,0
Exp/Cntr=0.3,0.1

Type RM Length L Ch R = 1 ,2045    ,1503,1503,1503
BEGIN DESCRIPTION:
ROCK LAKE CREEK 4.0
END DESCRIPTION:
XS GIS Cut Line= 3
      3634723.65     10198877.31      3634093.92     10198035.52
      3633225.38     10197579.59
#Sta/Elev= 30
  3731.9  225.42  3972.8  213.65  4067.2  212.22  4194.2   211.7    4288  208.68
    4715  209.36  4773.6  207.75  4883.6  208.04  4912.5   210.4  4928.9  217.42
  4943.3  218.32  4956.6  217.51  4965.9  213.91  4973.8  208.81  4997.7  204.48
  5000.4  203.98  5003.7  204.48  5011.1  206.09  5017.1  209.39  5039.1  210.37
  5083.5  209.08  5127.3  207.65  5157.9  210.76  5225.7  211.81  5304.7  226.36
  5336.6  224.59  5452.5  226.91    5513  225.67  5654.9  226.71  5764.1  232.09
#Mann= 9 ,-1 , 0
  3731.9     .05       0  3972.8     .16       0  4067.2     .05       0
    4715     .07       0  4883.6     .05       0  4973.8     .07       0
  4997.7     .07       0  5003.7     .07       0  5083.5     .05       0
Bank Sta=4997.7,5003.7
XS Rating Curve= 0 ,0
Exp/Cntr=0.3,0.1

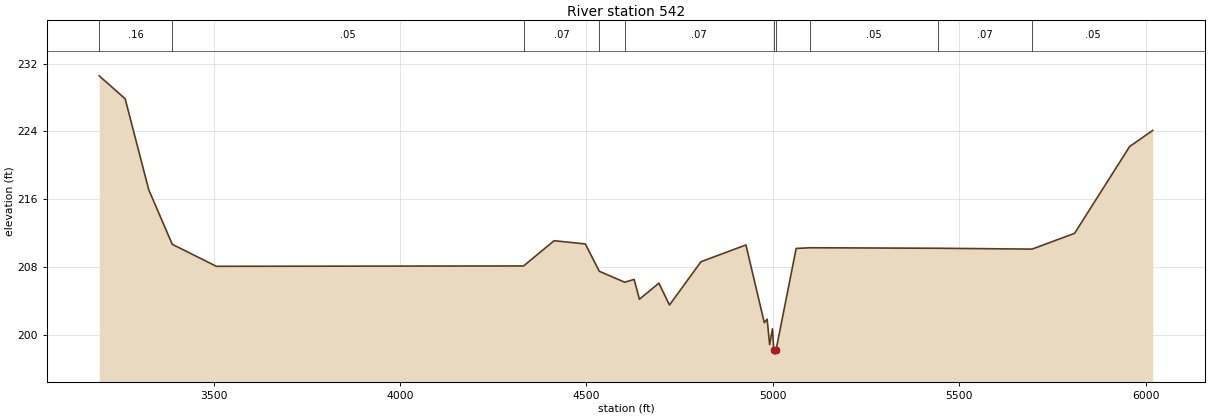
Type RM Length L Ch R = 1 ,542     ,0,0,0
BEGIN DESCRIPTION:
ROCK LAKE CREEK 1.0
END DESCRIPTION:
XS GIS Cut Line= 4
      3634966.69     10198717.56      3634501.41     10197342.56
      3634063.91     10196960.62      3633327.82     10197259.22
#Sta/Elev= 30
  3192.6  230.56  3262.2  227.85  3325.5  217.11  3388.5  210.67  3506.8  208.07
  4331.2  208.11  4413.1  211.09  4496.9  210.71  4534.4  207.48  4602.5  206.19
  4627.9  206.52    4642  204.18  4694.3  206.08  4722.7   203.5  4807.2  208.61
  4927.8  210.59  4977.1  201.41  4984.7  201.83  4991.4  198.83    4999  200.69
  5002.6   198.2  5005.4   197.7  5008.6   198.2  5062.6  210.18  5100.7  210.26
  5443.5   210.2  5695.5   210.1  5809.6  211.96  5957.3  222.21  6019.3  224.12
#Mann= 10 ,-1 , 0
  3192.6     .16       0  3388.5     .05       0  4331.2     .07       0
  4534.4     .05       0  4602.5     .07       0  5002.6     .07       0
  5008.6     .07       0  5100.7     .05       0  5443.5     .07       0
  5695.5     .05       0
Bank Sta=5002.6,5008.6
XS Rating Curve= 0 ,0
Exp/Cntr=0.3,0.1

Chan Stop Cuts=-1
Use User Specified Reach Order=0
Composite Channel Slope=5