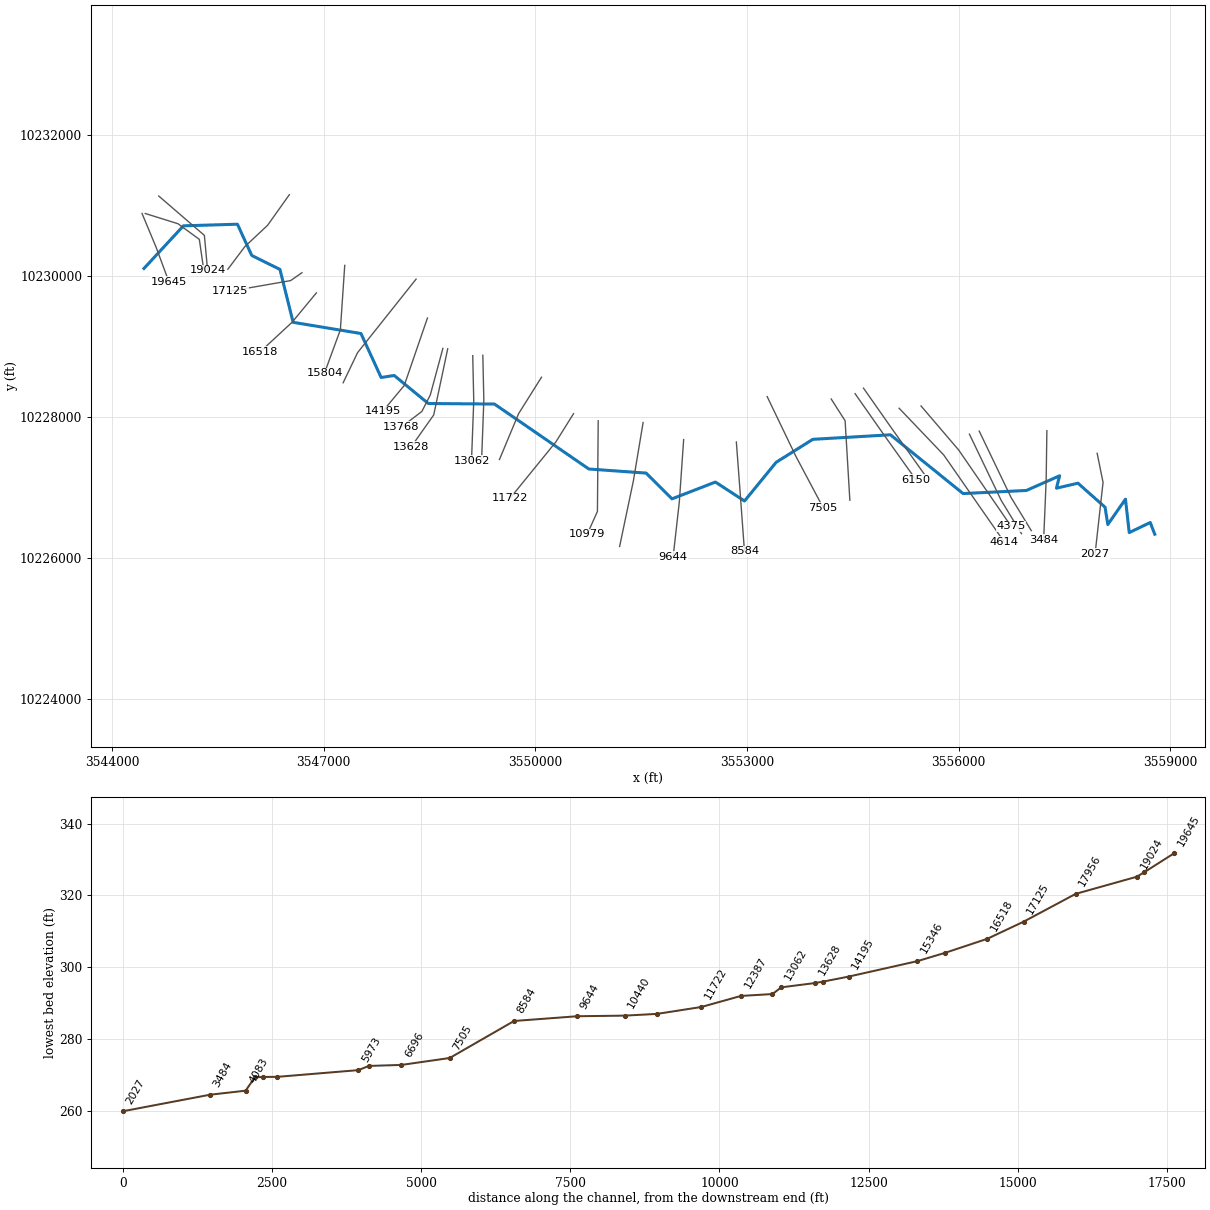
--- SEWER CREEK.prj (project) ---

Proj Title=SEWER CREEK Base Level Engineering
Current Plan=p01
Default Exp/Contr=0.3,0.1
English Units
Geom File=g01
Flow File=f01
Plan File=p01
Y Axis Title=Elevation
X Axis Title(PF)=Main Channel Distance
X Axis Title(XS)=Station
BEGIN DESCRIPTION:
SEWER CREEK
END DESCRIPTION:
DSS Export Rating Curves= 0
DSS Export Rating Curve Sorted= 0
DSS Export Volume Flow Curves= 0
DXF OffsetX= 0
DXF OffsetY= 0
DXF ScaleX= 1
DXF ScaleY= 10

--- SEWER CREEK.p01 (plan) ---

Plan Title=Multiple Run
Short Identifier=Multiple
Geom File=g01
Flow File=f01
Subcritical Flow
K Sum by GR= 0
Std Step Tol= 0.01
Critical Tol= 0.01
Num of Std Step Trials= 20
Max Error Tol= 0.3
Flow Tol Ratio= 0.001
Split Flow NTrial= 30
Split Flow Tol= 0.02
Split Flow Ratio= 0.02
Log Output Level= 0
Friction Slope Method= 1
Unsteady Friction Slope Method= 2
Unsteady Bridges Friction Slope Method= 1
Parabolic Critical Depth
Global Vel Dist=  1 , 1 , 1
Global Log Level= 0
CheckData=True
Encroach Param= -1, 0, 0, 0
BEGIN DESCRIPTION:
Multiple Run
END DESCRIPTION:

--- SEWER CREEK.f01 (steady flow) ---

Flow Title=Multiple
Program Version=4.10
Number of Profiles= 7
Profile Names=10-year,25-year,50-year,1pct_min,100-year,1pct_plu,500-year
River Rch & RM=SEWER CREEK,Reach-1         ,19645
     602     816     991     883    1194    1615    1736
River Rch & RM=SEWER CREEK,Reach-1         ,12916
     929    1280    1572    1411    1909    2581    2823
River Rch & RM=SEWER CREEK,Reach-1         ,4375
    1026    1422    1752    1578    2134    2886    3177
Boundary for River Rch & Prof#=SEWER CREEK,Reach-1         , 1
Up Type= 0
Dn Type= 3
Dn Slope=0.005
Boundary for River Rch & Prof#=SEWER CREEK,Reach-1         , 2
Up Type= 0
Dn Type= 3
Dn Slope=0.005
Boundary for River Rch & Prof#=SEWER CREEK,Reach-1         , 3
Up Type= 0
Dn Type= 3
Dn Slope=0.005
Boundary for River Rch & Prof#=SEWER CREEK,Reach-1         , 4
Up Type= 0
Dn Type= 3
Dn Slope=0.005
Boundary for River Rch & Prof#=SEWER CREEK,Reach-1         , 5
Up Type= 0
Dn Type= 3
Dn Slope=0.005
Boundary for River Rch & Prof#=SEWER CREEK,Reach-1         , 6
Up Type= 0
Dn Type= 3
Dn Slope=0.005
Boundary for River Rch & Prof#=SEWER CREEK,Reach-1         , 7
Up Type= 0
Dn Type= 3
Dn Slope=0.005
DSS Import GetInterval= 0
DSS Import GetPeak= 0
DSS Import FillOption= 0

--- SEWER CREEK.g01 (geometry) ---

Geom Title=Existing Conditions
Program Version=4.10

River Reach=SEWER CREEK     ,Reach-1
Reach XY= 30
       3544452.7     10230102.27      3545012.09     10230707.06
      3545777.75     10230729.84      3545980.43     10230286.87
      3546380.27     10230088.29      3546567.31     10229337.62
      3547528.73     10229179.51      3547814.66     10228555.64
      3548000.21     10228583.86      3548483.49     10228186.22
      3549420.94     10228178.83      3550759.58     10227256.92
      3551571.14     10227199.32      3551937.98     10226833.78
      3552553.68     10227072.11       3552966.1     10226803.32
      3553414.88     10227352.67      3553934.63     10227678.19
      3555034.45     10227742.43      3556064.57     10226908.83
      3556961.98      10226952.9      3557432.86     10227160.88
      3557388.29      10226985.2      3557692.88     10227056.02
      3558077.58     10226714.65      3558116.18     10226469.21
      3558366.58     10226829.32      3558420.18     10226354.98
       3558717.5     10226498.39      3558782.11     10226331.64

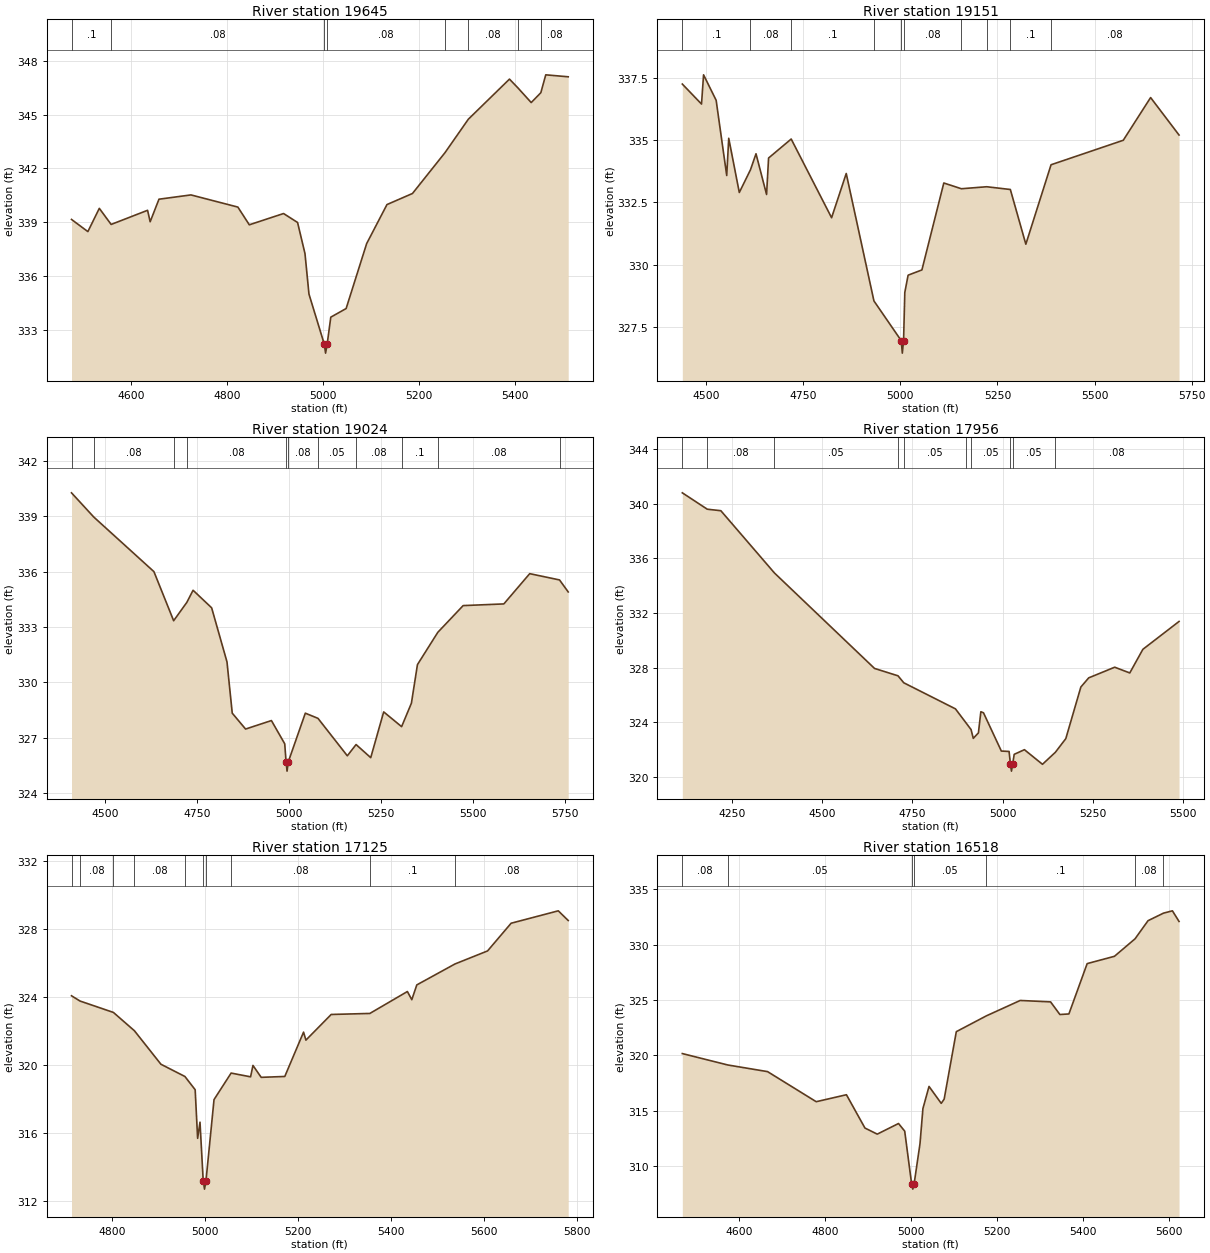
Type RM Length L Ch R = 1 ,19645   ,494,494,494
BEGIN DESCRIPTION:
SEWER CREEK 41.0
END DESCRIPTION:
XS GIS Cut Line= 3
      3544425.53     10230881.99      3544627.23     10230396.96
      3544804.81     10229916.53
#Sta/Elev= 30
  4474.7  339.15  4508.9  338.47  4532.8  339.77  4557.5  338.87  4633.6  339.66
    4639  339.02  4657.4  340.28  4724.2  340.52  4822.2  339.84  4846.1  338.85
  4917.6  339.48  4946.9  338.98  4962.4  337.24  4970.7  334.98  5002.7  332.18
  5005.4  331.68  5008.7  332.18  5016.3  333.69  5048.3  334.17  5091.2   337.8
  5133.6  339.98  5186.9   340.6  5254.8  342.88  5303.6  344.75  5389.5  346.99
  5406.8  346.51  5434.9  345.68    5455  346.23  5465.3  347.23  5512.2  347.12
#Mann= 8 ,-1 , 0
  4474.7      .1       0  4557.5     .08       0  5002.7     .07       0
  5008.7     .08       0  5254.8      .1       0  5303.6     .08       0
  5406.8      .1       0    5455     .08       0
Bank Sta=5002.7,5008.7
XS Rating Curve= 0 ,0
Exp/Cntr=0.3,0.1

Type RM Length L Ch R = 1 ,19151   ,127,127,127
BEGIN DESCRIPTION:
SEWER CREEK 42.0
END DESCRIPTION:
XS GIS Cut Line= 4
      3544471.32     10230881.84      3544935.03     10230736.55
      3545237.49     10230514.94      3545297.13     10230101.31
#Sta/Elev= 30
  4438.8  337.24  4488.2  336.44  4493.5  337.61  4525.9  336.59  4553.1  333.58
  4558.3  335.07  4585.5   332.9  4614.3  333.81  4628.5  334.45  4655.7  332.82
  4660.9  334.28  4719.1  335.04  4823.1  331.89  4860.8  333.66  4932.1  328.56
  5002.4  326.97  5005.2  326.47  5008.4  326.97  5011.6   328.9  5020.1  329.59
  5055.6   329.8    5112  333.28  5157.3  333.05  5222.4  333.13  5283.3  333.02
  5323.2  330.83  5388.1  334.01    5574  334.99  5644.4   336.7  5717.6   335.2
#Mann= 10 ,-1 , 0
  4438.8      .1       0  4614.3     .08       0  4719.1      .1       0
  4932.1     .08       0  5002.4     .07       0  5008.4     .08       0
  5157.3      .1       0  5222.4     .08       0  5283.3      .1       0
  5388.1     .08       0
Bank Sta=5002.4,5008.4
XS Rating Curve= 0 ,0
Exp/Cntr=0.3,0.1

Type RM Length L Ch R = 1 ,19024   ,1025,1025,1025
BEGIN DESCRIPTION:
SEWER CREEK 40.0
END DESCRIPTION:
XS GIS Cut Line= 3
      3544663.02     10231128.94       3545309.1     10230571.36
      3545354.35     10230077.44
#Sta/Elev= 30
  4408.3  340.27  4468.7  338.96  4632.2     336  4685.8  333.34  4721.5  334.33
  4738.6  334.99    4789  334.04  4830.7  331.11    4845  328.33  4881.2  327.47
  4951.4  327.93  4987.6  326.67  4991.2  325.69  4993.9  325.19  4997.2  325.69
  5043.5  328.33  5077.9  328.05  5157.6  326.02  5181.4  326.63  5221.2  325.92
  5256.4   328.4  5305.1   327.6  5331.7  328.87  5348.1  330.96  5403.4  332.71
  5472.3  334.16  5582.8  334.25  5653.1  335.89  5734.1  335.55  5757.7   334.9
#Mann= 11 ,-1 , 0
  4408.3      .1       0  4468.7     .08       0  4685.8      .1       0
  4721.5     .08       0  4991.2     .07       0  4997.2     .08       0
  5077.9     .05       0  5181.4     .08       0  5305.1      .1       0
  5403.4     .08       0  5734.1      .1       0
Bank Sta=4991.2,4997.2
XS Rating Curve= 0 ,0
Exp/Cntr=0.3,0.1

Type RM Length L Ch R = 1 ,17956   ,874,874,874
BEGIN DESCRIPTION:
SEWER CREEK 38.0
END DESCRIPTION:
XS GIS Cut Line= 4
      3546513.55     10231148.64      3546205.42     10230714.68
      3545881.69     10230410.62       3545642.1     10230091.63
#Sta/Elev= 30
  4113.1   340.8  4182.2   339.6  4219.8  339.49  4368.2  334.93  4645.3  327.94
  4710.3   327.4  4726.2  326.89  4869.3  324.98    4899  323.94  4912.6  323.46
  4918.7  322.82  4932.9  323.22  4939.7  324.77    4947  324.69  4996.4  321.89
  5017.8  321.86  5021.7  320.92  5024.4  320.42  5027.7  320.92    5032  321.65
  5060.3  321.99  5110.3  320.92    5146   321.8  5174.9   322.8  5216.6  326.58
  5238.3  327.25  5310.3  328.03    5352  327.61  5388.3  329.34  5488.4  331.38
#Mann= 10 ,-1 , 0
  4113.1      .1       0  4182.2     .08       0  4368.2     .05       0
  4710.3     .08       0  4726.2     .05       0    4899      .1       0
  4912.6     .05       0  5021.7     .04       0  5027.7     .05       0
    5146     .08       0
Bank Sta=5021.7,5027.7
XS Rating Curve= 0 ,0
Exp/Cntr=0.3,0.1

Type RM Length L Ch R = 1 ,17125   ,607,607,607
BEGIN DESCRIPTION:
SEWER CREEK 36.0
END DESCRIPTION:
XS GIS Cut Line= 3
      3546692.13     10230041.66      3546531.07     10229929.64
      3545671.07     10229779.51
#Sta/Elev= 30
  4712.5  324.05  4730.9  323.74  4802.7  323.07    4848  321.99    4905  320.02
  4956.6   319.3  4978.7  318.52    4984  315.66  4989.1  316.61    4996  313.17
  4998.8  312.67    5002  313.17  5019.3  317.94  5056.1   319.5    5098  319.28
  5103.1  319.95  5120.8  319.25  5171.6   319.3    5212  321.91  5217.1  321.44
  5271.5  322.95  5354.7  323.01  5435.5   324.3    5445  323.82  5455.8  324.69
  5537.8  325.92  5608.1  326.69  5658.8  328.32  5760.3  329.05  5781.7  328.48
#Mann= 10 ,-1 , 0
  4712.5     .05       0  4730.9     .08       0  4802.7     .05       0
    4848     .08       0  4956.6      .1       0    4996     .07       0
    5002      .1       0  5056.1     .08       0  5354.7      .1       0
  5537.8     .08       0
Bank Sta=4996,5002
XS Rating Curve= 0 ,0
Exp/Cntr=0.3,0.1

Type RM Length L Ch R = 1 ,16518   ,714,714,714
BEGIN DESCRIPTION:
SEWER CREEK 35.0
END DESCRIPTION:
XS GIS Cut Line= 3
      3546896.67     10229755.57      3546552.87     10229339.35
      3546101.03     10228920.59
#Sta/Elev= 30
  4468.3  320.17    4574  319.14  4666.6  318.54  4779.9  315.82  4850.2  316.45
  4893.3  313.44  4921.9  312.89  4971.4  313.85  4985.8  313.16  5001.8  308.42
  5004.6  307.92  5007.8  308.42  5021.4  312.03  5028.2   315.2  5042.4   317.2
  5070.8  315.67  5077.6  316.05  5105.9  322.15  5175.9  323.58  5254.6  324.97
  5325.3  324.84  5346.9   323.7  5367.9  323.75  5410.4   328.3  5473.9  328.96
  5521.8  330.54  5552.1  332.18    5588  332.86  5608.8  333.07  5624.2  332.11
#Mann= 7 ,-1 , 0
  4468.3     .08       0    4574     .05       0  5001.8     .04       0
  5007.8     .05       0  5175.9      .1       0  5521.8     .08       0
    5588      .1       0
Bank Sta=5001.8,5007.8
XS Rating Curve= 0 ,0
Exp/Cntr=0.3,0.1

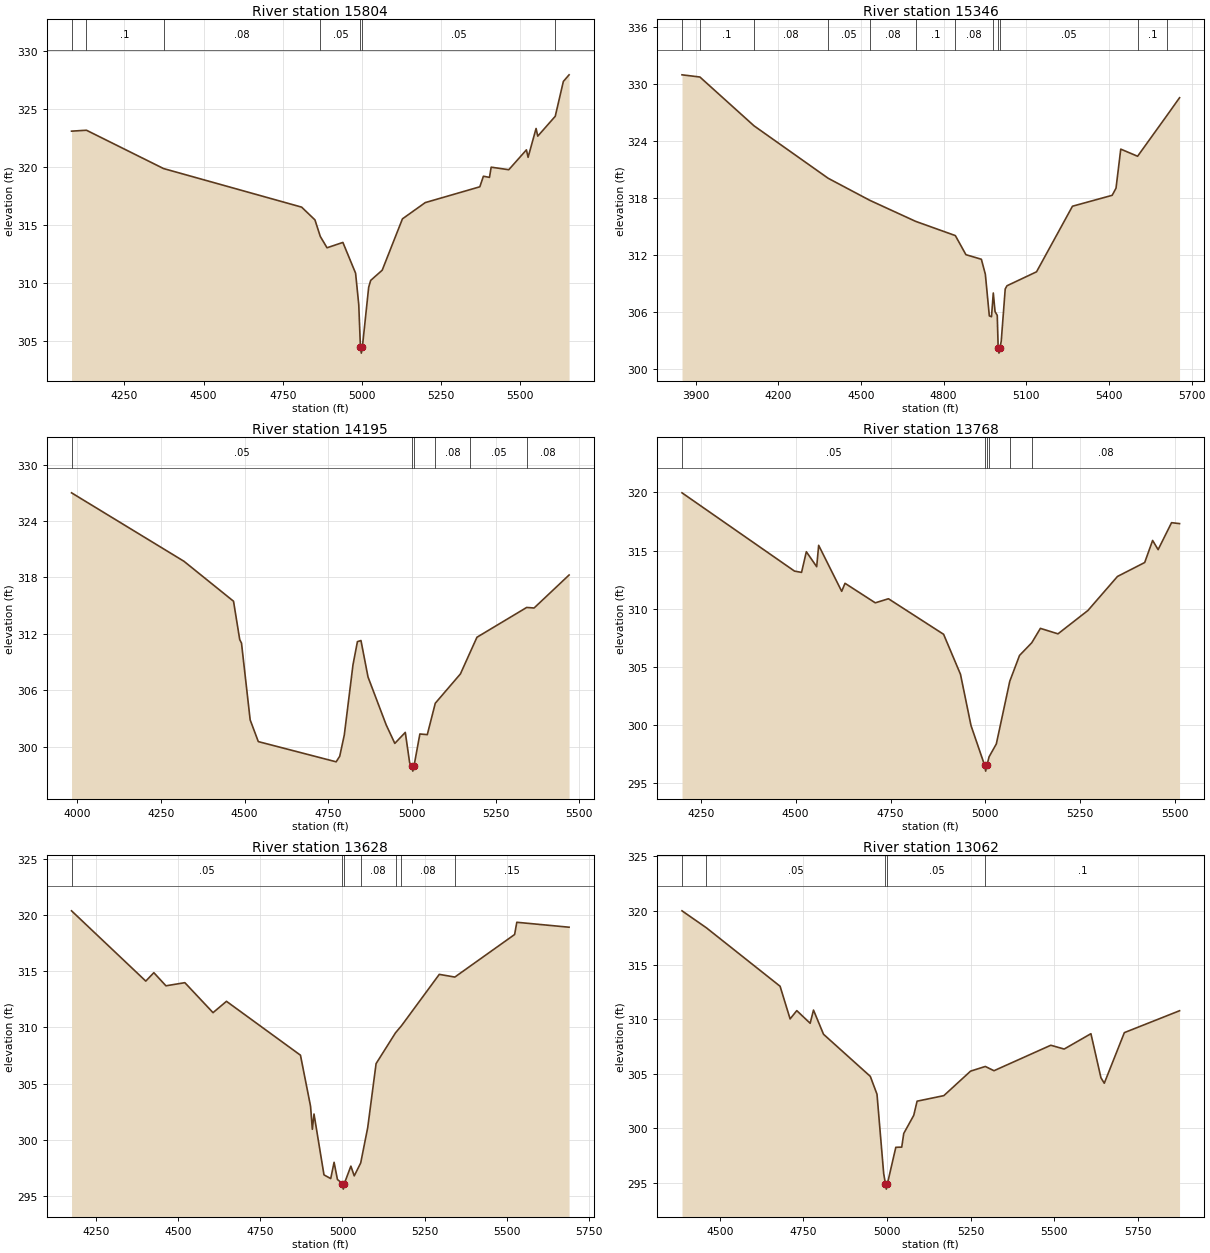
Type RM Length L Ch R = 1 ,15804   ,458,458,458
BEGIN DESCRIPTION:
SEWER CREEK 33.0
END DESCRIPTION:
XS GIS Cut Line= 3
      3547298.96     10230146.38      3547236.85     10229231.49
      3547011.61     10228617.71
#Sta/Elev= 30
    4083  323.09  4130.1  323.17  4373.5  319.87  4809.4  316.55  4851.5  315.45
  4868.3  314.03  4889.6  313.05  4939.7  313.51  4979.8  310.86  4989.8  308.15
  4995.1  304.48  4997.9  303.98  5001.1  304.48  5021.1  309.65  5027.4  310.24
  5063.8  311.12  5127.7  315.54  5199.7  316.94    5372   318.3  5383.3  319.21
  5402.5  319.11  5407.8  319.99  5463.4  319.77  5519.1  321.48  5524.4  320.84
  5549.6  323.32  5554.9  322.66  5610.1  324.37  5635.7  327.37  5653.8  327.94
#Mann= 7 ,-1 , 0
    4083     .08       0  4130.1      .1       0  4373.5     .08       0
  4868.3     .05       0  4995.1     .04       0  5001.1     .05       0
  5610.1      .1       0
Bank Sta=4995.1,5001.1
XS Rating Curve= 0 ,0
Exp/Cntr=0.3,0.1

Type RM Length L Ch R = 1 ,15346   ,1151,1151,1151
BEGIN DESCRIPTION:
SEWER CREEK 32.0
END DESCRIPTION:
XS GIS Cut Line= 3
      3548310.38     10229950.96      3547479.99     10228906.58
      3547276.54     10228480.98
#Sta/Elev= 30
  3850.2  330.99  3915.1  330.76  4111.7  325.62  4380.9   320.1    4532  317.78
  4698.1  315.57  4842.4  314.07  4880.8  312.06  4936.8  311.58  4951.3     310
  4965.7  305.62  4973.6  305.53  4977.3  306.95  4980.1  308.03  4986.5  306.07
  4994.5  305.67  4997.9   302.2  5000.7   301.7  5003.9   302.2  5008.9  302.95
  5023.4  308.45  5029.8  308.79  5137.1  310.26  5267.5  317.16  5411.6  318.31
  5425.6  319.06  5442.8  323.17  5503.9  322.42  5611.6  326.76  5656.2  328.58
#Mann= 12 ,-1 , 0
  3850.2     .08       0  3915.1      .1       0  4111.7     .08       0
  4380.9     .05       0    4532     .08       0  4698.1      .1       0
  4842.4     .08       0  4977.3     .05       0  4997.9     .04       0
  5003.9     .05       0  5503.9      .1       0  5611.6     .15       0
Bank Sta=4997.9,5003.9
XS Rating Curve= 0 ,0
Exp/Cntr=0.3,0.1

Type RM Length L Ch R = 1 ,14195   ,427,427,427
BEGIN DESCRIPTION:
SEWER CREEK 30.0
END DESCRIPTION:
XS GIS Cut Line= 3
       3548471.3     10229399.24      3548142.11     10228441.64
      3547839.15     10228077.49
#Sta/Elev= 30
    3983     327  4318.8  319.72  4466.9  315.47  4485.4  311.39  4490.7  311.02
  4516.6  302.85  4540.9  300.54  4773.5  298.39  4784.1  298.98  4797.8  301.24
  4823.8  308.72    4837  311.17  4847.6  311.29  4868.7  307.41  4922.8  302.33
  4948.7  300.35    4980  301.52    4993   298.3  4999.8   297.9  5002.5   297.4
  5005.8   297.9  5023.6  301.35  5045.7  301.28  5069.6  304.62  5144.7  307.74
  5173.4  310.01  5194.1  311.64  5342.7  314.81  5364.7  314.75  5469.3  318.26
#Mann= 6 ,-1 , 0
    3983     .05       0  4999.8     .04       0  5005.8     .05       0
  5069.6     .08       0  5173.4     .05       0  5342.7     .08       0
Bank Sta=4999.8,5005.8
XS Rating Curve= 0 ,0
Exp/Cntr=0.3,0.1

Type RM Length L Ch R = 1 ,13768   ,140,140,140
BEGIN DESCRIPTION:
SEWER CREEK 29.1
END DESCRIPTION:
XS GIS Cut Line= 4
      3548689.96     10228968.14        3548512.     10228308.39
      3548392.64     10228074.02      3548101.84     10227852.66
#Sta/Elev= 30
  4200.3  319.97    4497  313.23  4515.5  313.12  4528.1   314.9  4555.4  313.61
  4560.6  315.45  4621.3  311.49  4630.1  312.18  4709.9   310.5  4744.6  310.85
    4890  307.79  4934.5  304.35  4962.3  299.93  4998.2  296.51  5000.9  296.01
  5004.2  296.51  5009.9  297.24    5029  298.35  5064.5  303.75  5090.2  305.97
  5122.4  307.06  5145.2   308.3  5191.6  307.83  5270.5  309.84  5348.4  312.77
  5420.2  313.97  5441.1  315.87  5455.6  315.08    5491   317.4  5512.1  317.32
#Mann= 6 ,-1 , 0
  4200.3     .05       0  4998.2     .04       0  5004.2     .05       0
  5009.9     .08       0  5064.5     .05       0  5122.4     .08       0
Bank Sta=4998.2,5004.2
XS Rating Curve= 0 ,0
Exp/Cntr=0.3,0.1

Type RM Length L Ch R = 1 ,13628   ,566,566,566
BEGIN DESCRIPTION:
SEWER CREEK 29.0
END DESCRIPTION:
XS GIS Cut Line= 3
      3548758.65     10228962.48       3548560.2      10228024.2
      3548241.42     10227571.76
#Sta/Elev= 30
  4176.4  320.39  4402.1  314.13  4426.6  314.88  4463.4  313.71  4520.9  313.99
  4606.5  311.32  4647.4  312.33  4872.3  307.53    4903  302.98  4908.4  300.93
  4913.5  302.29  4943.8  296.87  4964.3  296.54  4974.5  297.99  4984.7  296.46
  4999.7   296.1  5002.5   295.6  5005.7   296.1  5025.6  297.65  5035.8  296.78
  5055.4  297.93  5076.7  301.07  5102.2  306.78  5161.4  309.53  5179.3  310.15
  5294.3  314.73  5341.6  314.49  5523.3  318.28    5530  319.37  5688.9  318.93
#Mann= 7 ,-1 , 0
  4176.4     .05       0  4999.7     .04       0  5005.7     .05       0
  5055.4     .08       0  5161.4      .1       0  5179.3     .08       0
  5341.6     .15       0
Bank Sta=4999.7,5005.7
XS Rating Curve= 0 ,0
Exp/Cntr=0.3,0.1

Type RM Length L Ch R = 1 ,13062   ,146,146,146
BEGIN DESCRIPTION:
SEWER CREEK 27.1
END DESCRIPTION:
XS GIS Cut Line= 3
      3549113.37     10228865.17      3549127.69     10228224.11
      3549096.02     10227376.52
#Sta/Elev= 30
  4386.4  319.97  4459.4  318.41    4680  313.04    4710  310.04    4730   310.8
    4770  309.64    4780  310.85    4810  308.63  4950.1  304.76  4970.1  303.12
  4990.1  295.84  4995.3   294.9    4998   294.4  5001.3   294.9  5026.4  298.24
  5044.2  298.26  5050.1  299.51  5080.1  301.18  5090.1  302.48  5170.2  302.99
  5250.2  305.24  5294.4  305.67  5320.3  305.28  5490.4  307.62  5530.4  307.27
  5610.5  308.68  5640.5  304.63  5650.5  304.13  5710.6  308.78  5875.8  310.79
#Mann= 5 ,-1 , 0
  4386.4      .1       0  4459.4     .05       0  4995.3     .04       0
  5001.3     .05       0  5294.4      .1       0
Bank Sta=4995.3,5001.3
XS Rating Curve= 0 ,0
Exp/Cntr=0.3,0.1

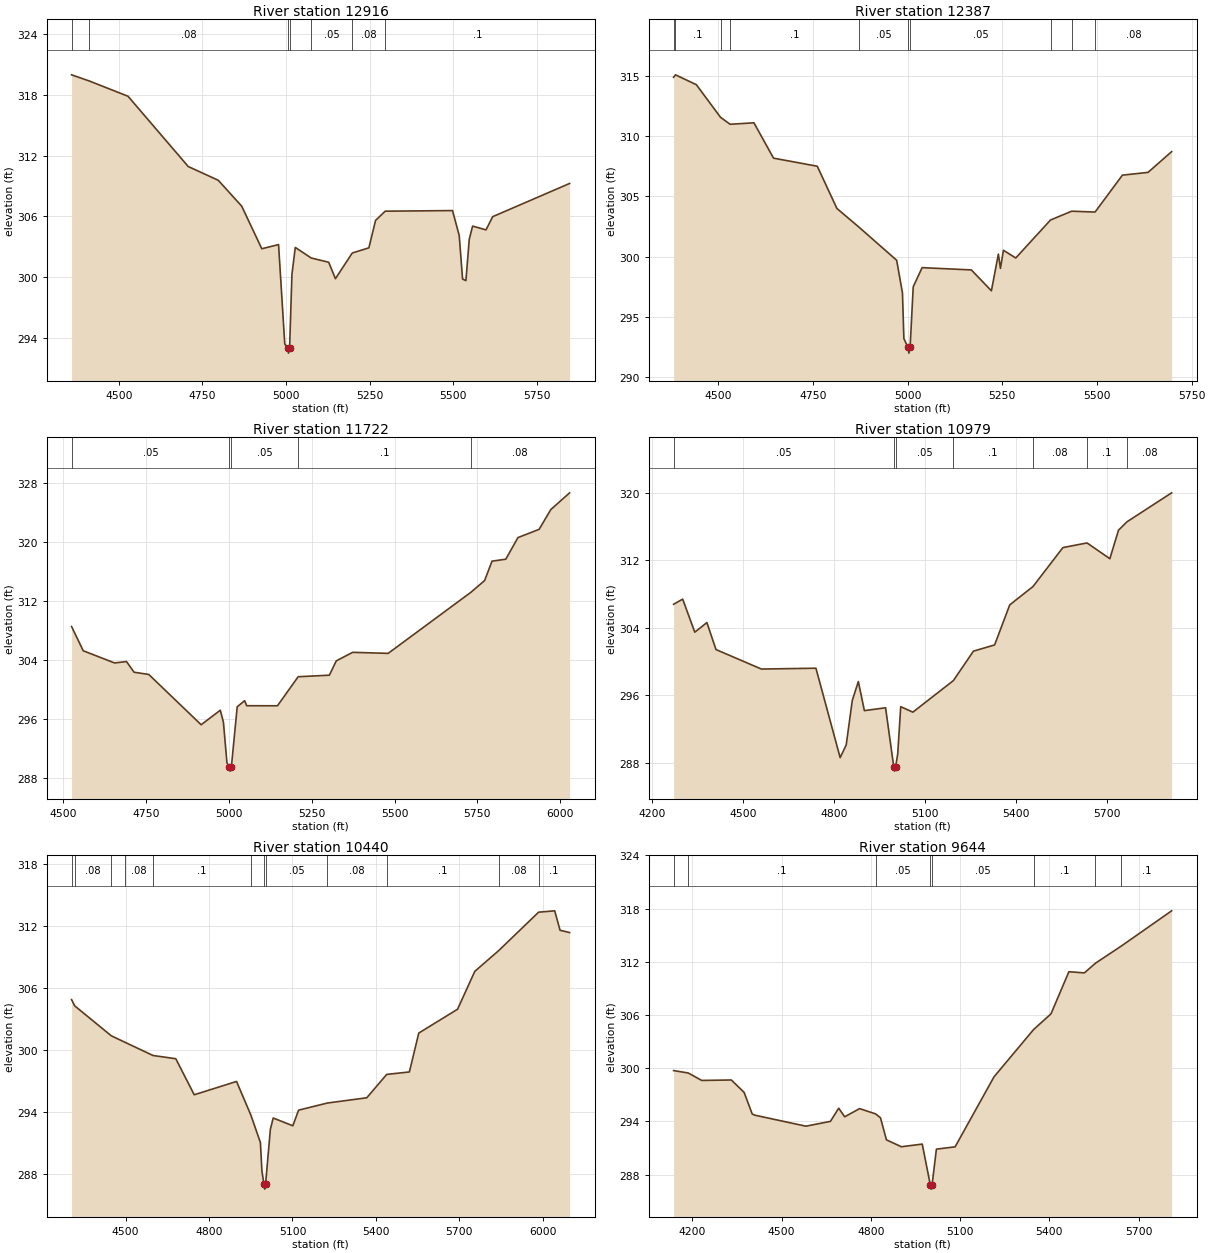
Type RM Length L Ch R = 1 ,12916   ,529,529,529
BEGIN DESCRIPTION:
SEWER CREEK 27.0
END DESCRIPTION:
XS GIS Cut Line= 3
      3549256.36     10228870.44      3549270.67      10228229.4
        3549239.     10227381.79
#Sta/Elev= 30
  4358.8  319.95  4412.1  319.34  4527.6  317.84  4707.7  310.92  4797.7  309.56
  4867.7  307.01  4927.7  302.82  4977.8  303.23  4996.4  293.45  5004.8  293.04
  5007.5  292.54  5010.8  293.04  5017.8  300.28  5027.8  302.95  5075.5  301.91
  5127.8  301.49  5147.9  299.87  5198.2   302.4  5247.9  302.91  5267.9  305.61
  5296.7  306.52  5498.1  306.58  5518.1  304.12  5528.1  299.84  5538.1  299.68
  5548.1  303.75  5558.1  305.05  5598.2  304.68  5618.2  305.98  5848.2  309.25
#Mann= 7 ,-1 , 0
  4358.8      .1       0  4412.1     .08       0  5004.8     .07       0
  5010.8     .08       0  5075.5     .05       0  5198.2     .08       0
  5296.7      .1       0
Bank Sta=5004.8,5010.8
XS Rating Curve= 0 ,0
Exp/Cntr=0.3,0.1

Type RM Length L Ch R = 1 ,12387   ,665,665,665
BEGIN DESCRIPTION:
SEWER CREEK 26.0
END DESCRIPTION:
XS GIS Cut Line= 3
      3550088.11     10228559.27      3549763.14     10228041.64
      3549492.12     10227391.67
#Sta/Elev= 30
  4381.7  314.89  4386.7  315.09  4441.9  314.27  4505.6  311.57  4530.9  310.99
  4593.9  311.11  4645.7  308.18  4761.2  307.51    4813  304.01  4872.3  302.43
  4970.9  299.71  4986.2     297  4989.9  293.22  5000.4  292.51  5003.2  292.01
  5006.4  292.51  5014.6  297.51  5038.1   299.1  5168.1  298.91  5221.1  297.18
  5239.5  300.22    5245  299.04  5252.9  300.54  5285.4   299.9  5377.2  303.05
  5433.1  303.78  5494.9  303.71  5567.1  306.77  5634.9     307  5697.1  308.72
#Mann= 10 ,-1 , 0
  4381.7     .08       0  4386.7      .1       0  4505.6     .08       0
  4530.9      .1       0  4872.3     .05       0  5000.4     .04       0
  5006.4     .05       0  5377.2     .08       0  5433.1      .1       0
  5494.9     .08       0
Bank Sta=5000.4,5006.4
XS Rating Curve= 0 ,0
Exp/Cntr=0.3,0.1

Type RM Length L Ch R = 1 ,11722   ,743,743,743
BEGIN DESCRIPTION:
SEWER CREEK 24.0
END DESCRIPTION:
XS GIS Cut Line= 3
      3550542.09     10228041.61      3550292.11     10227641.64
      3549642.13     10226841.67
#Sta/Elev= 30
  4525.7  308.54    4561  305.25  4655.4   303.6  4691.4  303.79  4714.3  302.34
  4758.6  302.04  4916.6  295.22  4974.4  297.19  4983.8  295.57  4994.4  290.08
  5001.6  289.43  5004.3  288.93  5007.6  289.43  5025.4  297.65  5047.7  298.48
  5054.1   297.8  5146.8  297.79  5209.3  301.73  5303.4  301.94  5324.2  303.88
  5373.7  305.04  5480.8   304.9    5730  313.17  5771.7  314.77    5794   317.4
  5835.6  317.67  5872.3   320.6  5936.2  321.72  5971.4   324.4  6028.1  326.67
#Mann= 5 ,-1 , 0
  4525.7     .05       0  5001.6     .04       0  5007.6     .05       0
  5209.3      .1       0    5730     .08       0
Bank Sta=5001.6,5007.6
XS Rating Curve= 0 ,0
Exp/Cntr=0.3,0.1

Type RM Length L Ch R = 1 ,10979   ,539,539,539
BEGIN DESCRIPTION:
SEWER CREEK 22.0
END DESCRIPTION:
XS GIS Cut Line= 3
      3550892.11      10227941.6      3550881.02     10226655.44
      3550734.62     10226328.42
#Sta/Elev= 30
    4270  306.79    4300   307.4    4340  303.48    4380  304.62    4410  301.42
    4560  299.11    4740  299.21    4820  288.61    4840  290.12    4860  295.38
    4880  297.63    4900  294.18    4970  294.52    4997  287.51  4999.7  287.01
    5003  287.51    5010  289.03    5020  294.65    5060     294  5194.1  297.75
    5260  301.23    5330  301.97    5380  306.72  5456.7  308.89  5555.6  313.51
  5635.2  314.06  5710.5  312.19  5739.1  315.57  5767.3  316.57  5914.5     320
#Mann= 7 ,-1 , 0
    4270     .05       0    4997     .04       0    5003     .05       0
  5194.1      .1       0  5456.7     .08       0  5635.2      .1       0
  5767.3     .08       0
Bank Sta=4997,5003
XS Rating Curve= 0 ,0
Exp/Cntr=0.3,0.1

Type RM Length L Ch R = 1 ,10440   ,796,796,796
BEGIN DESCRIPTION:
SEWER CREEK 21.0
END DESCRIPTION:
XS GIS Cut Line= 3
      3551528.64     10227916.56      3551390.72     10227089.05
      3551195.32     10226158.05
#Sta/Elev= 30
    4306  304.87  4317.5  304.26  4448.6  301.37  4498.7  300.73  4598.9  299.46
  4680.6  299.15  4746.9  295.66    4899  296.95  4950.3  293.71  4984.8  291.04
  4990.2  288.29  4997.4  287.03  5000.1  286.53  5003.4  287.03  5020.6  292.32
  5030.8  293.41  5101.4  292.66    5122  294.17  5225.3  294.86  5367.1  295.37
  5438.7  297.63  5520.3  297.87    5554  301.63  5693.5  303.94  5755.3   307.6
  5841.3  309.61  5984.8  313.33  6042.7  313.46  6061.9  311.58  6096.2  311.36
#Mann= 12 ,-1 , 0
    4306      .1       0  4317.5     .08       0  4448.6     .05       0
  4498.7     .08       0  4598.9      .1       0  4950.3     .05       0
  4997.4     .04       0  5003.4     .05       0  5225.3     .08       0
  5438.7      .1       0  5841.3     .08       0  5984.8      .1       0
Bank Sta=4997.4,5003.4
XS Rating Curve= 0 ,0
Exp/Cntr=0.3,0.1

Type RM Length L Ch R = 1 ,9644    ,1060,1060,1060
BEGIN DESCRIPTION:
SEWER CREEK 19.0
END DESCRIPTION:
XS GIS Cut Line= 3
      3552103.33     10227675.26      3552042.11     10226791.64
      3551953.91     10226008.63
#Sta/Elev= 30
  4137.1  299.73  4186.3  299.46  4231.5  298.62  4331.2  298.67  4374.1  297.27
  4401.4  294.83  4411.4  294.69  4581.8  293.46  4664.1     294    4692  295.49
  4712.1  294.52  4762.2  295.44  4815.7  294.85  4832.4   294.4  4852.4  291.92
  4902.5  291.14  4972.7  291.44  4999.8  286.86  5002.5  286.36  5005.8  286.86
  5020.3  290.87  5083.2  291.13    5214  299.03  5347.2  304.37  5405.2  306.12
  5465.6  310.88  5517.6  310.75  5554.8  311.84  5641.4  313.77  5810.8  317.75
#Mann= 8 ,-1 , 0
  4137.1     .05       0  4186.3      .1       0  4815.7     .05       0
  4999.8     .04       0  5005.8     .05       0  5347.2      .1       0
  5554.8     .08       0  5641.4      .1       0
Bank Sta=4999.8,5005.8
XS Rating Curve= 0 ,0
Exp/Cntr=0.3,0.1

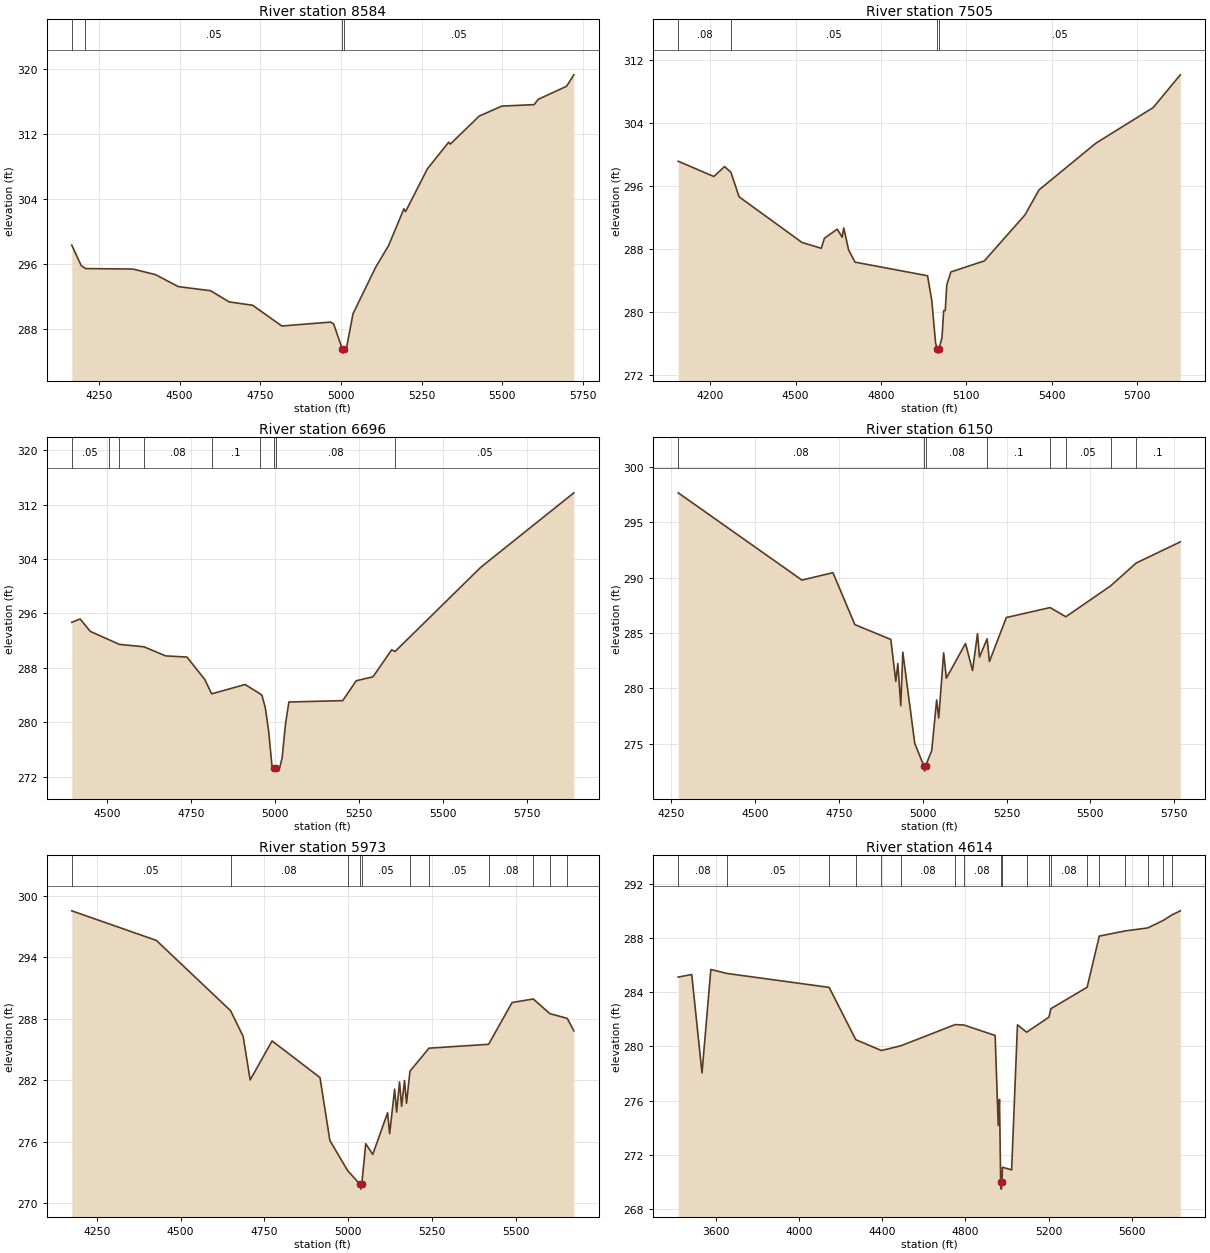
Type RM Length L Ch R = 1 ,8584    ,1079,1079,1079
BEGIN DESCRIPTION:
SEWER CREEK 17.0
END DESCRIPTION:
XS GIS Cut Line= 3
      3552850.42      10227640.7      3552902.17     10226952.42
      3552965.36     10226089.06
#Sta/Elev= 30
  4165.8  298.34  4194.9  295.83  4208.3  295.45  4355.4  295.39  4425.6   294.7
  4495.8  293.23  4596.1  292.72  4653.2  291.35  4726.4  290.93  4816.7  288.38
  4967.1  288.86  4977.1  288.66  5004.2  285.54    5007  285.04  5010.2  285.54
  5017.2  285.68  5037.3  289.88  5107.5  295.61  5147.6  298.28  5195.2  302.81
  5200.2  302.46  5267.9  307.73  5333.9  311.01  5338.9  310.77  5428.3  314.22
  5498.5  315.45  5598.8  315.63  5611.2  316.28  5699.1  317.89  5721.7   319.3
#Mann= 4 ,-1 , 0
  4165.8      .1       0  4208.3     .05       0  5004.2     .04       0
  5010.2     .05       0
Bank Sta=5004.2,5010.2
XS Rating Curve= 0 ,0
Exp/Cntr=0.3,0.1

Type RM Length L Ch R = 1 ,7505    ,809,809,809
BEGIN DESCRIPTION:
SEWER CREEK 14.0
END DESCRIPTION:
XS GIS Cut Line= 3
      3553287.19     10228284.38      3553692.11     10227441.64
      3554080.24     10226709.76
#Sta/Elev= 30
  4088.1  299.14  4213.2   297.2  4250.8  298.47  4273.2  297.72  4301.9  294.62
  4522.5  288.82  4590.4  288.07  4601.5  289.35  4646.7  290.51  4663.8  289.48
  4669.4  290.66  4686.5  287.86  4709.1  286.31  4963.7  284.58  4978.7  281.42
  4991.9  276.04  4997.9  275.24  5000.6  274.74  5003.9  275.24  5014.5  276.72
  5020.3  280.14  5025.9  280.14  5031.2  283.41  5045.7  285.06  5163.2  286.47
  5305.8  292.31  5355.4   295.5  5555.1  301.44  5756.3  305.97  5851.5  310.13
#Mann= 4 ,-1 , 0
  4088.1     .08       0  4273.2     .05       0  4997.9     .04       0
  5003.9     .05       0
Bank Sta=4997.9,5003.9
XS Rating Curve= 0 ,0
Exp/Cntr=0.3,0.1

Type RM Length L Ch R = 1 ,6696    ,546,546,546
BEGIN DESCRIPTION:
SEWER CREEK 12.0
END DESCRIPTION:
XS GIS Cut Line= 3
       3554195.2     10228249.89      3554392.11     10227941.64
      3554459.43     10226814.93
#Sta/Elev= 30
  4395.5   294.7  4420.4  295.19  4450.8  293.36  4505.8  292.15  4536.8  291.46
  4610.4   291.1    4675  289.76  4738.4  289.59  4791.3   286.3  4811.9  284.18
  4911.5  285.55  4954.6  284.23  4961.6  283.97  4971.7  282.11  4981.7  278.62
  4991.7  273.42  4998.7  273.31  5001.5  272.81  5004.7  273.31  5014.7  273.36
  5021.7  274.77  5031.8  279.79  5041.8  282.98  5202.1  283.18  5242.1   286.1
  5292.2  286.69  5347.7  290.65  5358.1  290.42  5612.8  302.79    5890  313.75
#Mann= 9 ,-1 , 0
  4395.5     .05       0  4505.8     .08       0  4536.8     .05       0
  4610.4     .08       0  4811.9      .1       0  4954.6     .08       0
  4998.7     .07       0  5004.7     .08       0  5358.1     .05       0
Bank Sta=4998.7,5004.7
XS Rating Curve= 0 ,0
Exp/Cntr=0.3,0.1

Type RM Length L Ch R = 1 ,6150    ,177,177,177
BEGIN DESCRIPTION:
SEWER CREEK 11.1
END DESCRIPTION:
XS GIS Cut Line= 3
      3554533.43     10228326.01      3554947.48     10227735.26
      3555397.51     10227103.33
#Sta/Elev= 30
    4271  297.66  4639.9  289.78  4732.3  290.45  4797.7  285.76  4904.9  284.42
  4919.8  280.63  4925.9  282.25  4934.6  278.44  4940.7  283.27  4976.4  275.03
    5003  273.03  5005.7  272.53    5009  273.03  5026.9  274.38  5041.6  278.96
  5047.8  277.32  5062.5  283.21  5070.5  280.92  5127.7  284.06  5148.6  281.62
  5163.4  284.94  5169.5  282.84  5192.2  284.48    5199  282.43  5249.4   286.4
  5379.9   287.3  5426.9  286.47  5560.1  289.25  5636.6  291.32  5768.2  293.23
#Mann= 8 ,-1 , 0
    4271     .08       0    5003     .07       0    5009     .08       0
  5192.2      .1       0  5379.9     .08       0  5426.9     .05       0
  5560.1     .08       0  5636.6      .1       0
Bank Sta=5003,5009
XS Rating Curve= 0 ,0
Exp/Cntr=0.3,0.1

Type RM Length L Ch R = 1 ,5973    ,1359,1359,1359
BEGIN DESCRIPTION:
SEWER CREEK 11.0
END DESCRIPTION:
XS GIS Cut Line= 3
      3554652.79     10228404.14      3555066.83     10227813.38
      3555517.22     10227180.97
#Sta/Elev= 30
  4175.3  298.55  4427.7  295.66  4649.1  288.79  4686.6  286.28  4707.5  282.03
  4772.9  285.84  4915.8  282.26  4945.3  276.11  4998.5  273.16  5034.5  271.86
  5037.3  271.36  5040.5  271.86  5052.3   275.8  5073.2  274.75  5117.5  278.82
  5123.6  276.77  5138.4  281.13  5144.5  278.89  5153.1  281.83  5159.3  279.45
  5167.9  281.97    5174  279.75  5184.2  282.88  5240.9  285.13  5418.8  285.51
  5488.8  289.59  5552.1  289.94  5601.3  288.51  5653.5  288.04  5673.1  286.83
#Mann= 11 ,-1 , 0
  4175.3     .05       0  4649.1     .08       0  4998.5     .05       0
  5034.5     .04       0  5040.5     .05       0  5184.2     .08       0
  5240.9     .05       0  5418.8     .08       0  5552.1      .1       0
  5601.3     .08       0  5653.5     .05       0
Bank Sta=5034.5,5040.5
XS Rating Curve= 0 ,0
Exp/Cntr=0.3,0.1

Type RM Length L Ch R = 1 ,4614    ,239,239,239
BEGIN DESCRIPTION:
SEWER CREEK 8.0
END DESCRIPTION:
XS GIS Cut Line= 3
      3555157.94     10228119.07      3555789.92     10227456.69
      3556645.32     10226225.36
#Sta/Elev= 30
  3418.7  285.11  3483.6   285.3    3533  278.05  3575.5  285.67    3652  285.38
  4144.6  284.35  4272.6   280.5  4395.8   279.7  4489.5  280.05  4750.7  281.61
  4792.2  281.58  4942.9  280.81  4957.8  274.18  4963.8   276.1  4969.6  269.99
  4972.4  269.49  4975.6  269.99  4978.1   271.1  5022.2  270.91  5050.3  281.59
  5094.5  281.05  5201.9  282.16    5211  282.78  5385.3  284.36  5443.9  288.13
  5568.8  288.51  5676.7  288.73  5752.3  289.29  5793.2  289.69  5833.5  289.99
#Mann= 20 ,-1 , 0
  3418.7     .08       0    3652     .05       0  4144.6      .1       0
  4272.6     .08       0  4395.8     .05       0  4489.5     .08       0
  4750.7     .05       0  4792.2     .08       0  4969.6     .07       0
  4975.6     .08       0  4978.1      .1       0  5094.5     .08       0
  5201.9      .1       0    5211     .08       0  5385.3      .1       0
  5443.9     .08       0  5568.8      .1       0  5676.7     .08       0
  5752.3      .1       0  5793.2     .08       0
Bank Sta=4969.6,4975.6
XS Rating Curve= 0 ,0
Exp/Cntr=0.3,0.1

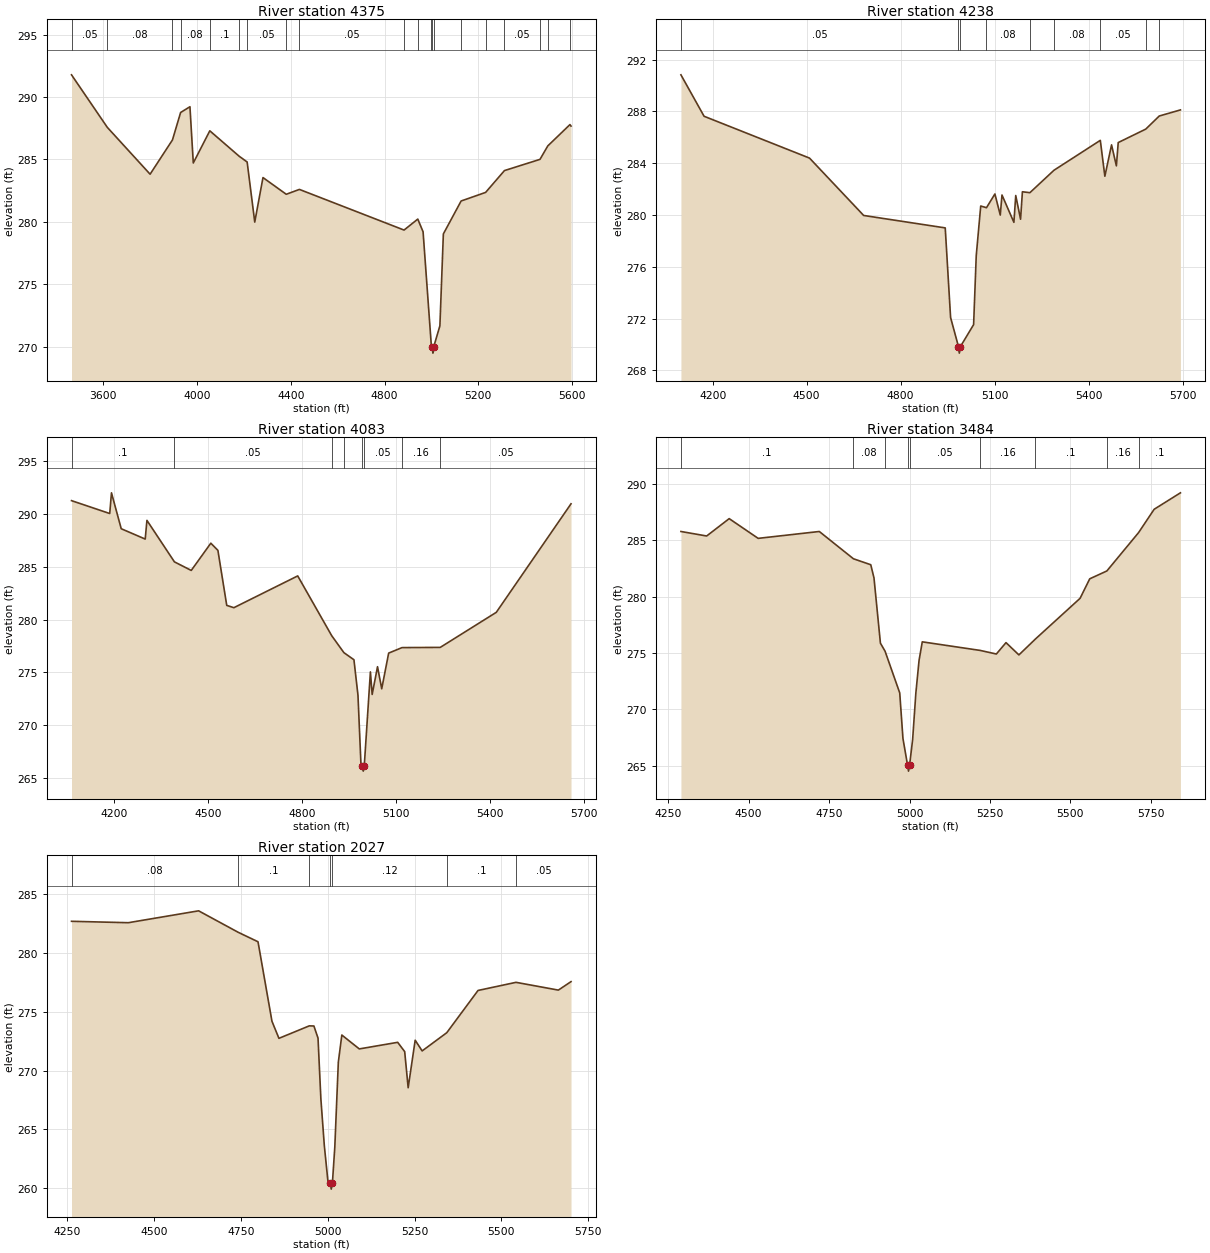
Type RM Length L Ch R = 1 ,4375    ,137,137,137
BEGIN DESCRIPTION:
SEWER CREEK 7.0
END DESCRIPTION:
XS GIS Cut Line= 3
      3555468.73     10228151.14       3556002.6     10227526.13
      3556744.55     10226445.86
#Sta/Elev= 30
  3463.8  291.79  3616.5  287.58  3799.3  283.82  3894.8  286.57  3929.6  288.77
  3969.4  289.23  3983.7  284.72  4054.2   287.3  4179.6  285.26  4213.6   284.8
  4246.1  279.98  4281.2  283.55  4380.6  282.21  4436.7   282.6  4883.5  279.34
  4942.1  280.22  4964.7   279.2  4999.6  270.16    5004  269.97  5006.7  269.47
    5010  269.97  5036.5  271.66  5051.3  279.03  5127.1  281.67  5231.7  282.36
  5312.1  284.11  5463.8  285.01  5497.2  286.09  5591.8   287.8  5596.3  287.68
#Mann= 20 ,-1 , 0
  3463.8     .05       0  3616.5     .08       0  3894.8     .05       0
  3929.6     .08       0  4054.2      .1       0  4179.6     .08       0
  4213.6     .05       0  4380.6     .08       0  4436.7     .05       0
  4883.5     .08       0  4942.1     .05       0  4999.6     .08       0
    5004     .07       0    5010     .08       0  5127.1     .05       0
  5231.7     .08       0  5312.1     .05       0  5463.8     .08       0
  5497.2     .05       0  5591.8     .08       0
Bank Sta=5004,5010
XS Rating Curve= 0 ,0
Exp/Cntr=0.3,0.1

Type RM Length L Ch R = 1 ,4238    ,155,155,155
BEGIN DESCRIPTION:
SEWER CREEK 5.1
END DESCRIPTION:
XS GIS Cut Line= 3
       3556154.5     10227751.84      3556605.89     10226809.99
      3556892.51     10226340.26
#Sta/Elev= 30
  4098.6  290.83  4172.5  287.63  4509.1   284.4    4682  279.97  4942.4  279.01
  4959.5  272.09  4984.7  269.84  4987.4  269.34  4990.7  269.84    5033  271.54
  5041.4  276.87  5055.7   280.7  5074.1  280.57    5101  281.63  5118.1     280
  5123.6  281.55  5161.6  279.44  5167.5  281.51  5182.9  279.68  5188.8   281.8
  5212.7  281.73  5289.5  283.46  5437.5  285.77    5452     283  5473.4  285.42
  5488.8   283.8  5494.7   285.6  5582.7  286.64  5625.7  287.65  5693.3  288.12
#Mann= 9 ,-1 , 0
  4098.6     .05       0  4984.7     .04       0  4990.7     .05       0
  5074.1     .08       0  5212.7     .05       0  5289.5     .08       0
  5437.5     .05       0  5582.7     .08       0  5625.7     .05       0
Bank Sta=4984.7,4990.7
XS Rating Curve= 0 ,0
Exp/Cntr=0.3,0.1

Type RM Length L Ch R = 1 ,4083    ,599,599,599
BEGIN DESCRIPTION:
SEWER CREEK 5.2
END DESCRIPTION:
XS GIS Cut Line= 3
      3556293.47     10227794.78      3556744.87      10226852.9
      3557031.52     10226383.11
#Sta/Elev= 30
  4064.8  291.26  4186.8  290.04  4192.4     292  4223.5   288.6  4300.1  287.62
  4305.6  289.39  4393.4  285.46  4447.1  284.65  4509.6  287.23  4532.2  286.55
  4560.4  281.34  4583.1  281.12    4787  284.13  4895.5  278.47  4934.5  276.86
  4966.5  276.19  4979.4  272.83  4988.7  266.43  4993.5  266.14  4996.2  265.64
  4999.5  266.14  5019.1  275.04  5024.7   272.9  5041.8  275.53  5055.2  273.44
  5077.4  276.82  5120.1  277.34  5242.1  277.36    5421  280.68  5659.6  290.96
#Mann= 8 ,-1 , 0
  4064.8      .1       0  4393.4     .05       0  4895.5     .08       0
  4934.5     .05       0  4993.5     .04       0  4999.5     .05       0
  5120.1     .16       0  5242.1     .05       0
Bank Sta=4993.5,4999.5
XS Rating Curve= 0 ,0
Exp/Cntr=0.3,0.1

Type RM Length L Ch R = 1 ,3484    ,1457,1457,1457
BEGIN DESCRIPTION:
SEWER CREEK 5.0
END DESCRIPTION:
XS GIS Cut Line= 3
      3557252.51     10227801.61      3557242.11     10227091.64
      3557206.53     10226250.04
#Sta/Elev= 30
  4289.5  285.77  4369.5  285.37  4439.5  286.91  4529.5  285.16  4719.5  285.77
  4825.6  283.35  4879.5  282.82  4889.5  281.65  4909.5  275.86  4923.9  275.15
  4969.5  271.45  4979.5  267.41    4994  265.01  4996.8  264.51    5000  265.01
  5009.6  267.31  5019.6  271.43  5029.6  274.34  5039.6  275.98  5219.3  275.22
  5269.8   274.9  5299.8  275.91  5339.9  274.82  5391.2  276.23    5530  279.84
    5560  281.57  5613.3  282.27  5711.8  285.67  5760.2  287.74  5841.9   289.2
#Mann= 9 ,-1 , 0
  4289.5      .1       0  4825.6     .08       0  4923.9     .05       0
    4994     .04       0    5000     .05       0  5219.3     .16       0
  5391.2      .1       0  5613.3     .16       0  5711.8      .1       0
Bank Sta=4994,5000
XS Rating Curve= 0 ,0
Exp/Cntr=0.3,0.1

Type RM Length L Ch R = 1 ,2027    ,0,0,0
BEGIN DESCRIPTION:
SEWER CREEK 1.0
END DESCRIPTION:
XS GIS Cut Line= 3
      3557965.13     10227479.79       3558048.8     10227067.48
      3557936.09     10226055.35
#Sta/Elev= 30
  4261.6  282.69  4425.2  282.57  4627.8  283.58  4742.1  281.75  4798.9  280.95
  4839.1  274.19  4859.2  272.74  4946.6   273.8  4959.9  273.79  4971.8  272.76
    4980   267.6    4990   263.6  5000.1  260.66  5007.2  260.42  5009.9  259.92
  5013.2  260.42  5020.2  263.52  5030.3  270.71  5040.4  273.02  5090.7  271.84
  5201.3   272.4  5221.5  271.61  5231.5  268.54  5251.7  272.58  5271.8  271.67
  5342.8  273.22  5432.8  276.81  5542.3   277.5  5664.2  276.84  5700.7  277.56
#Mann= 7 ,-1 , 0
  4261.6     .08       0  4742.1      .1       0  4946.6     .12       0
  5007.2     .07       0  5013.2     .12       0  5342.8      .1       0
  5542.3     .05       0
Bank Sta=5007.2,5013.2
XS Rating Curve= 0 ,0
Exp/Cntr=0.3,0.1
Stream Node=SEWER CREEK     ,Reach-1         , 0 , 0 ,Upstream end
Stream Node=SEWER CREEK     ,Reach-1         , 0 , 1 ,Downstream end

Chan Stop Cuts=-1
Use User Specified Reach Order=0
Composite Channel Slope=5