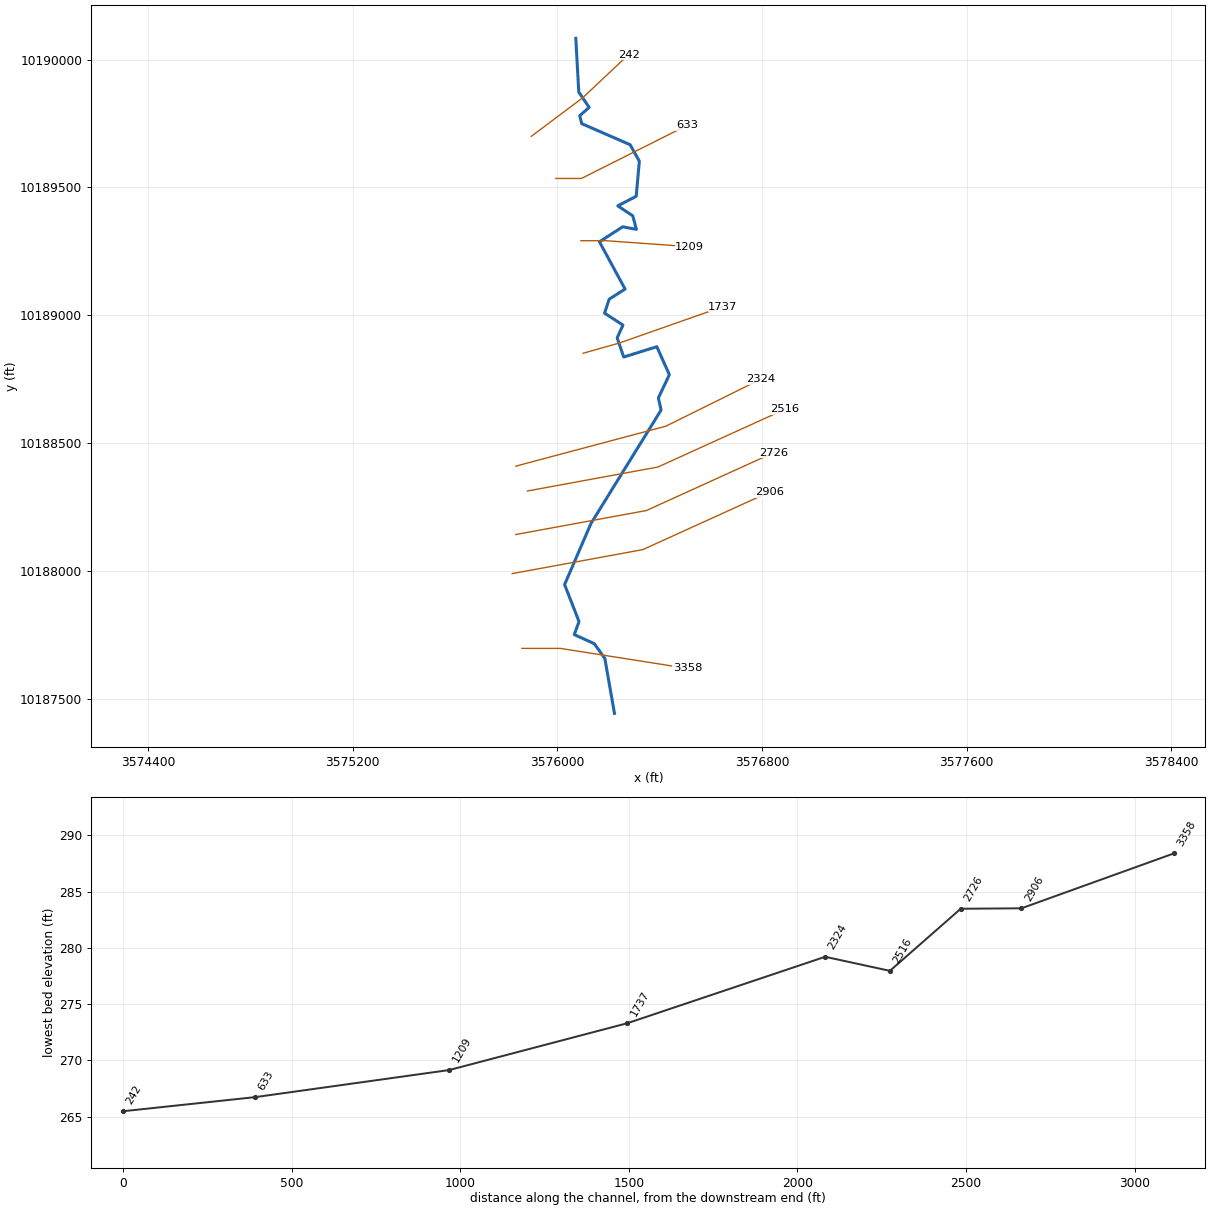
--- SPRING CREEK TRIB 5.prj (project) ---

Proj Title=SPRING CREEK TRIB 5 Base Level Engineering
Current Plan=p01
Default Exp/Contr=0.3,0.1
English Units
Geom File=g01
Flow File=f01
Plan File=p01
BEGIN DESCRIPTION:
SPRING CREEK TRIB 5
END DESCRIPTION:

--- SPRING CREEK TRIB 5.p01 (plan) ---

Plan Title=Multiple Run
Short Identifier=Multiple
Geom File=g01
Flow File=f01
Subcritical Flow
K Sum by GR= 0
Std Step Tol= 0.01
Critical Tol= 0.01
Num of Std Step Trials= 20
Max Error Tol= 0.3
Flow Tol Ratio= 0.001
Split Flow NTrial= 30
Split Flow Tol= 0.02
Split Flow Ratio= 0.02
Log Output Level= 0
Friction Slope Method= 1
Unsteady Friction Slope Method= 2
Unsteady Bridges Friction Slope Method= 1
Parabolic Critical Depth
Global Vel Dist=  1 , 1 , 1
Global Log Level= 0
CheckData=True
Encroach Param= -1, 0, 0, 0
BEGIN DESCRIPTION:
Multiple Run
END DESCRIPTION:

--- SPRING CREEK TRIB 5.f01 (steady flow) ---

Flow Title=Multiple
Number of Profiles=7
Profile Names=10-year,25-year,50-year,1pct_min,100-year,1pct_plu,500-year
River Rch & RM= SPRING CREEK TRI,Reach-1,3358
     276     356     419     364     492     665     675
Boundary for River Rch & Prof#=SPRING CREEK TRI,Reach-1,1
Up Type=0
Dn Type=3
Dn Slope=0.005
Boundary for River Rch & Prof#=SPRING CREEK TRI,Reach-1,2
Up Type=0
Dn Type=3
Dn Slope=0.005
Boundary for River Rch & Prof#=SPRING CREEK TRI,Reach-1,3
Up Type=0
Dn Type=3
Dn Slope=0.005
Boundary for River Rch & Prof#=SPRING CREEK TRI,Reach-1,4
Up Type=0
Dn Type=3
Dn Slope=0.005
Boundary for River Rch & Prof#=SPRING CREEK TRI,Reach-1,5
Up Type=0
Dn Type=3
Dn Slope=0.005
Boundary for River Rch & Prof#=SPRING CREEK TRI,Reach-1,6
Up Type=0
Dn Type=3
Dn Slope=0.005
Boundary for River Rch & Prof#=SPRING CREEK TRI,Reach-1,7
Up Type=0
Dn Type=3
Dn Slope=0.005

--- SPRING CREEK TRIB 5.g01 (geometry) ---

Geom Title=Existing Conditions

River Reach=SPRING CREEK TRI,Reach-1
Reach XY= 30
      3576223.31     10187443.79      3576185.58     10187658.64
      3576144.35     10187716.15      3576066.23     10187751.95
      3576084.67     10187802.95      3576028.25     10187947.27
      3576131.33     10188185.98      3576405.61     10188629.73
      3576394.98     10188677.10      3576437.87     10188767.76
      3576388.94     10188877.37      3576259.43     10188836.90
      3576233.77     10188912.01      3576256.55     10188961.76
      3576184.54     10189008.51      3576202.47     10189062.89
      3576264.70     10189102.81      3576164.55     10189287.49
      3576255.43     10189346.10      3576308.99     10189336.18
      3576294.83     10189389.11      3576236.20     10189428.14
      3576308.22     10189465.32      3576320.56     10189602.65
      3576284.42     10189667.15      3576095.11     10189749.48
      3576087.53     10189780.60      3576124.28     10189812.96
      3576083.78     10189872.81      3576072.11     10190082.96

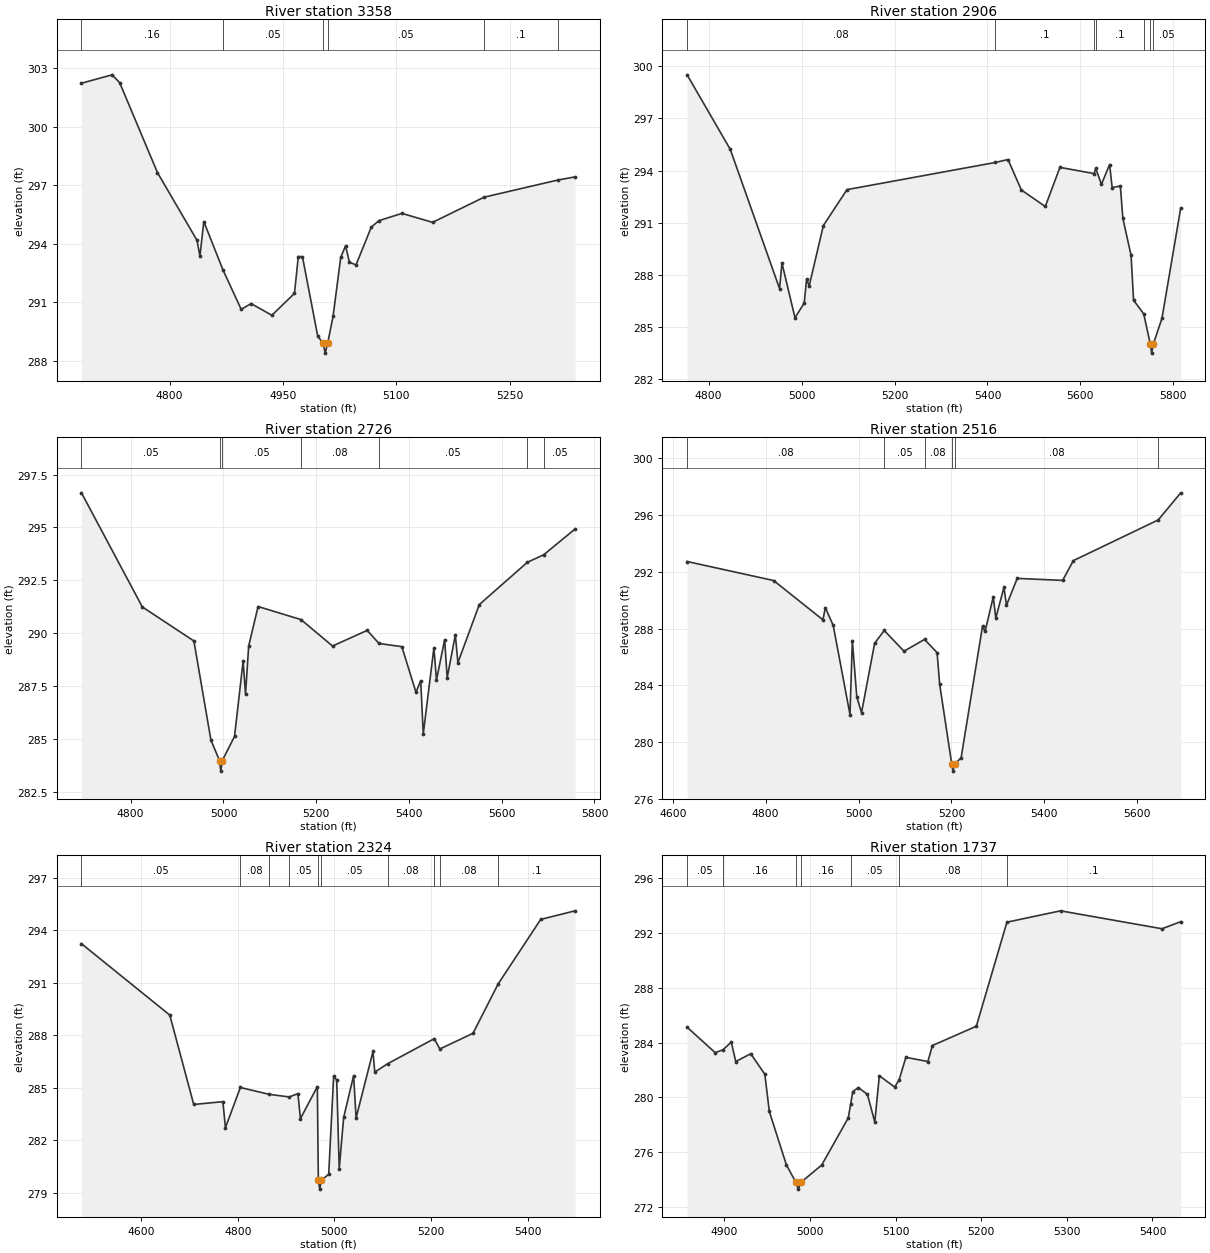
Type RM Length L Ch R = 1,3358,452,452,452
BEGIN DESCRIPTION:
SPRING CREEK TRIB 5 6.0
END DESCRIPTION:
XS GIS Cut Line= 3
      3575861.56     10187697.87      3576011.57     10187697.87
      3576508.34     10187619.61
#Sta/Elev= 30
  4683.5  302.22  4724.0  302.65  4734.0  302.25  4784.0  297.64  4836.3  294.17
  4840.2  293.36  4845.3  295.13  4870.6  292.66  4894.8  290.63  4907.8  290.93
  4935.3  290.33  4965.2  291.45  4970.3  293.34  4975.8  293.33  4996.0  289.26
  5003.1  288.89  5005.9  288.39  5009.1  288.89  5016.3  290.28  5026.4  293.29
  5032.8  293.89  5037.9  293.05  5046.6  292.91  5066.9  294.85  5077.0  295.18
  5107.4  295.55  5147.9  295.09  5216.0  296.38  5313.6  297.26  5336.4  297.42
#Mann=6,-1,0
  4683.5    0.16       0  4870.6    0.05       0  5003.1    0.04       0
  5009.1    0.05       0  5216.0     0.1       0  5313.6    0.05       0
Bank Sta=5003.1,5009.1
Exp/Cntr=0.3,0.1

Type RM Length L Ch R = 1,2906,180,180,180
BEGIN DESCRIPTION:
SPRING CREEK TRIB 5 5.2
END DESCRIPTION:
XS GIS Cut Line= 3
      3575823.69     10187990.27      3576334.07     10188084.01
      3576828.84     10188308.91
#Sta/Elev= 30
  4753.6  299.51  4846.4  295.23  4952.6  287.22  4957.7  288.69  4985.8  285.54
  5005.7  286.39  5010.8  287.78  5016.3  287.37  5046.8  290.84  5097.7  292.91
  5416.7  294.47  5444.3  294.64  5472.9  292.89  5524.5  291.94  5556.0  294.19
  5629.7  293.83  5633.0  294.14  5645.3  293.21  5662.9  294.35  5668.4  293.03
  5686.0  293.12  5691.5  291.25  5709.1  289.13  5714.5  286.55  5736.3  285.77
  5750.7  284.01  5753.4  283.51  5756.7  284.01  5775.6  285.51  5816.0  291.86
#Mann=7,-1,0
  4753.6    0.08       0  5416.7     0.1       0  5629.7    0.05       0
  5633.0     0.1       0  5736.3    0.05       0  5750.7    0.07       0
  5756.7    0.05       0
Bank Sta=5750.7,5756.7
Exp/Cntr=0.3,0.1

Type RM Length L Ch R = 1,2726,210,210,210
BEGIN DESCRIPTION:
SPRING CREEK TRIB 5 5.1
END DESCRIPTION:
XS GIS Cut Line= 3
      3575837.57     10188143.05      3576347.96     10188236.79
      3576844.45     10188462.47
#Sta/Elev= 30
  4693.9  296.64  4825.1  291.24  4936.3  289.63  4973.0  284.94  4991.5  283.97
  4994.3  283.47  4997.5  283.97  5023.9  285.11  5042.5  288.69  5047.6  287.10
  5054.4  289.39  5074.7  291.26  5167.3  290.64  5235.2  289.39  5309.9  290.13
  5335.5  289.51  5384.6  289.36  5415.1  287.20  5425.3  287.75  5430.8  285.23
  5453.8  289.31  5459.3  287.78  5476.9  289.69  5482.4  287.89  5500.0  289.92
  5505.5  288.60  5551.6  291.35  5655.1  293.35  5690.6  293.71  5758.2  294.93
#Mann=7,-1,0
  4693.9    0.05       0  4991.5    0.04       0  4997.5    0.05       0
  5167.3    0.08       0  5335.5    0.05       0  5655.1    0.08       0
  5690.6    0.05       0
Bank Sta=4991.5,4997.5
Exp/Cntr=0.3,0.1

Type RM Length L Ch R = 1,2516,192,192,192
BEGIN DESCRIPTION:
SPRING CREEK TRIB 5 5.0
END DESCRIPTION:
XS GIS Cut Line= 3
      3575882.72     10188313.19      3576393.10     10188406.93
      3576888.32     10188632.03
#Sta/Elev= 30
  4630.8  292.72  4817.1  291.38  4923.3  288.61  4928.4  289.47  4945.4  288.22
  4981.5  281.94  4986.6  287.15  4996.2  283.17  5006.4  282.07  5034.6  286.96
  5055.2  287.86  5097.9  286.40  5142.0  287.23  5169.1  286.30  5174.6  284.07
  5200.6  278.45  5203.3  277.95  5206.6  278.45  5220.8  278.88  5266.9  288.16
  5272.4  287.79  5290.0  290.22  5295.5  288.73  5313.0  290.90  5318.5  289.64
  5341.6  291.53  5439.4  291.39  5462.4  292.78  5645.2  295.65  5693.7  297.56
#Mann=6,-1,0
  4630.8    0.08       0  5055.2    0.05       0  5142.0    0.08       0
  5200.6    0.07       0  5206.6    0.08       0  5645.2     0.1       0
Bank Sta=5200.6,5206.6
Exp/Cntr=0.3,0.1

Type RM Length L Ch R = 1,2324,587,587,587
BEGIN DESCRIPTION:
SPRING CREEK TRIB 5 4.0
END DESCRIPTION:
XS GIS Cut Line= 3
      3575837.54     10188410.40      3576424.35     10188566.65
      3576795.91     10188750.70
#Sta/Elev= 30
  4476.5  293.23  4659.3  289.15  4708.9  284.04  4769.3  284.20  4774.5  282.71
  4805.4  285.01  4864.8  284.62  4906.5  284.47  4924.6  284.66  4929.8  283.23
  4964.8  285.06  4966.9  279.70  4969.7  279.20  4972.9  279.70  4988.3  280.05
  4998.6  285.67  5004.9  285.43  5010.1  280.37  5019.3  283.30  5039.9  285.69
  5045.0  283.27  5080.0  287.07  5083.7  285.89  5110.4  286.37  5206.8  287.80
  5218.4  287.21  5287.1  288.11  5339.1  290.93  5427.2  294.62  5498.4  295.11
#Mann=10,-1,0
  4476.5    0.05       0  4805.4    0.08       0  4864.8    0.16       0
  4906.5    0.05       0  4966.9    0.04       0  4972.9    0.05       0
  5110.4    0.08       0  5206.8    0.05       0  5218.4    0.08       0
  5339.1     0.1       0
Bank Sta=4966.9,4972.9
Exp/Cntr=0.3,0.1

Type RM Length L Ch R = 1,1737,528,528,528
BEGIN DESCRIPTION:
SPRING CREEK TRIB 5 3.0
END DESCRIPTION:
XS GIS Cut Line= 3
      3576100.57     10188851.74      3576242.11     10188891.64
      3576647.28     10189033.97
#Sta/Elev= 30
  4856.5  285.12  4889.3  283.26  4898.4  283.47  4908.1  284.03  4913.3  282.61
  4930.8  283.18  4947.3  281.68  4952.5  278.97  4972.4  275.07  4983.5  273.79
  4986.3  273.29  4989.5  273.79  5013.7  275.05  5044.7  278.49  5047.5  279.50
  5050.0  280.41  5056.5  280.71  5067.1  280.21  5075.7  278.19  5081.0  281.57
  5098.9  280.75  5104.0  281.25  5112.0  282.92  5137.7  282.61  5143.0  283.78
  5194.3  285.19  5230.0  292.79  5292.6  293.62  5411.2  292.31  5433.0  292.83
#Mann=7,-1,0
  4856.5    0.05       0  4898.4    0.16       0  4983.5    0.07       0
  4989.5    0.16       0  5047.5    0.05       0  5104.0    0.08       0
  5230.0     0.1       0
Bank Sta=4983.5,4989.5
Exp/Cntr=0.3,0.1

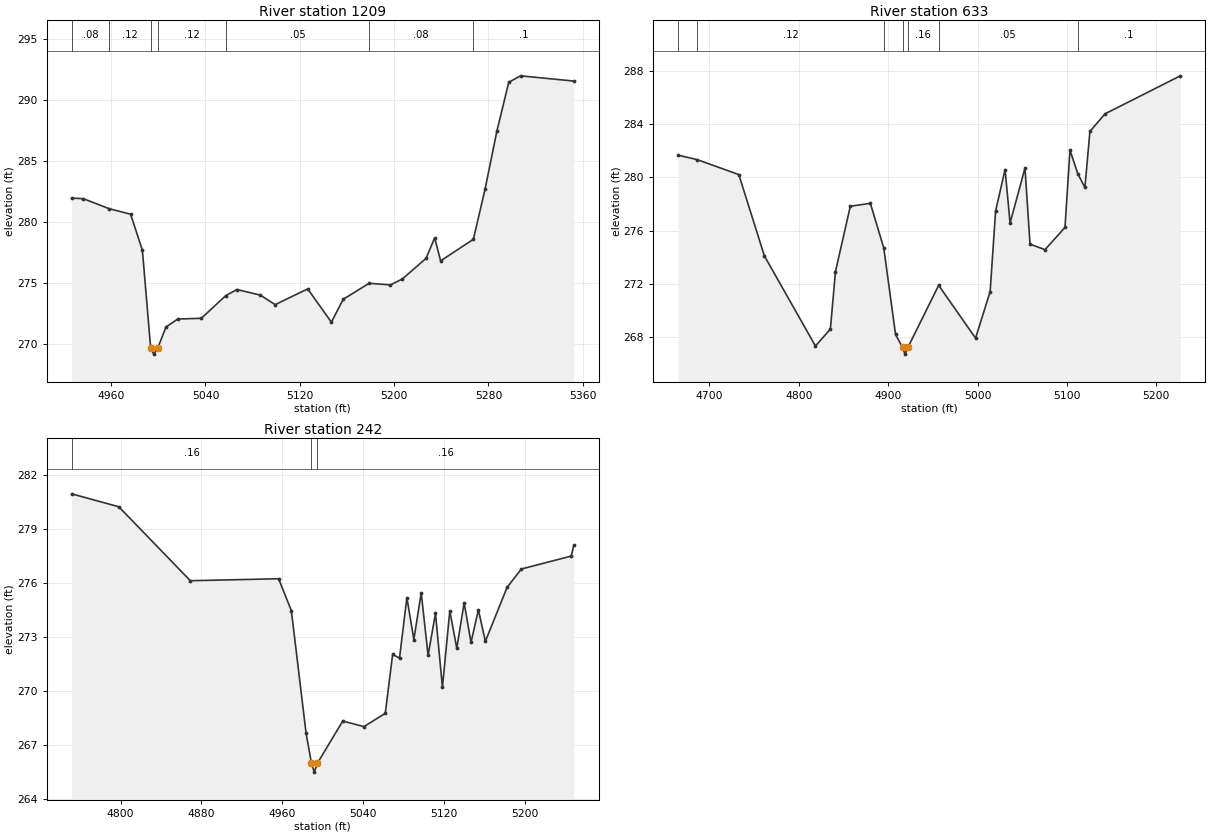
Type RM Length L Ch R = 1,1209,576,576,576
BEGIN DESCRIPTION:
SPRING CREEK TRIB 5 2.0
END DESCRIPTION:
XS GIS Cut Line= 3
      3576092.13     10189291.64      3576192.11     10189291.64
      3576517.20     10189268.40
#Sta/Elev= 30
  4926.5  281.93  4936.5  281.88  4958.3  281.06  4976.5  280.61  4986.5  277.65
  4993.5  269.63  4996.2  269.13  4999.5  269.63  5006.5  271.35  5016.5  272.01
  5036.5  272.07  5057.2  273.93  5066.6  274.43  5086.6  273.97  5099.1  273.19
  5126.7  274.48  5146.8  271.75  5156.8  273.63  5178.8  274.94  5196.9  274.81
  5206.9  275.29  5227.0  276.98  5234.4  278.67  5239.4  276.78  5267.2  278.55
  5277.1  282.66  5287.1  287.41  5297.2  291.43  5307.2  291.96  5352.4  291.53
#Mann=7,-1,0
  4926.5    0.08       0  4958.3    0.12       0  4993.5    0.07       0
  4999.5    0.12       0  5057.2    0.05       0  5178.8    0.08       0
  5267.2     0.1       0
Bank Sta=4993.5,4999.5
Exp/Cntr=0.3,0.1

Type RM Length L Ch R = 1,633,391,391,391
BEGIN DESCRIPTION:
SPRING CREEK TRIB 5 2.1
END DESCRIPTION:
XS GIS Cut Line= 3
      3575994.16     10189535.15      3576094.15     10189535.15
      3576506.77     10189742.34
#Sta/Elev= 30
  4665.1  281.67  4686.6  281.33  4733.0  280.21  4761.6  274.10  4818.7  267.33
  4835.4  268.60  4841.1  272.92  4857.7  277.83  4880.1  278.05  4895.1  274.70
  4908.3  268.20  4916.1  267.22  4918.9  266.72  4922.1  267.22  4956.5  271.89
  4997.8  267.92  5014.1  271.42  5020.2  277.47  5030.8  280.59  5036.4  276.57
  5053.1  280.70  5058.7  274.98  5075.5  274.57  5097.8  276.24  5103.4  282.05
  5112.2  280.26  5120.1  279.24  5125.7  283.45  5142.5  284.77  5226.8  287.63
#Mann=7,-1,0
  4665.1    0.05       0  4686.6    0.12       0  4895.1    0.16       0
  4916.1    0.04       0  4922.1    0.16       0  4956.5    0.05       0
  5112.2     0.1       0
Bank Sta=4916.1,4922.1
Exp/Cntr=0.3,0.1

Type RM Length L Ch R = 1,242,0,0,0
BEGIN DESCRIPTION:
SPRING CREEK TRIB 5 1.0
END DESCRIPTION:
XS GIS Cut Line= 3
      3575898.19     10189699.81      3576098.19     10189849.81
      3576278.29     10190019.13
#Sta/Elev= 30
  4751.5  280.94  4798.2  280.22  4869.0  276.11  4956.4  276.22  4969.0  274.45
  4983.6  267.64  4988.9  265.97  4991.7  265.47  4994.9  265.97  5019.9  268.31
  5040.9  268.00  5062.0  268.74  5069.3  272.01  5076.1  271.81  5083.4  275.17
  5090.3  272.84  5097.6  275.43  5104.4  271.96  5111.7  274.29  5118.6  270.19
  5125.9  274.44  5132.8  272.35  5140.1  274.88  5146.9  272.68  5154.2  274.49
  5161.1  272.74  5182.6  275.74  5196.7  276.76  5246.1  277.48  5248.7  278.09
#Mann=3,-1,0
  4751.5    0.16       0  4988.9    0.07       0  4994.9    0.16       0
Bank Sta=4988.9,4994.9
Exp/Cntr=0.3,0.1

Chan Stop Cuts=-1