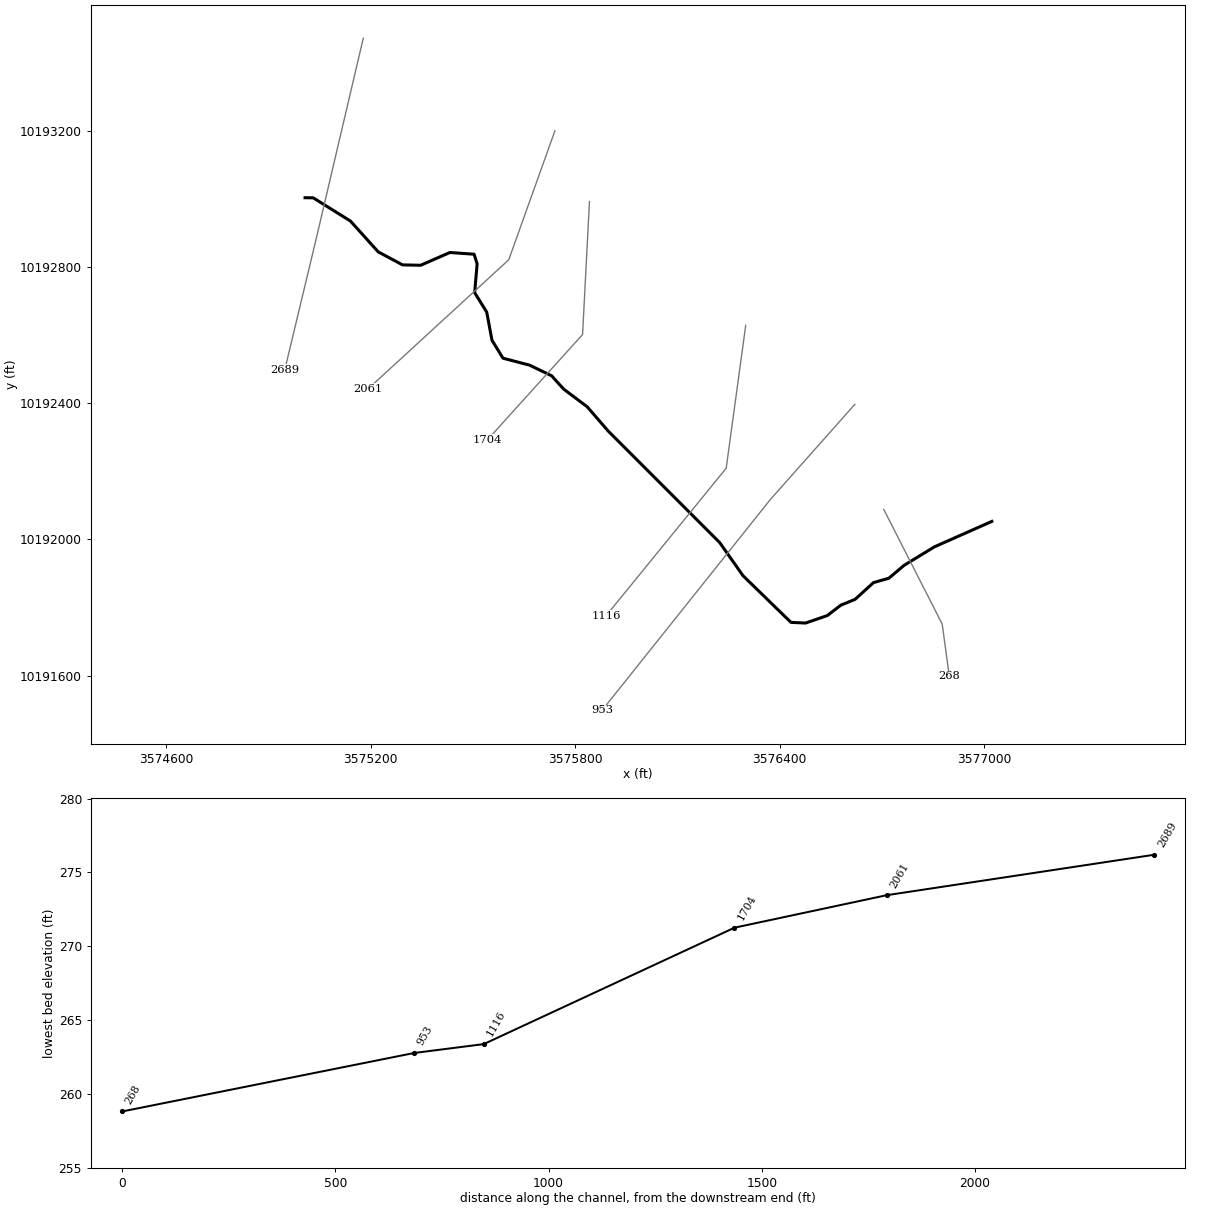
--- SPRING CREEK TRIBUTARY A.prj (project) ---

Proj Title=SPRING CREEK TRIBUTARY A Base Level Engineering
Current Plan=p01
Default Exp/Contr=0.3,0.1
English Units
Geom File=g01
Flow File=f01
Plan File=p01
BEGIN DESCRIPTION:
SPRING CREEK TRIBUTARY A
END DESCRIPTION:

--- SPRING CREEK TRIBUTARY A.p01 (plan) ---

Plan Title=Multiple Run
Short Identifier=Multiple
Geom File=g01
Flow File=f01
Subcritical Flow
K Sum by GR= 0
Std Step Tol= 0.01
Critical Tol= 0.01
Num of Std Step Trials= 20
Max Error Tol= 0.3
Flow Tol Ratio= 0.001
Split Flow NTrial= 30
Split Flow Tol= 0.02
Split Flow Ratio= 0.02
Log Output Level= 0
Friction Slope Method= 1
Unsteady Friction Slope Method= 2
Unsteady Bridges Friction Slope Method= 1
Parabolic Critical Depth
Global Vel Dist=  1 , 1 , 1
Global Log Level= 0
CheckData=True
Encroach Param= -1, 0, 0, 0
BEGIN DESCRIPTION:
Multiple Run
END DESCRIPTION:

--- SPRING CREEK TRIBUTARY A.f01 (steady flow) ---

Flow Title=Multiple
Number of Profiles=7
Profile Names=10-year,25-year,50-year,1pct_min,100-year,1pct_plu,500-year
River Rch & RM= SPRING CREEK TRI,Reach-1,2689
     169     209     240     202     273     369     353
Boundary for River Rch & Prof#=SPRING CREEK TRI,Reach-1,1
Up Type=0
Dn Type=3
Dn Slope=0.005
Boundary for River Rch & Prof#=SPRING CREEK TRI,Reach-1,2
Up Type=0
Dn Type=3
Dn Slope=0.005
Boundary for River Rch & Prof#=SPRING CREEK TRI,Reach-1,3
Up Type=0
Dn Type=3
Dn Slope=0.005
Boundary for River Rch & Prof#=SPRING CREEK TRI,Reach-1,4
Up Type=0
Dn Type=3
Dn Slope=0.005
Boundary for River Rch & Prof#=SPRING CREEK TRI,Reach-1,5
Up Type=0
Dn Type=3
Dn Slope=0.005
Boundary for River Rch & Prof#=SPRING CREEK TRI,Reach-1,6
Up Type=0
Dn Type=3
Dn Slope=0.005
Boundary for River Rch & Prof#=SPRING CREEK TRI,Reach-1,7
Up Type=0
Dn Type=3
Dn Slope=0.005

--- SPRING CREEK TRIBUTARY A.g01 (geometry) ---

Geom Title=Existing Conditions

River Reach=SPRING CREEK TRI,Reach-1
Reach XY= 30
      3575007.11     10193002.96      3575031.09     10193002.65
      3575140.46     10192934.42      3575221.68     10192844.15
      3575293.43     10192805.72      3575346.56     10192804.65
      3575432.25     10192842.10      3575503.48     10192837.06
      3575512.30     10192808.65      3575505.04     10192724.30
      3575540.39     10192667.26      3575555.95     10192584.40
      3575588.15     10192531.87      3575666.40     10192511.35
      3575730.91     10192480.29      3575766.41     10192441.07
      3575835.37     10192389.29      3575896.77     10192318.30
      3576224.41     10191990.54      3576292.83     10191893.29
      3576433.65     10191756.26      3576476.61     10191754.30
      3576540.65     10191776.40      3576579.98     10191806.78
      3576621.86     10191823.85      3576676.01     10191873.07
      3576720.93     10191885.81      3576765.44     10191923.42
      3576854.71     10191977.96      3577023.33     10192052.67

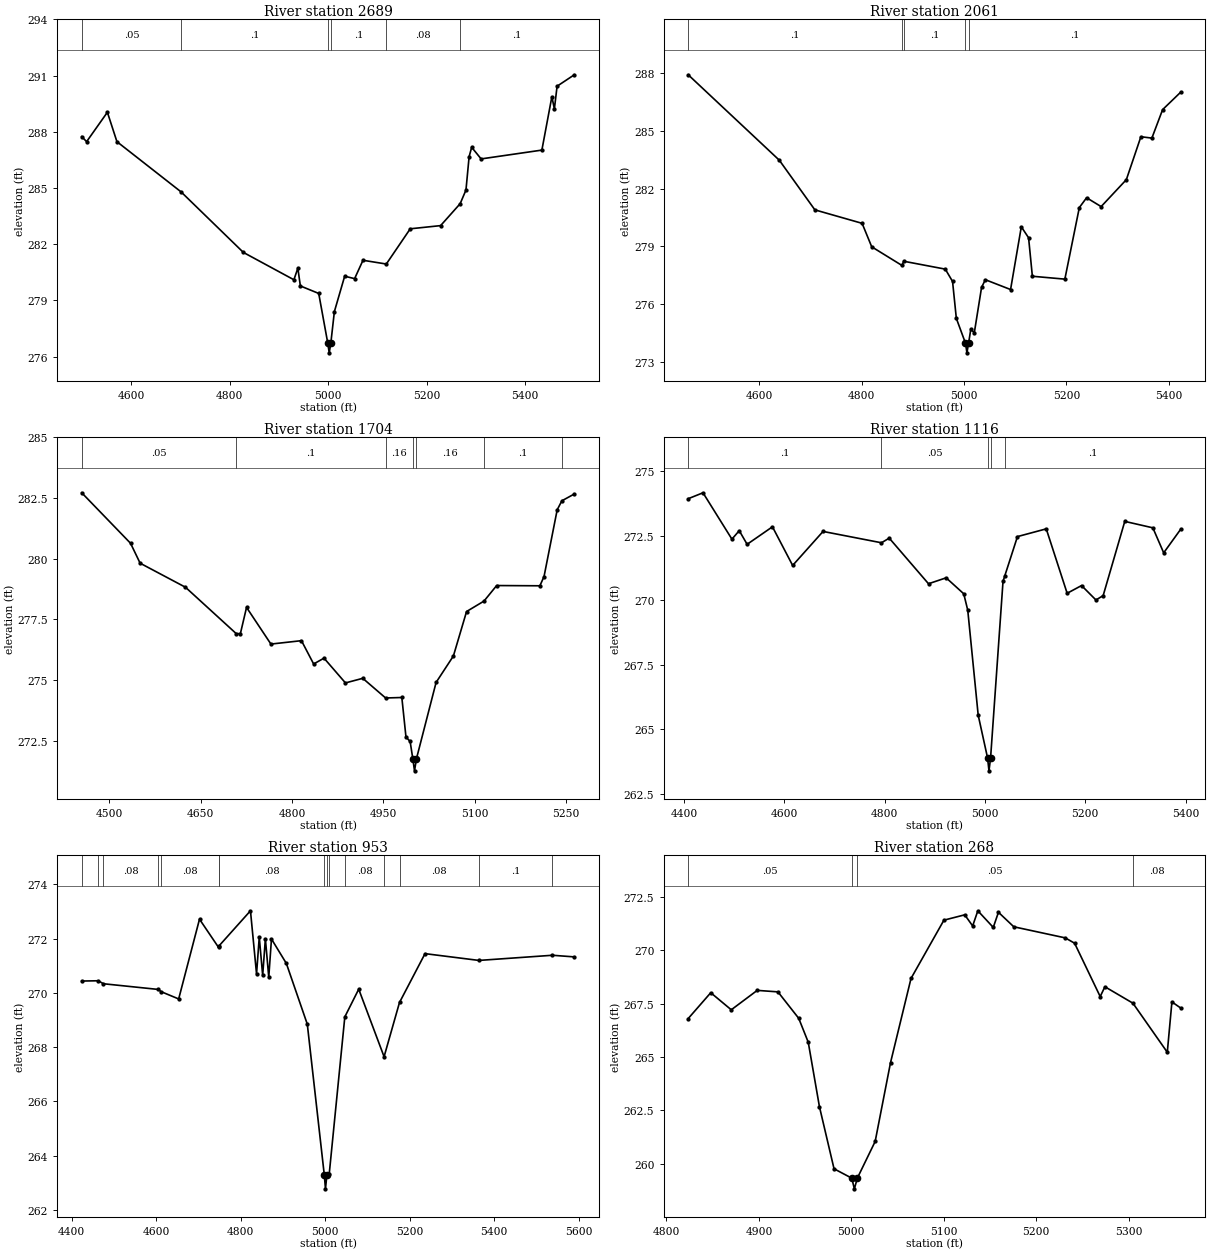
Type RM Length L Ch R = 1,2689,628,628,628
BEGIN DESCRIPTION:
SPRING CREEK TRIBUTARY A 8.0
END DESCRIPTION:
XS GIS Cut Line= 3
      3575178.10     10193471.26      3575037.54     10192872.73
      3574947.61     10192497.57
#Sta/Elev= 30
  4499.4  287.74  4509.3  287.47  4551.5  289.04  4570.9  287.47  4701.2  284.79
  4827.7  281.56  4930.4  280.10  4938.4  280.72  4943.5  279.77  4980.8  279.37
  4999.3  276.70  5002.1  276.20  5005.3  276.70  5012.6  278.40  5033.5  280.29
  5053.7  280.16  5070.7  281.14  5118.1  280.94  5166.7  282.82  5228.4  282.99
  5268.1  284.16  5279.9  284.89  5286.3  286.67  5291.5  287.17  5310.7  286.55
  5434.1  287.02  5454.4  289.87  5459.5  289.22  5465.0  290.43  5500.0  291.04
#Mann=6,-1,0
  4499.4    0.05       0  4701.2     0.1       0  4999.3    0.07       0
  5005.3     0.1       0  5118.1    0.08       0  5268.1     0.1       0
Bank Sta=4999.3,5005.3
Exp/Cntr=0.3,0.1

Type RM Length L Ch R = 1,2061,357,357,357
BEGIN DESCRIPTION:
SPRING CREEK TRIBUTARY A 5.0
END DESCRIPTION:
XS GIS Cut Line= 3
      3575740.65     10193199.33      3575605.22     10192820.84
      3575192.07     10192441.61
#Sta/Elev= 30
  4460.7  287.91  4638.8  283.47  4708.3  280.89  4800.6  280.19  4819.4  278.97
  4878.6  278.00  4881.9  278.22  4963.2  277.81  4977.4  277.17  4984.8  275.25
  5002.7  273.96  5005.5  273.46  5008.7  273.96  5013.1  274.69  5019.9  274.50
  5034.1  276.86  5041.5  277.26  5090.8  276.75  5111.8  280.01  5126.0  279.44
  5133.4  277.44  5196.9  277.29  5225.2  281.01  5239.4  281.52  5267.8  281.06
  5317.1  282.46  5345.5  284.69  5367.0  284.62  5388.0  286.10  5423.5  287.01
#Mann=5,-1,0
  4460.7     0.1       0  4878.6    0.05       0  4881.9     0.1       0
  5002.7    0.07       0  5008.7     0.1       0
Bank Sta=5002.7,5008.7
Exp/Cntr=0.3,0.1

Type RM Length L Ch R = 1,1704,588,588,588
BEGIN DESCRIPTION:
SPRING CREEK TRIBUTARY A 4.0
END DESCRIPTION:
XS GIS Cut Line= 3
      3575842.11     10192991.64      3575821.84     10192601.30
      3575542.08     10192291.62
#Sta/Elev= 30
  4455.0  282.71  4535.1  280.63  4550.8  279.81  4625.2  278.82  4708.5  276.91
  4715.3  276.91  4725.4  277.99  4765.4  276.48  4815.5  276.62  4835.5  275.66
  4852.5  275.90  4887.7  274.88  4916.1  275.07  4953.6  274.26  4980.2  274.28
  4987.0  272.65  4993.8  272.47  4998.2  271.76  5001.0  271.26  5004.2  271.76
  5036.4  274.90  5064.8  275.99  5086.4  277.82  5115.0  278.25  5135.8  278.89
  5206.7  278.88  5213.5  279.26  5235.1  282.01  5242.8  282.38  5263.2  282.66
#Mann=7,-1,0
  4455.0    0.05       0  4708.5     0.1       0  4953.6    0.16       0
  4998.2    0.07       0  5004.2    0.16       0  5115.0     0.1       0
  5242.8    0.05       0
Bank Sta=4998.2,5004.2
Exp/Cntr=0.3,0.1

Type RM Length L Ch R = 1,1116,163,163,163
BEGIN DESCRIPTION:
SPRING CREEK TRIBUTARY A 3.0
END DESCRIPTION:
XS GIS Cut Line= 3
      3576300.81     10192628.07      3576243.51     10192208.77
      3575890.46     10191775.24
#Sta/Elev= 30
  4408.2  273.94  4437.7  274.17  4495.4  272.37  4510.0  272.70  4525.7  272.17
  4576.2  272.85  4616.5  271.35  4677.1  272.67  4793.6  272.23  4809.1  272.41
  4887.4  270.64  4922.6  270.87  4957.7  270.25  4965.7  269.61  4986.5  265.54
  5005.2  263.88  5008.0  263.38  5011.2  263.88  5036.0  270.73  5039.6  270.95
  5064.8  272.47  5122.2  272.77  5163.9  270.27  5192.6  270.57  5221.3  270.01
  5235.7  270.18  5278.8  273.06  5334.8  272.81  5356.4  271.84  5390.5  272.76
#Mann=5,-1,0
  4408.2     0.1       0  4793.6    0.05       0  5005.2    0.04       0
  5011.2    0.05       0  5039.6     0.1       0
Bank Sta=5005.2,5011.2
Exp/Cntr=0.3,0.1

Type RM Length L Ch R = 1,953,685,685,685
BEGIN DESCRIPTION:
SPRING CREEK TRIBUTARY A 2.0
END DESCRIPTION:
XS GIS Cut Line= 3
      3576621.10     10192396.24      3576373.72     10192117.62
      3575878.91     10191497.80
#Sta/Elev= 30
  4424.0  270.44  4463.2  270.45  4475.4  270.34  4605.5  270.13  4611.6  270.05
  4653.4  269.78  4702.7  272.72  4747.8  271.68  4748.0  271.72  4823.3  273.03
  4837.7  270.70  4844.1  272.06  4852.2  270.65  4858.6  272.00  4866.6  270.58
  4873.0  271.99  4908.2  271.09  4957.8  268.85  4998.1  263.28  5000.8  262.78
  5004.1  263.28  5009.7  263.33  5046.6  269.12  5079.5  270.14  5139.5  267.65
  5176.0  269.65  5236.4  271.45  5363.9  271.20  5537.9  271.39  5589.7  271.33
#Mann=15,-1,0
  4424.0    0.08       0  4463.2    0.05       0  4475.4    0.08       0
  4605.5    0.05       0  4611.6    0.08       0  4747.8    0.05       0
  4748.0    0.08       0  4998.1    0.07       0  5004.1    0.08       0
  5009.7    0.05       0  5046.6    0.08       0  5139.5    0.05       0
  5176.0    0.08       0  5363.9     0.1       0  5537.9    0.08       0
Bank Sta=4998.1,5004.1
Exp/Cntr=0.3,0.1

Type RM Length L Ch R = 1,268,0,0,0
BEGIN DESCRIPTION:
SPRING CREEK TRIBUTARY A 1.0
END DESCRIPTION:
XS GIS Cut Line= 3
      3576705.93     10192088.17      3576877.68     10191751.20
      3576898.49     10191597.82
#Sta/Elev= 30
  4823.5  266.80  4847.9  268.01  4870.1  267.21  4898.2  268.12  4920.6  268.05
  4943.1  266.81  4953.4  265.69  4965.5  262.67  4981.3  259.76  5000.5  259.32
  5003.3  258.82  5006.5  259.32  5025.8  261.04  5042.4  264.73  5064.6  268.68
  5100.2  271.41  5122.7  271.66  5131.3  271.14  5136.9  271.85  5153.6  271.07
  5159.2  271.78  5175.8  271.10  5231.5  270.58  5241.6  270.33  5269.3  267.83
  5274.4  268.29  5304.7  267.52  5341.9  265.22  5346.9  267.58  5356.5  267.29
#Mann=4,-1,0
  4823.5    0.05       0  5000.5    0.03       0  5006.5    0.05       0
  5304.7    0.08       0
Bank Sta=5000.5,5006.5
Exp/Cntr=0.3,0.1

Chan Stop Cuts=-1