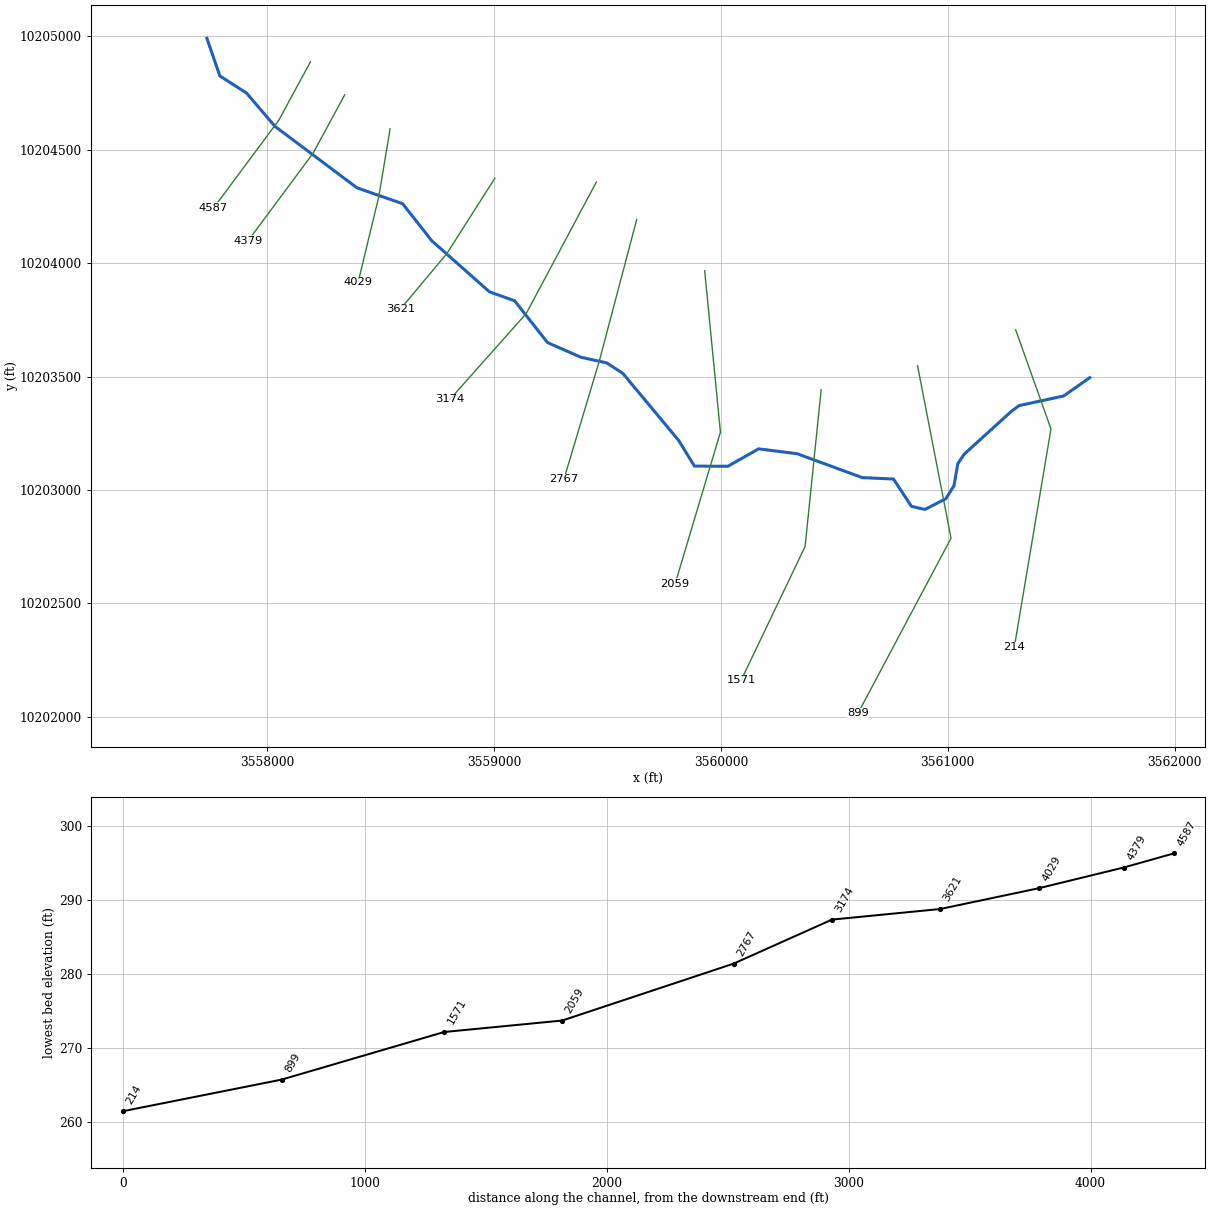
--- UNNAMED TRIB 2 TO BEE CR TRIB B.prj (project) ---

Proj Title=UNNAMED TRIB 2 TO BEE CR TRIB B Base Level Engineering
Current Plan=p01
Default Exp/Contr=0.3,0.1
English Units
Geom File=g01
Flow File=f01
Plan File=p01
Y Axis Title=Elevation
X Axis Title(PF)=Main Channel Distance
X Axis Title(XS)=Station
BEGIN DESCRIPTION:
UNNAMED TRIB 2 TO BEE CR TRIB B
END DESCRIPTION:
DSS Export Rating Curves= 0
DSS Export Rating Curve Sorted= 0
DSS Export Volume Flow Curves= 0
DXF OffsetX= 0
DXF OffsetY= 0
DXF ScaleX= 1
DXF ScaleY= 10

--- UNNAMED TRIB 2 TO BEE CR TRIB B.p01 (plan) ---

Plan Title=Multiple Run
Short Identifier=Multiple
Geom File=g01
Flow File=f01
Subcritical Flow
K Sum by GR= 0
Std Step Tol= 0.01
Critical Tol= 0.01
Num of Std Step Trials= 20
Max Error Tol= 0.3
Flow Tol Ratio= 0.001
Split Flow NTrial= 30
Split Flow Tol= 0.02
Split Flow Ratio= 0.02
Log Output Level= 0
Friction Slope Method= 1
Unsteady Friction Slope Method= 2
Unsteady Bridges Friction Slope Method= 1
Parabolic Critical Depth
Global Vel Dist=  1 , 1 , 1
Global Log Level= 0
CheckData=True
Encroach Param= -1, 0, 0, 0
BEGIN DESCRIPTION:
Multiple Run
END DESCRIPTION:

--- UNNAMED TRIB 2 TO BEE CR TRIB B.f01 (steady flow) ---

Flow Title=Multiple
Program Version=4.10
Number of Profiles= 7
Profile Names=10-year,25-year,50-year,1pct_min,100-year,1pct_plu,500-year
River Rch & RM=UNNAMED TRIB 2 T,Reach-1         ,4587
  299.29   299.6  299.81   299.6  300.04  300.52  300.52
Boundary for River Rch & Prof#=UNNAMED TRIB 2 T,Reach-1         , 1
Up Type= 0
Dn Type= 3
Dn Slope=0.01
Boundary for River Rch & Prof#=UNNAMED TRIB 2 T,Reach-1         , 2
Up Type= 0
Dn Type= 3
Dn Slope=0.01
Boundary for River Rch & Prof#=UNNAMED TRIB 2 T,Reach-1         , 3
Up Type= 0
Dn Type= 3
Dn Slope=0.01
Boundary for River Rch & Prof#=UNNAMED TRIB 2 T,Reach-1         , 4
Up Type= 0
Dn Type= 3
Dn Slope=0.01
Boundary for River Rch & Prof#=UNNAMED TRIB 2 T,Reach-1         , 5
Up Type= 0
Dn Type= 3
Dn Slope=0.01
Boundary for River Rch & Prof#=UNNAMED TRIB 2 T,Reach-1         , 6
Up Type= 0
Dn Type= 3
Dn Slope=0.01
Boundary for River Rch & Prof#=UNNAMED TRIB 2 T,Reach-1         , 7
Up Type= 0
Dn Type= 3
Dn Slope=0.01
DSS Import GetInterval= 0
DSS Import GetPeak= 0
DSS Import FillOption= 0

--- UNNAMED TRIB 2 TO BEE CR TRIB B.g01 (geometry) ---

Geom Title=Existing Conditions
Program Version=4.10

River Reach=UNNAMED TRIB 2 T,Reach-1
Reach XY= 30
      3557734.83     10204990.63      3557791.64      10204824.8
      3557908.83      10204749.8      3558034.35     10204602.92
      3558396.33     10204331.57      3558597.37     10204261.78
      3558725.49     10204098.76      3558980.18     10203873.24
      3559091.12     10203833.65      3559235.91     10203649.73
      3559383.42     10203584.81      3559496.53     10203560.22
      3559568.06     10203513.89      3559814.01     10203218.26
       3559883.5     10203105.14      3560030.96     10203104.38
      3560166.42     10203181.25      3560336.31     10203159.72
      3560623.27     10203054.45      3560760.86      10203048.2
      3560840.01     10202927.87      3560899.48     10202914.15
      3560991.78     10202961.53      3561027.53      10203018.8
      3561044.35     10203115.72      3561072.11     10203157.35
      3561281.31     10203347.45       3561314.3     10203371.76
        3561511.     10203414.36      3561626.03     10203495.05

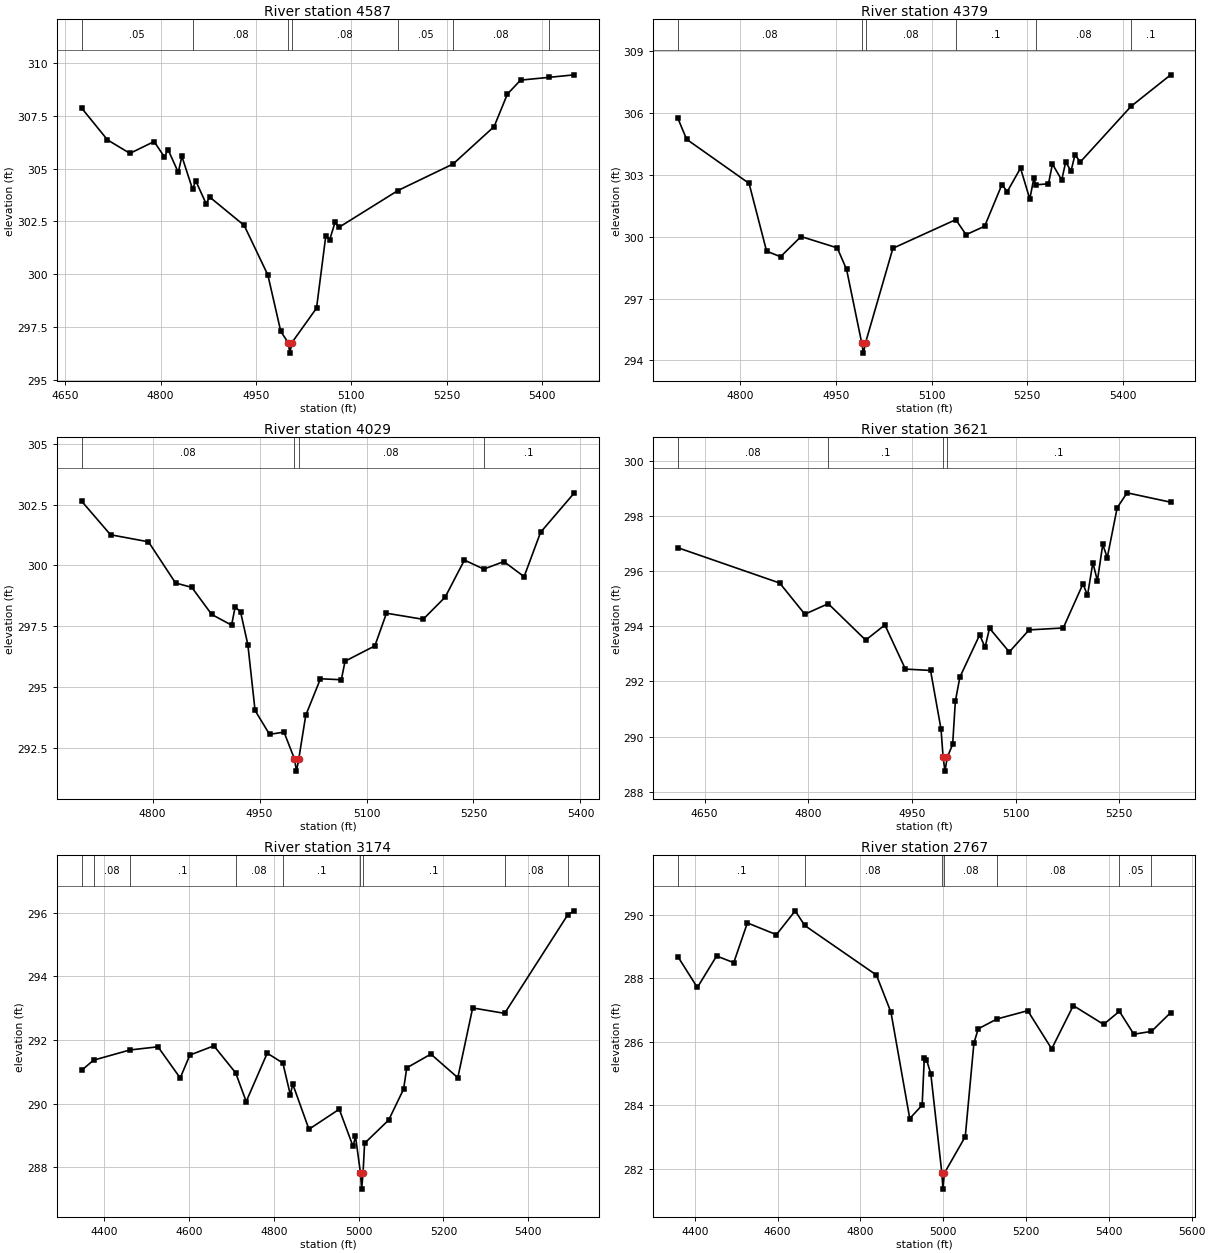
Type RM Length L Ch R = 1 ,4587    ,208,208,208
BEGIN DESCRIPTION:
UNNAMED TRIB 2 TO BEE CR TRIB B 10.0
END DESCRIPTION:
XS GIS Cut Line= 3
      3558191.23     10204887.53      3558051.61     10204629.76
      3557763.87     10204242.51
#Sta/Elev= 30
  4675.5  307.87  4716.3  306.36  4751.6  305.72  4789.7  306.28  4805.9  305.55
  4811.6   305.9  4827.7  304.82  4833.4  305.58  4850.1  304.03  4855.3  304.41
  4871.5  303.34  4877.2  303.65  4931.4  302.31  4968.7  299.96    4989  297.29
  5000.6  296.76  5003.3  296.26  5006.6  296.76  5045.3  298.39  5059.9  301.82
  5066.1  301.64  5074.5  302.46  5080.7  302.22  5173.4  303.96  5260.3  305.22
  5324.8  306.99  5345.7  308.53  5366.5  309.19  5411.1  309.32  5451.1  309.44
#Mann= 7 ,-1 , 0
  4675.5     .05       0  4850.1     .08       0  5000.6     .07       0
  5006.6     .08       0  5173.4     .05       0  5260.3     .08       0
  5411.1      .1       0
Bank Sta=5000.6,5006.6
XS Rating Curve= 0 ,0
Exp/Cntr=0.3,0.1

Type RM Length L Ch R = 1 ,4379    ,350,350,350
BEGIN DESCRIPTION:
UNNAMED TRIB 2 TO BEE CR TRIB B 9.0
END DESCRIPTION:
XS GIS Cut Line= 3
      3558342.12     10204741.66       3558202.5      10204483.9
      3557915.95     10204098.25
#Sta/Elev= 30
  4701.8  305.75  4715.6  304.73  4813.6  302.59  4841.1   299.3    4863  299.03
  4895.2  300.01    4952  299.46  4966.7  298.41  4990.4  294.85  4993.1  294.35
  4996.4  294.85  5039.4  299.44  5138.1  300.83  5154.2   300.1  5183.4  300.51
  5210.5  302.53  5218.9  302.19  5239.7  303.33  5254.3  301.83  5260.6  302.84
  5263.8  302.52  5283.6  302.57  5289.8  303.53  5304.4  302.75  5310.6  303.63
    5319  303.19  5325.2  303.98  5333.6  303.63  5413.2  306.33  5475.4  307.86
#Mann= 6 ,-1 , 0
  4701.8     .08       0  4990.4     .07       0  4996.4     .08       0
  5138.1      .1       0  5263.8     .08       0  5413.2      .1       0
Bank Sta=4990.4,4996.4
XS Rating Curve= 0 ,0
Exp/Cntr=0.3,0.1

Type RM Length L Ch R = 1 ,4029    ,408,408,408
BEGIN DESCRIPTION:
UNNAMED TRIB 2 TO BEE CR TRIB B 8.0
END DESCRIPTION:
XS GIS Cut Line= 3
      3558542.11     10204591.64      3558492.11     10204291.64
      3558401.15     10203915.52
#Sta/Elev= 30
  4700.4  302.64    4741  301.26  4794.2  300.97  4832.2  299.28    4855   299.1
  4882.9  297.99  4910.8  297.55  4915.8   298.3  4923.4  298.09  4933.6  296.75
  4943.7  294.05    4964  293.07  4984.3  293.16    4999  292.06  5001.8  291.56
    5005  292.06  5014.8  293.85  5035.4  295.35  5064.7  295.31  5069.9  296.07
  5111.7   296.7    5128  298.04  5179.4  297.79  5210.3   298.7  5237.3  300.22
  5264.5  299.85  5292.6  300.16    5321  299.54  5344.1  301.36  5391.5  302.98
#Mann= 4 ,-1 , 0
  4700.4     .08       0    4999     .07       0    5005     .08       0
  5264.5      .1       0
Bank Sta=4999,5005
XS Rating Curve= 0 ,0
Exp/Cntr=0.3,0.1

Type RM Length L Ch R = 1 ,3621    ,447,447,447
BEGIN DESCRIPTION:
UNNAMED TRIB 2 TO BEE CR TRIB B 7.0
END DESCRIPTION:
XS GIS Cut Line= 3
      3559004.16      10204374.4      3558792.11     10204041.64
      3558587.49     10203797.15
#Sta/Elev= 30
  4611.2  296.85  4758.6  295.57    4795  294.44  4828.9  294.82  4883.1   293.5
  4910.9  294.05  4940.6  292.45    4977   292.4  4992.2  290.27  4995.2  289.25
  4997.9  288.75  5001.2  289.25    5009  289.72  5012.9  291.28  5019.5  292.16
  5048.1  293.69  5055.9  293.24  5062.4  293.93    5091  293.07  5119.6  293.87
  5169.1  293.94  5197.7  295.54  5204.2  295.12    5212  296.31  5218.5  295.65
  5226.3  296.97  5232.8  296.49  5247.2   298.3  5261.5  298.84  5324.6   298.5
#Mann= 4 ,-1 , 0
  4611.2     .08       0  4828.9      .1       0  4995.2     .07       0
  5001.2      .1       0
Bank Sta=4995.2,5001.2
XS Rating Curve= 0 ,0
Exp/Cntr=0.3,0.1

Type RM Length L Ch R = 1 ,3174    ,407,407,407
BEGIN DESCRIPTION:
UNNAMED TRIB 2 TO BEE CR TRIB B 6.0
END DESCRIPTION:
XS GIS Cut Line= 3
      3559451.23     10204357.08      3559142.11     10203777.52
      3558805.84     10203399.34
#Sta/Elev= 30
  4346.2  291.05  4374.5  291.37  4460.3  291.69  4526.5  291.79    4579  290.81
  4601.7  291.53  4658.4  291.82  4709.9  290.97  4734.7  290.07  4784.3  291.59
  4821.2  291.28  4838.9  290.28  4844.5  290.62  4882.8   289.2  4954.3  289.83
  4986.9  288.66  4992.6  288.98  5004.4  287.82  5007.1  287.32  5010.4  287.82
  5014.1  288.76  5070.9  289.49  5106.1  290.46  5113.6  291.13  5170.5  291.56
    5234  290.82  5269.1  293.01  5344.5  292.84  5493.7  295.94  5509.1  296.06
#Mann= 9 ,-1 , 0
  4346.2      .1       0  4374.5     .08       0  4460.3      .1       0
  4709.9     .08       0  4821.2      .1       0  5004.4     .07       0
  5010.4      .1       0  5344.5     .08       0  5493.7      .1       0
Bank Sta=5004.4,5010.4
XS Rating Curve= 0 ,0
Exp/Cntr=0.3,0.1

Type RM Length L Ch R = 1 ,2767    ,708,708,708
BEGIN DESCRIPTION:
UNNAMED TRIB 2 TO BEE CR TRIB B 5.0
END DESCRIPTION:
XS GIS Cut Line= 3
      3559629.17     10204192.13       3559464.5     10203569.25
      3559308.03     10203046.44
#Sta/Elev= 30
  4359.3  288.68  4406.4  287.71  4452.9   288.7  4494.3  288.49  4527.2  289.74
  4597.3  289.37  4642.7  290.12  4665.6  289.66  4838.8   288.1  4873.9  286.93
  4919.3  283.59  4949.2  284.01  4954.4  285.49  4959.7  285.44  4970.1     285
  4996.8  281.87  4999.5  281.37  5002.8  281.87  5053.3  283.02  5074.2  285.96
  5084.6  286.41    5130  286.72  5204.2  286.98    5262  285.78  5314.2  287.14
  5387.3  286.55  5425.5  286.96  5460.4  286.24    5503  286.33  5549.3  286.92
#Mann= 7 ,-1 , 0
  4359.3      .1       0  4665.6     .08       0  4996.8     .04       0
  5002.8     .08       0    5130     .08       0  5425.5     .05       0
    5503     .08       0
Bank Sta=4996.8,5002.8
XS Rating Curve= 0 ,0
Exp/Cntr=0.3,0.1

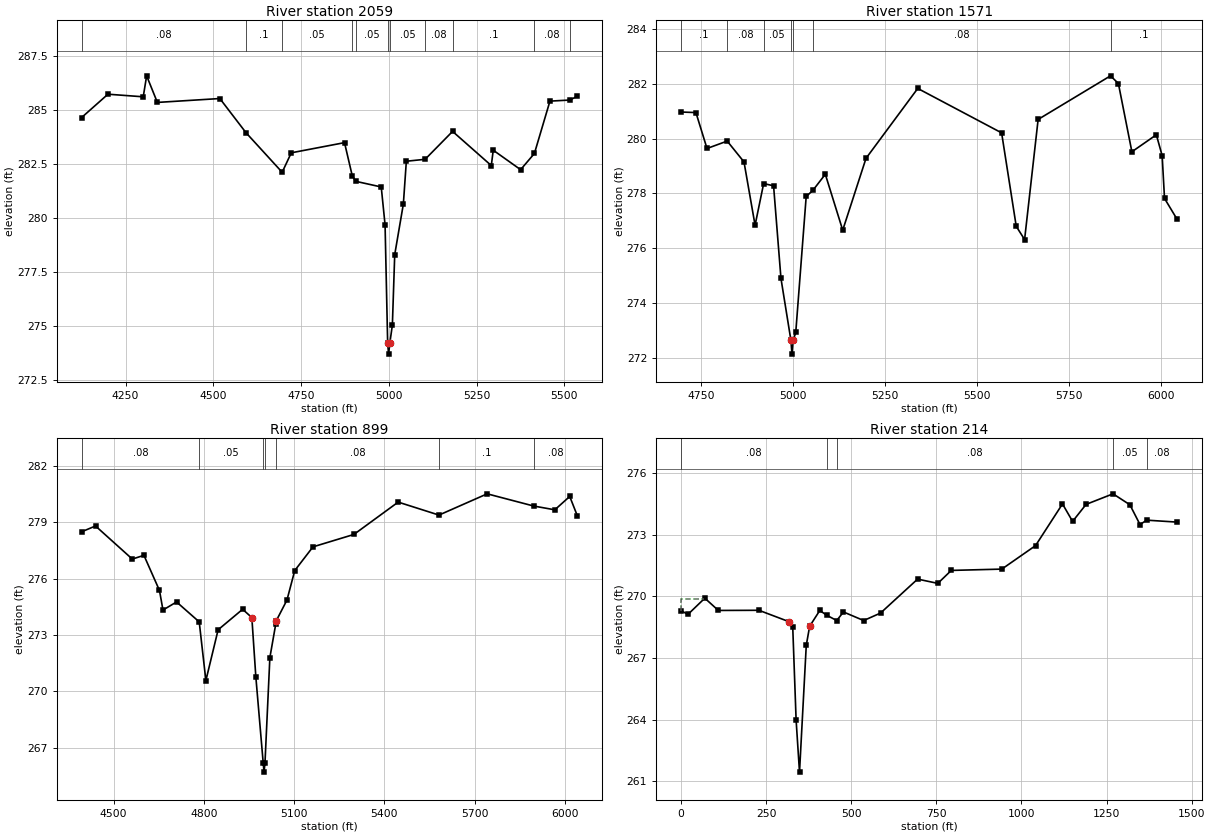
Type RM Length L Ch R = 1 ,2059    ,488,488,488
BEGIN DESCRIPTION:
UNNAMED TRIB 2 TO BEE CR TRIB B 4.0
END DESCRIPTION:
XS GIS Cut Line= 3
      3559928.65     10203966.38      3559998.09     10203254.62
       3559798.5     10202586.43
#Sta/Elev= 30
  4124.8  284.63  4199.9  285.71  4300.4  285.59  4310.1  286.56  4340.6  285.33
  4518.6  285.51  4593.1  283.93  4696.1   282.1  4722.1     283  4873.7  283.47
  4895.7  281.94  4906.1  281.68  4978.3  281.42  4989.2  279.67  4996.6  274.19
  4999.3  273.69  5002.6  274.19    5010  275.03  5016.7  278.29  5041.3  280.63
  5049.8  282.61  5103.3   282.7  5181.5  283.99  5291.8  282.41  5297.3  283.12
  5375.3  282.22  5414.6  282.97  5458.8  285.39  5515.4  285.44  5537.3  285.62
#Mann= 11 ,-1 , 0
  4124.8     .08       0  4593.1      .1       0  4696.1     .05       0
  4895.7     .08       0  4906.1     .05       0  4996.6     .04       0
  5002.6     .05       0  5103.3     .08       0  5181.5      .1       0
  5414.6     .08       0  5515.4     .05       0
Bank Sta=4996.6,5002.6
XS Rating Curve= 0 ,0
Exp/Cntr=0.3,0.1

Type RM Length L Ch R = 1 ,1571    ,672,672,672
BEGIN DESCRIPTION:
UNNAMED TRIB 2 TO BEE CR TRIB B 3.0
END DESCRIPTION:
XS GIS Cut Line= 3
       3560442.1     10203441.61      3560371.35     10202751.15
      3560089.24     10202160.88
#Sta/Elev= 30
  4696.6  280.97  4736.8  280.95  4766.9  279.64  4821.8  279.91  4867.5  279.15
  4897.6  276.84  4920.9  278.36  4947.9  278.28    4968   274.9  4995.1  272.64
  4997.9  272.14  5001.1  272.64  5008.2  272.93  5036.6  277.89  5054.6  278.11
  5088.6   278.7  5135.9  276.66  5199.2  279.28  5339.9  281.83  5567.9  280.21
  5607.7   276.8  5630.4  276.32  5667.2   280.7    5864  282.29  5885.4  282.01
  5922.1  279.52  5988.6  280.14  6004.4  279.38  6010.8  277.82  6044.9  277.06
#Mann= 7 ,-1 , 0
  4696.6      .1       0  4821.8     .08       0  4920.9     .05       0
  4995.1     .04       0  5001.1     .05       0  5054.6     .08       0
    5864      .1       0
Bank Sta=4995.1,5001.1
XS Rating Curve= 0 ,0
Exp/Cntr=0.3,0.1

Type RM Length L Ch R = 1 ,899     ,656,656,656
BEGIN DESCRIPTION:
UNNAMED TRIB 2 TO BEE CR TRIB B 2.0
END DESCRIPTION:
XS GIS Cut Line= 3
      3560867.01     10203547.14      3561014.58     10202787.61
      3560604.23     10202015.29
#Sta/Elev= 30
  4393.5  278.49  4439.8   278.8  4562.1  277.04  4600.7  277.24  4652.4  275.37
    4664  274.33  4709.2  274.76  4784.5   273.7  4806.6  270.58  4847.3  273.28
  4928.8  274.37  4959.4  273.93  4972.7  270.77  4997.1  266.21  4999.9  265.71
  5003.1  266.21  5019.3   271.8  5038.9  273.59  5040.9  273.77  5076.1  274.86
    5102  276.43  5162.6  277.69  5298.6  278.35  5445.8  280.07  5581.4  279.38
  5741.6  280.51  5896.5  279.86  5966.4  279.66    6016  280.37  6041.8  279.32
#Mann= 7 ,-1 , 0
  4393.5     .08       0  4784.5     .05       0  4997.1     .04       0
  5003.1     .05       0  5038.9     .08       0  5581.4      .1       0
  5896.5     .08       0
Bank Sta=4959.4,5040.9
XS Rating Curve= 0 ,0
Exp/Cntr=0.3,0.1

Type RM Length L Ch R = 1 ,214     ,0,0,0
BEGIN DESCRIPTION:
UNNAMED TRIB 2 TO BEE CR TRIB B 1.0
END DESCRIPTION:
XS GIS Cut Line= 3
      3561299.29     10203706.04      3561455.06     10203269.13
       3561293.3     10202306.28
#Sta/Elev= 30
       0269.300819.87341 269.11669.55692269.9076109.3037269.3108228.5442269.3182
317.9745268.7573327.9112268.4974337.8479263.9649347.7846261.4411 367.658267.6129
377.5947268.5405407.4048269.3102427.2783269.0813457.0884268.8205476.9618269.2365
536.3652268.8197 585.868269.1833694.7742270.8362754.1776270.6283793.7798 271.259
942.2883271.32311041.294272.46551120.499274.4952  1150.2273.64461189.802274.4731
1269.007274.9869 1318.51274.45491348.211273.49251368.013273.70511457.118273.6104
#Mann= 5 ,-1 , 0
       0     .08       0427.2783     .07       0457.0884     .08       0
1269.007     .05       01368.013     .08       0
#XS Ineff= 2 , 0
           68.18  269.89
Permanent Ineff=
       F       F
Bank Sta=317.9745,377.5947
XS Rating Curve= 0 ,0
Exp/Cntr=0.3,0.1

Chan Stop Cuts=-1
Use User Specified Reach Order=0
Composite Channel Slope=5