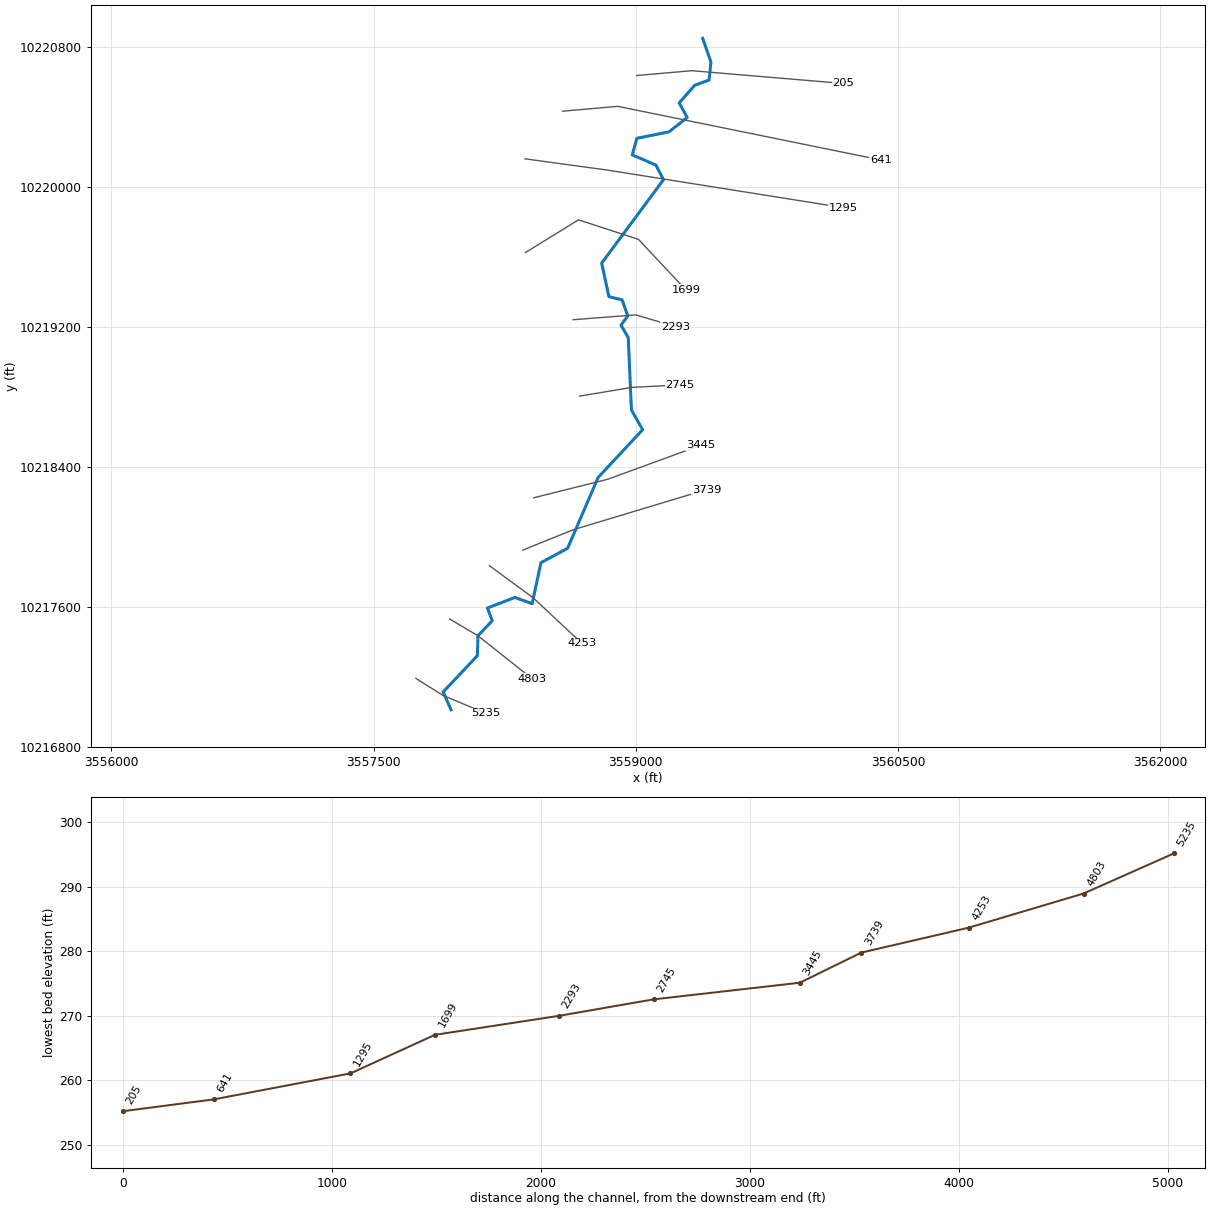
--- UNNAMEDTRIBBURTON.prj (project) ---

Proj Title=UNNAMED TRIB BURTON CREEK
Current Plan=p01
Default Exp/Contr=0.3,0.1
English Units
Geom File=g01
Flow File=f01
Plan File=p01
Y Axis Title=Elevation
X Axis Title(PF)=Main Channel Distance
X Axis Title(XS)=Station
BEGIN DESCRIPTION:
UNT145 IN GIBB
END DESCRIPTION:
DSS Export Rating Curves= 0
DSS Export Rating Curve Sorted= 0
DSS Export Volume Flow Curves= 0
DXF Filename=UNT145 IN GIBB.
DXF OffsetX= 0
DXF OffsetY= 0
DXF ScaleX= 1
DXF ScaleY= 10

--- UNNAMEDTRIBBURTON.p01 (plan) ---

Plan Title=Multiple Run
Short Identifier=Multiple
Geom File=g01
Flow File=f01
Subcritical Flow
K Sum by GR= 0
Std Step Tol= 0.01
Critical Tol= 0.01
Num of Std Step Trials= 20
Max Error Tol= 0.3
Flow Tol Ratio= 0.001
Split Flow NTrial= 30
Split Flow Tol= 0.02
Split Flow Ratio= 0.02
Log Output Level= 0
Friction Slope Method= 1
Unsteady Friction Slope Method= 2
Unsteady Bridges Friction Slope Method= 1
Parabolic Critical Depth
Global Vel Dist=  1 , 1 , 1
Global Log Level= 0
CheckData=True
Encroach Param= -1, 0, 0, 0
BEGIN DESCRIPTION:
Multiple Run
END DESCRIPTION:

--- UNNAMEDTRIBBURTON.f01 (steady flow) ---

Flow Title=Multiple
Program Version=4.10
Number of Profiles= 7
Profile Names=10-year,25-year,50-year,1pct_min,100-year,1pct_plu,500-year
River Rch & RM=UNT145 IN GIBB,Reach-1         ,5235
     248     319     374     323     436     590     594
River Rch & RM=UNT BURTON CREEK,Reach-1         ,5235
     248     319     374     323     436     590     594
Boundary for River Rch & Prof#=UNT BURTON CREEK,Reach-1         , 1
Up Type= 0
Dn Type= 3
Dn Slope=0.005
Boundary for River Rch & Prof#=UNT BURTON CREEK,Reach-1         , 2
Up Type= 0
Dn Type= 3
Dn Slope=0.005
Boundary for River Rch & Prof#=UNT BURTON CREEK,Reach-1         , 3
Up Type= 0
Dn Type= 3
Dn Slope=0.005
Boundary for River Rch & Prof#=UNT BURTON CREEK,Reach-1         , 4
Up Type= 0
Dn Type= 3
Dn Slope=0.005
Boundary for River Rch & Prof#=UNT BURTON CREEK,Reach-1         , 5
Up Type= 0
Dn Type= 3
Dn Slope=0.005
Boundary for River Rch & Prof#=UNT BURTON CREEK,Reach-1         , 6
Up Type= 0
Dn Type= 3
Dn Slope=0.005
Boundary for River Rch & Prof#=UNT BURTON CREEK,Reach-1         , 7
Up Type= 0
Dn Type= 3
Dn Slope=0.005
DSS Import GetInterval= 0
DSS Import GetPeak= 0
DSS Import FillOption= 0

--- UNNAMEDTRIBBURTON.g01 (geometry) ---

Geom Title=Existing Conditions
Program Version=4.10

River Reach=UNT BURTON CREEK,Reach-1
Reach XY= 30
      3557943.16     10217012.44      3557898.67     10217114.44
      3558093.98     10217321.68      3558097.24     10217435.62
      3558179.15     10217521.72      3558151.03     10217594.12
      3558308.32     10217654.53      3558407.28     10217618.86
      3558457.19     10217853.23      3558609.91     10217935.67
      3558784.16     10218340.44      3559038.88      10218613.5
      3558974.75     10218726.91      3558956.66     10219140.68
      3558914.89     10219211.48      3558953.81     10219263.87
      3558921.69      10219356.3      3558846.19     10219374.25
      3558804.69     10219566.19      3559158.06     10220043.24
      3559114.83     10220126.94      3558979.62     10220185.19
      3559005.62     10220279.91      3559190.11     10220317.14
      3559293.67     10220399.21      3559247.86     10220482.61
      3559336.55     10220583.33      3559418.61     10220612.89
      3559429.44     10220716.14      3559382.11     10220851.64

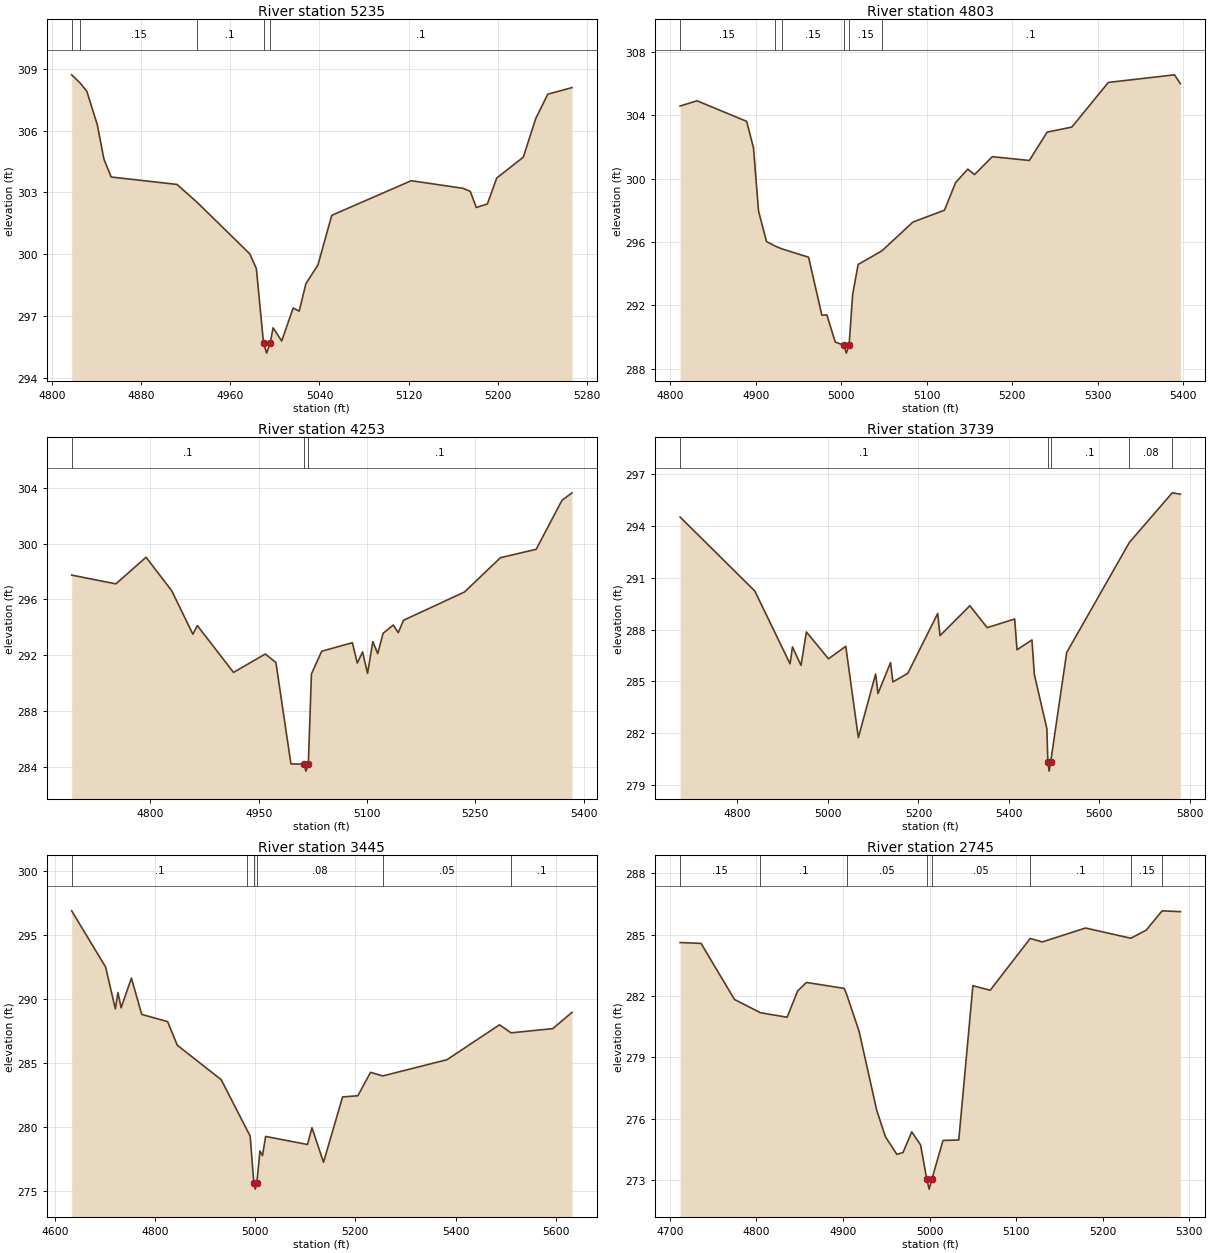
Type RM Length L Ch R = 1 ,5235    ,432,432,432
BEGIN DESCRIPTION:
UNT145 IN GIBB 10.0
END DESCRIPTION:
XS GIS Cut Line= 3
       3557742.1     10217191.64       3557896.5     10217094.91
      3558142.08     10216991.65
#Sta/Elev= 30
  4817.8  308.71  4825.1  308.33  4831.4  307.91  4840.8  306.28  4846.7  304.62
  4853.2  303.75  4912.2  303.39  4930.1  302.53  4977.5  300.02  4983.4   299.3
  4989.8   295.7  4992.6   295.2  4995.8   295.7  4998.4  296.43  5006.1  295.79
  5016.4  297.39  5021.8  297.24  5027.8  298.57  5038.6  299.48    5051  301.89
  5122.3  303.57  5168.8   303.2  5175.2  303.05  5180.6  302.27  5190.5  302.44
  5198.9   303.7  5222.7  304.71  5233.9  306.59  5244.7  307.77  5266.4  308.09
#Mann= 5 ,-1 , 0
  4817.8      .1       0  4825.1     .15       0  4930.1      .1       0
  4989.8     .07       0  4995.8      .1       0
Bank Sta=4989.8,4995.8
XS Rating Curve= 0 ,0
Exp/Cntr=0.3,0.1

Type RM Length L Ch R = 1 ,4803    ,550,550,550
BEGIN DESCRIPTION:
UNT145 IN GIBB 9.0
END DESCRIPTION:
XS GIS Cut Line= 3
      3557935.11     10217531.57      3558097.24     10217435.62
      3558408.16     10217188.92
#Sta/Elev= 30
  4811.6  304.59  4831.4  304.92  4889.5  303.62  4897.5  301.94  4903.4  297.95
  4912.7  296.03  4922.2  295.76  4930.4  295.57  4961.9  295.04  4977.5  291.37
  4983.3   291.4  4993.1  289.68  5003.3  289.48    5006  288.98  5009.3  289.48
  5013.5  292.69  5019.9  294.58  5047.7  295.44    5084  297.26  5120.9  298.01
  5133.9  299.75  5148.1   300.6  5156.1  300.26  5176.9  301.39  5220.2  301.15
    5241  302.94  5269.9  303.26  5312.6  306.08    5390  306.56  5396.9     306
#Mann= 6 ,-1 , 0
  4811.6     .15       0  4922.2      .1       0  4930.4     .15       0
  5003.3     .07       0  5009.3     .15       0  5047.7      .1       0
Bank Sta=5003.3,5009.3
XS Rating Curve= 0 ,0
Exp/Cntr=0.3,0.1

Type RM Length L Ch R = 1 ,4253    ,514,514,514
BEGIN DESCRIPTION:
UNT145 IN GIBB 8.0
END DESCRIPTION:
XS GIS Cut Line= 3
      3558162.46     10217836.34      3558411.62     10217653.58
      3558692.12     10217391.63
#Sta/Elev= 30
    4691  297.74  4752.2  297.11    4794  299.02  4829.5  296.62  4858.8   293.5
    4865  294.12  4915.1  290.76  4959.1  292.08  4973.8  291.47  4994.6   284.2
  5012.7  284.18  5015.4  283.68  5018.7  284.18    5023  290.65  5037.2  292.28
  5079.7  292.89  5086.5  291.43  5093.8  292.23  5100.7  290.69    5108  292.97
  5114.8  292.11  5122.2  293.56  5136.3  294.16  5143.2  293.61  5150.5   294.5
    5235  296.53  5284.8  298.99  5334.2  299.59  5369.9   303.1  5383.8  303.64
#Mann= 3 ,-1 , 0
    4691      .1       0  5012.7     .07       0  5018.7      .1       0
Bank Sta=5012.7,5018.7
XS Rating Curve= 0 ,0
Exp/Cntr=0.3,0.1

Type RM Length L Ch R = 1 ,3739    ,294,294,294
BEGIN DESCRIPTION:
UNT145 IN GIBB 7.0
END DESCRIPTION:
XS GIS Cut Line= 3
      3558353.09     10217925.18      3558642.11     10218041.64
      3559402.82     10218270.88
#Sta/Elev= 30
  4673.1  294.51  4838.3  290.23  4916.2  286.02  4921.6     287  4940.4  285.93
  4952.4  287.86  5001.2  286.31  5039.4  287.03  5067.2  281.75  5105.4  285.43
  5110.6   284.3  5138.4  286.09  5143.6  284.97  5176.6  285.47  5242.6  288.93
  5247.8  287.65  5313.8  289.38    5352  288.11  5412.8  288.61    5418  286.83
    5451   287.4  5456.3   285.4    5484  282.27  5486.2  280.31    5489  279.81
  5492.2  280.31  5527.8  286.67  5666.4  293.04  5761.2  295.91  5779.2  295.83
#Mann= 5 ,-1 , 0
  4673.1      .1       0  5486.2     .07       0  5492.2      .1       0
  5666.4     .08       0  5761.2      .1       0
Bank Sta=5486.2,5492.2
XS Rating Curve= 0 ,0
Exp/Cntr=0.3,0.1

Type RM Length L Ch R = 1 ,3445    ,700,700,700
BEGIN DESCRIPTION:
UNT145 IN GIBB 6.0
END DESCRIPTION:
XS GIS Cut Line= 3
      3558416.35     10218224.51      3558837.91      10218329.9
      3559368.15     10218523.48
#Sta/Elev= 30
  4633.6   296.9  4701.4   292.5  4720.8  289.23    4726  290.51  4732.3  289.32
  4752.9  291.64  4773.5   288.8  4825.1  288.24  4844.5  286.39  4932.1   283.7
  4984.3  279.72    4990   279.3  4997.3  275.64  5000.1  275.14  5003.3  275.64
  5009.5  278.12  5014.6  277.76  5020.9  279.26  5104.5  278.63  5113.4  279.94
  5136.5  277.24  5174.5  282.35    5205  282.44  5230.3  284.27  5254.8  283.99
    5383  285.26  5487.8  287.99    5511  287.36  5594.2  287.69  5632.6  288.96
#Mann= 6 ,-1 , 0
  4633.6      .1       0  4984.3     .08       0  4997.3     .07       0
  5003.3     .08       0  5254.8     .05       0    5511      .1       0
Bank Sta=4997.3,5003.3
XS Rating Curve= 0 ,0
Exp/Cntr=0.3,0.1

Type RM Length L Ch R = 1 ,2745    ,452,452,452
BEGIN DESCRIPTION:
UNT145 IN GIBB 5.0
END DESCRIPTION:
XS GIS Cut Line= 3
      3558678.22     10218805.81      3558978.18     10218855.81
      3559251.43     10218869.63
#Sta/Elev= 30
  4711.9  284.61  4736.1  284.57  4774.7  281.83  4804.7  281.18  4835.5  280.96
  4847.6  282.24  4857.8  282.66  4901.4  282.37  4904.2  282.08  4918.6  280.27
  4938.9  276.42    4949  275.12  4962.2  274.26  4969.3  274.35  4979.4  275.36
  4989.6  274.72  4996.7  273.06  4999.5  272.56  5002.7  273.06  5015.5  274.94
  5033.7  274.96    5050   282.5    5070  282.28  5116.2  284.81  5130.1  284.64
  5180.1  285.32  5232.4  284.82  5250.2  285.22  5268.5  286.16  5289.6  286.12
#Mann= 8 ,-1 , 0
  4711.9     .15       0  4804.7      .1       0  4904.2     .05       0
  4996.7     .04       0  5002.7     .05       0  5116.2      .1       0
  5232.4     .15       0  5268.5      .1       0
Bank Sta=4996.7,5002.7
XS Rating Curve= 0 ,0
Exp/Cntr=0.3,0.1

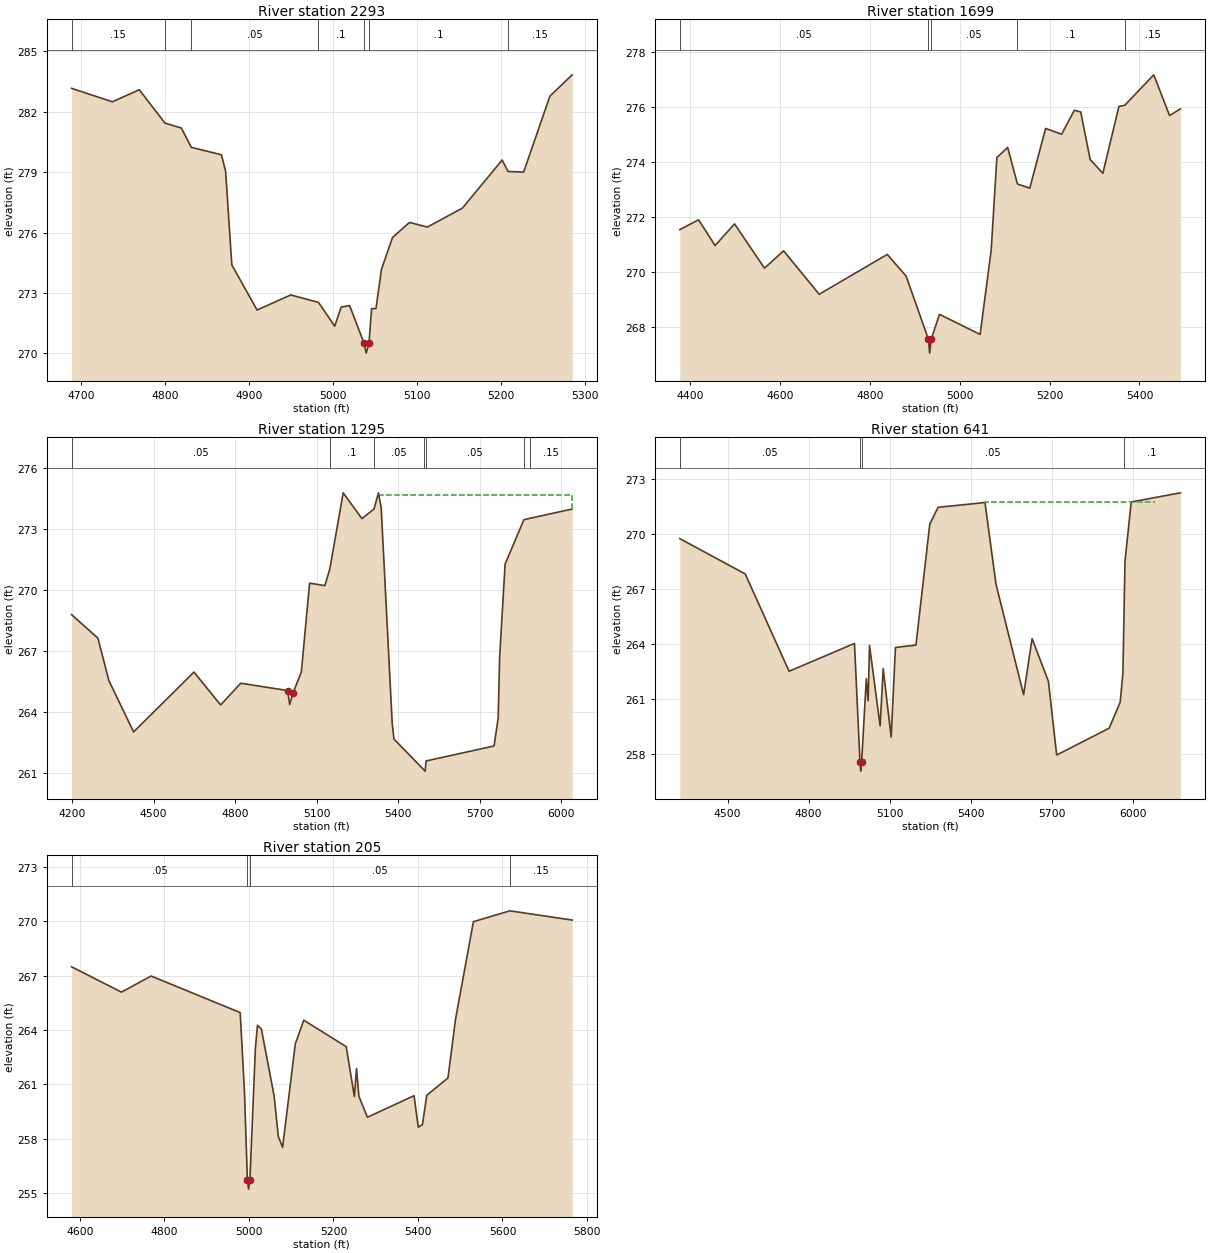
Type RM Length L Ch R = 1 ,2293    ,594,594,594
BEGIN DESCRIPTION:
UNT145 IN GIBB 4.0
END DESCRIPTION:
XS GIS Cut Line= 3
      3558641.69     10219242.65      3558999.31     10219270.33
      3559227.56     10219203.23
#Sta/Elev= 30
  4688.2  283.16  4736.8  282.49  4768.9  283.09  4799.6  281.43    4819  281.19
  4830.9  280.23  4866.8  279.86  4871.8  279.04  4879.2  274.39  4909.3  272.15
  4949.4   272.9  4982.5  272.53  5001.8  271.35  5009.6   272.3  5019.6  272.37
  5036.7  270.51  5039.4  270.01  5042.7  270.51  5045.8  272.22    5051  272.22
  5057.5  274.16  5070.7  275.75  5090.9   276.5  5112.3  276.27    5154  277.21
  5201.4   279.6  5208.4  279.03    5227     279  5258.3  282.77  5284.8  283.83
#Mann= 7 ,-1 , 0
  4688.2     .15       0  4799.6      .1       0  4830.9     .05       0
  4982.5      .1       0  5036.7     .07       0  5042.7      .1       0
  5208.4     .15       0
Bank Sta=5036.7,5042.7
XS Rating Curve= 0 ,0
Exp/Cntr=0.3,0.1

Type RM Length L Ch R = 1 ,1699    ,404,404,404
BEGIN DESCRIPTION:
UNT145 IN GIBB 3.0
END DESCRIPTION:
XS GIS Cut Line= 4
      3558368.43      10219626.6      3558672.24     10219813.83
      3559015.32     10219701.97      3559286.61      10219412.3
#Sta/Elev= 30
  4376.5  271.55  4418.3  271.91    4455  270.97  4498.3  271.76    4565  270.15
  4607.6  270.78  4686.8   269.2  4838.4  270.65  4880.4  269.86  4930.1  267.56
  4932.8  267.06  4936.1  267.56  4954.7  268.47  5045.2  267.74  5069.8   270.8
  5082.4  274.17  5106.5  274.54  5128.2  273.21  5155.8  273.06    5191  275.23
  5226.7  275.02    5255  275.89  5269.2  275.83  5290.2   274.1  5318.5   273.6
  5354.2  276.03  5367.1  276.07  5431.8  277.18    5467   275.7  5491.1  275.94
#Mann= 5 ,-1 , 0
  4376.5     .05       0  4930.1     .04       0  4936.1     .05       0
  5128.2      .1       0  5367.1     .15       0
Bank Sta=4930.1,4936.1
XS Rating Curve= 0 ,0
Exp/Cntr=0.3,0.1

Type RM Length L Ch R = 1 ,1295    ,654,654,654
BEGIN DESCRIPTION:
UNT145 IN GIBB 1.2
END DESCRIPTION:
XS GIS Cut Line= 3
      3558366.13     10220162.73      3558844.77     10220097.16
      3560185.51     10219883.92
#Sta/Elev= 30
  4198.6  268.79  4295.5  267.63  4335.8  265.54  4426.7  263.01  4648.7  265.96
  4746.7  264.34  4820.8  265.41  4992.9  265.05  5000.7  264.36  5013.2  264.94
  5043.5  265.96  5073.9  270.34  5130.1  270.22  5148.2  271.03  5197.4  274.79
  5266.3  273.52  5310.6  273.99  5327.1  274.79  5337.2  274.05  5377.7  263.43
    5384  262.66  5498.9  261.08  5502.2  261.58  5752.3  262.32  5767.4  263.71
  5772.6  266.65  5792.8  271.28  5861.7  273.46  5885.6  273.54  6039.3  273.99
#Mann= 7 ,-1 , 0
  4198.6     .05       0  5148.2      .1       0  5310.6     .05       0
  5496.2     .04       0  5502.2     .05       0  5861.7      .1       0
  5885.6     .15       0
#XS Ineff= 1 ,-1
  5326.7 6038.35  274.68
Permanent Ineff=
       F
Bank Sta=4992.9,5013.2
XS Rating Curve= 0 ,0
Exp/Cntr=0.3,0.1

Type RM Length L Ch R = 1 ,641     ,436,436,436
BEGIN DESCRIPTION:
UNT145 IN GIBB 1.1
END DESCRIPTION:
XS GIS Cut Line= 3
        3558581.     10220434.99      3558896.96     10220462.77
      3560400.34     10220156.18
#Sta/Elev= 30
  4323.4  269.74  4565.4  267.81  4727.5   262.5  4969.4  264.02  4989.8  257.55
  4992.6  257.05  4995.8  257.55  5013.2  262.09  5019.9  260.89    5025  263.91
  5064.3  259.52  5075.6  262.64  5105.1  258.91    5121   263.8  5196.9  263.93
    5248  270.53  5278.6  271.45  5452.1  271.71  5492.9  267.25    5595  261.22
  5626.4  264.28  5686.8  261.95  5717.3  257.93  5911.3  259.39  5952.2  260.81
  5962.4  262.41  5966.7  265.86    5970   268.5    5993  271.74  6174.9  272.24
#Mann= 4 ,-1 , 0
  4323.4     .05       0  4989.8     .04       0  4995.8     .05       0
  5966.7      .1       0
#XS Ineff= 1 ,-1
 5450.28 6079.55  271.75
Permanent Ineff=
       F
Bank Sta=4989.8,4995.8
XS Rating Curve= 0 ,0
Exp/Cntr=0.3,0.1

Type RM Length L Ch R = 1 ,205     ,0,0,0
BEGIN DESCRIPTION:
UNT145 IN GIBB 1.0
END DESCRIPTION:
XS GIS Cut Line= 3
       3559004.5     10220638.83      3559320.47      10220666.6
      3560185.01     10220593.69
#Sta/Elev= 30
  4580.1  267.49  4698.2  266.09  4768.4  266.98  4979.2  264.96  4989.3  260.61
  4996.3  255.71    4999  255.21  5002.3  255.71  5015.1  262.96  5020.1  264.26
  5029.4  264.05  5059.5  260.36  5069.5  258.11  5079.6  257.52  5109.7  263.23
  5129.7  264.54  5230.1  263.08  5249.5  260.32  5254.5  261.87  5260.2  260.34
  5280.3  259.18  5390.7  260.37  5400.7  258.63  5410.7  258.78  5420.8  260.39
    5471  261.35  5488.9  264.59  5531.2  269.98  5617.6  270.58  5764.9  270.07
#Mann= 4 ,-1 , 0
  4580.1     .05       0  4996.3     .04       0  5002.3     .05       0
  5617.6     .15       0
Bank Sta=4996.3,5002.3
XS Rating Curve= 0 ,0
Exp/Cntr=0.3,0.1

Chan Stop Cuts=-1
Use User Specified Reach Order=0
Composite Channel Slope=5