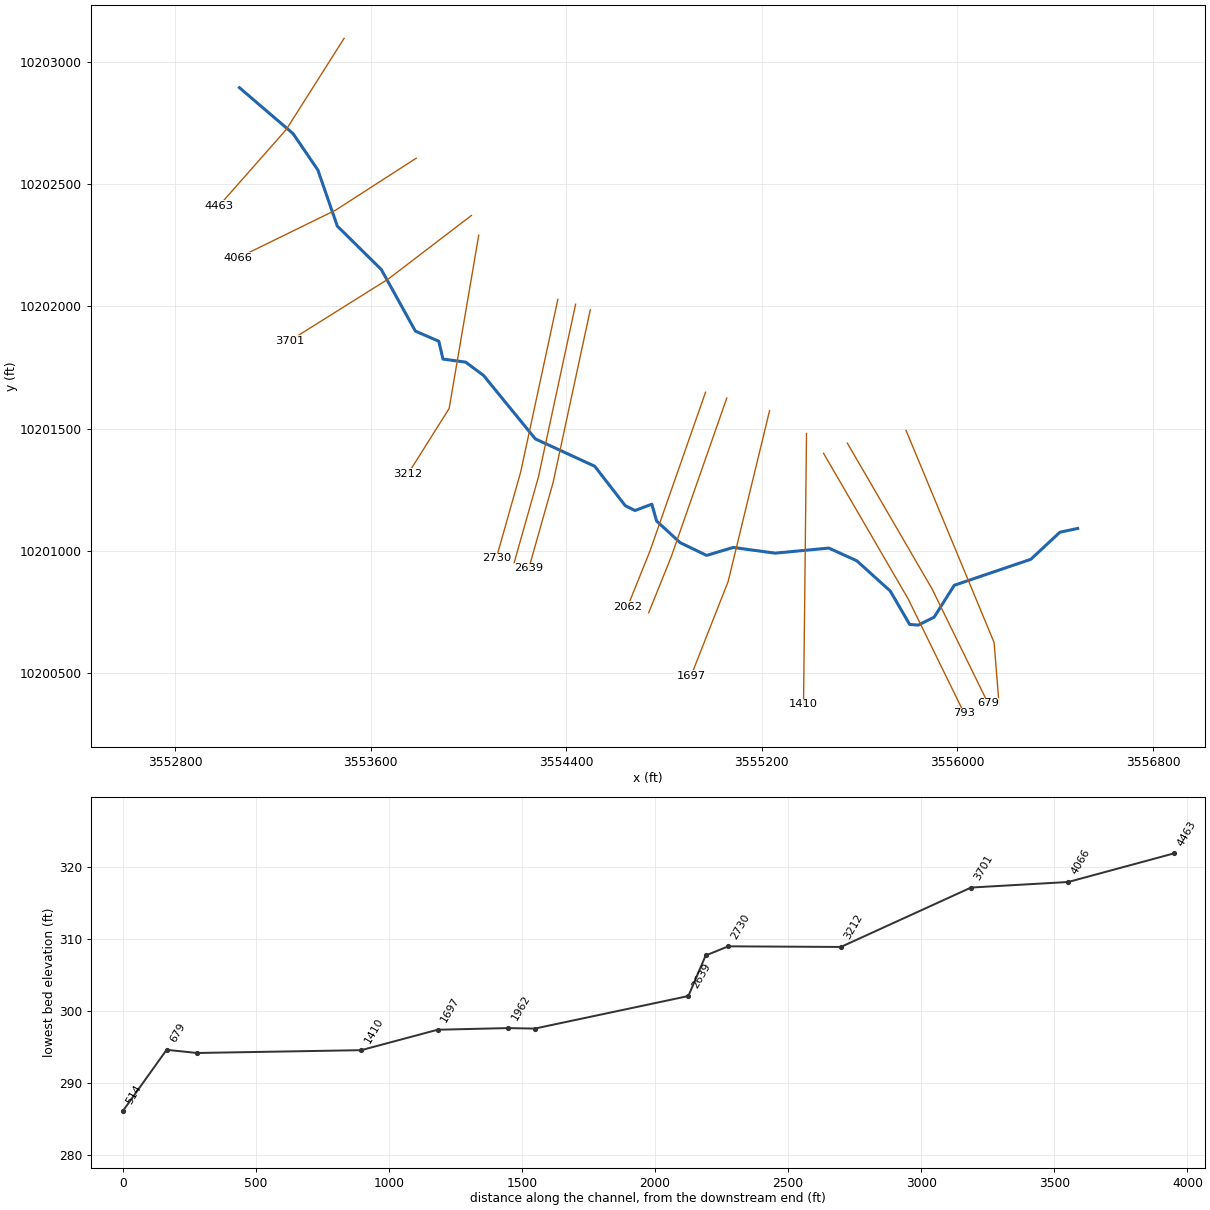
--- UNNAMED TRIB TO BEE CREEK TRIB B.prj (project) ---

Proj Title=UNNAMED TRIB TO BEE CREEK TRIB B Base Level Engineering
Current Plan=p01
Default Exp/Contr=0.3,0.1
English Units
Geom File=g01
Flow File=f01
Plan File=p01
Y Axis Title=Elevation
X Axis Title(PF)=Main Channel Distance
X Axis Title(XS)=Station
BEGIN DESCRIPTION:
UNNAMED TRIB TO BEE CREEK TRIB B
END DESCRIPTION:
DSS Export Rating Curves= 0
DSS Export Rating Curve Sorted= 0
DSS Export Volume Flow Curves= 0
DXF OffsetX= 0
DXF OffsetY= 0
DXF ScaleX= 1
DXF ScaleY= 10

--- UNNAMED TRIB TO BEE CREEK TRIB B.p01 (plan) ---

Plan Title=Multiple Run
Short Identifier=Multiple
Geom File=g01
Flow File=f01
Subcritical Flow
K Sum by GR= 0
Std Step Tol= 0.01
Critical Tol= 0.01
Num of Std Step Trials= 20
Max Error Tol= 0.3
Flow Tol Ratio= 0.001
Split Flow NTrial= 30
Split Flow Tol= 0.02
Split Flow Ratio= 0.02
Log Output Level= 0
Friction Slope Method= 1
Unsteady Friction Slope Method= 2
Unsteady Bridges Friction Slope Method= 1
Parabolic Critical Depth
Global Vel Dist=  1 , 1 , 1
Global Log Level= 0
CheckData=True
Encroach Param= -1, 0, 0, 0
BEGIN DESCRIPTION:
Multiple Run
END DESCRIPTION:

--- UNNAMED TRIB TO BEE CREEK TRIB B.f01 (steady flow) ---

Flow Title=Multiple
Number of Profiles=7
Profile Names=10-year,25-year,50-year,1pct_min,100-year,1pct_plu,500-year
River Rch & RM= UNNAMED TRIB TO ,Reach-1,4463
     225     286     333     285     386     522     517
Boundary for River Rch & Prof#=UNNAMED TRIB TO ,Reach-1,1
Up Type=0
Dn Type=3
Dn Slope=0.005
Boundary for River Rch & Prof#=UNNAMED TRIB TO ,Reach-1,2
Up Type=0
Dn Type=3
Dn Slope=0.005
Boundary for River Rch & Prof#=UNNAMED TRIB TO ,Reach-1,3
Up Type=0
Dn Type=3
Dn Slope=0.005
Boundary for River Rch & Prof#=UNNAMED TRIB TO ,Reach-1,4
Up Type=0
Dn Type=3
Dn Slope=0.005
Boundary for River Rch & Prof#=UNNAMED TRIB TO ,Reach-1,5
Up Type=0
Dn Type=3
Dn Slope=0.005
Boundary for River Rch & Prof#=UNNAMED TRIB TO ,Reach-1,6
Up Type=0
Dn Type=3
Dn Slope=0.005
Boundary for River Rch & Prof#=UNNAMED TRIB TO ,Reach-1,7
Up Type=0
Dn Type=3
Dn Slope=0.005

--- UNNAMED TRIB TO BEE CREEK TRIB B.g01 (geometry) ---

Geom Title=Existing Conditions
Program Version=4.10

River Reach=UNNAMED TRIB TO ,Reach-1
Reach XY= 30
      3553063.01      10202895.3      3553282.28     10202707.63
      3553383.84     10202558.67      3553463.53     10202328.98
      3553643.74     10202150.86       3553782.8      10201899.3
      3553878.63     10201857.63      3553895.82     10201784.71
      3553988.53     10201772.21      3554061.97     10201717.53
      3554273.46     10201458.16      3554516.52     10201346.18
      3554641.52     10201184.72      3554681.17     10201164.98
      3554750.18     10201191.02      3554769.71     10201122.01
      3554866.06     10201033.47      3554974.13     10200981.39
      3555083.51     10201013.94      3555254.08      10200990.5
      3555474.13     10201011.34      3555588.72     10200959.25
      3555725.44     10200835.56      3555804.86     10200698.84
      3555840.02     10200696.23      3555905.12     10200728.78
      3555987.16     10200858.99      3556300.54     10200965.42
      3556419.38     10201076.17      3556492.11     10201091.64

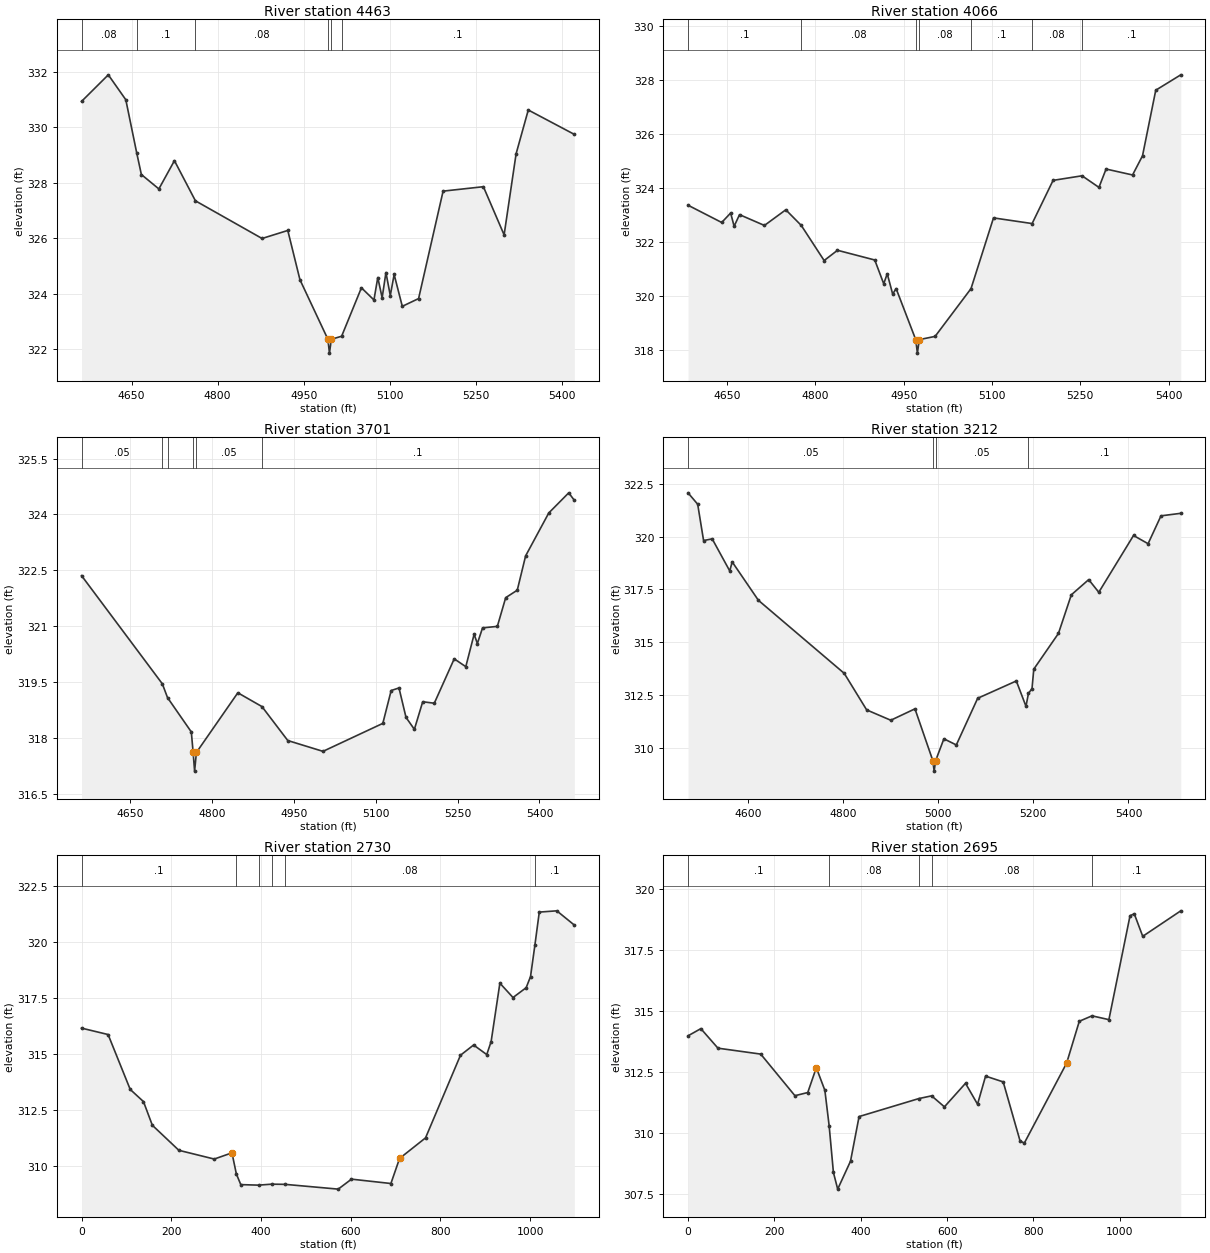
Type RM Length L Ch R = 1 ,4463    ,397,397,397
BEGIN DESCRIPTION:
UNNAMED TRIB TO BEE CREEK TRIB B 9.0
END DESCRIPTION:
XS GIS Cut Line= 3
      3553491.31     10203097.22      3553254.85      10202724.3
      3552979.19      10202411.5
#Sta/Elev= 30
  4562.9  330.94  4609.5   331.9    4640     331  4658.9  329.09  4667.1   328.3
  4697.6  327.78  4724.7   328.8  4761.3  327.35  4877.4  325.99  4922.2  326.28
  4943.4   324.5  4992.1  322.35  4994.8  321.85  4998.1  322.35    5016  322.46
  5050.5  324.21  5072.3  323.77    5079  324.58  5086.6  323.85  5093.2  324.76
  5100.8  323.93  5107.5  324.69  5121.7  323.54  5150.1  323.82  5192.8   327.7
    5263  327.86  5299.1  326.12    5320  329.05  5341.2  330.63  5421.4  329.75
#Mann= 6 ,-1 , 0
  4562.9     .08       0  4658.9      .1       0  4761.3     .08       0
  4992.1     .07       0  4998.1     .08       0    5016      .1       0
Bank Sta=4992.1,4998.1
XS Rating Curve= 0 ,0
Exp/Cntr=0.3,0.1

Type RM Length L Ch R = 1 ,4066    ,365,365,365
BEGIN DESCRIPTION:
UNNAMED TRIB TO BEE CREEK TRIB B 8.0
END DESCRIPTION:
XS GIS Cut Line= 3
      3553786.46     10202606.79      3553457.11     10202394.44
      3553057.28      10202198.8
#Sta/Elev= 30
  4583.6  323.37  4640.8  322.73    4656  323.08  4661.9  322.59  4671.1  323.02
  4713.4  322.62  4749.7   323.2    4776  322.62  4814.8  321.32  4837.5   321.7
  4900.8  321.34    4916  320.46    4922  320.83  4931.2  320.08  4937.1  320.28
  4970.4  318.39  4973.2  317.89  4976.4  318.39  5003.3  318.51  5064.3  320.28
  5102.5   322.9  5168.1  322.69  5203.7  324.29  5252.9  324.46  5281.6  324.03
  5293.7  324.71  5338.7  324.49  5355.6   325.2  5378.1  327.63  5420.6   328.2
#Mann= 7 ,-1 , 0
  4583.6      .1       0    4776     .08       0  4970.4     .07       0
  4976.4     .08       0  5064.3      .1       0  5168.1     .08       0
  5252.9      .1       0
Bank Sta=4970.4,4976.4
XS Rating Curve= 0 ,0
Exp/Cntr=0.3,0.1

Type RM Length L Ch R = 1 ,3701    ,489,489,489
BEGIN DESCRIPTION:
UNNAMED TRIB TO BEE CREEK TRIB B 7.0
END DESCRIPTION:
XS GIS Cut Line= 3
      3554012.13      10202372.4      3553673.25     10202113.19
      3553269.96     10201860.26
#Sta/Elev= 30
  4561.1  322.36  4709.1  319.46  4718.6  319.09  4762.2  318.17  4765.5  317.62
  4768.2  317.12  4771.5  317.62  4847.4  319.22  4891.6  318.85  4938.9  317.94
  5003.4  317.65    5113   318.4  5128.3  319.28  5142.6  319.35  5155.5  318.56
  5170.8  318.24  5186.1  318.98  5207.3  318.94  5243.8  320.13    5265  319.92
  5280.3  320.79  5286.2  320.54  5295.7  320.96  5322.8     321  5338.1  321.77
  5359.3  321.97  5374.6  322.89    5417  324.04  5453.6  324.58  5463.8  324.38
#Mann= 6 ,-1 , 0
  4561.1     .05       0  4709.1     .08       0  4718.6     .05       0
  4765.5     .07       0  4771.5     .05       0  4891.6      .1       0
Bank Sta=4765.5,4771.5
XS Rating Curve= 0 ,0
Exp/Cntr=0.3,0.1

Type RM Length L Ch R = 1 ,3212    ,423,423,423
BEGIN DESCRIPTION:
UNNAMED TRIB TO BEE CREEK TRIB B 6.0
END DESCRIPTION:
XS GIS Cut Line= 3
      3554042.11     10202291.69      3553921.02     10201582.49
      3553752.74     10201314.98
#Sta/Elev= 30
  4474.4  322.07  4494.7  321.53  4507.1  319.81  4525.2  319.89  4562.1  318.37
  4567.2   318.8  4622.3  316.98  4802.7  313.52  4849.8  311.79  4900.5   311.3
  4951.3  311.84  4988.8  309.39  4991.6  308.89  4994.8  309.39  5012.1  310.42
  5038.2  310.13  5083.1  312.34  5164.3  313.16  5184.6  311.96  5189.8  312.57
  5197.3   312.8    5201  313.72  5252.8  315.41  5279.9  317.24  5316.4  317.96
  5337.6  317.36  5410.6  320.05  5441.2  319.66  5468.3  320.98  5509.9   321.1
#Mann= 4 ,-1 , 0
  4474.4     .05       0  4988.8     .04       0  4994.8     .05       0
  5189.8      .1       0
Bank Sta=4988.8,4994.8
XS Rating Curve= 0 ,0
Exp/Cntr=0.3,0.1

Type RM Length L Ch R = 1 ,2730    ,85,85,85
BEGIN DESCRIPTION:
UNNAMED TRIB TO BEE CREEK TRIB B 5.2
END DESCRIPTION:
XS GIS Cut Line= 3
      3554365.64     10202029.01       3554213.7     10201322.84
      3554113.91     10200970.02
#Sta/Elev= 30
       0 316.16459.15205315.8781108.4454313.4277138.0215312.8838157.7388311.8285
216.8909310.7097295.7603310.3194335.1949310.5969345.0536309.6517354.9123309.1779
394.3894309.1547423.9973309.1982453.6051  309.19572.0364308.9767601.6266 309.422
689.4846309.2275708.7847310.3467766.6851 311.265844.5345314.9537873.8092315.4107
903.0839314.9831912.8421315.5631932.3586318.1702961.6332317.5298990.9079 317.968
1000.666318.46521010.424319.87341020.183 321.3441059.215321.40041098.248320.7649
#Mann= 6 ,-1 , 0
       0      .1       0345.0536     .05       0394.3894     .08       0
423.9973     .07       0453.6051     .08       01010.424      .1       0
Bank Sta=335.1949,708.7847
XS Rating Curve= 0 ,0
Exp/Cntr=0.3,0.1

Type RM Length L Ch R = 1 ,2695    ,65,65,65
BEGIN DESCRIPTION:
UNNAMED TRIB TO BEE CREEK TRIB B 5.1
END DESCRIPTION:
XS GIS Cut Line= 3
       3554438.3       10202009.      3554286.37     10201302.83
      3554186.85     10200950.96
#Sta/Elev= 30
       0313.985429.71022314.279569.32385313.4795168.3579 313.237247.5852311.5334
277.2954311.6635297.1022312.6801 316.909 311.754326.8124310.3051336.7159308.3908
346.6192307.7077376.3295308.8531396.1363310.6791534.4893311.4156564.1315311.5276
593.7737 311.077642.5968312.0409670.4974311.1847689.0978312.3352729.9133312.0985
769.0775309.6746778.8686309.5951876.7792312.8678906.1524314.5814935.5256 314.804
974.6898314.64781023.645318.90371033.436318.98181053.018318.05921141.138319.1038
#Mann= 5 ,-1 , 0
       0      .1       0326.8124     .08       0534.4893     .07       0
564.1315     .08       0935.5256      .1       0
Bank Sta=297.1022,876.7792
XS Rating Curve= 0 ,0
Exp/Cntr=0.3,0.1

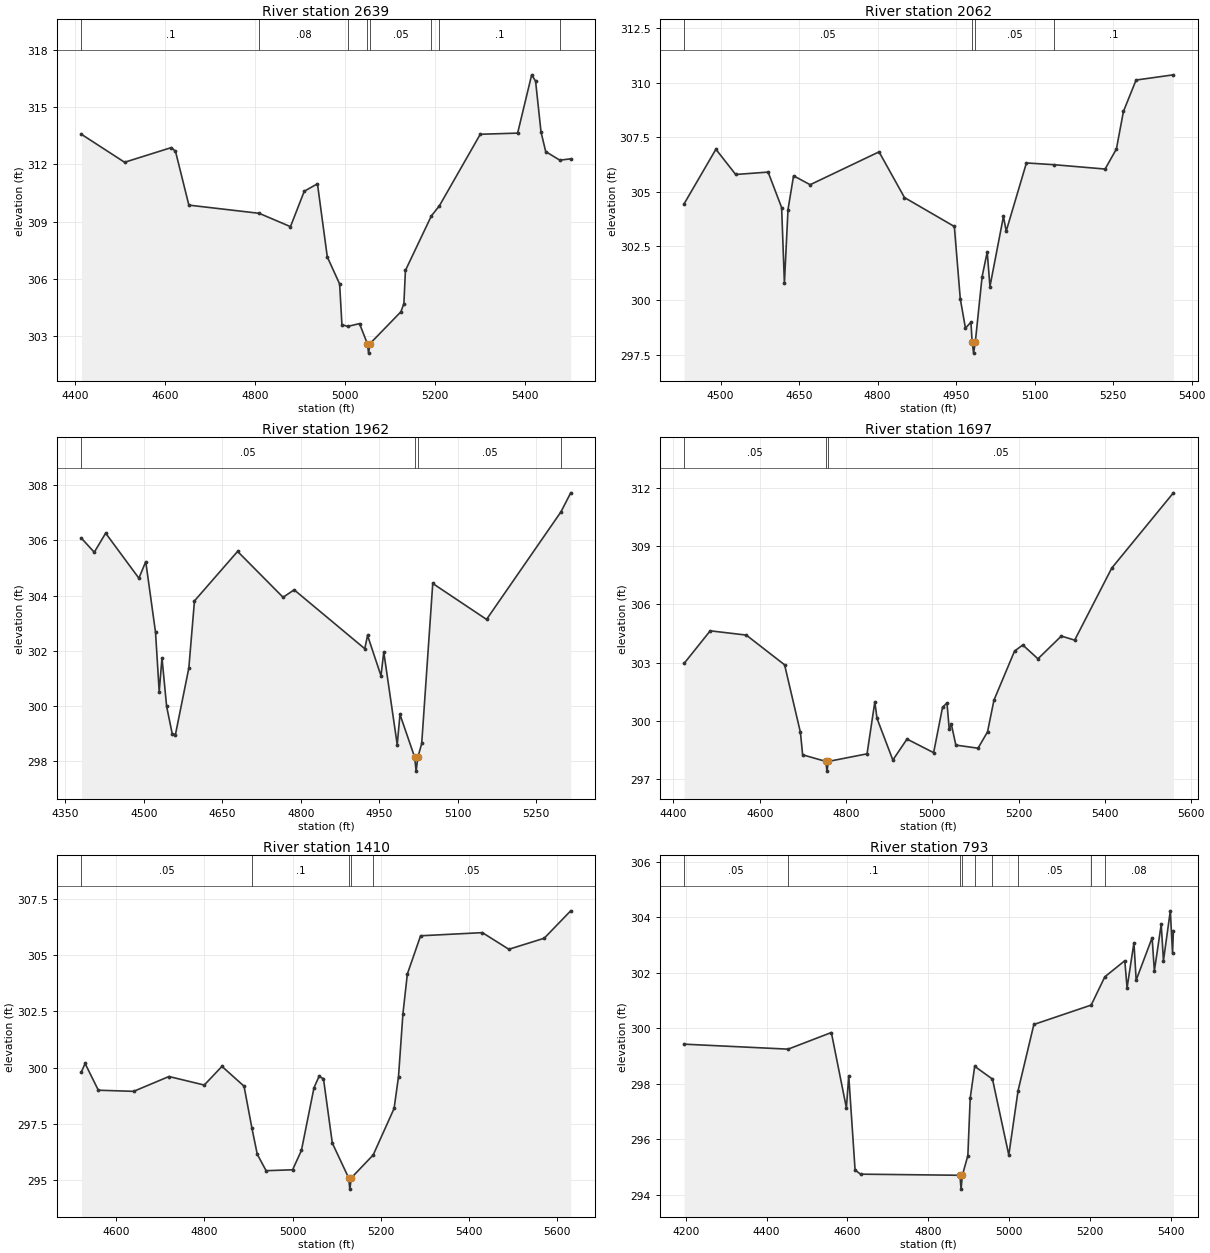
Type RM Length L Ch R = 1 ,2639    ,577,577,577
BEGIN DESCRIPTION:
UNNAMED TRIB TO BEE CREEK TRIB B 5.0
END DESCRIPTION:
XS GIS Cut Line= 3
      3554498.28     10201986.17      3554346.34     10201279.98
      3554246.83     10200928.13
#Sta/Elev= 30
  4413.2  313.58  4509.3  312.11  4613.1  312.88  4622.4  312.69  4652.2  309.86
  4808.5  309.43  4878.1  308.73  4908.8  310.59  4938.1  310.98    4960  307.14
  4987.4  305.72  4992.5  303.59    5005  303.49  5031.6  303.64    5049  302.59
  5051.8  302.09    5055  302.59  5123.6  304.26  5130.3  304.69  5133.7  306.43
  5191.3  309.29  5209.1  309.82  5300.1  313.58  5383.2  313.64  5414.4   316.7
  5423.1  316.37  5435.2   313.7  5445.6  312.67    5477  312.22  5501.2  312.29
#Mann= 8 ,-1 , 0
  4413.2      .1       0  4808.5     .08       0    5005     .05       0
    5049     .07       0    5055     .05       0  5191.3     .08       0
  5209.1      .1       0    5477     .05       0
Bank Sta=5049,5055
XS Rating Curve= 0 ,0
Exp/Cntr=0.3,0.1

Type RM Length L Ch R = 1 ,2062    ,100,100,100
BEGIN DESCRIPTION:
UNNAMED TRIB TO BEE CREEK TRIB B 4.1
END DESCRIPTION:
XS GIS Cut Line= 3
      3554969.88     10201649.06      3554742.24     10200998.57
      3554650.45     10200770.63
#Sta/Elev= 30
  4430.2  304.44    4491  306.95  4528.8  305.79  4590.8   305.9  4616.6  304.27
  4621.9  300.79  4628.8  304.18  4639.4  305.73  4671.1  305.32  4802.7  306.83
  4851.3  304.73  4946.6   303.4  4957.9  300.08  4967.8  298.73  4978.3     299
  4980.6  298.08  4983.4  297.58  4986.6  298.08  4999.6  301.09  5009.4  302.23
  5014.6  300.64  5040.4  303.86  5045.7  303.19  5084.3  306.32  5136.9  306.24
  5234.6  306.04  5256.2  306.96  5269.7  308.69  5293.8  310.13  5365.1  310.37
#Mann= 4 ,-1 , 0
  4430.2     .05       0  4980.6     .03       0  4986.6     .05       0
  5136.9      .1       0
Bank Sta=4980.6,4986.6
XS Rating Curve= 0 ,0
Exp/Cntr=0.3,0.1

Type RM Length L Ch R = 1 ,1962    ,265,265,265
BEGIN DESCRIPTION:
UNNAMED TRIB TO BEE CREEK TRIB B 4.0
END DESCRIPTION:
XS GIS Cut Line= 3
      3555056.78      10201625.4      3554829.11     10200974.83
      3554737.31     10200746.87
#Sta/Elev= 30
  4380.7  306.08  4405.3  305.57  4427.1  306.26  4490.6  304.63  4503.7  305.23
  4522.4  302.67  4529.4  300.52  4534.7  301.75  4543.6  299.99  4554.2  299.01
  4560.4  298.97    4586  301.38  4596.8  303.81  4679.2   305.6  4766.1  303.94
  4787.3  304.21  4922.2  302.08  4927.5  302.56  4953.2   301.1  4958.5  301.96
  4984.2  298.61  4989.5   299.7  5017.6  298.15  5020.3  297.65  5023.6  298.15
    5031  298.65  5052.1  304.44  5154.9  303.14    5297  307.03  5315.7  307.72
#Mann= 4 ,-1 , 0
  4380.7     .05       0  5017.6     .03       0  5023.6     .05       0
    5297      .1       0
Bank Sta=5017.6,5023.6
XS Rating Curve= 0 ,0
Exp/Cntr=0.3,0.1

Type RM Length L Ch R = 1 ,1697    ,287,287,287
BEGIN DESCRIPTION:
UNNAMED TRIB TO BEE CREEK TRIB B 3.1
END DESCRIPTION:
XS GIS Cut Line= 3
      3555231.78     10201573.81      3555062.51     10200875.03
      3554910.59     10200488.72
#Sta/Elev= 30
  4424.6  302.96  4485.2  304.64  4568.8  304.42  4657.6  302.89  4694.3  299.41
  4699.4  298.26  4753.1  297.92  4755.8  297.42  4759.1  297.92  4848.7  298.31
  4866.7  300.98  4871.8  300.13  4908.5  297.99  4941.3  299.07    5003  298.37
  5023.6   300.7  5033.9  300.93  5039.1  299.59  5044.2  299.82  5054.5  298.76
  5105.9   298.6  5127.9  299.44  5142.8  301.07  5190.6   303.6  5209.7  303.91
  5244.8   303.2    5299  304.37  5329.9  304.16  5415.9  307.87  5558.7  311.74
#Mann= 3 ,-1 , 0
  4424.6     .05       0  4753.1     .03       0  4759.1     .05       0
Bank Sta=4753.1,4759.1
XS Rating Curve= 0 ,0
Exp/Cntr=0.3,0.1

Type RM Length L Ch R = 1 ,1410    ,617,617,617
BEGIN DESCRIPTION:
UNNAMED TRIB TO BEE CREEK TRIB B 3.0
END DESCRIPTION:
XS GIS Cut Line= 3
      3555382.82     10201480.07      3555375.57      10200807.2
      3555370.67     10200371.54
#Sta/Elev= 30
  4521.6   299.8    4530  300.18    4560  298.99    4640  298.94    4720   299.6
    4800  299.22  4840.1  300.05  4890.1  299.17  4908.1  297.29  4920.1  296.14
  4940.1  295.41  5000.1  295.45  5020.1  296.31  5048.6   299.1  5060.1  299.61
  5070.1   299.5  5090.1  296.64  5127.1  295.09  5129.8  294.59  5133.1  295.09
  5182.7  296.11  5230.1  298.18  5240.1   299.6  5250.1  302.39  5260.1  304.16
  5290.1  305.86  5430.1     306  5490.1  305.26  5570.1  305.75  5630.2  306.97
#Mann= 5 ,-1 , 0
  4521.6     .05       0  4908.1      .1       0  5127.1     .07       0
  5133.1      .1       0  5182.7     .05       0
Bank Sta=5127.1,5133.1
XS Rating Curve= 0 ,0
Exp/Cntr=0.3,0.1

Type RM Length L Ch R = 1 ,793     ,114,114,114
BEGIN DESCRIPTION:
UNNAMED TRIB TO BEE CREEK TRIB B 2.1
END DESCRIPTION:
XS GIS Cut Line= 3
      3555452.54      10201399.1      3555798.99      10200802.8
      3556028.06      10200334.9
#Sta/Elev= 30
  4195.8  299.43  4453.3  299.25  4560.2  299.85  4597.4  297.13  4603.2  298.29
  4618.9  294.89  4632.3  294.74  4878.3   294.7  4881.1   294.2  4884.3   294.7
  4897.9  295.41  4903.7  297.48  4914.8  298.63  4958.8  298.17  4999.2  295.43
  5022.1  297.75  5061.2  300.14    5203  300.84  5236.8  301.86  5286.2  302.44
  5291.8  301.46  5308.8  303.09  5314.3  301.74  5353.8  303.27  5359.3  302.07
  5376.3  303.75  5381.8  302.44  5398.8  304.24  5404.3  302.71  5406.4  303.52
#Mann= 9 ,-1 , 0
  4195.8     .05       0  4453.3      .1       0  4878.3     .07       0
  4884.3      .1       0  4914.8     .05       0  4958.8      .1       0
  5022.1     .05       0    5203     .15       0  5236.8     .08       0
Bank Sta=4878.3,4884.3
XS Rating Curve= 0 ,0
Exp/Cntr=0.3,0.1

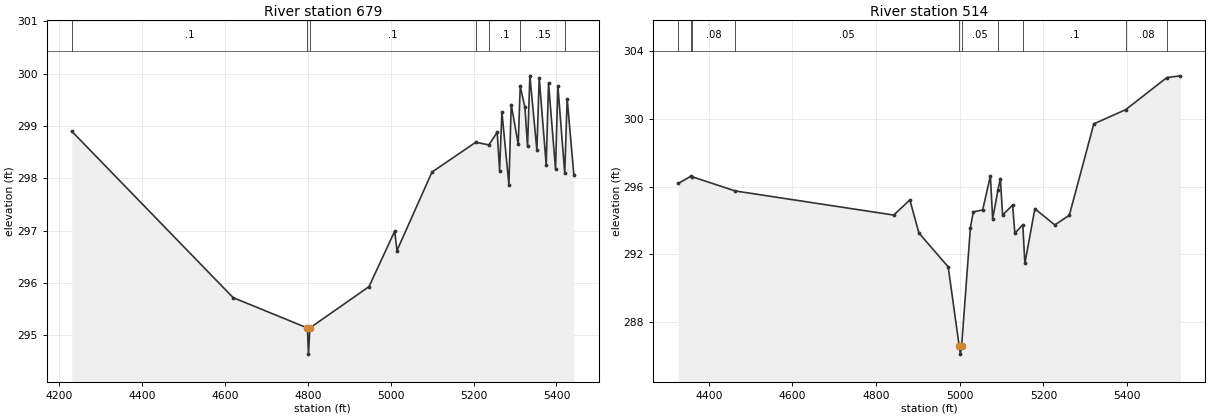
Type RM Length L Ch R = 1 ,679     ,165,165,165
BEGIN DESCRIPTION:
UNNAMED TRIB TO BEE CREEK TRIB B 2.0
END DESCRIPTION:
XS GIS Cut Line= 3
      3555549.94     10201440.61      3555896.42     10200844.27
      3556125.86     10200375.61
#Sta/Elev= 30
  4230.4   298.9  4619.8  295.72  4798.9  295.14  4801.6  294.64  4804.9  295.14
  4947.6  295.93  5009.6  296.99  5015.1  296.62  5099.6  298.12  5205.2  298.69
  5236.8  298.64    5257  298.88  5262.7  298.15  5268.3  299.27  5285.2  297.88
  5290.8  299.41  5307.7  298.65  5312.5  299.76  5323.8  299.36  5330.2  298.61
  5335.8  299.96  5352.7  298.54  5358.3  299.92  5375.2  298.26  5380.8  299.82
  5397.7  298.18  5403.3  299.77  5419.9   298.1  5425.8  299.52  5441.9  298.07
#Mann= 7 ,-1 , 0
  4230.4      .1       0  4798.9     .07       0  4804.9      .1       0
  5205.2     .15       0  5236.8      .1       0  5312.5     .15       0
  5419.9     .08       0
Bank Sta=4798.9,4804.9
XS Rating Curve= 0 ,0
Exp/Cntr=0.3,0.1

Type RM Length L Ch R = 1 ,514     ,0,0,0
BEGIN DESCRIPTION:
UNNAMED TRIB TO BEE CREEK TRIB B 1.0
END DESCRIPTION:
XS GIS Cut Line= 3
      3555789.95     10201493.05      3556150.18     10200625.03
       3556171.2     10200365.48
#Sta/Elev= 30
  4327.1  296.18  4356.8   296.6    4360  296.58  4463.3  295.74  4842.2  294.32
  4880.8  295.21  4902.5  293.26  4972.4  291.27  4998.6  286.63  5001.4  286.13
  5004.6  286.63  5025.5  293.57  5032.4  294.51  5054.8  294.62  5073.3  296.63
  5078.7   294.1  5091.4   295.8  5097.1  296.47  5102.5  294.32  5126.4  294.91
  5131.8  293.25  5150.8  293.75  5155.7  291.47  5179.6  294.69  5227.3  293.74
    5262  294.31  5320.5  299.69  5396.9  300.53  5495.2  302.42  5527.3  302.52
#Mann= 10 ,-1 , 0
  4327.1     .15       0  4356.8      .1       0    4360     .08       0
  4463.3     .05       0  4998.6     .04       0  5004.6     .05       0
  5091.4     .08       0  5150.8      .1       0  5396.9     .08       0
  5495.2     .15       0
Bank Sta=4998.6,5004.6
XS Rating Curve= 0 ,0
Exp/Cntr=0.3,0.1

Chan Stop Cuts=-1
Use User Specified Reach Order=0
Composite Channel Slope=5