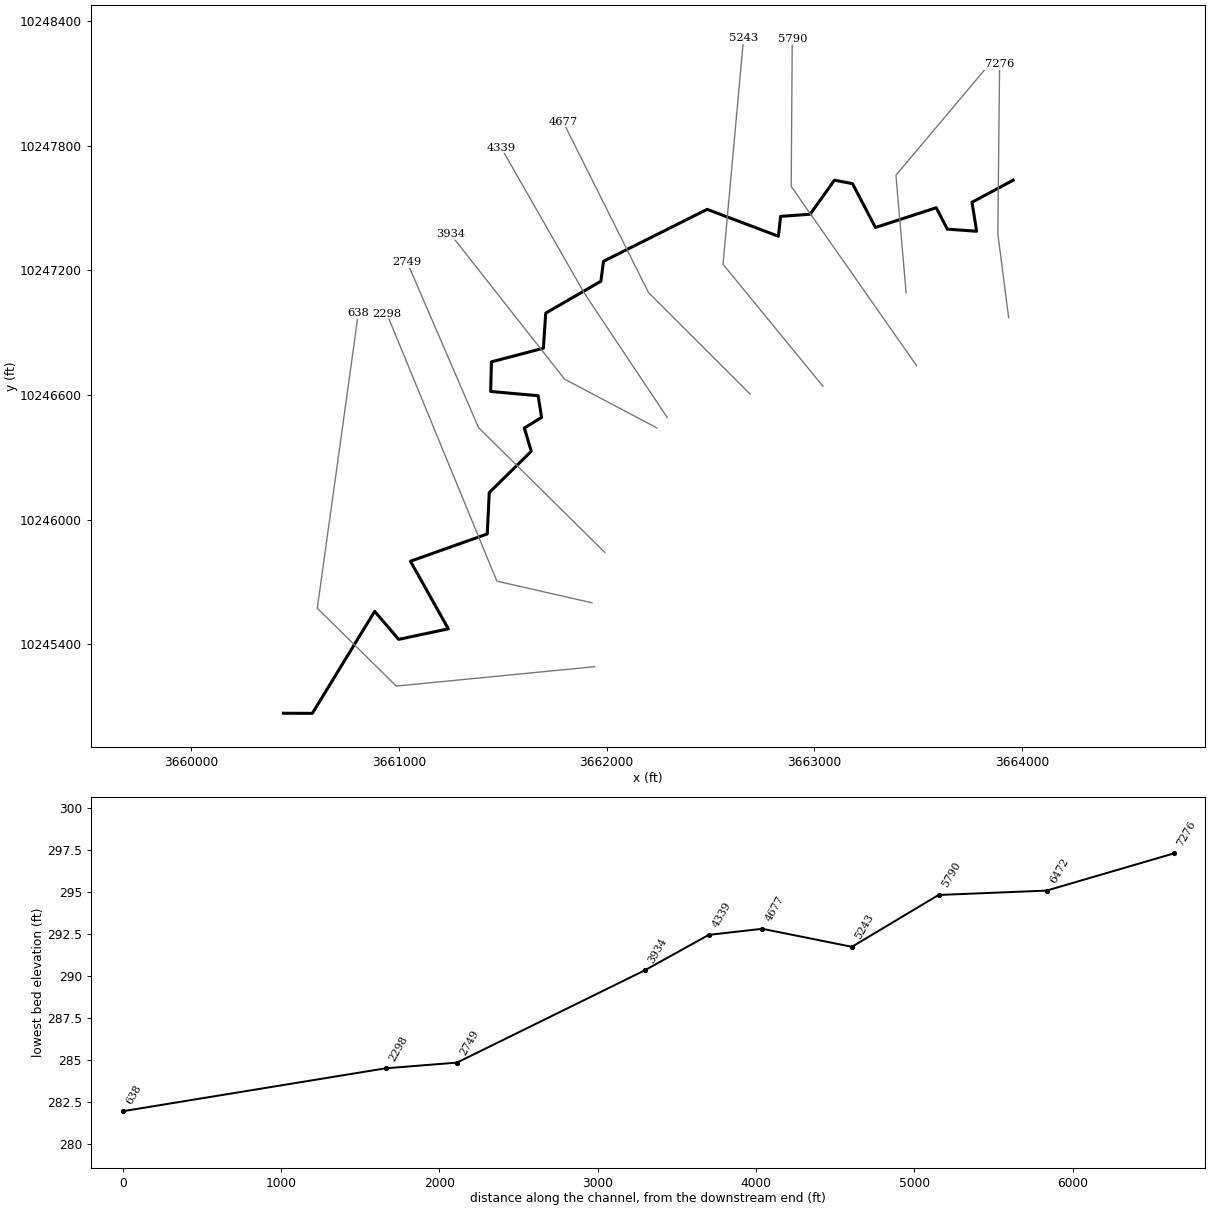
--- UNT004 IN GIBB.prj (project) ---

Proj Title=UNT004 IN GIBB Base Level Engineering
Current Plan=p01
Default Exp/Contr=0.3,0.1
English Units
Geom File=g01
Flow File=f01
Plan File=p01
BEGIN DESCRIPTION:
UNT004 IN GIBB
END DESCRIPTION:

--- UNT004 IN GIBB.p01 (plan) ---

Plan Title=Multiple Run
Short Identifier=Multiple
Geom File=g01
Flow File=f01
Subcritical Flow
K Sum by GR= 0
Std Step Tol= 0.01
Critical Tol= 0.01
Num of Std Step Trials= 20
Max Error Tol= 0.3
Flow Tol Ratio= 0.001
Split Flow NTrial= 30
Split Flow Tol= 0.02
Split Flow Ratio= 0.02
Log Output Level= 0
Friction Slope Method= 1
Unsteady Friction Slope Method= 2
Unsteady Bridges Friction Slope Method= 1
Parabolic Critical Depth
Global Vel Dist=  1 , 1 , 1
Global Log Level= 0
CheckData=True
Encroach Param= -1, 0, 0, 0
BEGIN DESCRIPTION:
Multiple Run
END DESCRIPTION:

--- UNT004 IN GIBB.f01 (steady flow) ---

Flow Title=Multiple
Number of Profiles=7
Profile Names=10-year,25-year,50-year,1pct_min,100-year,1pct_plu,500-year
River Rch & RM= UNT004 IN GIBB,Reach-1,7276
     705     940    1130     993    1343    1817    1899
Boundary for River Rch & Prof#=UNT004 IN GIBB,Reach-1,1
Up Type=0
Dn Type=3
Dn Slope=0.005
Boundary for River Rch & Prof#=UNT004 IN GIBB,Reach-1,2
Up Type=0
Dn Type=3
Dn Slope=0.005
Boundary for River Rch & Prof#=UNT004 IN GIBB,Reach-1,3
Up Type=0
Dn Type=3
Dn Slope=0.005
Boundary for River Rch & Prof#=UNT004 IN GIBB,Reach-1,4
Up Type=0
Dn Type=3
Dn Slope=0.005
Boundary for River Rch & Prof#=UNT004 IN GIBB,Reach-1,5
Up Type=0
Dn Type=3
Dn Slope=0.005
Boundary for River Rch & Prof#=UNT004 IN GIBB,Reach-1,6
Up Type=0
Dn Type=3
Dn Slope=0.005
Boundary for River Rch & Prof#=UNT004 IN GIBB,Reach-1,7
Up Type=0
Dn Type=3
Dn Slope=0.005

--- UNT004 IN GIBB.g01 (geometry) ---

Geom Title=Existing Conditions

River Reach=UNT004 IN GIBB,Reach-1
Reach XY= 30
      3663957.04     10247634.21      3663759.37     10247528.08
      3663781.58     10247388.32      3663640.65     10247398.60
      3663587.01     10247501.63      3663294.52     10247406.53
      3663184.04     10247617.67      3663096.97     10247634.19
      3662979.94     10247470.41      3662838.01     10247460.00
      3662827.16     10247364.51      3662484.28     10247493.85
      3661985.37     10247243.86      3661972.76     10247147.60
      3661707.30     10246994.20      3661695.84     10246825.13
      3661445.94     10246759.60      3661442.06     10246616.96
      3661670.62     10246596.39      3661687.26     10246492.06
      3661604.21     10246440.85      3661637.78     10246329.00
      3661435.34     10246129.97      3661425.77     10245930.76
      3661056.03     10245799.49      3661238.36     10245473.93
      3660999.17     10245423.13      3660883.72     10245558.11
      3660583.67     10245066.83      3660444.91     10245067.49

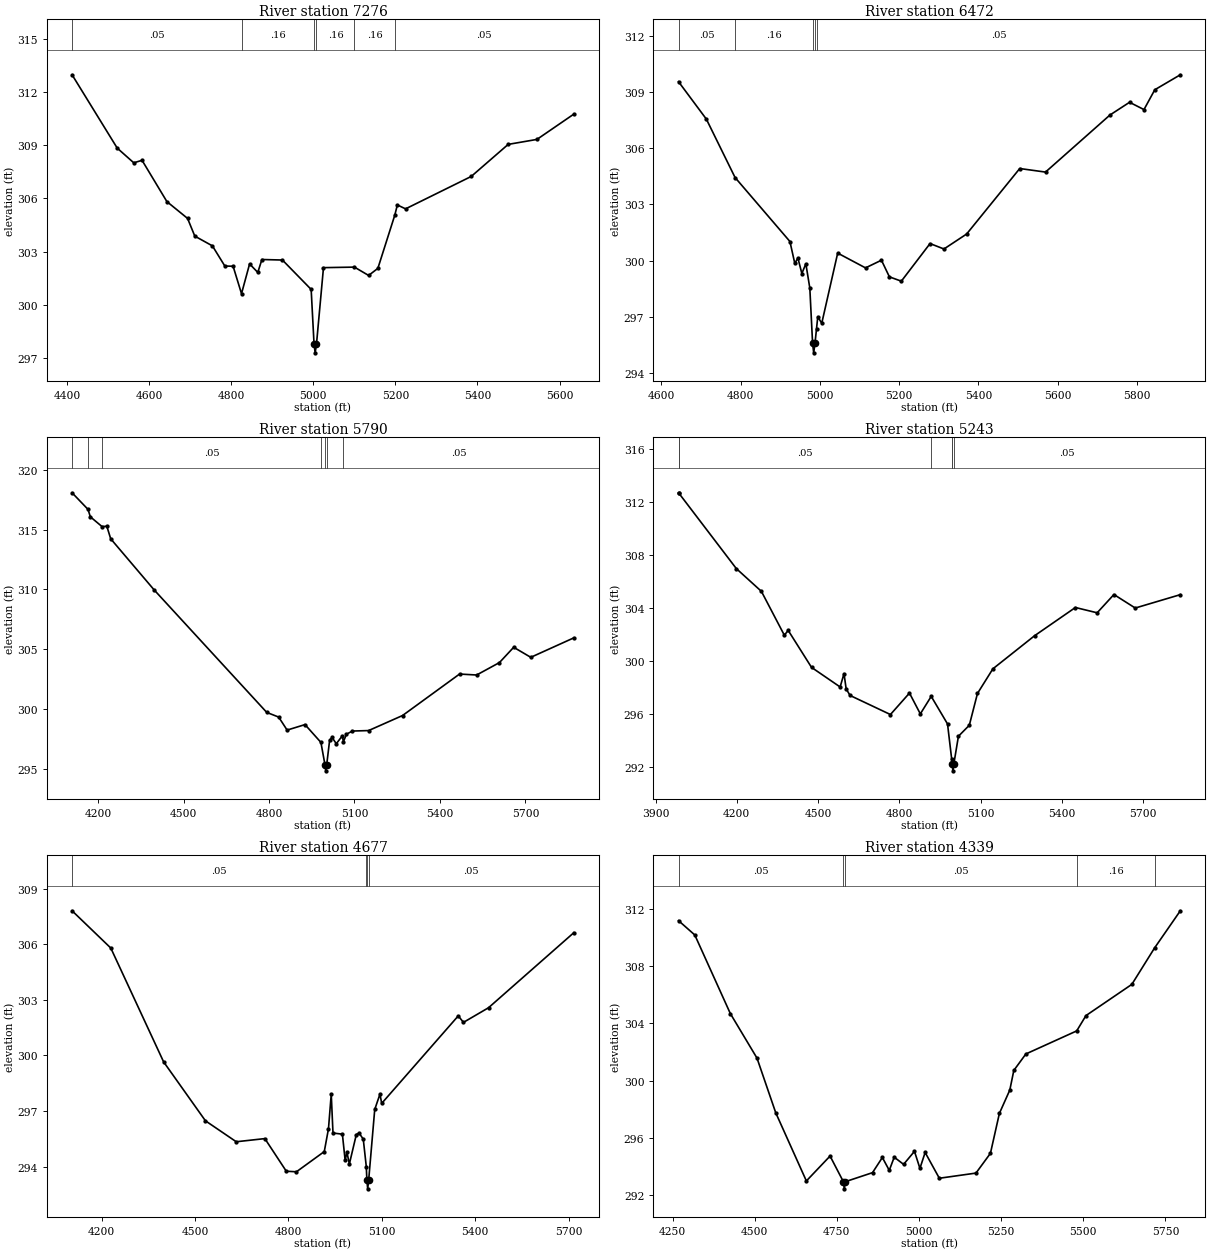
Type RM Length L Ch R = 1,7276,804,804,804
BEGIN DESCRIPTION:
UNT004 IN GIBB 11.0
END DESCRIPTION:
XS GIS Cut Line= 3
      3663935.70     10246972.54      3663883.61     10247376.19
      3663892.11     10248191.65
#Sta/Elev= 30
  4412.3  312.98  4522.3  308.84  4562.6  308.01  4582.8  308.15  4643.3  305.82
  4693.7  304.87  4711.3  303.87  4754.2  303.32  4784.5  302.18  4804.6  302.17
  4825.1  300.62  4844.8  302.30  4864.8  301.82  4874.8  302.55  4924.8  302.52
  4994.8  300.86  5001.8  297.78  5004.5  297.28  5007.8  297.78  5024.8  302.09
  5100.2  302.12  5134.8  301.65  5157.3  302.05  5198.5  305.05  5204.8  305.63
  5224.8  305.41  5384.8  307.24  5474.8  309.05  5544.8  309.33  5634.8  310.76
#Mann=6,-1,0
  4412.3    0.05       0  4825.1    0.16       0  5001.8    0.07       0
  5007.8    0.16       0  5100.2    0.16       0  5198.5    0.05       0
Bank Sta=5001.8,5007.8
Exp/Cntr=0.3,0.1

Type RM Length L Ch R = 1,6472,682,682,682
BEGIN DESCRIPTION:
UNT004 IN GIBB 10.0
END DESCRIPTION:
XS GIS Cut Line= 3
      3663442.10     10247091.67      3663393.16     10247658.31
      3663842.11     10248191.65
#Sta/Elev= 30
  4643.5  309.56  4713.7  307.56  4786.1  304.44  4924.5  301.02  4936.8  299.85
  4944.6  300.14  4954.6  299.31  4964.7  299.83  4974.7  298.53  4981.7  295.57
  4984.5  295.07  4987.7  295.57  4991.6  296.36  4994.8  297.00  5004.8  296.65
  5045.0  300.40  5115.2  299.61  5155.4  300.02  5175.5  299.13  5205.6  298.90
  5278.0  300.91  5313.1  300.62  5370.3  301.42  5504.3  304.92  5569.3  304.73
  5731.9  307.78  5781.3  308.46  5817.7  308.07  5845.0  309.13  5909.4  309.93
#Mann=5,-1,0
  4643.5    0.05       0  4786.1    0.16       0  4981.7    0.03       0
  4987.7    0.16       0  4991.6    0.05       0
Bank Sta=4981.7,4987.7
Exp/Cntr=0.3,0.1

Type RM Length L Ch R = 1,5790,547,547,547
BEGIN DESCRIPTION:
UNT004 IN GIBB 9.0
END DESCRIPTION:
XS GIS Cut Line= 3
      3663492.11     10246741.64      3662888.82     10247604.49
      3662894.03     10248312.83
#Sta/Elev= 30
  4108.8  318.08  4164.8  316.69  4172.9  316.07  4214.0  315.25  4230.8  315.28
  4244.4  314.23  4396.2  309.97  4792.1  299.70  4833.9  299.31  4863.6  298.22
  4926.4  298.68  4982.2  297.19  4996.5  295.31  4999.3  294.81  5002.5  295.31
  5012.7  297.36  5021.4  297.61  5036.1  297.08  5057.2  297.73  5061.2  297.25
  5072.0  297.88  5092.9  298.14  5149.6  298.18  5268.8  299.44  5468.8  302.91
  5528.8  302.83  5608.8  303.87  5658.8  305.15  5718.8  304.31  5870.0  305.94
#Mann=7,-1,0
  4108.8    0.05       0  4164.8    0.16       0  4214.0    0.05       0
  4982.2    0.12       0  4996.5    0.07       0  5002.5    0.12       0
  5061.2    0.05       0
Bank Sta=4996.5,5002.5
Exp/Cntr=0.3,0.1

Type RM Length L Ch R = 1,5243,566,566,566
BEGIN DESCRIPTION:
UNT004 IN GIBB 8.0
END DESCRIPTION:
XS GIS Cut Line= 3
      3663042.11     10246641.64      3662560.69     10247229.49
      3662659.59     10248317.38
#Sta/Elev= 30
  3985.0  312.72  3985.1  312.72  4198.2  307.00  4290.8  305.28  4375.5  301.97
  4389.8  302.33  4475.9  299.54  4581.5  298.06  4595.8  299.07  4603.7  297.92
  4618.1  297.42  4767.1  295.98  4837.4  297.60  4877.5  296.03  4917.7  297.35
  4977.9  295.27  4993.2  292.62  4995.0  292.23  4997.8  291.73  5001.0  292.23
  5018.1  294.34  5058.3  295.17  5088.4  297.57  5145.3  299.43  5299.3  301.93
  5449.9  304.06  5530.2  303.66  5592.1  305.04  5670.8  304.02  5837.2  305.03
#Mann=6,-1,0
  3985.0     0.1       0  3985.1    0.05       0  4917.7    0.12       0
  4993.2    0.05       0  4995.0    0.03       0  5001.0    0.05       0
Bank Sta=4995,5001
Exp/Cntr=0.3,0.1

Type RM Length L Ch R = 1,4677,338,338,338
BEGIN DESCRIPTION:
UNT004 IN GIBB 7.0
END DESCRIPTION:
XS GIS Cut Line= 3
      3662690.90     10246604.49      3662201.32     10247094.07
      3661789.96     10247916.78
#Sta/Elev= 30
  4104.9  307.80  4229.3  305.79  4399.0  299.65  4533.4  296.47  4632.4  295.34
  4724.3  295.51  4793.2  293.75  4825.8  293.72  4915.2  294.81  4928.7  296.04
  4937.6  297.91  4943.2  295.81  4973.4  295.75  4982.3  294.33  4987.9  294.78
  4995.8  294.14  5018.2  295.73  5027.0  295.81  5040.5  295.48  5050.2  294.00
  5052.0  293.30  5054.7  292.80  5058.0  293.30  5077.3  297.08  5094.1  297.91
  5099.7  297.41  5345.7  302.13  5362.4  301.78  5443.0  302.57  5717.1  306.62
#Mann=4,-1,0
  4104.9    0.05       0  5050.2    0.16       0  5052.0    0.03       0
  5058.0    0.05       0
Bank Sta=5052,5058
Exp/Cntr=0.3,0.1

Type RM Length L Ch R = 1,4339,405,405,405
BEGIN DESCRIPTION:
UNT004 IN GIBB 6.0
END DESCRIPTION:
XS GIS Cut Line= 3
      3662292.08     10246491.68      3661892.11     10247091.64
      3661492.10     10247791.65
#Sta/Elev= 30
  4268.2  311.17  4317.7  310.17  4425.9  304.68  4507.0  301.57  4564.1  297.75
  4657.3  292.99  4729.4  294.73  4769.9  292.94  4772.7  292.44  4775.9  292.94
  4858.6  293.57  4888.6  294.63  4909.6  293.73  4924.7  294.65  4953.2  294.15
  4986.3  295.06  5002.9  293.87  5018.8  294.98  5062.0  293.18  5173.5  293.54
  5217.5  294.92  5244.8  297.71  5276.5  299.34  5288.7  300.71  5325.4  301.86
  5480.1  303.47  5508.3  304.54  5647.9  306.72  5717.0  309.26  5795.5  311.86
#Mann=5,-1,0
  4268.2    0.05       0  4769.9    0.03       0  4775.9    0.05       0
  5480.1    0.16       0  5717.0    0.05       0
Bank Sta=4769.9,4775.9
Exp/Cntr=0.3,0.1

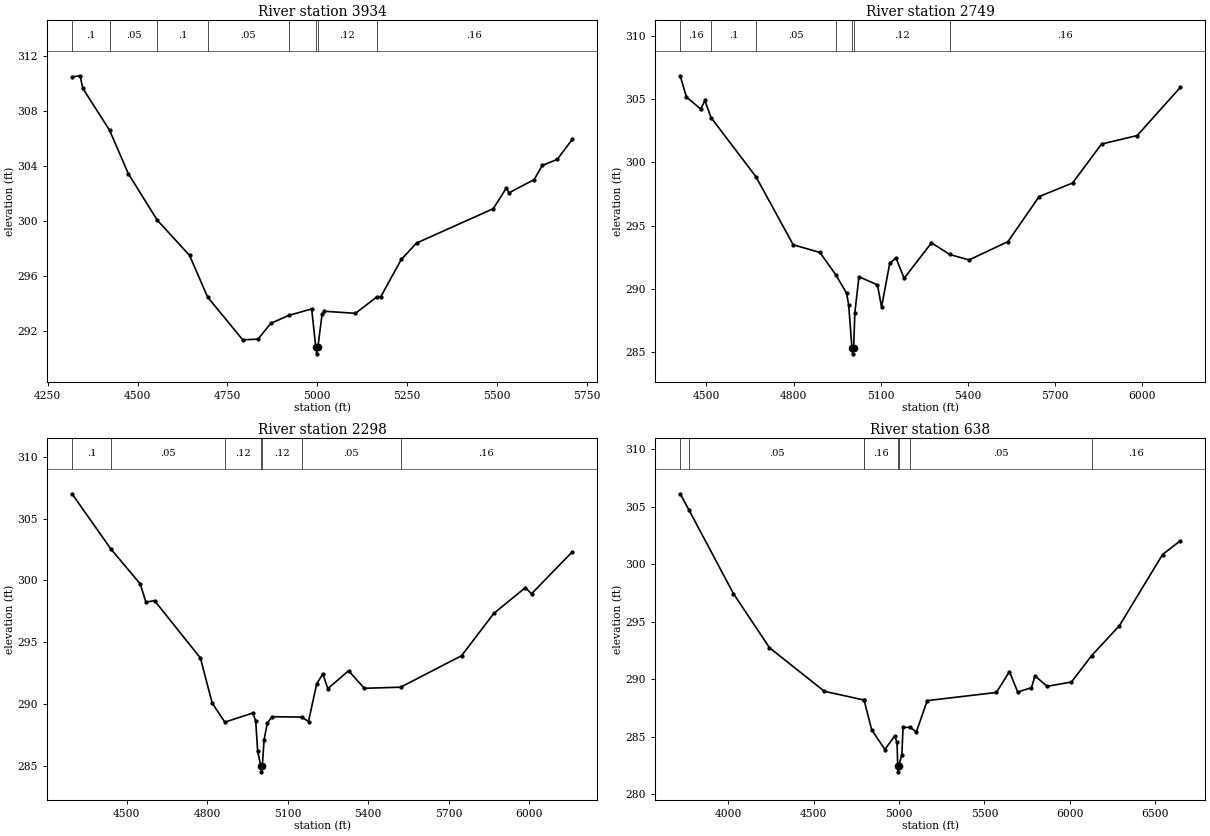
Type RM Length L Ch R = 1,3934,1185,1185,1185
BEGIN DESCRIPTION:
UNT004 IN GIBB 5.0
END DESCRIPTION:
XS GIS Cut Line= 3
      3662242.09     10246441.65      3661797.67     10246676.52
      3661248.21     10247375.31
#Sta/Elev= 30
  4317.4  310.50  4340.0  310.58  4347.6  309.66  4422.0  306.61  4474.0  303.46
  4554.5  300.07  4644.4  297.50  4694.8  294.46  4792.4  291.35  4835.0  291.40
  4870.3  292.55  4920.8  293.13  4984.2  293.60  4995.6  290.83  4998.4  290.33
  5001.6  290.83  5013.1  293.20  5019.4  293.43  5106.1  293.28  5164.6  294.46
  5176.7  294.50  5233.7  297.21  5276.1  298.40  5489.4  300.90  5526.2  302.42
  5532.7  302.05  5603.2  303.02  5625.8  304.05  5667.4  304.49  5709.0  305.94
#Mann=8,-1,0
  4317.4     0.1       0  4422.0    0.05       0  4554.5     0.1       0
  4694.8    0.05       0  4920.8    0.12       0  4995.6    0.07       0
  5001.6    0.12       0  5164.6    0.16       0
Bank Sta=4995.6,5001.6
Exp/Cntr=0.3,0.1

Type RM Length L Ch R = 1,2749,451,451,451
BEGIN DESCRIPTION:
UNT004 IN GIBB 4.0
END DESCRIPTION:
XS GIS Cut Line= 3
      3661992.11     10245841.64      3661383.61     10246443.03
      3661040.57     10247238.26
#Sta/Elev= 30
  4409.6  306.85  4430.8  305.18  4480.3  304.21  4494.4  304.90  4515.8  303.54
  4670.4  298.86  4798.5  293.48  4890.4  292.87  4945.3  291.10  4982.4  289.64
  4989.4  288.73  5000.6  285.35  5003.3  284.85  5006.6  285.35  5010.7  288.11
  5024.8  290.95  5088.4  290.31  5102.6  288.55  5130.8  292.02  5152.1  292.44
  5180.4  290.83  5274.5  293.63  5337.3  292.71  5403.8  292.28  5537.7  293.73
  5644.8  297.29  5760.2  298.37  5859.7  301.45  5982.4  302.12  6131.2  305.94
#Mann=7,-1,0
  4409.6    0.16       0  4515.8     0.1       0  4670.4    0.05       0
  4945.3    0.12       0  5000.6    0.07       0  5006.6    0.12       0
  5337.3    0.16       0
Bank Sta=5000.6,5006.6
Exp/Cntr=0.3,0.1

Type RM Length L Ch R = 1,2298,1660,1660,1660
BEGIN DESCRIPTION:
UNT004 IN GIBB 3.0
END DESCRIPTION:
XS GIS Cut Line= 3
      3661930.49     10245599.28      3661472.15     10245703.44
      3660942.11     10246991.64
#Sta/Elev= 30
  4296.4  307.01  4441.3  302.54  4550.6  299.72  4571.6  298.25  4603.9  298.36
  4774.8  293.72  4818.5  290.08  4865.7  288.53  4969.9  289.27  4980.7  288.62
  4988.0  286.17  4999.4  285.01  5002.1  284.51  5005.4  285.01  5012.0  287.12
  5024.0  288.46  5041.4  288.97  5152.5  288.94  5177.3  288.58  5207.8  291.63
  5230.7  292.43  5249.2  291.24  5326.5  292.69  5385.2  291.27  5520.2  291.36
  5747.6  293.91  5867.4  297.33  5984.8  299.41  6008.0  298.92  6159.4  302.30
#Mann=7,-1,0
  4296.4     0.1       0  4441.3    0.05       0  4865.7    0.12       0
  4999.4    0.07       0  5005.4    0.12       0  5152.5    0.05       0
  5520.2    0.16       0
Bank Sta=4999.4,5005.4
Exp/Cntr=0.3,0.1

Type RM Length L Ch R = 1,638,0,0,0
BEGIN DESCRIPTION:
UNT004 IN GIBB 1.0
END DESCRIPTION:
XS GIS Cut Line= 4
      3661942.11     10245291.64      3660987.78     10245198.24
      3660607.57     10245573.24      3660805.49     10246995.11
#Sta/Elev= 30
  3718.8  306.13  3769.8  304.73  4030.3  297.46  4241.3  292.75  4562.8  288.96
  4795.3  288.20  4795.9  288.17  4839.7  285.62  4917.5  283.90  4974.0  285.07
  4988.2  284.55  4992.2  282.46  4995.0  281.96  4998.2  282.46  5016.5  283.44
  5023.5  285.82  5065.1  285.83  5101.3  285.43  5164.9  288.15  5569.8  288.86
  5646.4  290.67  5694.7  288.90  5775.5  289.27  5795.7  290.31  5866.4  289.39
  6009.5  289.77  6127.9  292.07  6290.4  294.67  6542.8  300.85  6647.3  302.05
#Mann=8,-1,0
  3718.8     0.1       0  3769.8    0.05       0  4795.3    0.12       0
  4795.9    0.16       0  4992.2    0.07       0  4998.2    0.16       0
  5065.1    0.05       0  6127.9    0.16       0
Bank Sta=4992.2,4998.2
Exp/Cntr=0.3,0.1

Chan Stop Cuts=-1