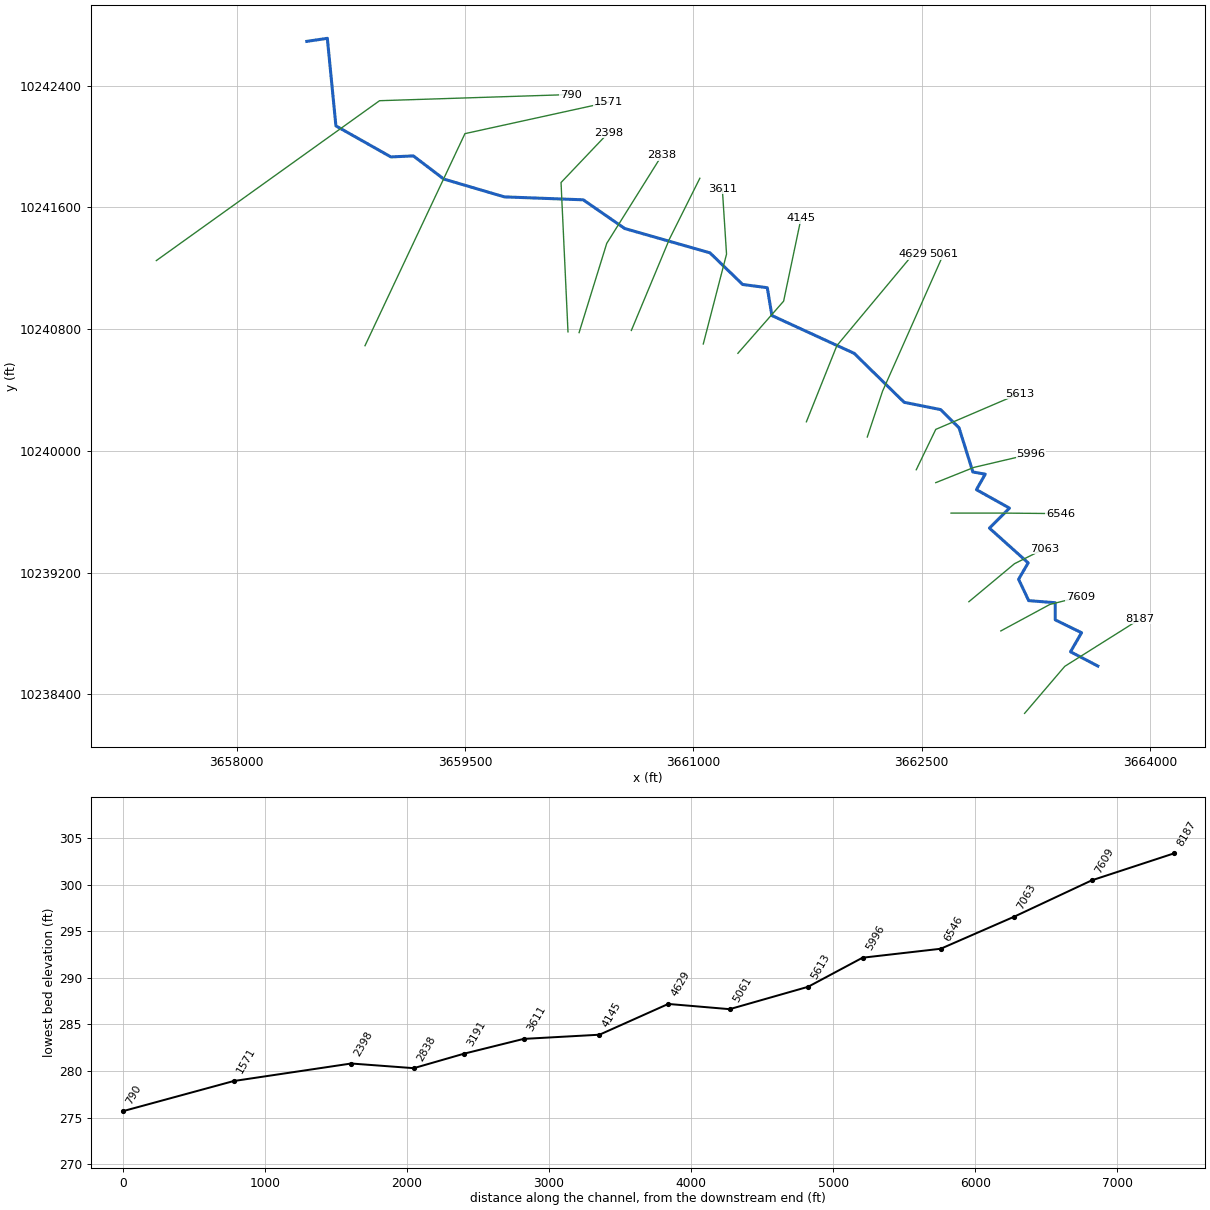
--- UNT005 IN GIBB.prj (project) ---

Proj Title=UNT005 IN GIBB Base Level Engineering
Current Plan=p01
Default Exp/Contr=0.3,0.1
English Units
Geom File=g01
Flow File=f01
Plan File=p01
Y Axis Title=Elevation
X Axis Title(PF)=Main Channel Distance
X Axis Title(XS)=Station
BEGIN DESCRIPTION:
UNT005 IN GIBB
END DESCRIPTION:
DSS Export Rating Curves= 0
DSS Export Rating Curve Sorted= 0
DSS Export Volume Flow Curves= 0
DXF OffsetX= 0
DXF OffsetY= 0
DXF ScaleX= 1
DXF ScaleY= 10

--- UNT005 IN GIBB.p01 (plan) ---

Plan Title=Multiple Run
Short Identifier=Multiple
Geom File=g01
Flow File=f01
Subcritical Flow
K Sum by GR= 0
Std Step Tol= 0.01
Critical Tol= 0.01
Num of Std Step Trials= 20
Max Error Tol= 0.3
Flow Tol Ratio= 0.001
Split Flow NTrial= 30
Split Flow Tol= 0.02
Split Flow Ratio= 0.02
Log Output Level= 0
Friction Slope Method= 1
Unsteady Friction Slope Method= 2
Unsteady Bridges Friction Slope Method= 1
Parabolic Critical Depth
Global Vel Dist=  1 , 1 , 1
Global Log Level= 0
CheckData=True
Encroach Param= -1, 0, 0, 0
BEGIN DESCRIPTION:
Multiple Run
END DESCRIPTION:

--- UNT005 IN GIBB.f01 (steady flow) ---

Flow Title=Multiple
Program Version=4.10
Number of Profiles= 7
Profile Names=10-year,25-year,50-year,1pct_min,100-year,1pct_plu,500-year
River Rch & RM=UNT005 IN GIBB,Reach-1         ,8187
     245     308     357     304     411     555     542
River Rch & RM=UNT005 IN GIBB,Reach-1         ,5061
     958    1310    1600    1431    1935    2617    2828
Boundary for River Rch & Prof#=UNT005 IN GIBB,Reach-1         , 1
Up Type= 0
Dn Type= 3
Dn Slope=0.0065
Boundary for River Rch & Prof#=UNT005 IN GIBB,Reach-1         , 2
Up Type= 0
Dn Type= 3
Dn Slope=0.0065
Boundary for River Rch & Prof#=UNT005 IN GIBB,Reach-1         , 3
Up Type= 0
Dn Type= 3
Dn Slope=0.0065
Boundary for River Rch & Prof#=UNT005 IN GIBB,Reach-1         , 4
Up Type= 0
Dn Type= 3
Dn Slope=0.0065
Boundary for River Rch & Prof#=UNT005 IN GIBB,Reach-1         , 5
Up Type= 0
Dn Type= 3
Dn Slope=0.0065
Boundary for River Rch & Prof#=UNT005 IN GIBB,Reach-1         , 6
Up Type= 0
Dn Type= 3
Dn Slope=0.0065
Boundary for River Rch & Prof#=UNT005 IN GIBB,Reach-1         , 7
Up Type= 0
Dn Type= 3
Dn Slope=0.0065
DSS Import GetInterval= 0
DSS Import GetPeak= 0
DSS Import FillOption= 0

--- UNT005 IN GIBB.g01 (geometry) ---

Geom Title=Existing Conditions
Program Version=4.10

River Reach=UNT005 IN GIBB  ,Reach-1
Reach XY= 30
      3663657.11     10238586.64       3663477.6     10238680.55
      3663549.81     10238805.68      3663377.13     10238890.23
      3663376.97     10239002.87      3663202.67     10239016.51
      3663136.34     10239156.84      3663199.12     10239264.69
      3662944.82     10239492.94      3663076.33     10239624.43
      3662859.35     10239745.51      3662917.17     10239847.28
      3662835.92     10239861.86      3662744.95     10240152.14
      3662624.11     10240271.59      3662384.45     10240319.52
      3662056.01     10240641.16      3661515.39     10240889.59
      3661485.18     10241072.41       3661323.2     10241093.76
      3661108.62     10241301.57      3660549.24     10241460.95
       3660275.8     10241650.01      3659757.57     10241669.28
      3659359.66     10241786.47      3659159.66     10241938.55
      3659012.26     10241931.78      3658650.91     10242135.64
      3658594.55     10242710.95      3658459.94     10242691.11

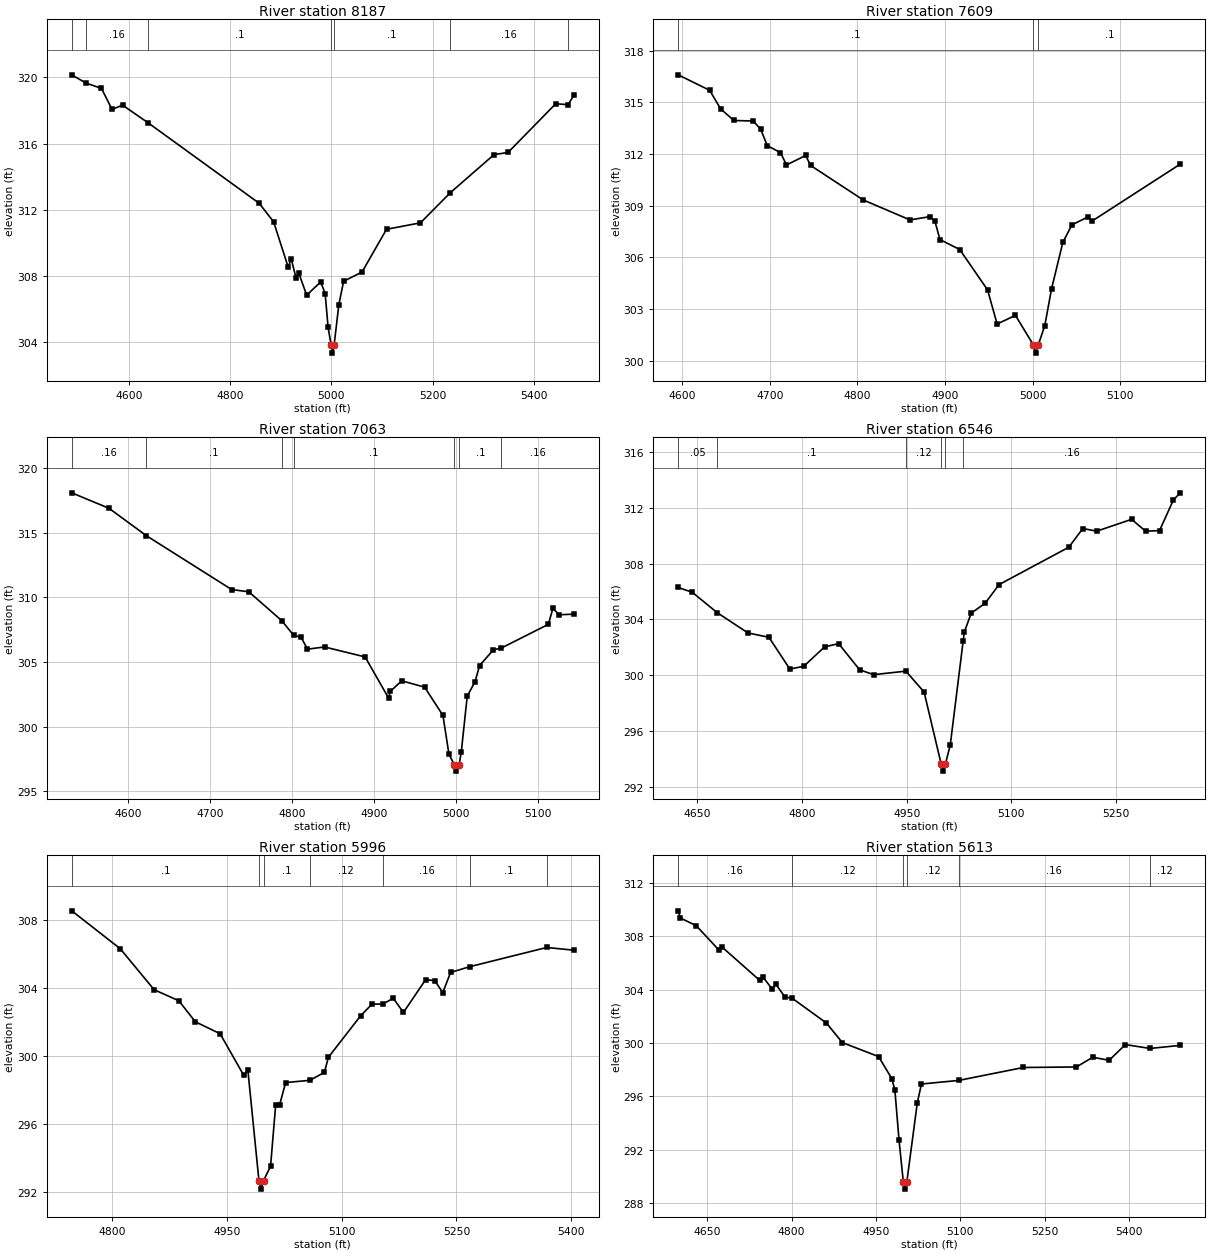
Type RM Length L Ch R = 1 ,8187    ,578,578,578
BEGIN DESCRIPTION:
UNT005 IN GIBB 16.0
END DESCRIPTION:
XS GIS Cut Line= 3
      3663175.76     10238275.77      3663439.62     10238584.76
      3663935.64     10238896.94
#Sta/Elev= 30
  4486.8  320.15  4514.3  319.66  4545.5  319.33  4566.4  318.06  4587.2  318.32
  4638.2  317.24  4857.3  312.39  4885.8  311.27  4914.6  308.53  4920.5  309.04
  4929.9   307.9  4935.8  308.15  4951.1  306.84  4978.8  307.64  4987.6  306.94
  4993.5  304.89  4999.4  303.84  5002.1  303.34  5005.4  303.84  5014.7  306.27
  5024.1  307.68  5060.6  308.24  5108.9  310.82    5176  311.21  5234.7  313.02
  5321.4  315.33  5349.1  315.46  5443.3   318.4  5467.8  318.35  5479.2  318.91
#Mann= 7 ,-1 , 0
  4486.8      .1       0  4514.3     .16       0  4638.2      .1       0
  4999.4     .07       0  5005.4      .1       0  5234.7     .16       0
  5467.8      .1       0
Bank Sta=4999.4,5005.4
XS Rating Curve= 0 ,0
Exp/Cntr=0.3,0.1

Type RM Length L Ch R = 1 ,7609    ,546,546,546
BEGIN DESCRIPTION:
UNT005 IN GIBB 14.0
END DESCRIPTION:
XS GIS Cut Line= 3
       3663019.5     10238817.41      3663342.11     10238991.64
       3663542.1     10239041.64
#Sta/Elev= 30
  4595.6   316.6  4631.5   315.7    4644  314.62  4659.1  313.95    4681  313.92
  4689.5  313.46  4697.2  312.49  4712.2  312.09  4719.1  311.37    4741  311.92
  4746.6  311.34  4806.6  309.34    4860  308.18  4882.7  308.37  4888.5  308.09
  4894.2  307.04  4916.8  306.46  4948.5  304.12  4959.4  302.14  4980.3  302.64
  5000.5  300.95  5003.2  300.45  5006.5  300.95  5013.8  302.05  5021.5  304.18
  5034.4  306.88  5044.7  307.89  5062.8  308.35  5067.9  308.12  5168.4  311.42
#Mann= 3 ,-1 , 0
  4595.6      .1       0  5000.5     .07       0  5006.5      .1       0
Bank Sta=5000.5,5006.5
XS Rating Curve= 0 ,0
Exp/Cntr=0.3,0.1

Type RM Length L Ch R = 1 ,7063    ,517,517,517
BEGIN DESCRIPTION:
UNT005 IN GIBB 13.0
END DESCRIPTION:
XS GIS Cut Line= 3
      3662809.78     10239009.51      3663109.77      10239259.5
      3663308.43     10239358.83
#Sta/Elev= 30
  4531.5  318.09    4577  316.89  4622.6  314.77  4726.7   310.6  4747.5  310.43
  4787.8  308.19  4802.2  307.06  4811.3  306.91  4819.1  305.99  4839.9  306.16
  4889.4  305.39    4918  302.21  4920.3  302.73  4934.1  303.54    4962  303.05
  4984.4  300.86  4991.7  297.86  4998.2  297.05  5000.9  296.55  5004.2  297.05
  5006.8  298.06    5014  302.35  5023.5  303.47  5029.1  304.72  5045.9  305.94
  5055.7  306.08    5113  307.91  5118.6  309.16  5125.9  308.65  5144.1   308.7
#Mann= 7 ,-1 , 0
  4531.5     .16       0  4622.6      .1       0  4787.8     .05       0
  4802.2      .1       0  4998.2     .07       0  5004.2      .1       0
  5055.7     .16       0
Bank Sta=4998.2,5004.2
XS Rating Curve= 0 ,0
Exp/Cntr=0.3,0.1

Type RM Length L Ch R = 1 ,6546    ,550,550,550
BEGIN DESCRIPTION:
UNT005 IN GIBB 12.0
END DESCRIPTION:
XS GIS Cut Line= 3
      3662692.07     10239591.64      3663042.11     10239591.64
      3663411.86     10239588.23
#Sta/Elev= 30
  4622.5  306.28  4642.5  305.94  4678.5  304.47  4722.5  303.02  4752.5  302.71
  4782.5  300.43  4802.5  300.63  4832.5  302.03  4852.5  302.25  4882.5  300.38
  4902.5  300.03  4948.9  300.28    4975  298.78  4999.5  293.61  5002.3  293.11
  5005.5  293.61  5012.5  294.99    5031  302.45  5032.5  303.06  5042.5  304.44
  5062.5  305.15  5082.5  306.49  5182.5  309.17  5202.5  310.51  5222.5  310.32
  5272.5  311.17  5292.5  310.32  5312.5  310.36  5332.5  312.57  5342.3  313.07
#Mann= 6 ,-1 , 0
  4622.5     .05       0  4678.5      .1       0  4948.9     .12       0
  4999.5     .07       0  5005.5     .12       0    5031     .16       0
Bank Sta=4999.5,5005.5
XS Rating Curve= 0 ,0
Exp/Cntr=0.3,0.1

Type RM Length L Ch R = 1 ,5996    ,383,383,383
BEGIN DESCRIPTION:
UNT005 IN GIBB 11.0
END DESCRIPTION:
XS GIS Cut Line= 3
      3662592.08     10239791.63      3662842.11     10239891.64
      3663218.97     10239980.14
#Sta/Elev= 30
  4747.1  308.55  4810.4  306.32  4854.8   303.9  4887.1  303.25  4908.7  302.01
    4941  301.31    4972  298.85  4977.3  299.17  4991.8  292.65  4994.6  292.15
  4997.8  292.65    5007   293.5  5013.7  297.13  5018.9  297.13  5026.7  298.43
  5058.2  298.56  5077.4  299.03  5082.6  299.92    5125  302.38  5139.6  303.05
    5154  303.06  5167.4   303.4  5180.7  302.56  5209.8   304.5  5221.8  304.43
  5232.1  303.73  5242.4  304.92  5267.5  305.26    5368  306.39  5403.5  306.23
#Mann= 7 ,-1 , 0
  4747.1      .1       0  4991.8     .07       0  4997.8      .1       0
  5058.2     .12       0    5154     .16       0  5267.5      .1       0
    5368     .05       0
Bank Sta=4991.8,4997.8
XS Rating Curve= 0 ,0
Exp/Cntr=0.3,0.1

Type RM Length L Ch R = 1 ,5613    ,552,552,552
BEGIN DESCRIPTION:
UNT005 IN GIBB 10.0
END DESCRIPTION:
XS GIS Cut Line= 3
      3662463.93     10239876.43      3662592.11     10240141.64
      3663141.91      10240377.2
#Sta/Elev= 30
  4598.6  309.92  4602.4  309.38  4630.5  308.81  4670.2  307.01  4675.7  307.23
  4743.5   304.7  4749.1  304.96  4766.1  304.02  4771.6  304.44  4788.7  303.43
  4800.5  303.38    4862   301.5  4890.4  300.03  4954.8  298.98  4978.4  297.32
  4983.8  296.47  4991.1  292.74  4998.9  289.53  5001.7  289.03  5004.9  289.53
  5023.7  295.52    5031  296.92  5097.3  297.19  5212.3  298.16  5306.6   298.2
  5335.6  298.93  5364.7   298.7  5393.7  299.88  5437.3  299.59  5491.3  299.82
#Mann= 6 ,-1 , 0
  4598.6     .16       0  4800.5     .12       0  4998.9     .07       0
  5004.9     .12       0  5097.3     .16       0  5437.3     .12       0
Bank Sta=4998.9,5004.9
XS Rating Curve= 0 ,0
Exp/Cntr=0.3,0.1

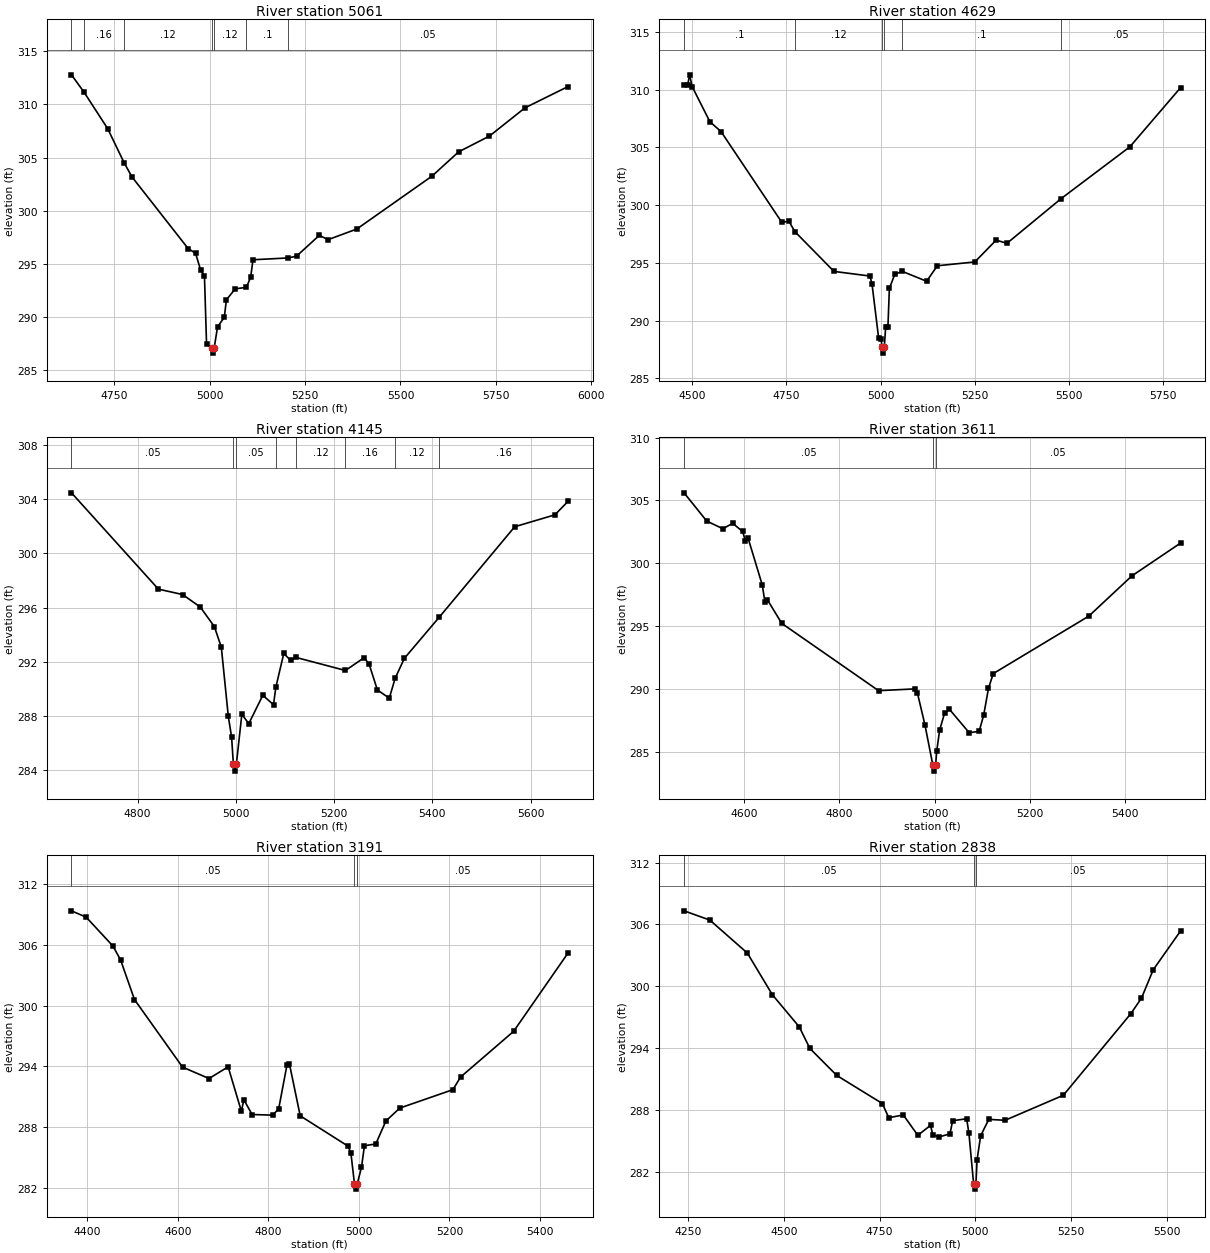
Type RM Length L Ch R = 1 ,5061    ,432,432,432
BEGIN DESCRIPTION:
UNT005 IN GIBB 9.0
END DESCRIPTION:
XS GIS Cut Line= 3
       3662142.1     10240091.61      3662242.11     10240391.64
      3662642.09      10241291.6
#Sta/Elev= 30
    4638  312.77  4670.9  311.14  4732.9  307.71  4775.8  304.52  4796.1   303.2
  4943.7  296.45  4963.1  296.01  4976.1  294.47  4986.4  293.87  4991.9  287.46
    5006  287.13  5008.7  286.63    5012  287.13  5020.6  289.09  5038.4     290
  5043.9  291.64  5067.1  292.67  5096.4  292.81  5107.5  293.77  5113.6   295.4
  5205.8  295.57  5227.8  295.74  5287.3  297.69  5310.6  297.29  5385.8  298.29
  5582.8  303.26  5652.6  305.54  5733.3  307.02  5826.3  309.67  5939.1  311.67
#Mann= 7 ,-1 , 0
    4638     .05       0  4670.9     .16       0  4775.8     .12       0
    5006     .07       0    5012     .12       0  5096.4      .1       0
  5205.8     .05       0
Bank Sta=5006,5012
XS Rating Curve= 0 ,0
Exp/Cntr=0.3,0.1

Type RM Length L Ch R = 1 ,4629    ,484,484,484
BEGIN DESCRIPTION:
UNT005 IN GIBB 8.0
END DESCRIPTION:
XS GIS Cut Line= 3
       3661742.1     10240191.63      3661942.11     10240691.64
      3662442.14     10241291.68
#Sta/Elev= 30
  4477.9  310.43  4487.3  310.36  4492.7  311.27  4499.5  310.25  4546.6  307.21
  4576.2  306.36  4737.7  298.51  4756.6   298.6  4772.5   297.7  4876.4  294.26
    4972  293.86  4977.4  293.18  4994.9  288.53  5001.6  288.41    5004  287.69
  5006.8  287.19    5010  287.69  5013.7  289.43  5019.7  289.43  5023.6  292.79
  5037.9     294  5057.4  294.27  5122.5  293.41  5151.2  294.75  5250.7  295.08
  5307.4  296.97    5336  296.69  5480.1  300.56  5662.7  305.04  5797.5  310.16
#Mann= 6 ,-1 , 0
  4477.9      .1       0  4772.5     .12       0    5004     .07       0
    5010     .12       0  5057.4      .1       0  5480.1     .05       0
Bank Sta=5004,5010
XS Rating Curve= 0 ,0
Exp/Cntr=0.3,0.1

Type RM Length L Ch R = 1 ,4145    ,534,534,534
BEGIN DESCRIPTION:
UNT005 IN GIBB 7.0
END DESCRIPTION:
XS GIS Cut Line= 3
      3661292.08     10240641.62       3661592.4     10240984.06
      3661706.71      10241527.9
#Sta/Elev= 30
  4665.2  304.49  4842.2  297.36  4891.6  296.96  4927.6  296.03  4956.1  294.59
  4970.3  293.07  4984.5  287.95  4991.2  286.43  4994.9  284.39  4997.6  283.89
  5000.9  284.39  5012.1  288.09  5026.3  287.41  5054.8   289.5  5076.6  288.81
  5081.3  290.09  5097.5   292.6  5111.7  292.08  5121.9  292.31  5223.1  291.34
  5261.3  292.29  5271.5  291.79  5288.1   289.9  5312.4  289.29  5324.3  290.76
  5343.1  292.24  5414.5   295.3  5567.8  301.98  5649.6  302.86  5676.4  303.86
#Mann= 8 ,-1 , 0
  4665.2     .05       0  4994.9    .035       0  5000.9     .05       0
  5081.3     .16       0  5121.9     .12       0  5223.1     .16       0
  5324.3     .12       0  5414.5     .16       0
Bank Sta=4994.9,5000.9
XS Rating Curve= 0 ,0
Exp/Cntr=0.3,0.1

Type RM Length L Ch R = 1 ,3611    ,420,420,420
BEGIN DESCRIPTION:
UNT005 IN GIBB 6.0
END DESCRIPTION:
XS GIS Cut Line= 3
      3661064.62     10240702.79       3661217.4     10241293.09
      3661189.62     10241723.65
#Sta/Elev= 30
  4474.5  305.61  4522.1  303.36  4555.9  302.75  4576.6  303.18  4597.3  302.53
  4603.3  301.77  4608.5  302.04  4638.6  298.26  4643.9  296.95  4649.1   297.1
  4679.4  295.21  4882.4  289.85  4958.5  289.99  4963.7  289.69  4979.5  287.15
  4996.1  283.94  4998.9  283.44  5002.1  283.94  5004.3  285.03  5010.4   286.7
  5020.8  288.06  5031.1  288.36  5072.4   286.5  5093.3  286.61  5102.8   287.9
  5112.9  290.04  5122.9  291.21  5323.3  295.79  5413.5  298.99  5515.7  301.61
#Mann= 3 ,-1 , 0
  4474.5     .05       0  4996.1    .035       0  5002.1     .05       0
Bank Sta=4996.1,5002.1
XS Rating Curve= 0 ,0
Exp/Cntr=0.3,0.1

Type RM Length L Ch R = 1 ,3191    ,353,353,353
BEGIN DESCRIPTION:
UNT005 IN GIBB 5.0
END DESCRIPTION:
XS GIS Cut Line= 3
      3660592.11     10240791.65      3660842.11     10241391.64
       3661042.1     10241791.64
#Sta/Elev= 30
  4364.8  309.38  4397.3  308.75  4456.3   305.9  4473.1  304.54    4504   300.6
  4610.2  293.92  4668.7  292.79  4710.9  293.95  4740.2  289.55  4745.6  290.69
    4764  289.23    4809  289.17  4822.5  289.77  4840.9  294.12  4846.3  294.25
  4870.2   289.1  4976.3  286.09  4982.3  285.38  4990.1  282.35  4992.9  281.85
  4996.1  282.35  5005.6  284.02  5012.1  286.14  5037.2  286.32  5059.5  288.59
  5090.3  289.87  5207.7  291.69  5224.4  292.93  5341.8  297.46    5462  305.21
#Mann= 3 ,-1 , 0
  4364.8     .05       0  4990.1     .03       0  4996.1     .05       0
Bank Sta=4990.1,4996.1
XS Rating Curve= 0 ,0
Exp/Cntr=0.3,0.1

Type RM Length L Ch R = 1 ,2838    ,440,440,440
BEGIN DESCRIPTION:
UNT005 IN GIBB 4.0
END DESCRIPTION:
XS GIS Cut Line= 3
      3660248.66      10240777.5      3660430.24     10241363.62
      3660792.13     10241941.68
#Sta/Elev= 30
  4239.8  307.31  4307.2  306.41    4405  303.21  4470.2  299.17  4540.6  296.04
    4568  293.96  4638.4  291.33  4757.1  288.61    4774  287.23  4811.9   287.5
  4849.8  285.52  4882.9  286.49  4888.8  285.59  4904.1  285.36  4933.7  285.66
  4940.6  286.94  4977.2  287.13  4983.1  285.73  4995.4   280.8  4998.2   280.3
  5001.4   280.8  5004.4  283.15  5013.7  285.47  5034.9  287.07  5077.4  286.98
  5229.5  289.41  5405.6  297.33  5433.4  298.84    5464  301.59  5535.4  305.36
#Mann= 3 ,-1 , 0
  4239.8     .05       0  4995.4     .03       0  5001.4     .05       0
Bank Sta=4995.4,5001.4
XS Rating Curve= 0 ,0
Exp/Cntr=0.3,0.1

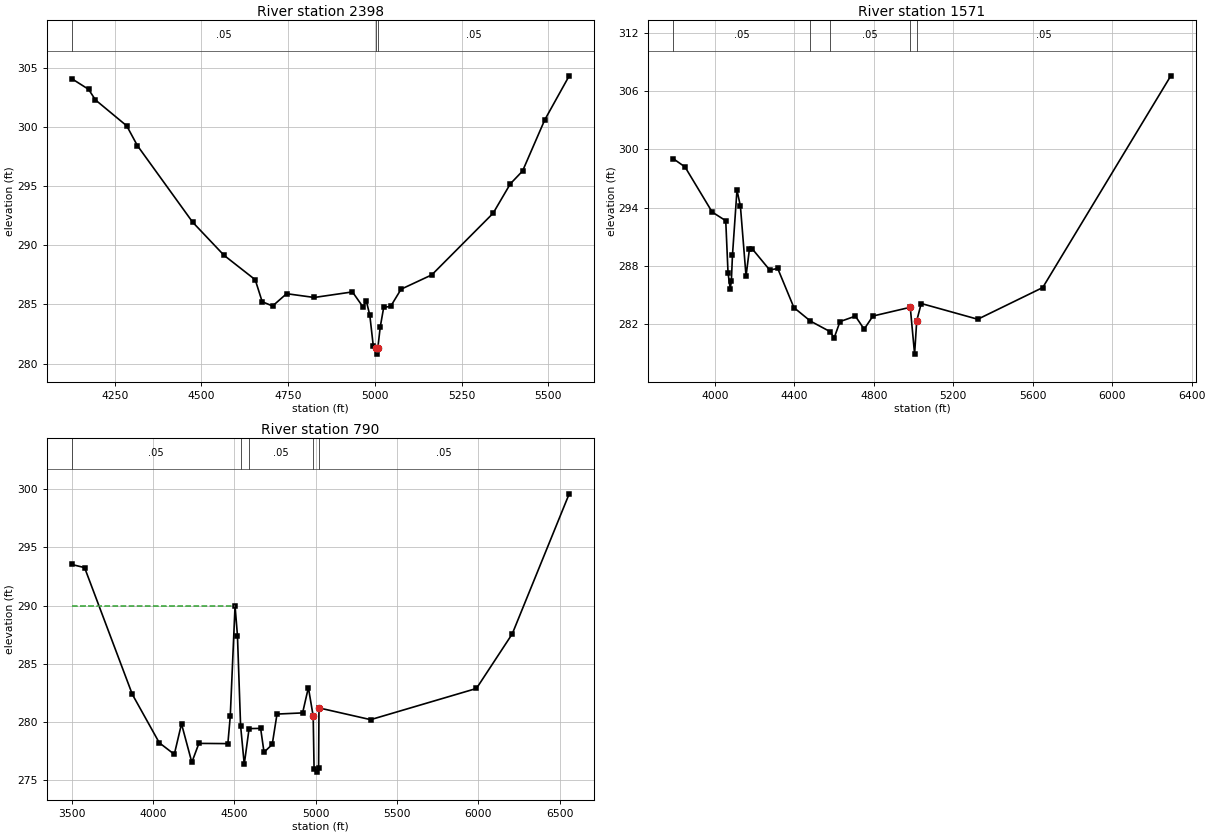
Type RM Length L Ch R = 1 ,2398    ,827,827,827
BEGIN DESCRIPTION:
UNT005 IN GIBB 3.0
END DESCRIPTION:
XS GIS Cut Line= 3
      3660175.73     10240782.68      3660130.06     10241763.47
       3660442.1     10242091.64
#Sta/Elev= 30
  4125.4   304.1  4174.4  303.19  4194.4  302.29  4284.5   300.1  4315.2  298.43
  4474.7  291.95  4564.8  289.16  4654.9  287.09    4675  285.23    4705  284.87
  4745.4  285.91  4825.1  285.59  4935.2  286.06  4965.3   284.8  4975.3  285.28
  4985.3  284.08  4995.3  281.48  5002.3   281.3  5005.1   280.8  5008.3   281.3
  5015.3  283.09  5025.3  284.75  5045.4  284.84  5075.4  286.29  5163.9   287.5
  5340.7  292.71  5390.4   295.2  5425.6  296.28  5489.5   300.6  5560.1  304.33
#Mann= 3 ,-1 , 0
  4125.4     .05       0  5002.3     .03       0  5008.3     .05       0
Bank Sta=5002.3,5008.3
XS Rating Curve= 0 ,0
Exp/Cntr=0.3,0.1

Type RM Length L Ch R = 1 ,1571    ,781,781,781
BEGIN DESCRIPTION:
UNT005 IN GIBB 2.0
END DESCRIPTION:
XS GIS Cut Line= 3
      3658842.09      10240691.6      3659498.65     10242084.76
      3660442.12     10242291.65
#Sta/Elev= 30
    3789  299.04  3848.8  298.18  3985.5  293.54  4053.8  292.65  4065.4  287.26
  4076.5  285.63  4082.1  286.45  4087.7  289.11  4110.4   295.8  4127.7  294.14
    4156  286.95  4173.3  289.76    4187  289.76  4275.5  287.57  4315.5  287.74
  4397.1  283.71  4480.3  282.32  4578.8  281.24  4599.9   280.6  4629.2  282.27
  4706.6  282.83  4750.8  281.49    4795  282.84    4983  283.74  5004.8  278.92
  5015.6  282.36  5038.2  284.13  5322.8  282.51    5650  285.77    6295  307.56
#Mann= 5 ,-1 , 0
    3789     .05       0  4480.3     .12       0  4578.8     .05       0
    4983     .03       0  5015.6     .05       0
Bank Sta=4983,5015.6
XS Rating Curve= 0 ,0
Exp/Cntr=0.3,0.1

Type RM Length L Ch R = 1 ,790     ,0,0,0
BEGIN DESCRIPTION:
UNT005 IN GIBB 1.0
END DESCRIPTION:
XS GIS Cut Line= 3
        3657471.     10241250.66      3658937.57     10242301.17
      3660192.12     10242341.64
#Sta/Elev= 30
  3499.9  293.53    3580  293.26  3873.6  282.36  4039.4   278.2  4131.6  277.21
  4175.8  279.83  4239.3  276.52  4282.7  278.15  4460.8  278.13  4475.5  280.47
    4505  289.97  4519.7  287.42    4539  279.68  4561.5  276.35  4591.2  279.42
  4662.2  279.44  4683.1  277.39  4733.5  278.06  4762.9  280.67  4920.2  280.77
  4955.8  282.95  4985.3  280.49 4990.71  275.99  5005.9  275.68 5018.58  276.07
  5020.9   281.2  5338.5  280.19  5988.8  282.87  6208.9  287.56  6559.1   299.6
#Mann= 5 ,-1 , 0
  3499.9     .05       0    4539     .03       0  4591.2     .05       0
  4985.3     .03       0  5020.9     .05       0
#XS Ineff= 2 , 0
         4505.24  289.95
Permanent Ineff=
       F       F
Bank Sta=4985.3,5020.9
XS Rating Curve= 0 ,0
Exp/Cntr=0.3,0.1

Chan Stop Cuts=-1
Use User Specified Reach Order=0
Composite Channel Slope=5