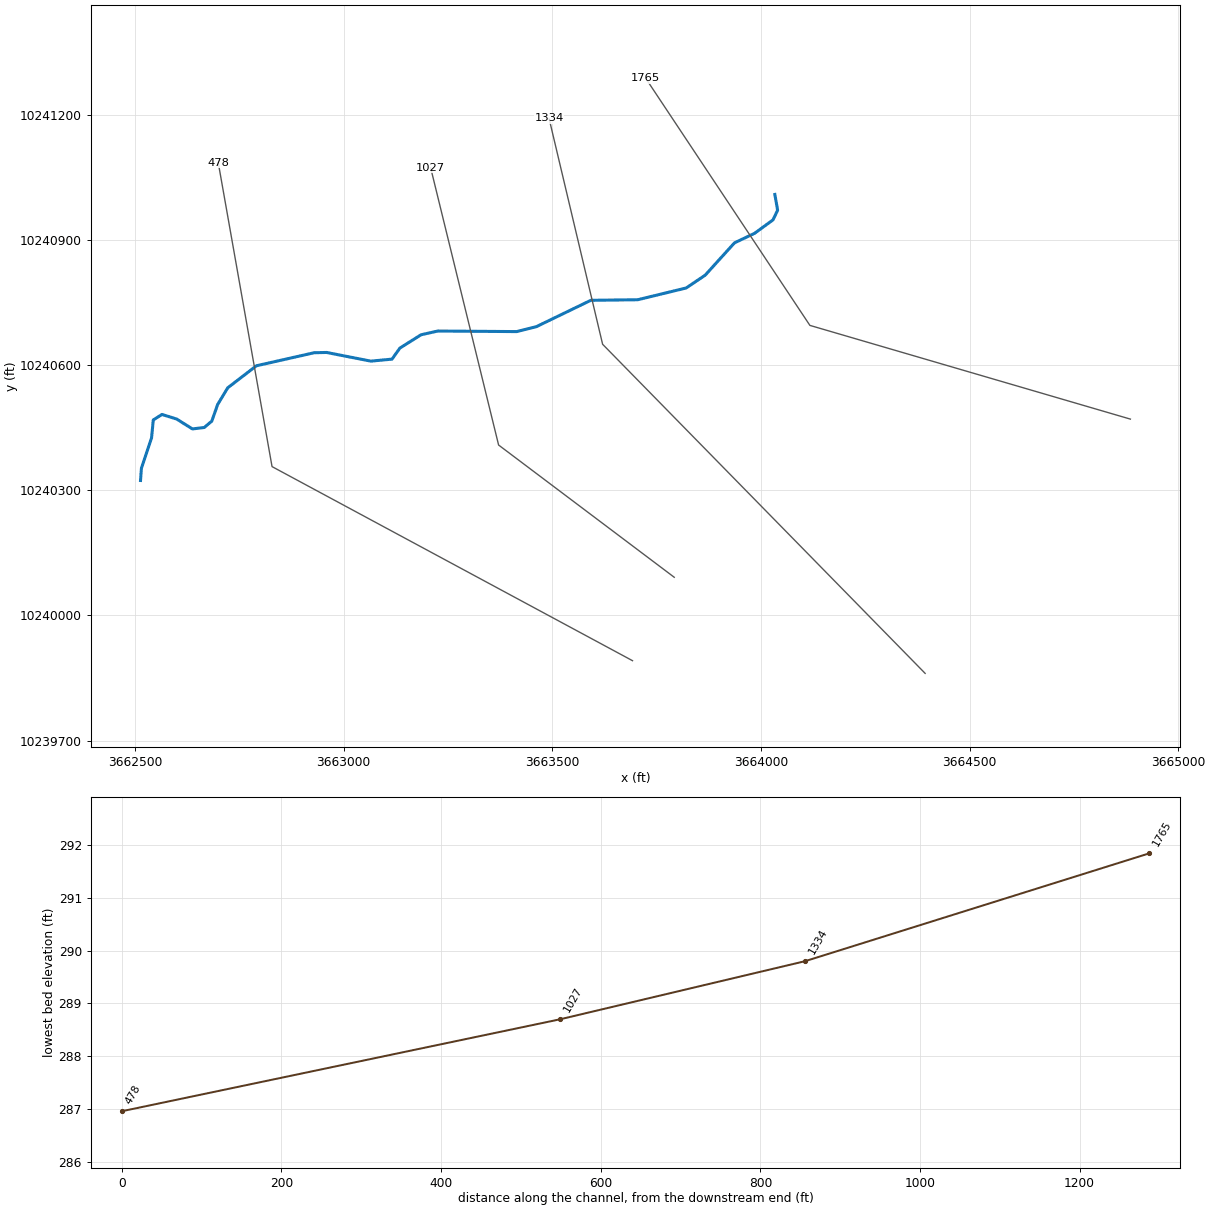
--- UNT006 IN GIBB.prj (project) ---

Proj Title=UNT006 IN GIBB Base Level Engineering
Current Plan=p01
Default Exp/Contr=0.3,0.1
English Units
Geom File=g01
Flow File=f01
Plan File=p01
Y Axis Title=Elevation
X Axis Title(PF)=Main Channel Distance
X Axis Title(XS)=Station
BEGIN DESCRIPTION:
UNT006 IN GIBB
END DESCRIPTION:
DSS Export Rating Curves= 0
DSS Export Rating Curve Sorted= 0
DSS Export Volume Flow Curves= 0
DXF OffsetX= 0
DXF OffsetY= 0
DXF ScaleX= 1
DXF ScaleY= 10

--- UNT006 IN GIBB.p01 (plan) ---

Plan Title=Multiple Run
Short Identifier=Multiple
Geom File=g01
Flow File=f01
Subcritical Flow
K Sum by GR= 0
Std Step Tol= 0.01
Critical Tol= 0.01
Num of Std Step Trials= 20
Max Error Tol= 0.3
Flow Tol Ratio= 0.001
Split Flow NTrial= 30
Split Flow Tol= 0.02
Split Flow Ratio= 0.02
Log Output Level= 0
Friction Slope Method= 1
Unsteady Friction Slope Method= 2
Unsteady Bridges Friction Slope Method= 1
Parabolic Critical Depth
Global Vel Dist=  1 , 1 , 1
Global Log Level= 0
CheckData=True
Encroach Param= -1, 0, 0, 0
BEGIN DESCRIPTION:
Multiple Run
END DESCRIPTION:

--- UNT006 IN GIBB.f01 (steady flow) ---

Flow Title=Multiple
Number of Profiles=7
Profile Names=10-year,25-year,50-year,1pct_min,100-year,1pct_plu,500-year
River Rch & RM= UNT006 IN GIBB,Reach-1,1765
     786    1066    1297    1155    1562    2113    2266
Boundary for River Rch & Prof#=UNT006 IN GIBB,Reach-1,1
Up Type=0
Dn Type=3
Dn Slope=0.005
Boundary for River Rch & Prof#=UNT006 IN GIBB,Reach-1,2
Up Type=0
Dn Type=3
Dn Slope=0.005
Boundary for River Rch & Prof#=UNT006 IN GIBB,Reach-1,3
Up Type=0
Dn Type=3
Dn Slope=0.005
Boundary for River Rch & Prof#=UNT006 IN GIBB,Reach-1,4
Up Type=0
Dn Type=3
Dn Slope=0.005
Boundary for River Rch & Prof#=UNT006 IN GIBB,Reach-1,5
Up Type=0
Dn Type=3
Dn Slope=0.005
Boundary for River Rch & Prof#=UNT006 IN GIBB,Reach-1,6
Up Type=0
Dn Type=3
Dn Slope=0.005
Boundary for River Rch & Prof#=UNT006 IN GIBB,Reach-1,7
Up Type=0
Dn Type=3
Dn Slope=0.005

--- UNT006 IN GIBB.g01 (geometry) ---

Geom Title=Existing Conditions
Program Version=4.10

River Reach=UNT006 IN GIBB  ,Reach-1
Reach XY= 30
      3664033.29     10241009.46      3664039.85     10240971.39
       3664028.8     10240948.44        3663985.     10240916.45
       3663936.5     10240893.34      3663866.12     10240815.72
      3663820.65     10240785.17      3663704.67       10240757.
      3663592.17     10240755.61      3663461.61     10240692.42
      3663414.39     10240680.61       3663225.5       10240682.
      3663185.22     10240672.97      3663134.53     10240641.03
      3663115.78     10240614.64      3663065.08     10240609.78
      3662958.83     10240630.61      3662928.97     10240629.92
      3662790.78     10240598.67      3662722.03     10240545.89
      3662697.72     10240505.61      3662683.83     10240466.03
      3662665.78     10240450.75      3662637.31     10240447.28
      3662599.81     10240470.89      3662564.39       10240482.
      3662543.56     10240468.81      3662539.39     10240425.75
      3662515.08     10240352.84        3662513.     10240323.67

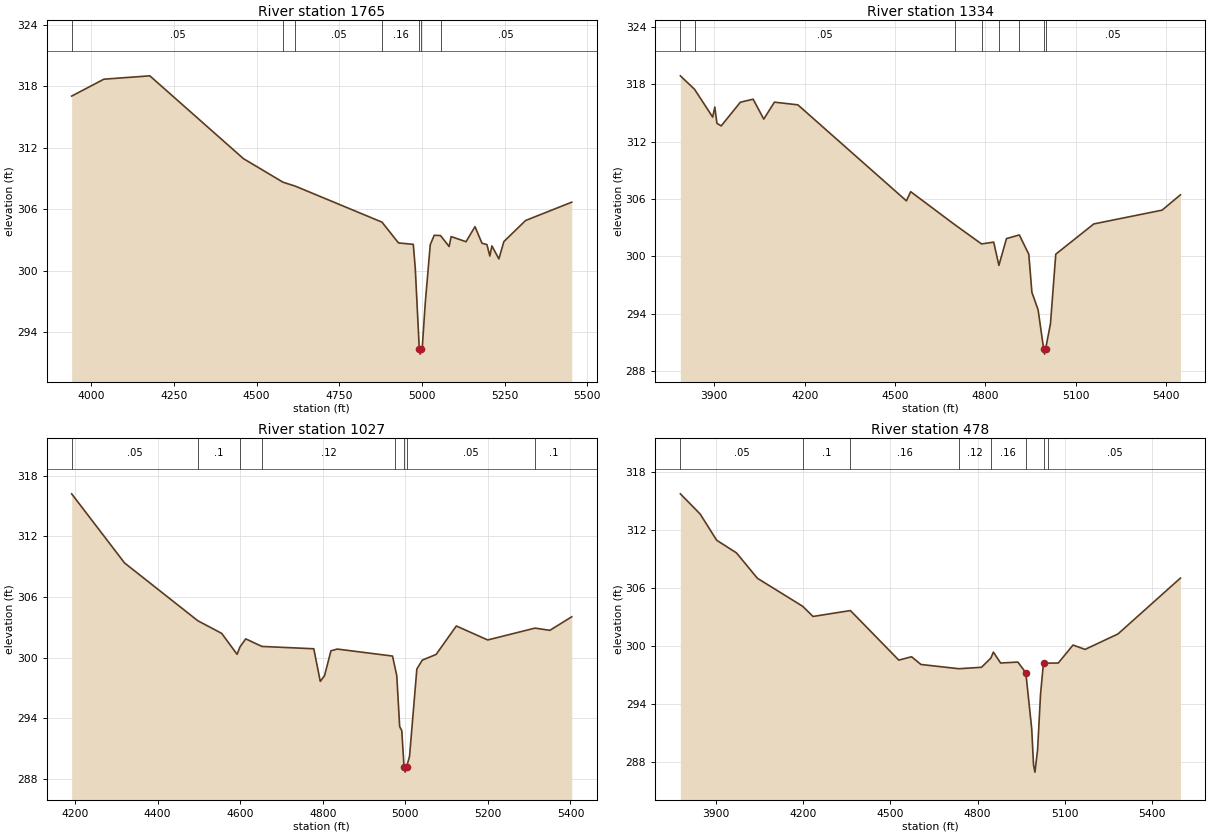
Type RM Length L Ch R = 1 ,1765    ,431,431,431
BEGIN DESCRIPTION:
UNT006 IN GIBB 4.0
END DESCRIPTION:
XS GIS Cut Line= 3
      3664885.36     10240470.81      3664117.24     10240695.49
      3663723.79     10241287.82
#Sta/Elev= 30
  3941.2  317.04  4038.4  318.69  4177.4  319.02  4460.5  310.93    4580  308.63
  4617.6  308.24  4879.2  304.73    4929   302.7  4973.8  302.56  4979.8   300.2
  4991.9  292.34  4994.6  291.84  4997.9  292.34    5001  292.56  5009.9  296.82
    5025  302.52    5037  303.45    5056  303.42  5082.1  302.35  5088.1  303.32
  5133.1  302.82  5160.3  304.29  5181.3  302.67  5196.3  302.54  5205.1  301.42
  5211.4  302.41  5232.4  301.14  5247.5  302.83  5313.1  304.89  5452.6  306.68
#Mann= 7 ,-1 , 0
  3941.2     .05       0    4580     .12       0  4617.6     .05       0
  4879.2     .16       0  4991.9     .07       0  4997.9     .16       0
    5056     .05       0
Bank Sta=4991.9,4997.9
XS Rating Curve= 0 ,0
Exp/Cntr=0.3,0.1

Type RM Length L Ch R = 1 ,1334    ,307,307,307
BEGIN DESCRIPTION:
UNT006 IN GIBB 3.0
END DESCRIPTION:
XS GIS Cut Line= 3
      3664393.47      10239861.2      3663620.44     10240650.25
      3663492.11     10241191.63
#Sta/Elev= 30
  3787.1  318.87  3834.1  317.47  3894.5  314.56  3901.5  315.61  3908.6  313.91
  3922.8  313.64  3986.3  316.11  4028.8  316.43  4064.2  314.35  4099.5  316.12
  4177.4  315.84    4538  305.81  4552.1  306.77  4698.3  303.33  4787.5  301.31
  4827.9   301.5  4845.2  299.07  4870.3  301.87  4913.1  302.25  4944.5  300.23
  4954.8  296.26  4975.4  294.43    4994   290.3  4996.7   289.8    5000   290.3
  5016.5  292.98  5034.1  300.24  5160.4   303.4  5387.3  304.84  5448.1  306.44
#Mann= 8 ,-1 , 0
  3787.1      .1       0  3834.1     .05       0  4698.3      .1       0
  4787.5     .12       0  4845.2      .1       0  4913.1     .05       0
    4994     .03       0    5000     .05       0
Bank Sta=4994,5000
XS Rating Curve= 0 ,0
Exp/Cntr=0.3,0.1

Type RM Length L Ch R = 1 ,1027    ,549,549,549
BEGIN DESCRIPTION:
UNT006 IN GIBB 2.0
END DESCRIPTION:
XS GIS Cut Line= 3
      3663792.12     10240091.63      3663371.16     10240408.68
      3663208.37     10241073.13
#Sta/Elev= 30
    4192   316.2  4320.1  309.37  4497.5  303.66  4555.4  302.41  4592.6  300.34
  4599.8  301.08  4613.6  301.87  4652.8  301.12  4778.4  300.89  4794.1  297.67
  4804.4  298.23    4820  300.69  4835.3  300.86  4969.1  300.17  4975.8  298.91
  4979.4  298.23  4986.4   293.2  4991.5   292.8    4997   289.2  4999.8   288.7
    5003   289.2  5010.3  290.26    5028  298.89  5041.2  299.77  5074.7  300.33
  5123.6  303.14  5199.6  301.76  5314.2  302.93  5350.1  302.71  5403.1  304.05
#Mann= 8 ,-1 , 0
    4192     .05       0  4497.5      .1       0  4599.8     .05       0
  4652.8     .12       0  4975.8     .05       0    4997     .03       0
    5003     .05       0  5314.2      .1       0
Bank Sta=4997,5003
XS Rating Curve= 0 ,0
Exp/Cntr=0.3,0.1

Type RM Length L Ch R = 1 ,478     ,0,0,0
BEGIN DESCRIPTION:
UNT006 IN GIBB 1.0
END DESCRIPTION:
XS GIS Cut Line= 3
      3663692.13     10239891.63      3662828.17     10240356.95
      3662699.24     10241085.74
#Sta/Elev= 30
  3776.7  315.76  3844.9  313.67  3901.7  310.96  3969.8  309.65    4042  307.02
  4197.9  304.12  4233.4  303.07  4362.1  303.68  4528.7  298.55  4572.5   298.9
    4605   298.1  4735.8  297.66  4813.5  297.81  4845.7  298.77  4854.2  299.38
  4879.2  298.25  4938.4  298.35  4965.9  297.25  4986.2  291.46  4992.5   287.7
  4997.3  286.96  5006.5  289.29  5016.6  295.03  5026.8   298.3  5043.9  298.24
  5077.6  298.25  5128.4  300.11    5170  299.66  5283.2  301.26  5498.1  307.04
#Mann= 8 ,-1 , 0
  3776.7     .05       0  4197.9      .1       0  4362.1     .16       0
  4735.8     .12       0  4845.7     .16       0  4965.9     .07       0
  5026.8     .12       0  5043.9     .05       0
Bank Sta=4965.9,5026.8
XS Rating Curve= 0 ,0
Exp/Cntr=0.3,0.1

Chan Stop Cuts=-1
Use User Specified Reach Order=0
Composite Channel Slope=5