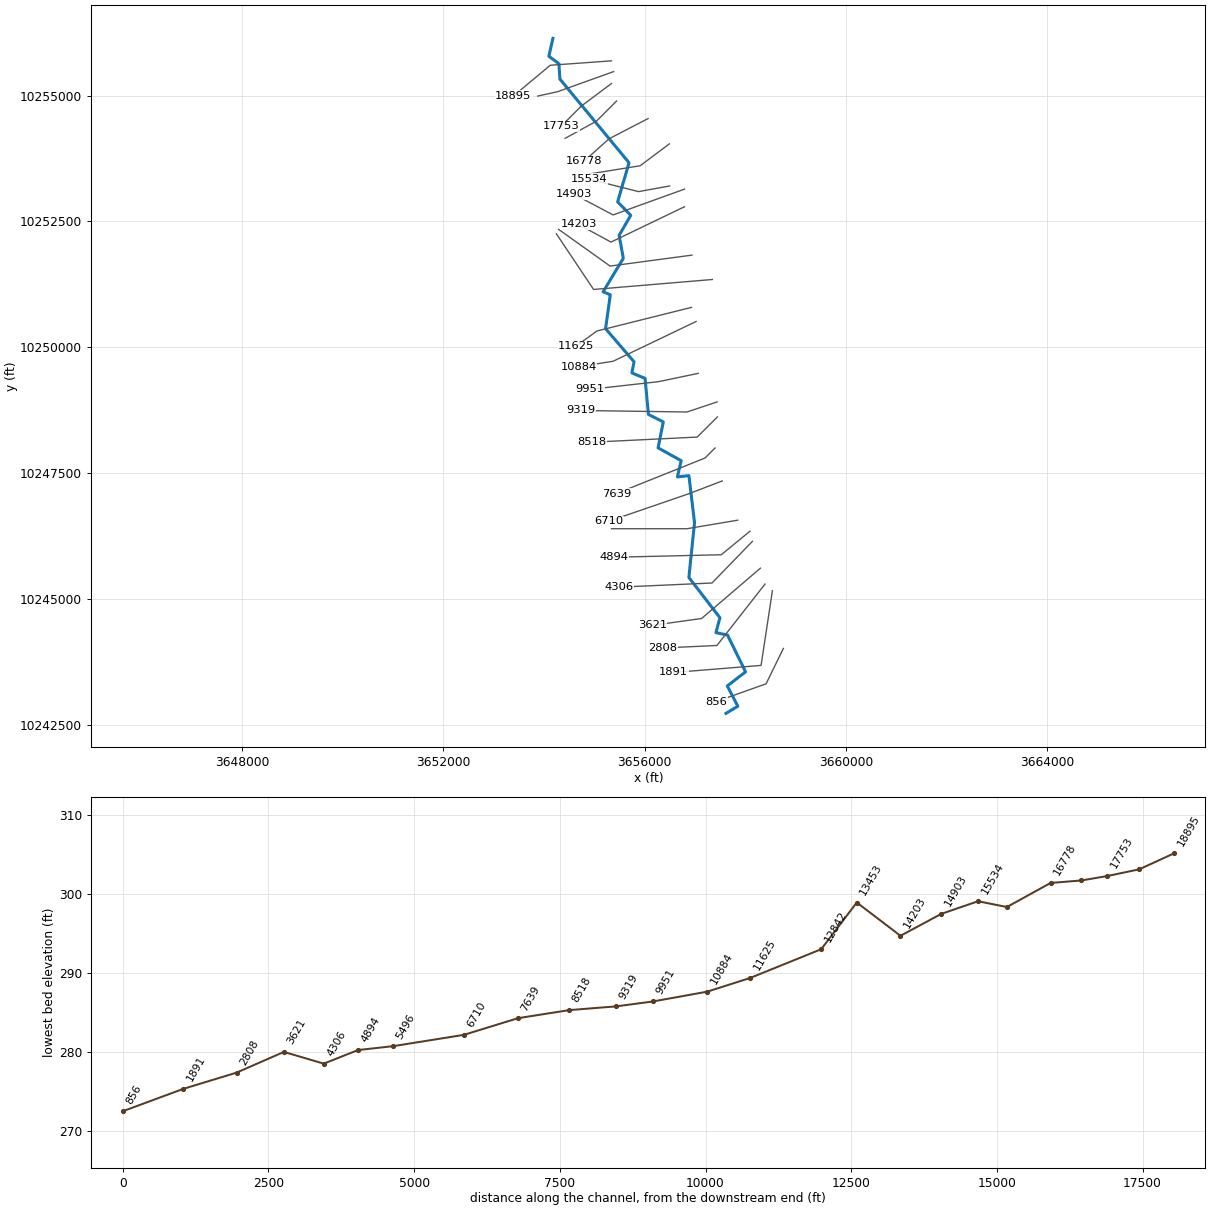
--- UNT007 IN GIBB.prj (project) ---

Proj Title=UNT007 IN GIBB Base Level Engineering
Current Plan=p01
Default Exp/Contr=0.3,0.1
English Units
Geom File=g01
Flow File=f01
Plan File=p01
Y Axis Title=Elevation
X Axis Title(PF)=Main Channel Distance
X Axis Title(XS)=Station
BEGIN DESCRIPTION:
UNT007 IN GIBB
END DESCRIPTION:
DSS Export Rating Curves= 0
DSS Export Rating Curve Sorted= 0
DSS Export Volume Flow Curves= 0
DXF OffsetX= 0
DXF OffsetY= 0
DXF ScaleX= 1
DXF ScaleY= 10

--- UNT007 IN GIBB.p01 (plan) ---

Plan Title=Multiple Run
Short Identifier=Multiple
Geom File=g01
Flow File=f01
Subcritical Flow
K Sum by GR= 0
Std Step Tol= 0.01
Critical Tol= 0.01
Num of Std Step Trials= 20
Max Error Tol= 0.3
Flow Tol Ratio= 0.001
Split Flow NTrial= 30
Split Flow Tol= 0.02
Split Flow Ratio= 0.02
Log Output Level= 0
Friction Slope Method= 1
Unsteady Friction Slope Method= 2
Unsteady Bridges Friction Slope Method= 1
Parabolic Critical Depth
Global Vel Dist=  1 , 1 , 1
Global Log Level= 0
CheckData=True
Encroach Param= -1, 0, 0, 0
BEGIN DESCRIPTION:
Multiple Run
END DESCRIPTION:

--- UNT007 IN GIBB.f01 (steady flow) ---

Flow Title=Multiple
Program Version=4.10
Number of Profiles= 7
Profile Names=10-year,25-year,50-year,1pct_min,100-year,1pct_plu,500-year
River Rch & RM=UNT007 IN GIBB,Reach-1         ,18895
    1095    1504    1843    1652    2234    3022    3288
River Rch & RM=UNT007 IN GIBB,Reach-1         ,17309
    1178    1618    1983    1777    2403    3250    3533
River Rch & RM=UNT007 IN GIBB,Reach-1         ,11625
    1616    2248    2778    2507    3390    4584    5056
River Rch & RM=UNT007 IN GIBB,Reach-1         ,6710
    1704    2369    2928    2640    3570    4828    5317
Boundary for River Rch & Prof#=UNT007 IN GIBB,Reach-1         , 1
Up Type= 0
Dn Type= 3
Dn Slope=0.005
Boundary for River Rch & Prof#=UNT007 IN GIBB,Reach-1         , 2
Up Type= 0
Dn Type= 3
Dn Slope=0.005
Boundary for River Rch & Prof#=UNT007 IN GIBB,Reach-1         , 3
Up Type= 0
Dn Type= 3
Dn Slope=0.005
Boundary for River Rch & Prof#=UNT007 IN GIBB,Reach-1         , 4
Up Type= 0
Dn Type= 3
Dn Slope=0.005
Boundary for River Rch & Prof#=UNT007 IN GIBB,Reach-1         , 5
Up Type= 0
Dn Type= 3
Dn Slope=0.005
Boundary for River Rch & Prof#=UNT007 IN GIBB,Reach-1         , 6
Up Type= 0
Dn Type= 3
Dn Slope=0.005
Boundary for River Rch & Prof#=UNT007 IN GIBB,Reach-1         , 7
Up Type= 0
Dn Type= 3
Dn Slope=0.005
DSS Import GetInterval= 0
DSS Import GetPeak= 0
DSS Import FillOption= 0

--- UNT007 IN GIBB.g01 (geometry) ---

Geom Title=Existing Conditions
Program Version=4.10

River Reach=UNT007 IN GIBB  ,Reach-1
Reach XY= 30
      3654178.83       10256139.      3654098.51     10255782.55
      3654297.93     10255634.73      3654317.51     10255329.31
      3655690.25     10253666.01      3655464.09     10252889.73
      3655724.31     10252620.87      3655493.75     10252222.96
      3655577.43      10251767.4      3655175.75     10251100.54
      3655318.43     10251041.47      3655224.37     10250367.61
      3655790.28     10249710.49      3655746.85     10249488.64
      3656008.88     10249380.31      3656075.72     10248663.07
      3656370.73     10248515.93      3656267.53      10247999.1
      3656726.67     10247744.39      3656651.54     10247421.92
      3656880.06     10247446.28      3656991.82      10246511.3
      3656879.32     10245423.11      3657495.99     10244622.41
      3657416.13     10244325.89      3657647.38     10244277.97
      3658005.01     10243546.02      3657642.51     10243266.86
      3657851.54     10242863.39       3657615.9      10242721.2

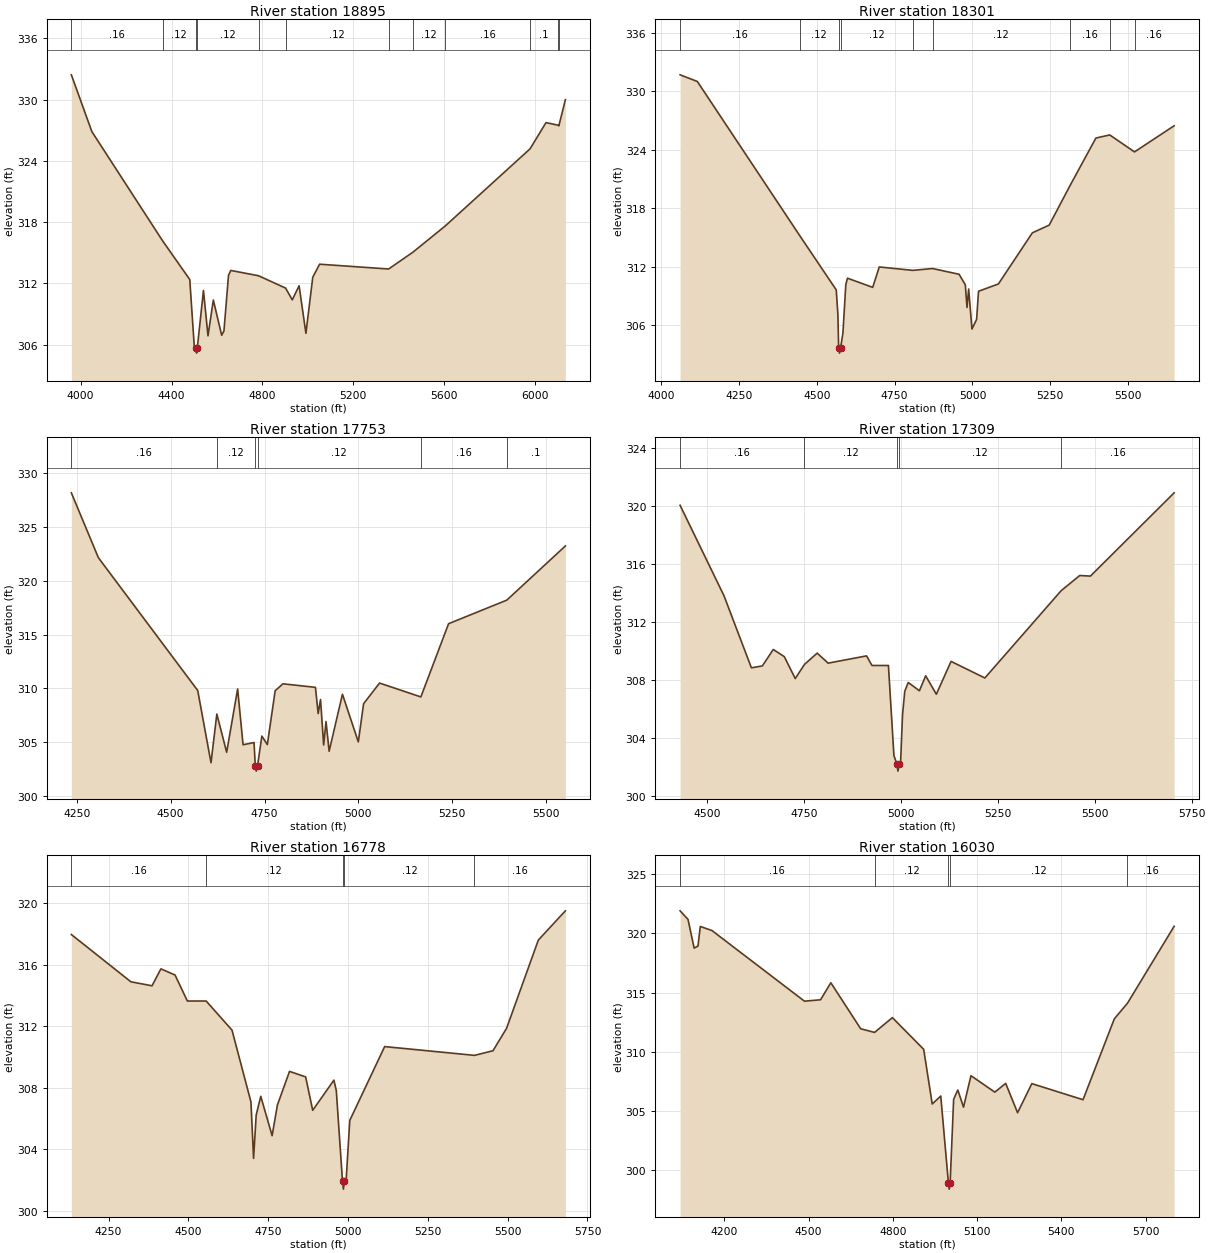
Type RM Length L Ch R = 1 ,18895   ,594,594,594
BEGIN DESCRIPTION:
UNT007 IN GIBB 33.0
END DESCRIPTION:
XS GIS Cut Line= 3
      3655342.06     10255691.64      3654125.73     10255603.63
      3653392.09     10254991.63
#Sta/Elev= 30
  3959.1  332.42  4049.3  326.86  4360.4  316.17  4480.4  312.37  4500.5   305.7
  4507.5  305.66  4510.2  305.16  4513.5  305.66  4540.6   311.3  4560.6  306.85
  4584.1  310.36  4620.8  306.91  4630.8  307.33  4650.9  312.78  4660.9  313.26
  4783.1  312.74  4902.2  311.53  4931.6  310.38  4961.7  311.76  4991.7   307.1
  5021.8  312.59  5051.9  313.87  5355.8   313.4  5461.7  315.03  5604.8  317.61
  5978.4  325.17  6048.7  327.74    6103  327.48  6105.2  327.42    6134  329.99
#Mann= 12 ,-1 , 0
  3959.1     .16       0  4360.4     .12       0  4507.5     .07       0
  4513.5     .12       0  4783.1     .16       0  4902.2     .12       0
  5355.8      .1       0  5461.7     .12       0  5604.8     .16       0
  5978.4      .1       0    6103     .16       0  6105.2      .1       0
Bank Sta=4507.5,4513.5
XS Rating Curve= 0 ,0
Exp/Cntr=0.3,0.1

Type RM Length L Ch R = 1 ,18301   ,548,548,548
BEGIN DESCRIPTION:
UNT007 IN GIBB 31.0
END DESCRIPTION:
XS GIS Cut Line= 3
      3655384.19     10255477.61      3654268.52     10255077.61
      3653876.74     10254991.71
#Sta/Elev= 30
  4061.3  331.67  4116.6  330.99  4445.7  315.18  4562.7  309.63    4568  307.11
  4570.4  303.65  4573.2  303.15  4576.4  303.65  4584.1  305.19  4593.4  310.17
  4598.8  310.83  4679.7  309.89  4700.9  311.98  4808.9  311.63  4871.9  311.82
  4957.1  311.23  4977.1  310.15  4982.6  307.83  4987.9  309.72  4998.4  305.62
  5013.3   306.6  5019.6  309.49  5083.4  310.24  5192.5  315.48  5246.5  316.27
  5312.7  320.28  5396.4  325.19  5440.8  325.51  5520.4  323.77  5647.6  326.45
#Mann= 9 ,-1 , 0
  4061.3     .16       0  4445.7     .12       0  4570.4     .07       0
  4576.4     .12       0  4808.9     .16       0  4871.9     .12       0
  5312.7     .16       0  5440.8      .1       0  5520.4     .16       0
Bank Sta=4570.4,4576.4
XS Rating Curve= 0 ,0
Exp/Cntr=0.3,0.1

Type RM Length L Ch R = 1 ,17753   ,444,444,444
BEGIN DESCRIPTION:
UNT007 IN GIBB 30.0
END DESCRIPTION:
XS GIS Cut Line= 3
      3655342.14     10255241.67      3654742.11     10254791.64
      3654342.13     10254391.66
#Sta/Elev= 30
  4235.6  328.18  4307.5  322.15  4572.1   309.8  4607.5  303.08    4623  307.61
  4649.2  304.05  4678.4  309.94  4692.9  304.75  4722.1  304.96  4725.4   302.8
  4728.1   302.3  4731.4   302.8  4742.9  305.56  4757.5  304.77  4778.4  309.78
  4799.2  310.42  4885.6  310.09  4892.9  307.65  4899.2  308.96  4907.5  304.73
  4913.8  306.91  4922.1  304.15  4957.5  309.45  4999.8  305.02  5013.9  308.57
  5056.4  310.49  5166.4   309.2  5240.2  316.01  5395.2   318.2  5551.3  323.24
#Mann= 6 ,-1 , 0
  4235.6     .16       0    4623     .12       0  4725.4     .07       0
  4731.4     .12       0  5166.4     .16       0  5395.2      .1       0
Bank Sta=4725.4,4731.4
XS Rating Curve= 0 ,0
Exp/Cntr=0.3,0.1

Type RM Length L Ch R = 1 ,17309   ,531,531,531
BEGIN DESCRIPTION:
UNT007 IN GIBB 29.0
END DESCRIPTION:
XS GIS Cut Line= 3
      3655442.12     10254891.66      3655042.11     10254491.64
      3654420.36     10254151.53
#Sta/Elev= 30
  4430.4  320.03  4543.6  313.81  4614.3  308.85  4642.6  308.98  4670.8  310.11
  4699.1  309.62  4727.4  308.11  4751.2  309.08    4784  309.86  4812.3  309.17
  4911.3  309.67  4925.4  309.01  4967.8  309.01    4982  302.81  4989.6  302.24
  4992.3  301.74  4995.6  302.24    4999  302.24  5004.2  305.61  5009.9  307.23
  5018.9  307.84  5047.8  307.27  5063.9   308.3  5091.4  307.03  5129.4  309.29
  5216.6  308.15  5413.5  314.16  5461.3   315.2  5488.9  315.16  5704.8  320.89
#Mann= 5 ,-1 , 0
  4430.4     .16       0  4751.2     .12       0  4989.6     .07       0
  4995.6     .12       0  5413.5     .16       0
Bank Sta=4989.6,4995.6
XS Rating Curve= 0 ,0
Exp/Cntr=0.3,0.1

Type RM Length L Ch R = 1 ,16778   ,748,748,748
BEGIN DESCRIPTION:
UNT007 IN GIBB 28.0
END DESCRIPTION:
XS GIS Cut Line= 3
      3656068.85     10254544.34      3655292.11     10254141.64
      3654792.11     10253691.65
#Sta/Elev= 30
  4133.3  317.96  4319.7  314.89    4386  314.63  4413.8  315.73  4458.1  315.33
  4496.7  313.64  4555.6  313.64  4636.5  311.75  4695.8  307.09  4704.1  303.42
  4712.3  306.24  4726.6  307.45  4762.2  304.89  4778.7  306.88  4816.7  309.07
  4867.2  308.71  4889.3  306.54  4955.7   308.5  4963.2  307.83  4982.7  301.92
  4985.5  301.42  4988.7  301.92  4994.3  302.07  5005.4  305.88  5114.7  310.68
  5396.1  310.11  5454.1  310.41  5496.7  311.87  5596.1   317.6  5680.9   319.5
#Mann= 5 ,-1 , 0
  4133.3     .16       0  4555.6     .12       0  4982.7     .07       0
  4988.7     .12       0  5396.1     .16       0
Bank Sta=4982.7,4988.7
XS Rating Curve= 0 ,0
Exp/Cntr=0.3,0.1

Type RM Length L Ch R = 1 ,16030   ,496,496,496
BEGIN DESCRIPTION:
UNT007 IN GIBB 26.0
END DESCRIPTION:
XS GIS Cut Line= 3
      3656492.11     10254041.65      3655911.45     10253606.15
      3654892.07     10253441.64
#Sta/Elev= 30
  4042.8  321.91  4070.9  321.19  4092.8  318.76  4106.4  318.93  4114.7  320.59
  4156.4  320.24  4485.5  314.27  4542.8  314.39  4579.3  315.83  4685.5  311.94
  4734.9  311.63  4798.4  312.88  4909.8   310.2  4940.2  305.58  4970.6  306.25
  4997.9  298.88  5000.7  298.38  5003.9  298.88  5016.4  305.97  5031.3  306.76
  5051.6  305.31  5078.1  307.97    5163  306.58  5201.7  307.32    5244  304.84
  5294.7   307.3    5477  305.94  5588.4  312.78  5635.2   314.1  5801.2   320.6
#Mann= 5 ,-1 , 0
  4042.8     .16       0  4734.9     .12       0  4997.9     .07       0
  5003.9     .12       0  5635.2     .16       0
Bank Sta=4997.9,5003.9
XS Rating Curve= 0 ,0
Exp/Cntr=0.3,0.1

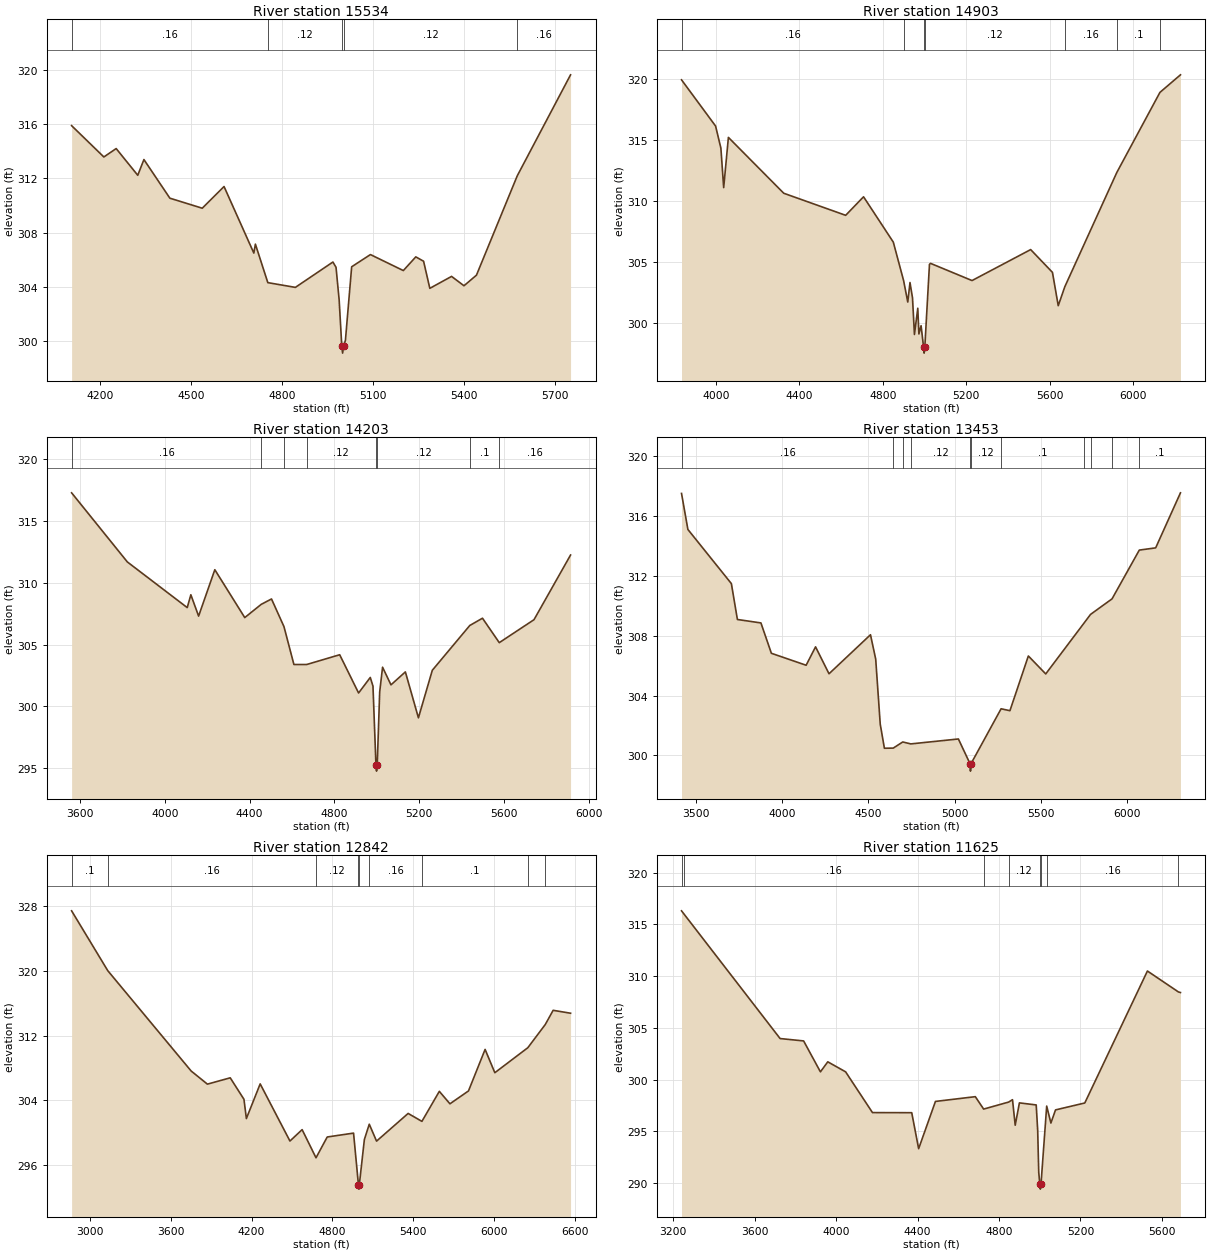
Type RM Length L Ch R = 1 ,15534   ,631,631,631
BEGIN DESCRIPTION:
UNT007 IN GIBB 25.0
END DESCRIPTION:
XS GIS Cut Line= 3
      3656496.75     10253204.49      3655879.48     10253092.26
      3654892.08     10253341.65
#Sta/Elev= 30
  4105.3  315.89  4211.7  313.58  4252.3   314.2  4323.5  312.23  4343.8  313.39
  4429.4  310.54  4536.2   309.8  4608.1   311.4  4706.4  306.49  4711.5  307.15
  4752.5  304.31  4843.4  303.96  4967.2  305.83  4977.5  305.44  4987.8  303.04
  4996.5  299.61  4999.2  299.11  5002.5  299.61  5008.5  300.06  5029.1  305.48
    5091  306.38  5199.5   305.2  5240.6  306.21  5266.3  305.89  5286.9  303.89
  5358.6  304.77  5399.6  304.08  5440.7  304.86  5575.3  312.19  5751.1  319.64
#Mann= 5 ,-1 , 0
  4105.3     .16       0  4752.5     .12       0  4996.5     .07       0
  5002.5     .12       0  5575.3     .16       0
Bank Sta=4996.5,5002.5
XS Rating Curve= 0 ,0
Exp/Cntr=0.3,0.1

Type RM Length L Ch R = 1 ,14903   ,700,700,700
BEGIN DESCRIPTION:
UNT007 IN GIBB 23.0
END DESCRIPTION:
XS GIS Cut Line= 3
      3656792.13     10253141.65       3655374.4     10252629.27
      3654592.12     10253041.64
#Sta/Elev= 30
  3835.3  319.92  3998.6  316.13    4024  314.32  4037.4  311.08    4060   315.2
  4325.3  310.62  4622.2  308.81  4707.9  310.33  4850.6  306.61    4900  303.45
  4919.9   301.7  4930.5   303.3  4942.6  302.04  4951.8  299.04  4967.9  301.19
  4973.2  299.08  4983.7  299.76  4995.6  298.01  4998.3  297.51  5001.6  298.01
  5023.9  304.79  5029.2  304.87  5227.9  303.46    5509     306  5613.5  304.13
  5641.2   301.4  5672.6  302.95  5922.2  312.33  6128.7  318.89  6227.1  320.33
#Mann= 7 ,-1 , 0
  3835.3     .16       0    4900     .12       0  4995.6     .07       0
  5001.6     .12       0  5672.6     .16       0  5922.2      .1       0
  6128.7     .16       0
Bank Sta=4995.6,5001.6
XS Rating Curve= 0 ,0
Exp/Cntr=0.3,0.1

Type RM Length L Ch R = 1 ,14203   ,750,750,750
BEGIN DESCRIPTION:
UNT007 IN GIBB 22.0
END DESCRIPTION:
XS GIS Cut Line= 3
      3656792.09     10252791.64      3655332.31     10252089.11
      3654686.99     10252439.83
#Sta/Elev= 30
  3560.2  317.29  3823.2  311.69  4105.8  307.99  4122.9  309.03  4159.5   307.3
    4236  311.06  4377.3  307.18  4454.7  308.25  4503.5  308.69  4562.3  306.45
  4609.2  303.38  4669.8  303.38  4825.3  304.17  4914.4  301.07  4969.6  302.33
  4982.3  301.63  4996.4  295.24  4999.1  294.74  5002.4  295.24    5014  301.15
  5027.6  303.16  5067.3  301.73  5135.2  302.78  5196.8  299.06  5262.3  302.91
  5439.1  306.54  5499.1  307.13  5578.3  305.15  5742.2  307.01  5914.7  312.25
#Mann= 8 ,-1 , 0
  3560.2     .16       0  4454.7     .12       0  4562.3     .16       0
  4669.8     .12       0  4996.4     .07       0  5002.4     .12       0
  5439.1      .1       0  5578.3     .16       0
Bank Sta=4996.4,5002.4
XS Rating Curve= 0 ,0
Exp/Cntr=0.3,0.1

Type RM Length L Ch R = 1 ,13453   ,611,611,611
BEGIN DESCRIPTION:
UNT007 IN GIBB 21.0
END DESCRIPTION:
XS GIS Cut Line= 3
      3656938.77     10251829.56      3655314.01     10251612.33
      3654292.09     10252341.65
#Sta/Elev= 30
  3415.9  317.52  3452.9  315.11  3705.1  311.49  3740.1  309.09  3876.6  308.86
  3937.2  306.83  4138.9  306.03  4193.5  307.26  4271.6  305.46  4512.2  308.07
  4542.5  306.44  4568.8  302.09  4592.9  300.48  4644.3  300.49  4699.4   300.9
    4746  300.77  5022.2   301.1  5089.6  299.45  5092.3  298.95  5095.6  299.45
    5270  303.12  5321.2  302.99  5428.1  306.65  5528.9  305.45  5751.1  308.85
  5788.9  309.43  5913.7  310.47  6071.8  313.73  6166.8  313.88  6310.6  317.56
#Mann= 11 ,-1 , 0
  3415.9     .16       0  4644.3     .12       0  4699.4     .16       0
    4746     .12       0  5089.6     .07       0  5095.6     .12       0
    5270      .1       0  5751.1     .05       0  5788.9      .1       0
  5913.7     .05       0  6071.8      .1       0
Bank Sta=5089.6,5095.6
XS Rating Curve= 0 ,0
Exp/Cntr=0.3,0.1

Type RM Length L Ch R = 1 ,12842   ,1217,1217,1217
BEGIN DESCRIPTION:
UNT007 IN GIBB 20.0
END DESCRIPTION:
XS GIS Cut Line= 3
      3657345.58     10251345.52      3654986.61     10251147.14
      3654246.34     10252255.45
#Sta/Elev= 30
  2865.7  327.42  3133.7  320.03  3752.3  307.63  3872.7  306.01    4042  306.79
  4143.7  304.14  4161.8  301.76  4264.1  306.04  4484.9  298.98  4575.2  300.39
  4678.1  296.91  4761.2  299.48  4956.5  299.96    4993  293.54  4995.7  293.04
    4999  293.54  5036.8  299.17  5073.1  301.06  5127.1  298.97  5361.4  302.39
  5463.5  301.41  5592.7  305.12  5671.3  303.58  5808.9  305.17  5932.1   310.3
  6004.2  307.42    6249  310.51  6378.1  313.37  6436.7  315.13  6565.8  314.77
#Mann= 9 ,-1 , 0
  2865.7      .1       0  3133.7     .16       0  4678.1     .12       0
    4993     .07       0    4999     .12       0  5073.1     .16       0
  5463.5      .1       0    6249     .05       0  6378.1      .1       0
Bank Sta=4993,4999
XS Rating Curve= 0 ,0
Exp/Cntr=0.3,0.1

Type RM Length L Ch R = 1 ,11625   ,741,741,741
BEGIN DESCRIPTION:
UNT007 IN GIBB 18.0
END DESCRIPTION:
XS GIS Cut Line= 3
      3656931.77     10250791.35      3655051.71     10250321.33
      3654637.79     10250019.67
#Sta/Elev= 30
  3240.9  316.32  3253.4     316    3725  303.97  3840.5  303.74    3923  300.75
  3959.1  301.72  4046.7  300.75  4178.6  296.81  4371.4   296.8  4405.3  293.32
  4487.8  297.89  4683.6  298.35  4724.5  297.15  4847.7  297.83  4866.2  298.06
  4879.5  295.59  4900.1  297.75  4982.6  297.55  4989.9  295.09    4995  291.05
  5000.2  289.91  5002.9  289.41  5006.2  289.91  5034.1  297.44  5054.7   295.8
  5077.5  297.07  5221.2  297.74  5528.7   310.5  5680.7  308.48    5691  308.42
#Mann= 8 ,-1 , 0
  3240.9      .1       0  3253.4     .16       0  4724.5      .1       0
  4847.7     .12       0  5000.2     .07       0  5006.2     .12       0
  5034.1     .16       0  5680.7      .1       0
Bank Sta=5000.2,5006.2
XS Rating Curve= 0 ,0
Exp/Cntr=0.3,0.1

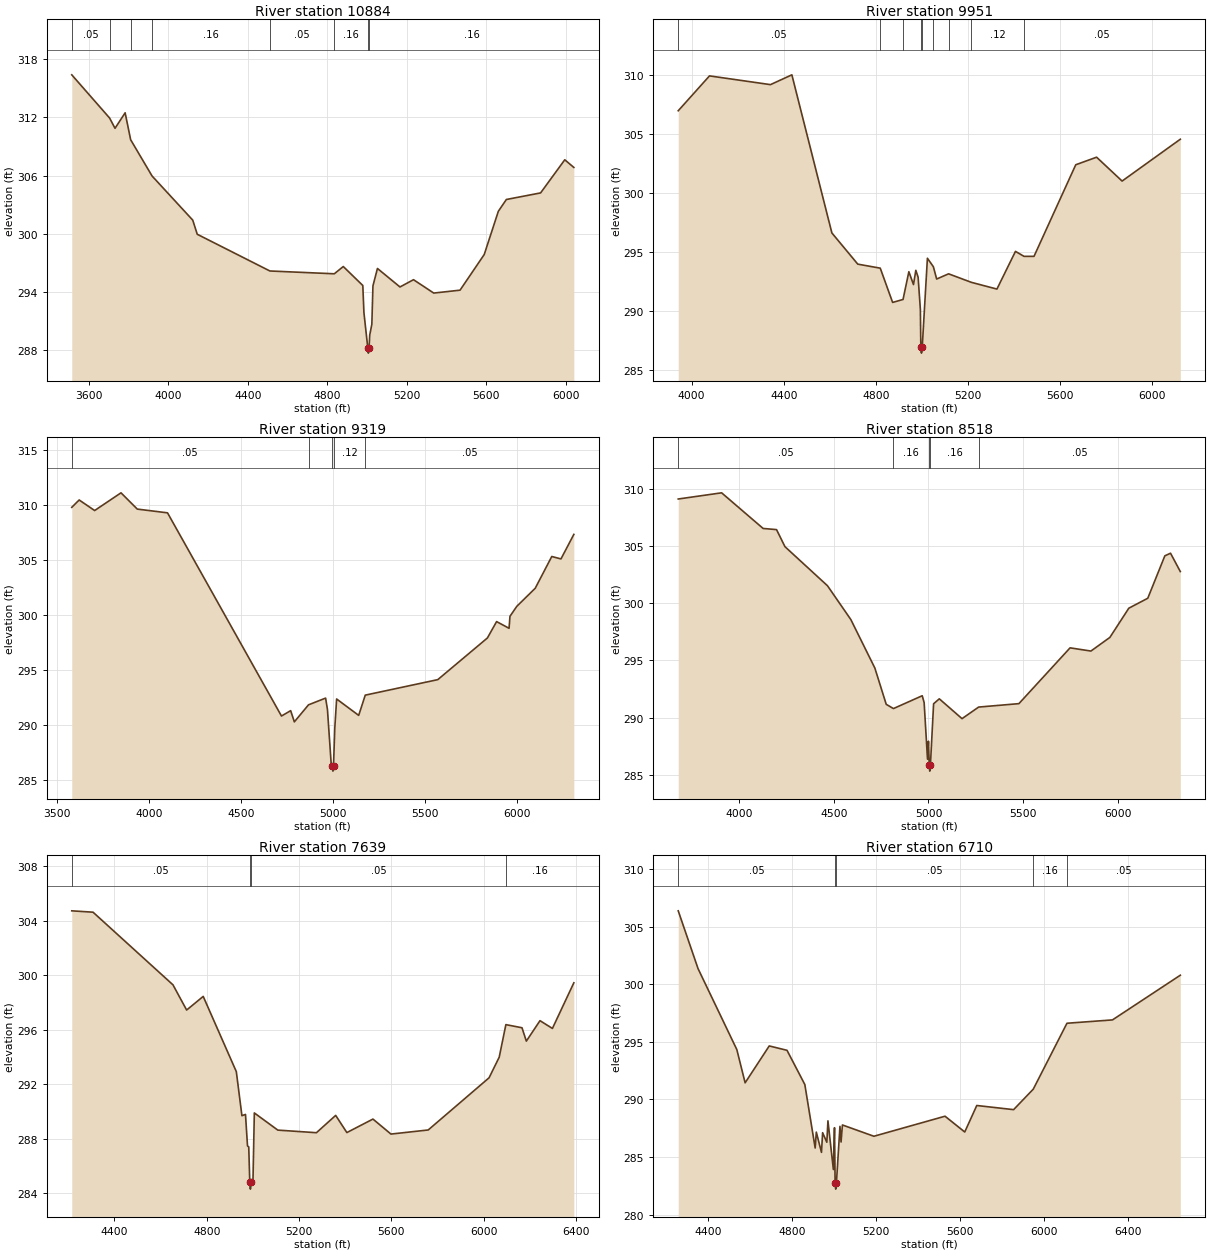
Type RM Length L Ch R = 1 ,10884   ,933,933,933
BEGIN DESCRIPTION:
UNT007 IN GIBB 17.0
END DESCRIPTION:
XS GIS Cut Line= 3
       3657022.9     10250510.73      3655373.43     10249720.15
      3654687.02     10249612.83
#Sta/Elev= 30
  3515.5   316.4  3705.7  311.94  3732.9  310.88  3783.8  312.48  3811.5   309.7
    3919  305.96  4123.6   301.4  4146.3  299.94  4511.4  296.15  4835.2  295.86
  4880.4  296.61  4978.6  294.65  4984.1  291.87  5003.8  288.17  5006.5  287.67
  5009.8  288.17  5013.4  289.55  5023.9  290.64  5029.5  294.61  5052.1  296.41
  5165.4   294.5  5233.4  295.25  5335.1  293.87  5467.4  294.17  5588.9  297.85
  5659.8  302.31  5700.2  303.53  5872.3  304.21  5993.8  307.63  6039.4  306.84
#Mann= 8 ,-1 , 0
  3515.5     .05       0  3705.7      .1       0  3811.5     .05       0
    3919     .16       0  4511.4     .05       0  4835.2     .16       0
  5003.8     .07       0  5009.8     .16       0
Bank Sta=5003.8,5009.8
XS Rating Curve= 0 ,0
Exp/Cntr=0.3,0.1

Type RM Length L Ch R = 1 ,9951    ,632,632,632
BEGIN DESCRIPTION:
UNT007 IN GIBB 15.0
END DESCRIPTION:
XS GIS Cut Line= 3
      3657064.97     10249479.53      3656276.25     10249314.39
      3654910.96     10249161.94
#Sta/Elev= 30
  3941.8  306.94  4077.5  309.89  4342.2  309.15  4435.1  309.98  4608.8   296.6
  4721.2  293.96  4818.8  293.62  4872.5  290.72  4917.7  290.97    4943  293.32
  4963.1  292.23  4973.2  293.44  4983.2  292.85    4993  290.11    4995  286.93
  4997.7  286.43    5001  286.93  5023.5  294.46  5049.4  293.74  5063.7   292.7
  5115.5  293.14  5214.4  292.42  5325.3  291.85  5405.8  295.04  5442.9  294.62
  5486.3  294.62  5667.5  302.37    5758  303.01  5868.7  300.99  6121.4  304.53
#Mann= 9 ,-1 , 0
  3941.8     .05       0  4818.8     .12       0  4917.7     .16       0
    4995     .07       0    5001     .16       0  5049.4     .12       0
  5115.5     .16       0  5214.4     .12       0  5442.9     .05       0
Bank Sta=4995,5001
XS Rating Curve= 0 ,0
Exp/Cntr=0.3,0.1

Type RM Length L Ch R = 1 ,9319    ,801,801,801
BEGIN DESCRIPTION:
UNT007 IN GIBB 13.0
END DESCRIPTION:
XS GIS Cut Line= 3
       3657440.2     10248911.66      3656840.17     10248711.65
      3654742.07     10248741.64
#Sta/Elev= 30
    3581   309.8  3621.2  310.47  3705.5  309.51  3848.8  311.12  3937.4  309.64
  4101.8   309.3  4721.6  290.82  4771.6  291.31  4791.6  290.29  4868.7  291.84
  4961.6  292.45  4971.6  291.43  4991.6  286.58  4998.6  286.31  5001.4  285.81
  5004.6  286.31  5011.6  289.73  5021.6  292.37  5141.6  290.88  5177.3  292.72
  5571.7  294.13  5841.7  297.92  5891.7  299.41  5959.4   298.8  5964.4  299.89
  6001.7   300.8  6101.7  302.44  6191.8  305.33  6241.8  305.11  6311.8  307.34
#Mann= 5 ,-1 , 0
    3581     .05       0  4868.7     .12       0  4998.6     .07       0
  5004.6     .12       0  5177.3     .05       0
Bank Sta=4998.6,5004.6
XS Rating Curve= 0 ,0
Exp/Cntr=0.3,0.1

Type RM Length L Ch R = 1 ,8518    ,879,879,879
BEGIN DESCRIPTION:
UNT007 IN GIBB 12.0
END DESCRIPTION:
XS GIS Cut Line= 3
       3657444.5     10248613.44       3657044.5     10248213.44
      3654960.48     10248111.61
#Sta/Elev= 30
  3678.1  309.09  3907.3  309.63  4126.5  306.52  4197.3  306.42  4241.9  304.93
  4466.5  301.52  4589.8  298.57  4716.7  294.34  4776.8  291.17    4815   290.8
    4967  291.92  4977.1  291.32  4994.9  286.38  4999.9  287.95  5004.1  285.84
  5006.8  285.34  5010.1  285.84  5027.1  291.22  5057.2  291.65  5177.3  289.92
  5264.9  290.93  5477.7  291.23    5748   296.1  5858.1  295.82  5958.2  297.01
  6058.3  299.56  6158.5  300.43  6248.6  304.13  6278.6  304.36  6330.3  302.76
#Mann= 5 ,-1 , 0
  3678.1     .05       0    4815     .16       0  5004.1     .07       0
  5010.1     .16       0  5264.9     .05       0
Bank Sta=5004.1,5010.1
XS Rating Curve= 0 ,0
Exp/Cntr=0.3,0.1

Type RM Length L Ch R = 1 ,7639    ,929,929,929
BEGIN DESCRIPTION:
UNT007 IN GIBB 11.0
END DESCRIPTION:
XS GIS Cut Line= 3
      3657398.06     10247995.95      3657198.08     10247795.97
      3655442.08     10247091.63
#Sta/Elev= 30
  4215.5  304.74  4307.6  304.64  4653.9  299.31  4713.1  297.46  4784.9  298.46
  4928.3  292.94  4952.5  289.71    4968   289.8  4976.7  287.49  4982.1  287.42
  4986.6  284.82  4989.3  284.32  4992.6  284.82  5000.4  284.92  5006.3  289.91
  5108.1  288.65  5275.3  288.46  5358.7  289.73  5407.1  288.47  5520.1  289.46
  5598.1  288.36  5759.5  288.66  6023.1  292.49    6067     294  6095.9  296.39
  6165.7  296.16  6184.5  295.18  6243.7  296.68  6297.5  296.11  6390.3  299.46
#Mann= 4 ,-1 , 0
  4215.5     .05       0  4986.6     .03       0  4992.6     .05       0
  6095.9     .16       0
Bank Sta=4986.6,4992.6
XS Rating Curve= 0 ,0
Exp/Cntr=0.3,0.1

Type RM Length L Ch R = 1 ,6710    ,1214,1214,1214
BEGIN DESCRIPTION:
UNT007 IN GIBB 10.0
END DESCRIPTION:
XS GIS Cut Line= 3
      3657542.12     10247341.65      3656892.11     10247091.64
      3655292.13     10246541.65
#Sta/Elev= 30
  4258.6  306.37  4352.9  301.35  4537.2  294.33  4576.8  291.44  4691.5  294.64
  4776.1  294.26  4860.8  291.29    4910  285.78  4915.4  287.16    4940   285.4
  4945.4  287.11  4965.4  286.28  4970.7  288.14  4996.6  283.91  5001.9  287.54
  5004.9  282.71  5007.7  282.21  5010.9  282.71  5027.9  287.66  5033.1   286.3
  5039.6  287.78  5189.4   286.8  5527.7  288.54  5621.5  287.17  5678.7  289.47
  5853.9  289.11  5947.5  290.89  6107.7  296.61  6324.2   296.9  6646.9  300.78
#Mann= 5 ,-1 , 0
  4258.6     .05       0  5004.9     .03       0  5010.9     .05       0
  5947.5     .16       0  6107.7     .05       0
Bank Sta=5004.9,5010.9
XS Rating Curve= 0 ,0
Exp/Cntr=0.3,0.1

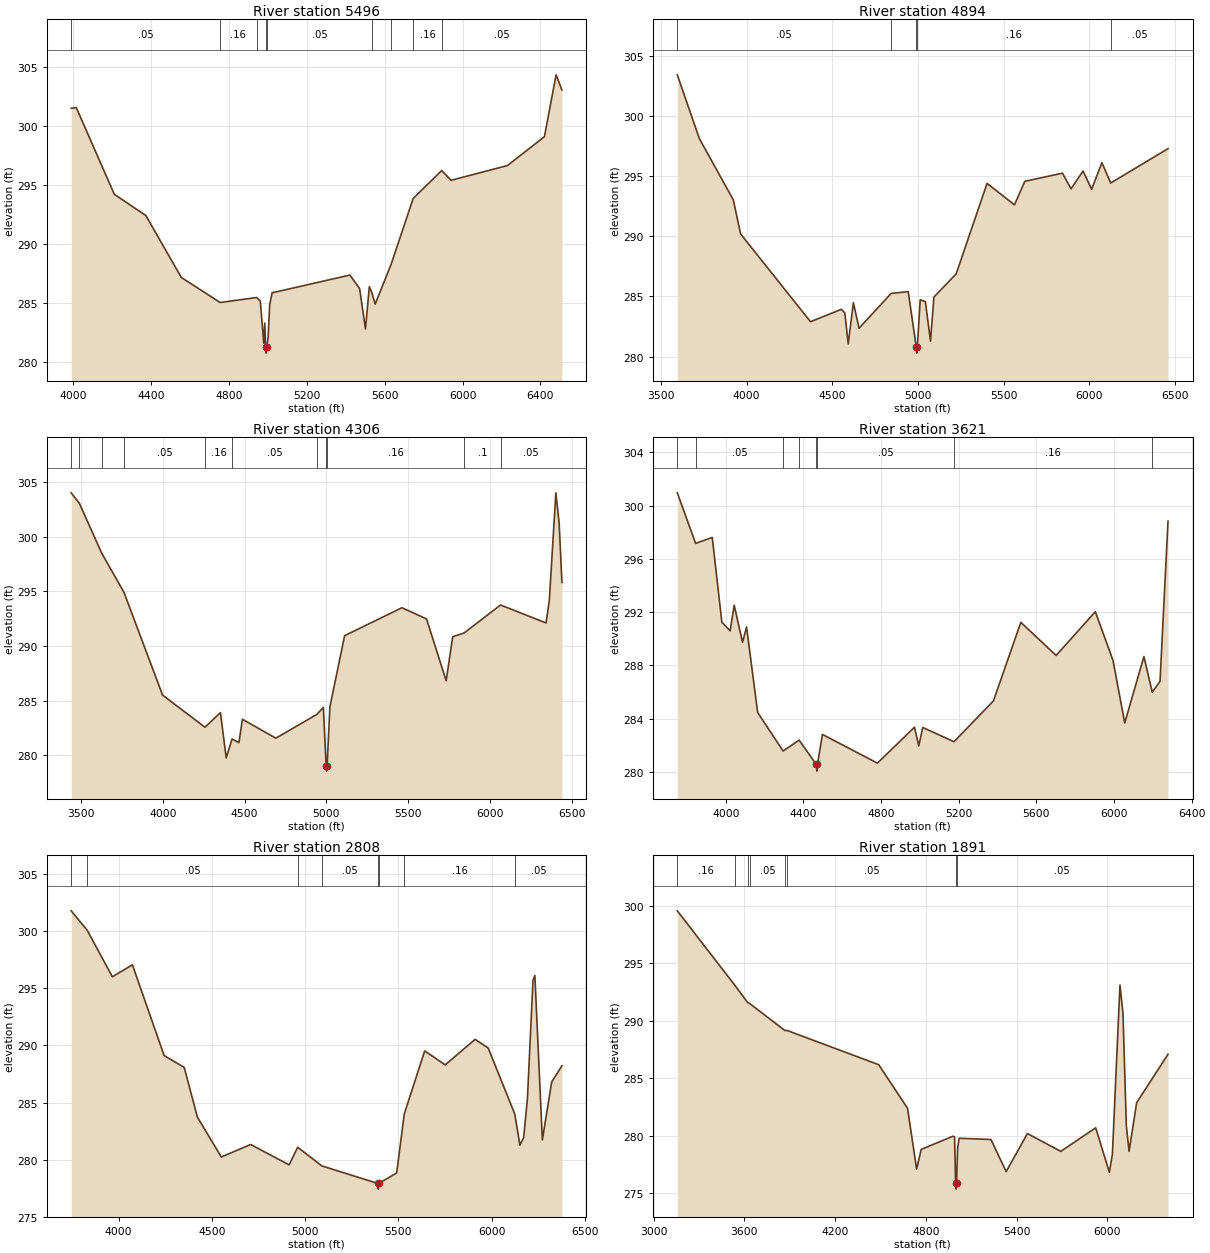
Type RM Length L Ch R = 1 ,5496    ,602,602,602
BEGIN DESCRIPTION:
UNT007 IN GIBB 8.0
END DESCRIPTION:
XS GIS Cut Line= 3
      3657850.74      10246561.3      3656842.11     10246391.64
      3655342.11     10246391.64
#Sta/Elev= 30
  3988.3  301.48  4014.3  301.54    4210  294.21  4372.3  292.41  4554.3  287.18
  4754.1  285.06  4941.1  285.48  4960.4   285.2  4978.3  281.61  4983.4  283.32
  4987.8  281.28  4990.6  280.78  4993.8  281.28    5001   282.2  5008.6  284.84
  5021.1  285.88  5421.1  287.38  5471.1  286.24  5501.1  282.82  5521.1  286.41
    5534  285.88  5551.1  284.93  5632.8  288.28  5746.5  293.86  5893.3  296.22
  5941.1  295.39  6231.1  296.64  6421.1  299.08  6481.1  304.31  6511.1  303.03
#Mann= 9 ,-1 , 0
  3988.3     .05       0  4754.1     .16       0  4941.1     .05       0
  4987.8    .035       0  4993.8     .05       0    5534      .1       0
  5632.8     .05       0  5746.5     .16       0  5893.3     .05       0
Bank Sta=4987.8,4993.8
XS Rating Curve= 0 ,0
Exp/Cntr=0.3,0.1

Type RM Length L Ch R = 1 ,4894    ,588,588,588
BEGIN DESCRIPTION:
UNT007 IN GIBB 6.0
END DESCRIPTION:
XS GIS Cut Line= 3
      3658092.09     10246341.63      3657522.63     10245874.12
      3655396.28     10245824.74
#Sta/Elev= 30
    3596  303.41  3724.4  298.12  3922.5  293.03  3965.5  290.19  4373.3   282.9
  4553.4  283.93  4573.4  283.63  4593.4  281.06  4623.4  284.48  4656.6  282.36
  4843.8  285.25  4943.5   285.4  4990.5  280.79  4993.2  280.29  4996.5  280.79
  5013.5  284.72  5043.5  284.57  5073.5  281.29  5093.5  284.95  5223.5  286.88
  5403.6  294.39  5563.6  292.61  5623.7  294.56  5843.7  295.24  5893.7  293.94
  5963.7  295.42  6013.8   293.9  6073.8  296.11  6125.1  294.42  6459.7  297.28
#Mann= 5 ,-1 , 0
    3596     .05       0  4843.8     .16       0  4990.5     .07       0
  4996.5     .16       0  6125.1     .05       0
Bank Sta=4990.5,4996.5
XS Rating Curve= 0 ,0
Exp/Cntr=0.3,0.1

Type RM Length L Ch R = 1 ,4306    ,685,685,685
BEGIN DESCRIPTION:
UNT007 IN GIBB 5.0
END DESCRIPTION:
XS GIS Cut Line= 3
      3658142.12     10246141.66       3657338.6     10245312.63
      3655495.18     10245230.21
#Sta/Elev= 30
  3440.2     304  3489.9  303.05  3626.3   298.5  3762.7  294.91  3998.8  285.52
  4258.1  282.58  4352.5  283.92  4387.8  279.78  4423.5  281.51  4465.7  281.17
  4486.8  283.31  4691.3  281.58  4941.4  283.75  4981.6  284.39  4998.6  279.07
  5001.4  278.57  5004.6  279.07  5021.7  284.45  5111.7  290.95  5462.1   293.5
  5612.2  292.48  5732.4  286.83  5772.4  290.85  5842.5   291.2  6064.7  293.75
    6343  292.11    6363  294.18    6403     304  6423.1  301.22    6440  295.81
#Mann= 11 ,-1 , 0
  3440.2     .16       0  3489.9     .05       0  3626.3      .1       0
  3762.7     .05       0  4258.1     .16       0  4423.5     .05       0
  4941.4     .16       0  4998.6     .07       0  5004.6     .16       0
  5842.5      .1       0  6064.7     .05       0
Bank Sta=4998.6,5004.6
XS Rating Curve= 0 ,0
Exp/Cntr=0.3,0.1

Type RM Length L Ch R = 1 ,3621    ,813,813,813
BEGIN DESCRIPTION:
UNT007 IN GIBB 4.0
END DESCRIPTION:
XS GIS Cut Line= 3
      3658299.68     10245607.28      3657133.08     10244607.78
      3656151.25     10244469.75
#Sta/Elev= 30
  3750.6  300.96  3844.9  297.16  3930.6  297.61    3980  291.24  4022.8  290.59
  4043.6  292.52  4086.5  289.72  4107.3  290.88  4164.4  284.46  4295.6  281.56
  4378.2  282.38  4466.5  280.55  4469.3  280.05  4472.5  280.55    4498  282.81
  4781.2  280.65  4972.2  283.35  4994.2  281.95    5015  283.33  5175.6  282.26
  5378.7  285.32  5520.1  291.23  5701.8  288.74  5903.8  292.03  5994.7  288.37
  6055.3  283.67  6154.1  288.66  6197.1  285.98    6237   286.8  6278.3  298.83
#Mann= 8 ,-1 , 0
  3750.6     .16       0  3844.9     .05       0  4295.6     .16       0
  4378.2     .05       0  4466.5     .03       0  4472.5     .05       0
  5175.6     .16       0  6197.1     .05       0
Bank Sta=4466.5,4472.5
XS Rating Curve= 0 ,0
Exp/Cntr=0.3,0.1

Type RM Length L Ch R = 1 ,2808    ,917,917,917
BEGIN DESCRIPTION:
UNT007 IN GIBB 3.0
END DESCRIPTION:
XS GIS Cut Line= 3
      3658392.08     10245291.61      3657436.81     10244070.97
       3656357.3     10244020.41
#Sta/Elev= 30
  3746.4  301.75  3831.9  300.06    3967  295.99  4074.6  297.03  4244.6   289.1
  4352.2  288.07  4422.7  283.73  4551.1  280.24  4708.4  281.33  4914.6  279.55
  4960.6  281.09  5089.9  279.46  5389.6  277.93  5392.3  277.43  5395.6  277.93
  5491.3  278.85    5532     284  5641.5  289.51  5751.6  288.29  5911.8  290.52
  5981.9  289.76  6124.2     284    6152  281.27  6172.1  281.94  6192.1  285.31
  6222.1  295.67  6232.1   296.1  6272.2  281.73  6322.2  286.79  6377.1  288.21
#Mann= 8 ,-1 , 0
  3746.4     .16       0  3831.9     .05       0  4960.6     .12       0
  5089.9     .05       0  5389.6     .07       0  5395.6     .05       0
    5532     .16       0  6124.2     .05       0
Bank Sta=5389.6,5395.6
XS Rating Curve= 0 ,0
Exp/Cntr=0.3,0.1

Type RM Length L Ch R = 1 ,1891    ,1034,1034,1034
BEGIN DESCRIPTION:
UNT007 IN GIBB 1.0
END DESCRIPTION:
XS GIS Cut Line= 3
      3658538.17     10245158.32      3658313.42     10243674.63
      3656575.31     10243534.17
#Sta/Elev= 30
  3157.4  299.55  3536.3  293.11  3621.9  291.59  3637.4  291.48  3867.7  289.16
  3884.3  289.15  4489.1  286.18  4679.4   282.4  4739.6  277.11  4769.7  278.82
  4980.4  279.97  4990.4  279.91  4997.4  275.87  5000.2  275.37  5003.4  275.87
  5010.5  278.89  5020.5  279.79  5231.2  279.68  5331.5  276.89    5472   280.2
  5692.7  278.65  5923.5   280.7  6013.7  276.84  6033.8  278.39    6084   293.1
    6104  290.63    6126   280.9  6144.2  278.65  6194.3  282.88  6401.8  287.09
#Mann= 8 ,-1 , 0
  3157.4     .16       0  3536.3     .05       0  3621.9     .16       0
  3637.4     .05       0  3867.7     .12       0  3884.3     .05       0
  4997.4     .03       0  5003.4     .05       0
Bank Sta=4997.4,5003.4
XS Rating Curve= 0 ,0
Exp/Cntr=0.3,0.1

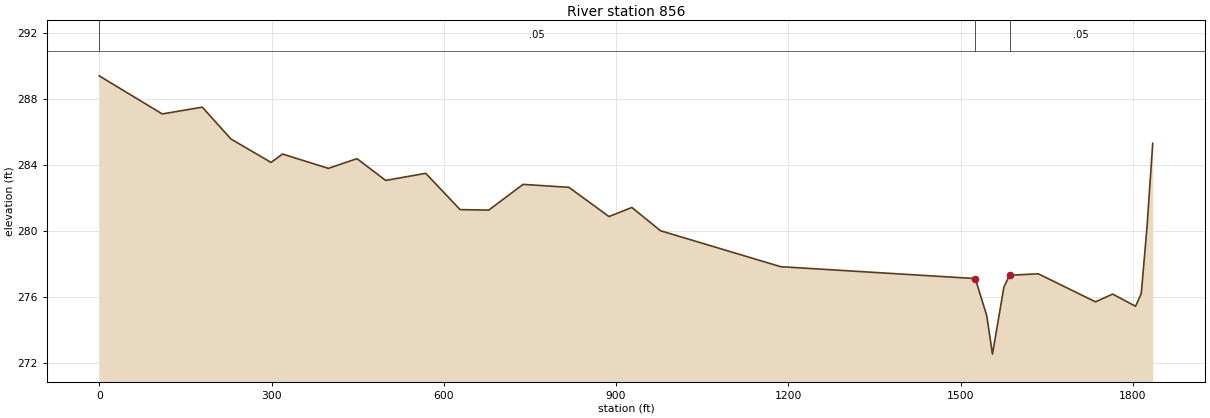
Type RM Length L Ch R = 1 ,856     ,0,0,0
XS GIS Cut Line= 3
     3658756.613    10244012.115     3658412.863     10243308.99
     3657418.071    10242954.824
#Sta/Elev= 30
       0  289.42  109.72  287.11  179.54  287.52  229.41  285.59  299.23  284.17
  319.18  284.68  398.97  283.81  448.84   284.4  498.72  283.08  568.54  283.51
  628.38  281.31  678.25  281.28   738.1  282.84  817.86  282.66  887.63  280.89
  927.49  281.44  977.32  280.03 1186.61  277.85 1525.46  277.13  1545.4  274.88
 1555.36  272.55 1575.29  276.62 1585.26  277.33 1635.09  277.42 1734.75  275.72
 1764.65  276.19 1804.52  275.45 1814.48  276.23 1824.45  280.26 1834.42  285.33
#Mann= 3 ,-1 , 0
       0     .05       0 1525.46     .07       0 1585.26     .05       0
Bank Sta=1525.46,1585.26
XS Rating Curve= 0 ,0
Exp/Cntr=0.3,0.1
Stream Node=UNT007 IN GIBB  ,Reach-1         , 0 , 0 ,Upstream end
Stream Node=UNT007 IN GIBB  ,Reach-1         , 0 , 1 ,Downstream end

Chan Stop Cuts=-1
Use User Specified Reach Order=0
Composite Channel Slope=5