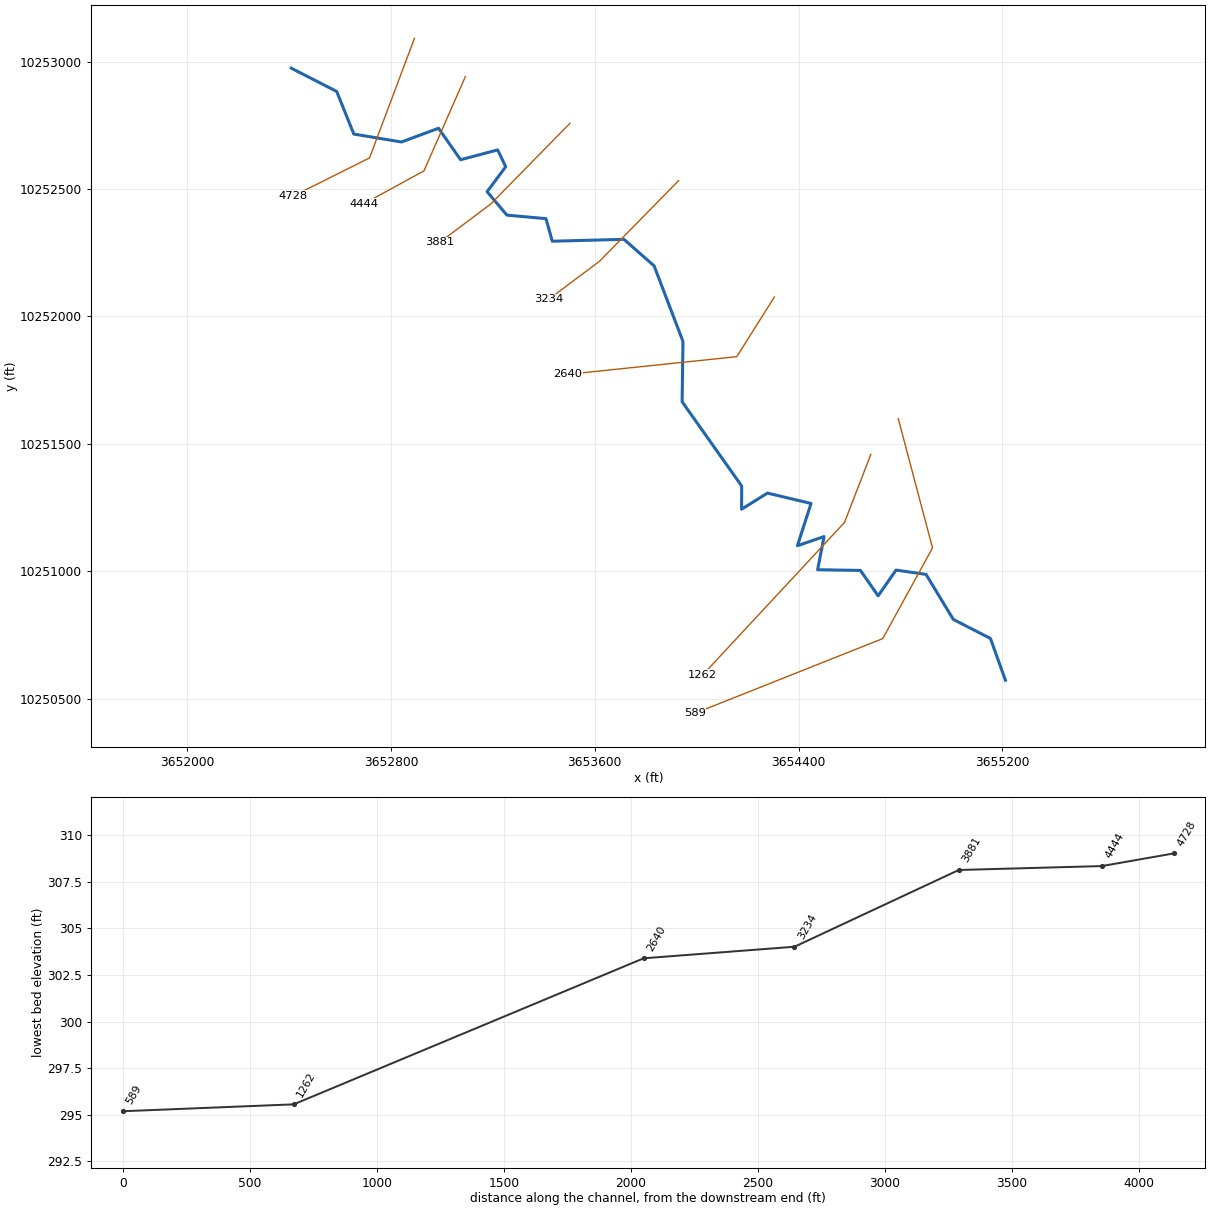
--- UNT008 IN GIBB.prj (project) ---

Proj Title=UNT008 IN GIBB Base Level Engineering
Current Plan=p01
Default Exp/Contr=0.3,0.1
English Units
Geom File=g01
Flow File=f01
Plan File=p01
Y Axis Title=Elevation
X Axis Title(PF)=Main Channel Distance
X Axis Title(XS)=Station
BEGIN DESCRIPTION:
UNT008 IN GIBB
END DESCRIPTION:
DSS Export Rating Curves= 0
DSS Export Rating Curve Sorted= 0
DSS Export Volume Flow Curves= 0
DXF OffsetX= 0
DXF OffsetY= 0
DXF ScaleX= 1
DXF ScaleY= 10

--- UNT008 IN GIBB.p01 (plan) ---

Plan Title=Multiple Run
Short Identifier=Multiple
Geom File=g01
Flow File=f01
Subcritical Flow
K Sum by GR= 0
Std Step Tol= 0.01
Critical Tol= 0.01
Num of Std Step Trials= 20
Max Error Tol= 0.3
Flow Tol Ratio= 0.001
Split Flow NTrial= 30
Split Flow Tol= 0.02
Split Flow Ratio= 0.02
Log Output Level= 0
Friction Slope Method= 1
Unsteady Friction Slope Method= 2
Unsteady Bridges Friction Slope Method= 1
Parabolic Critical Depth
Global Vel Dist=  1 , 1 , 1
Global Log Level= 0
CheckData=True
Encroach Param= -1, 0, 0, 0
BEGIN DESCRIPTION:
Multiple Run
END DESCRIPTION:

--- UNT008 IN GIBB.f01 (steady flow) ---

Flow Title=Multiple
Number of Profiles=7
Profile Names=10-year,25-year,50-year,1pct_min,100-year,1pct_plu,500-year
River Rch & RM= UNT008 IN GIBB,Reach-1,4728
     538     710     848     742    1004    1357    1407
River Rch & RM= UNT008 IN GIBB,Reach-1,1262
     610     812     973     855    1157    1564    1635
Boundary for River Rch & Prof#=UNT008 IN GIBB,Reach-1,1
Up Type=0
Dn Type=3
Dn Slope=0.005
Boundary for River Rch & Prof#=UNT008 IN GIBB,Reach-1,2
Up Type=0
Dn Type=3
Dn Slope=0.005
Boundary for River Rch & Prof#=UNT008 IN GIBB,Reach-1,3
Up Type=0
Dn Type=3
Dn Slope=0.005
Boundary for River Rch & Prof#=UNT008 IN GIBB,Reach-1,4
Up Type=0
Dn Type=3
Dn Slope=0.005
Boundary for River Rch & Prof#=UNT008 IN GIBB,Reach-1,5
Up Type=0
Dn Type=3
Dn Slope=0.005
Boundary for River Rch & Prof#=UNT008 IN GIBB,Reach-1,6
Up Type=0
Dn Type=3
Dn Slope=0.005
Boundary for River Rch & Prof#=UNT008 IN GIBB,Reach-1,7
Up Type=0
Dn Type=3
Dn Slope=0.005

--- UNT008 IN GIBB.g01 (geometry) ---

Geom Title=Existing Conditions
Program Version=4.10

River Reach=UNT008 IN GIBB  ,Reach-1
Reach XY= 30
      3652408.56     10252974.46      3652586.81     10252883.21
      3652654.08     10252715.83      3652841.02     10252684.69
      3652986.61     10252738.67      3653073.29     10252615.06
      3653218.89     10252653.68      3653250.29     10252587.56
      3653177.26     10252489.52      3653255.08     10252397.58
      3653408.46      10252383.8      3653433.16     10252295.16
      3653714.49     10252302.62      3653832.97     10252198.45
      3653946.26     10251901.58      3653942.91     10251665.01
      3654176.76     10251334.06      3654176.39     10251243.09
      3654277.95     10251306.45      3654448.96     10251265.65
      3654395.59     10251099.72      3654500.18     10251135.79
      3654474.83     10251005.59      3654642.88     10251002.81
      3654712.33     10250903.15      3654782.81      10251004.2
      3654900.52     10250987.18      3655007.47     10250810.45
       3655153.3     10250735.79      3655212.11     10250571.64

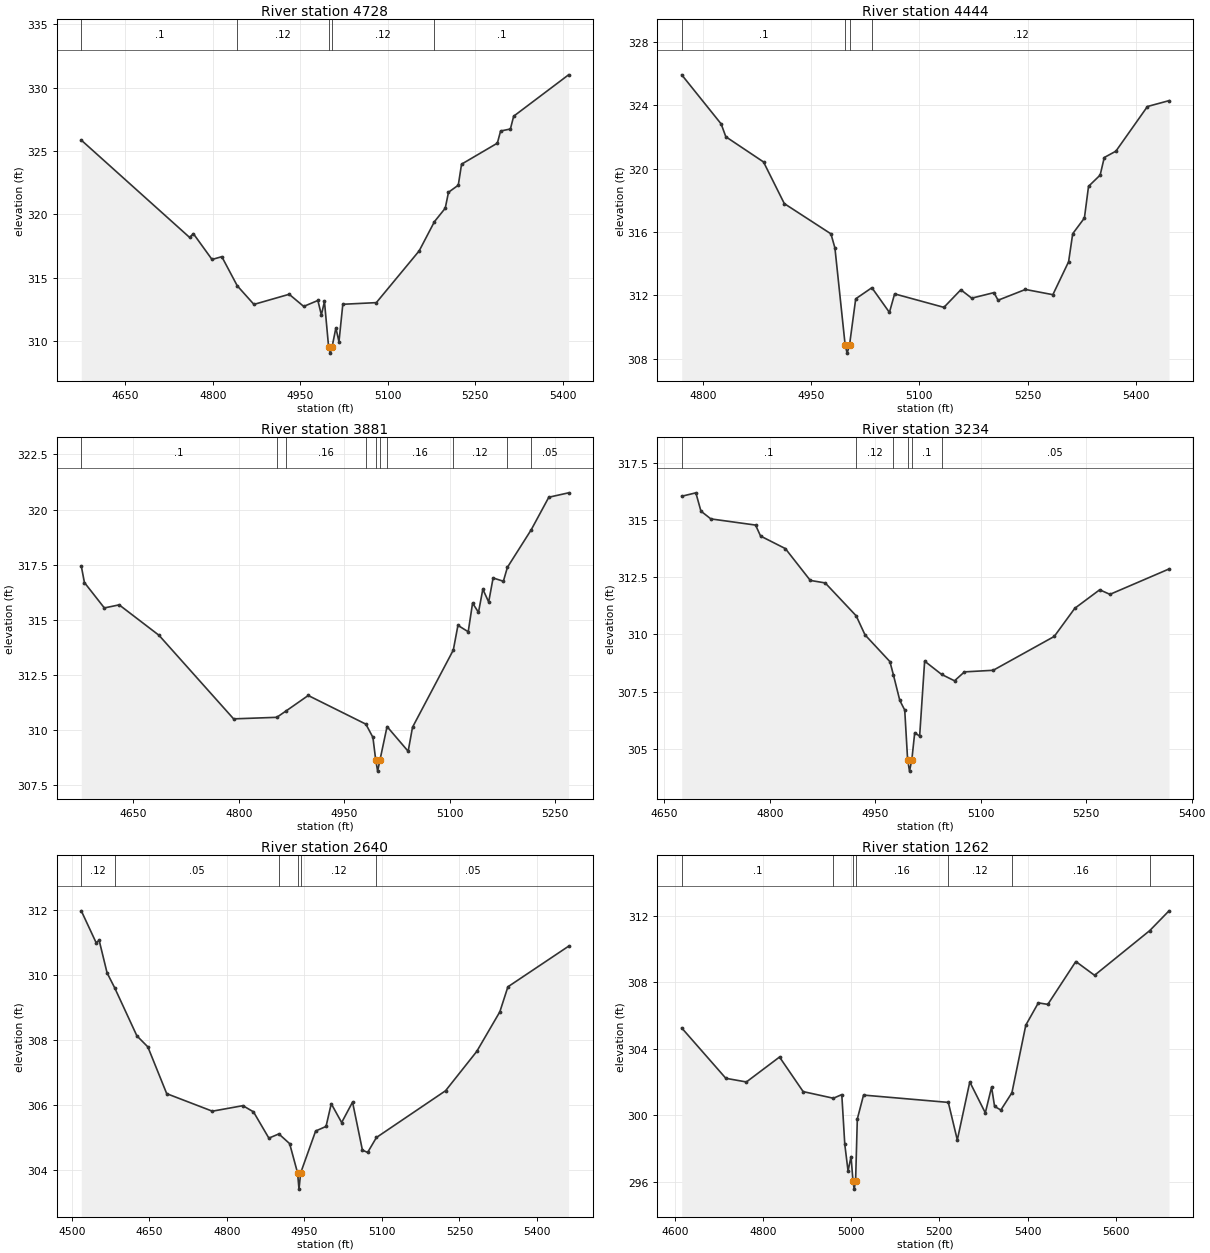
Type RM Length L Ch R = 1 ,4728    ,284,284,284
BEGIN DESCRIPTION:
UNT008 IN GIBB 5.0
END DESCRIPTION:
XS GIS Cut Line= 3
      3652892.11     10253091.66      3652715.89     10252622.37
      3652416.51     10252472.68
#Sta/Elev= 30
  4574.4  325.86  4760.3  318.17  4766.7  318.47  4798.7  316.43  4815.5  316.65
    4842  314.35  4870.6  312.88  4931.1  313.68    4956  312.72  4980.3  313.19
  4986.3  312.05  4991.6  313.11  4998.7  309.53  5001.4  309.03  5004.7  309.53
  5011.2  311.02  5016.5  309.93  5023.1  312.89  5080.6  313.02  5154.1  317.11
  5180.3  319.42  5198.8  320.48  5204.4  321.74  5221.2   322.3  5226.8  323.96
  5288.2  325.62  5293.8  326.58  5310.6  326.74  5316.2  327.75  5410.4  331.02
#Mann= 5 ,-1 , 0
  4574.4      .1       0    4842     .12       0  4998.7     .07       0
  5004.7     .12       0  5180.3      .1       0
Bank Sta=4998.7,5004.7
XS Rating Curve= 0 ,0
Exp/Cntr=0.3,0.1

Type RM Length L Ch R = 1 ,4444    ,563,563,563
BEGIN DESCRIPTION:
UNT008 IN GIBB 4.0
END DESCRIPTION:
XS GIS Cut Line= 3
      3653092.11     10252941.65      3652929.35     10252571.18
      3652692.07     10252441.62
#Sta/Elev= 30
  4770.8  325.92  4825.4  322.82  4831.9  322.01  4884.1  320.42  4912.9  317.79
  4977.5  315.88    4983  314.99  4997.2  308.85  4999.9  308.35  5003.2  308.85
  5011.8  311.78  5034.2  312.48  5058.5  310.92  5065.7  312.09    5134  311.24
  5157.4  312.35  5172.5  311.82  5203.3  312.17    5209  311.69  5246.9  312.37
  5284.9  312.04  5306.7  314.12  5312.4  315.89  5328.6  316.88  5334.3  318.88
  5350.4  319.59  5356.1   320.7  5372.2   321.1  5415.9  323.92  5445.8  324.29
#Mann= 4 ,-1 , 0
  4770.8      .1       0  4997.2     .07       0  5003.2      .1       0
  5034.2     .12       0
Bank Sta=4997.2,5003.2
XS Rating Curve= 0 ,0
Exp/Cntr=0.3,0.1

Type RM Length L Ch R = 1 ,3881    ,647,647,647
BEGIN DESCRIPTION:
UNT008 IN GIBB 3.0
END DESCRIPTION:
XS GIS Cut Line= 3
      3653502.25     10252757.79      3653192.11     10252441.64
      3652992.09     10252291.63
#Sta/Elev= 30
  4576.1  317.44  4580.6  316.69  4608.9  315.54    4630  315.68  4686.6   314.3
  4792.7  310.51  4854.1  310.58  4867.8  310.88  4898.8  311.57  4980.8  310.27
  4990.8  309.67  4994.8  308.64  4997.5  308.14  5000.8  308.64  5010.9  310.16
  5040.9  309.04  5047.1  310.13  5105.1  313.63  5111.7  314.75  5126.3  314.46
  5132.5  315.76  5140.9  315.34  5147.1  316.39  5155.4  315.81  5161.7   316.9
  5176.3  316.75    5182  317.38  5215.8  319.08  5240.9  320.56    5269  320.76
#Mann= 10 ,-1 , 0
  4576.1      .1       0  4854.1     .12       0  4867.8     .16       0
  4980.8     .12       0  4994.8     .07       0  5000.8     .12       0
  5010.9     .16       0  5105.1     .12       0    5182     .16       0
  5215.8     .05       0
Bank Sta=4994.8,5000.8
XS Rating Curve= 0 ,0
Exp/Cntr=0.3,0.1

Type RM Length L Ch R = 1 ,3234    ,594,594,594
BEGIN DESCRIPTION:
UNT008 IN GIBB 3.1
END DESCRIPTION:
XS GIS Cut Line= 3
      3653929.18     10252533.07      3653619.04     10252216.93
      3653419.01     10252066.91
#Sta/Elev= 30
  4674.9  316.04    4695  316.19  4702.2  315.39  4716.3  315.05  4779.9  314.78
    4787   314.3  4822.3  313.75  4857.7  312.36  4878.9  312.25    4923  310.81
  4935.5  309.98  4970.9  308.81  4975.8  308.24    4985  307.11    4992  306.69
  4996.1  304.52  4998.8  304.02  5002.1  304.52  5006.2   305.7  5013.2  305.55
  5020.3  308.83  5044.4  308.25  5062.8  307.97  5076.9  308.36  5117.8  308.43
  5204.6  309.91  5233.8  311.14  5269.2  311.95  5283.8  311.75  5367.8  312.86
#Mann= 6 ,-1 , 0
  4674.9      .1       0    4923     .12       0  4975.8      .1       0
  4996.1     .07       0  5002.1      .1       0  5044.4     .05       0
Bank Sta=4996.1,5002.1
XS Rating Curve= 0 ,0
Exp/Cntr=0.3,0.1

Type RM Length L Ch R = 1 ,2640    ,1378,1378,1378
BEGIN DESCRIPTION:
UNT008 IN GIBB 2.0
END DESCRIPTION:
XS GIS Cut Line= 3
      3654305.25     10252076.42      3654157.65     10251842.01
      3653495.37     10251772.75
#Sta/Elev= 30
  4518.3  311.97    4547  310.99  4552.9  311.06  4568.2  310.06  4582.9   309.6
  4625.9  308.12  4647.1  307.78  4683.6  306.34  4771.9   305.8    4831  305.97
  4851.5  305.78  4881.3  304.97  4900.6   305.1  4921.5   304.8  4936.8   303.9
  4939.6   303.4  4942.8   303.9  4971.8  305.19  4991.9  305.33    5002  306.03
  5022.1  305.45  5043.2  306.08  5062.3   304.6  5072.4  304.53  5089.4  304.99
  5223.2  306.43  5283.5  307.64  5328.2  308.86  5343.8  309.63  5461.2  310.88
#Mann= 6 ,-1 , 0
  4518.3     .12       0  4582.9     .05       0  4900.6     .12       0
  4936.8     .07       0  4942.8     .12       0  5089.4     .05       0
Bank Sta=4936.8,4942.8
XS Rating Curve= 0 ,0
Exp/Cntr=0.3,0.1

Type RM Length L Ch R = 1 ,1262    ,673,673,673
BEGIN DESCRIPTION:
UNT008 IN GIBB 2.1
END DESCRIPTION:
XS GIS Cut Line= 3
      3654683.78     10251458.39      3654580.41     10251191.17
      3654023.11     10250592.01
#Sta/Elev= 30
  4615.9  305.26  4715.9  302.23  4762.5  302.01  4837.6  303.51  4891.2  301.43
  4959.7  301.03  4978.8  301.25  4985.6  298.25    4993  296.65  4999.8  297.52
  5004.1  296.06  5006.9  295.56  5010.1  296.06    5014  299.78  5028.1  301.22
  5220.3  300.78  5240.7  298.52    5269  302.01  5304.2  300.15  5318.4   301.7
  5325.2  300.54  5339.4  300.32  5364.5  301.36    5396  305.43  5424.4  306.77
  5445.9  306.68  5509.4  309.26  5551.9  308.43    5677  311.12  5720.7  312.31
#Mann= 7 ,-1 , 0
  4615.9      .1       0  4959.7     .16       0  5004.1     .07       0
  5010.1     .16       0  5220.3     .12       0  5364.5     .16       0
    5677      .1       0
Bank Sta=5004.1,5010.1
XS Rating Curve= 0 ,0
Exp/Cntr=0.3,0.1

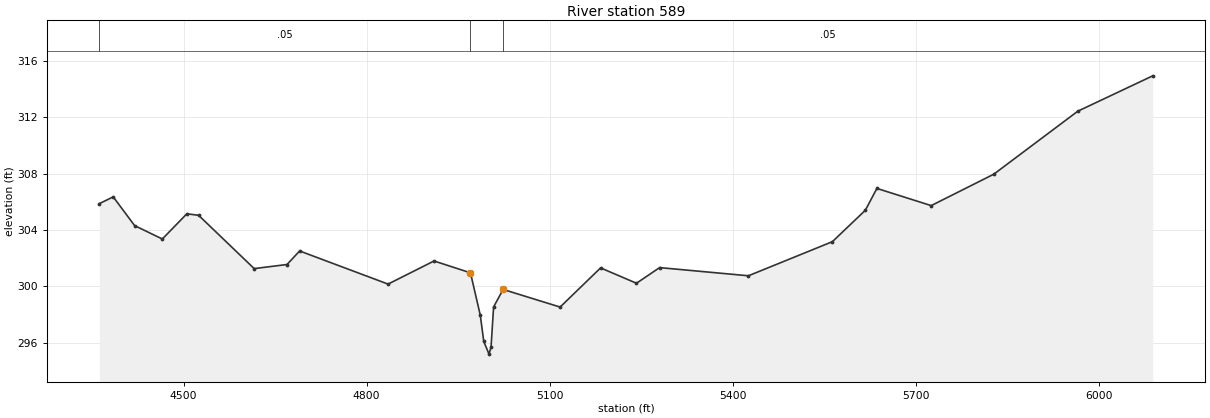
Type RM Length L Ch R = 1 ,589     ,0,0,0
BEGIN DESCRIPTION:
UNT008 IN GIBB 1.0
END DESCRIPTION:
XS GIS Cut Line= 4
      3654791.34     10251598.92      3654925.88     10251091.14
      3654730.57     10250735.24      3653992.07     10250441.63
#Sta/Elev= 30
    4362  305.87  4384.8  306.35  4419.8  304.31  4465.2  303.36  4505.4  305.15
  4524.7  305.04  4615.7  301.26  4669.5  301.55  4690.2  302.51  4835.1  300.16
  4910.4   301.8  4970.1  300.96  4986.2  297.95  4991.9  296.09  5000.5  295.19
  5003.8  295.69    5008  298.54  5023.6  299.78    5117  298.53  5183.3  301.31
  5242.1  300.22    5280  301.33  5425.5  300.75  5563.1  303.17  5617.1   305.4
    5636  306.95    5725  305.73  5827.6  307.96  5965.2  312.43    6088  314.94
#Mann= 3 , 0 , 0
    4362     .05       0  4970.1     .03       0  5023.6     .05       0
Bank Sta=4970.1,5023.6
XS Rating Curve= 0 ,0
Exp/Cntr=0.3,0.1

Chan Stop Cuts=-1
Use User Specified Reach Order=0
Composite Channel Slope=5