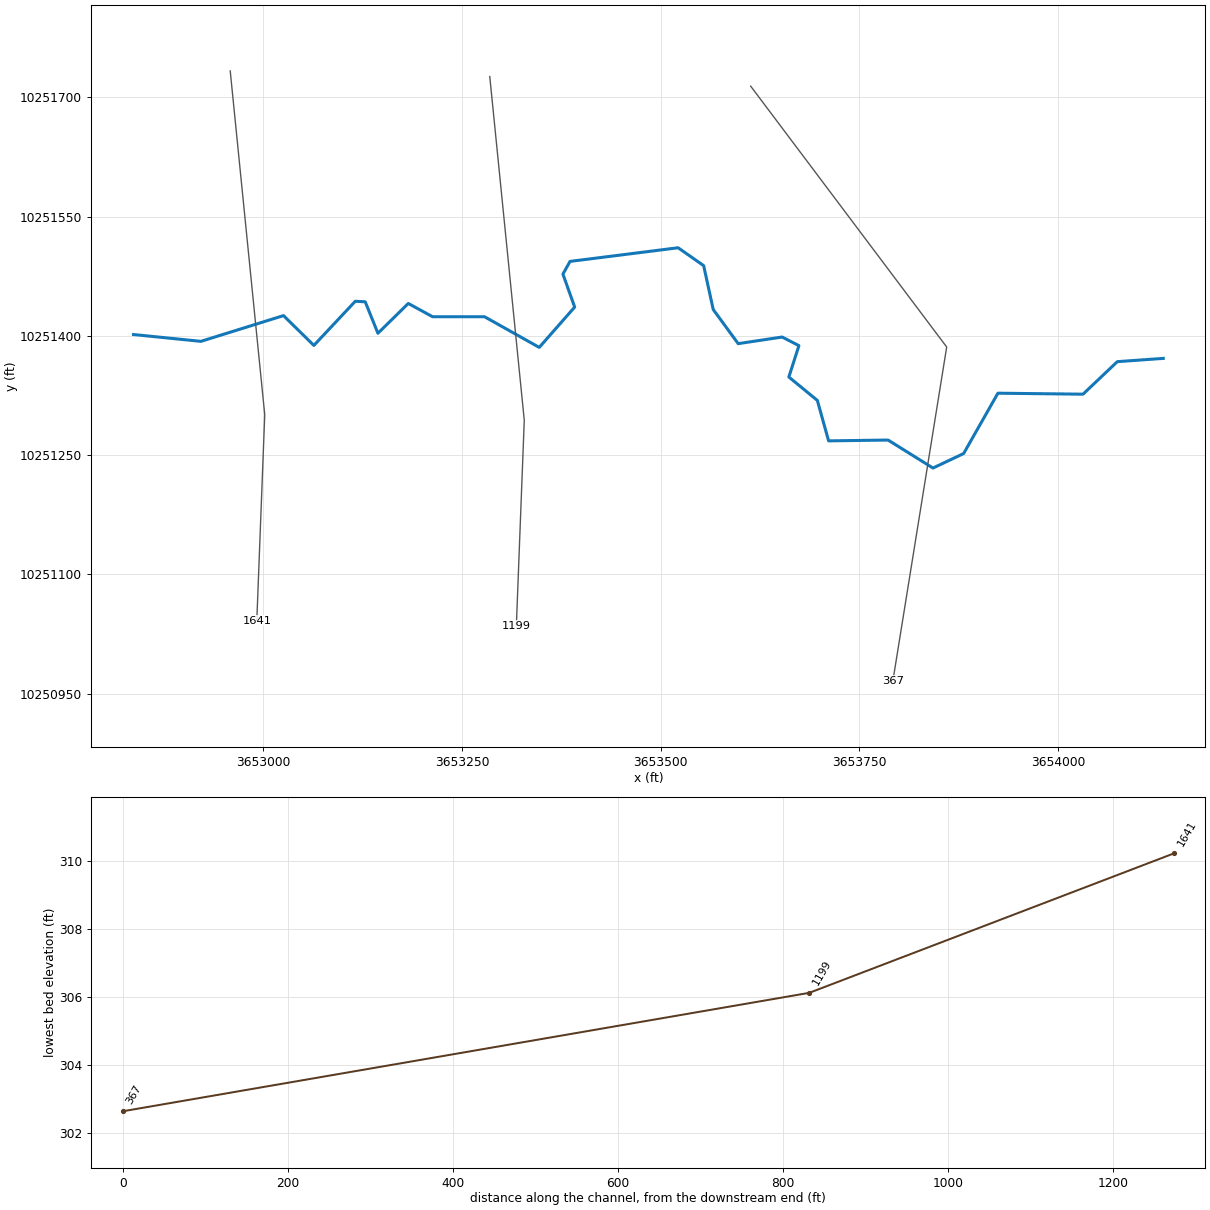
--- UNT009 IN GIBB.prj (project) ---

Proj Title=UNT009 IN GIBB Base Level Engineering
Current Plan=p01
Default Exp/Contr=0.3,0.1
English Units
Geom File=g01
Flow File=f01
Plan File=p01
Y Axis Title=Elevation
X Axis Title(PF)=Main Channel Distance
X Axis Title(XS)=Station
BEGIN DESCRIPTION:
UNT009 IN GIBB
END DESCRIPTION:
DSS Export Rating Curves= 0
DSS Export Rating Curve Sorted= 0
DSS Export Volume Flow Curves= 0
DXF OffsetX= 0
DXF OffsetY= 0
DXF ScaleX= 1
DXF ScaleY= 10

--- UNT009 IN GIBB.p01 (plan) ---

Plan Title=Multiple Run
Short Identifier=Multiple
Geom File=g01
Flow File=f01
Subcritical Flow
K Sum by GR= 0
Std Step Tol= 0.01
Critical Tol= 0.01
Num of Std Step Trials= 20
Max Error Tol= 0.3
Flow Tol Ratio= 0.001
Split Flow NTrial= 30
Split Flow Tol= 0.02
Split Flow Ratio= 0.02
Log Output Level= 0
Friction Slope Method= 1
Unsteady Friction Slope Method= 2
Unsteady Bridges Friction Slope Method= 1
Parabolic Critical Depth
Global Vel Dist=  1 , 1 , 1
Global Log Level= 0
CheckData=True
Encroach Param= -1, 0, 0, 0
BEGIN DESCRIPTION:
Multiple Run
END DESCRIPTION:

--- UNT009 IN GIBB.f01 (steady flow) ---

Flow Title=Multiple
Number of Profiles=7
Profile Names=10-year,25-year,50-year,1pct_min,100-year,1pct_plu,500-year
River Rch & RM= UNT009 IN GIBB,Reach-1,1641
     150     183     207     173     234     316     297
Boundary for River Rch & Prof#=UNT009 IN GIBB,Reach-1,1
Up Type=0
Dn Type=3
Dn Slope=0.005
Boundary for River Rch & Prof#=UNT009 IN GIBB,Reach-1,2
Up Type=0
Dn Type=3
Dn Slope=0.005
Boundary for River Rch & Prof#=UNT009 IN GIBB,Reach-1,3
Up Type=0
Dn Type=3
Dn Slope=0.005
Boundary for River Rch & Prof#=UNT009 IN GIBB,Reach-1,4
Up Type=0
Dn Type=3
Dn Slope=0.005
Boundary for River Rch & Prof#=UNT009 IN GIBB,Reach-1,5
Up Type=0
Dn Type=3
Dn Slope=0.005
Boundary for River Rch & Prof#=UNT009 IN GIBB,Reach-1,6
Up Type=0
Dn Type=3
Dn Slope=0.005
Boundary for River Rch & Prof#=UNT009 IN GIBB,Reach-1,7
Up Type=0
Dn Type=3
Dn Slope=0.005

--- UNT009 IN GIBB.g01 (geometry) ---

Geom Title=Existing Conditions
Program Version=4.10

River Reach=UNT009 IN GIBB  ,Reach-1
Reach XY= 30
      3652837.11     10251401.64      3652921.81     10251393.08
      3653025.68     10251425.45      3653063.88     10251387.95
      3653115.96      10251443.5      3653128.46     10251442.81
      3653144.43     10251403.23      3653182.63     10251440.73
      3653213.18     10251424.06      3653278.46     10251424.06
      3653347.31     10251385.47      3653391.87     10251436.15
      3653377.09     10251477.68      3653386.06     10251493.62
      3653521.97     10251510.78      3653554.09     10251488.29
      3653566.13     10251433.08       3653597.5     10251390.18
      3653652.78     10251398.51      3653673.89     10251387.67
      3653661.21     10251348.22      3653697.07     10251318.79
      3653711.21     10251267.92        3653786.     10251268.95
       3653842.5     10251233.74      3653881.04     10251251.98
      3653924.15     10251327.86      3654031.18     10251326.62
       3654074.3     10251367.54      3654132.11     10251371.64

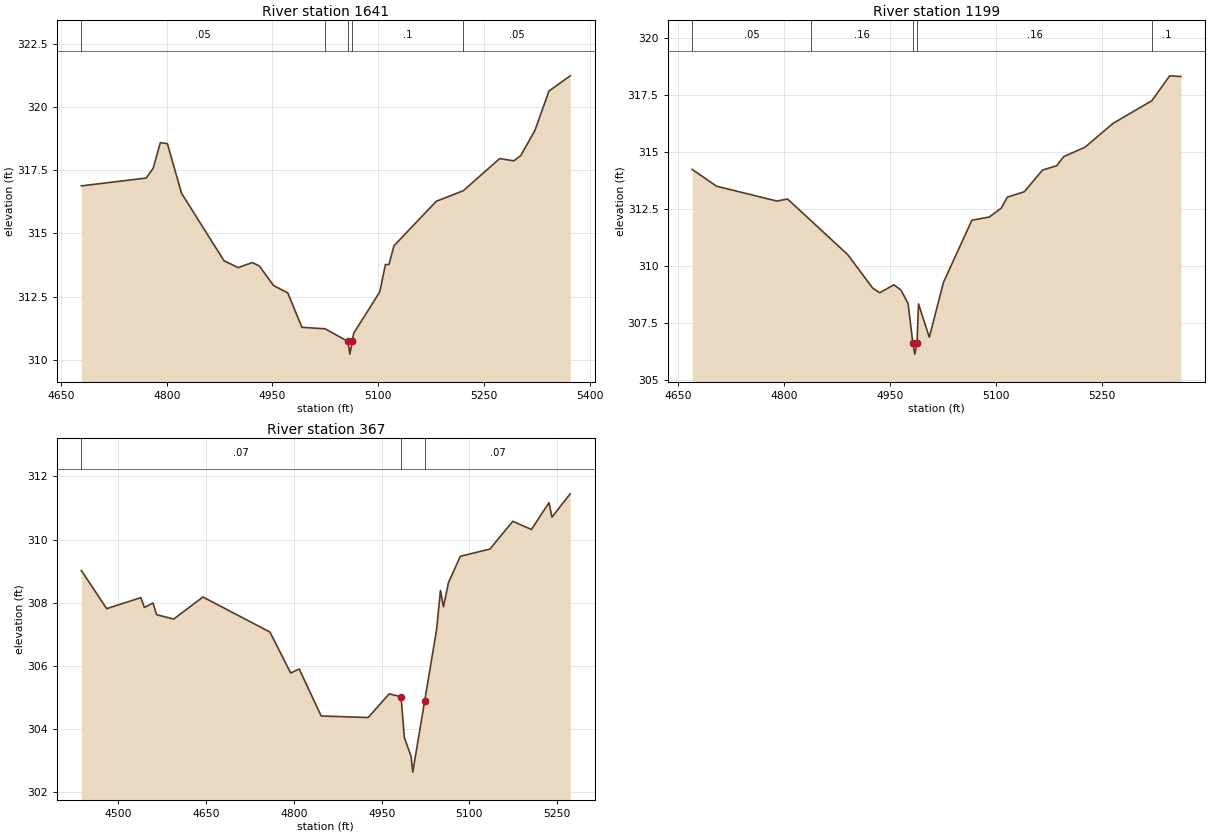
Type RM Length L Ch R = 1 ,1641    ,442,442,442
BEGIN DESCRIPTION:
UNT009 IN GIBB 2.0
END DESCRIPTION:
XS GIS Cut Line= 3
      3652958.68     10251733.14      3653002.09     10251300.86
       3652992.1     10251041.61
#Sta/Elev= 30
  4678.7  316.88  4770.7  317.19  4780.7  317.58  4790.8  318.59  4800.8  318.55
  4820.9  316.59  4881.2  313.92  4901.3  313.65  4921.4  313.85  4931.5  313.71
  4951.6  312.94  4971.7  312.65  4991.8  311.29  5024.8  311.23  5057.2  310.73
  5059.9  310.23  5063.2  310.73  5065.2  311.05  5102.3  312.69  5110.3  313.77
  5115.3  313.77  5122.4  314.51  5182.4  316.27  5220.9  316.69  5272.5  317.96
  5292.5  317.87  5302.5  318.08  5322.5  319.07  5342.5  320.63  5372.6  321.23
#Mann= 5 ,-1 , 0
  4678.7     .05       0  5024.8      .1       0  5057.2     .03       0
  5063.2      .1       0  5220.9     .05       0
Bank Sta=5057.2,5063.2
XS Rating Curve= 0 ,0
Exp/Cntr=0.3,0.1

Type RM Length L Ch R = 1 ,1199    ,832,832,832
BEGIN DESCRIPTION:
UNT009 IN GIBB 2.1
END DESCRIPTION:
XS GIS Cut Line= 3
      3653285.08     10251726.16      3653328.48     10251293.91
      3653318.53     10251035.63
#Sta/Elev= 30
  4669.6  314.22  4704.3  313.48  4789.9  312.83  4804.8  312.92  4838.5  311.96
  4890.2  310.48  4925.4  309.02  4935.5  308.81  4955.6  309.16  4965.6  308.93
  4975.7  308.34  4982.4  306.62  4985.2  306.12  4988.4  306.62  4990.5  308.32
  5005.8  306.86  5025.9  309.27  5066.1  311.99  5090.8  312.13  5107.7  312.52
  5116.3     313  5140.5  313.24  5166.3  314.19  5186.4  314.38  5196.4  314.78
  5226.4  315.19  5266.4  316.24  5321.3  317.23  5346.5  318.32  5362.5  318.29
#Mann= 5 ,-1 , 0
  4669.6     .05       0  4838.5     .16       0  4982.4     .07       0
  4988.4     .16       0  5321.3      .1       0
Bank Sta=4982.4,4988.4
XS Rating Curve= 0 ,0
Exp/Cntr=0.3,0.1

Type RM Length L Ch R = 1 ,367     ,0,0,0
BEGIN DESCRIPTION:
UNT009 IN GIBB 1.0
END DESCRIPTION:
XS GIS Cut Line= 3
      3653613.22     10251714.02      3653859.73     10251385.92
      3653792.09     10250966.22
#Sta/Elev= 30
  4436.8  309.02  4480.1  307.81  4538.4  308.16  4544.6  307.85  4559.2  307.99
  4565.5  307.62  4594.6  307.48  4644.6  308.18  4759.1  307.07  4794.6  305.77
  4809.1   305.9  4846.7  304.41    4927  304.36  4962.9  305.11  4983.2  305.02
  4988.8  303.73  5000.4  303.13  5003.2  302.63  5023.7   304.9    5044  307.15
  5050.6  308.39  5055.7  307.87  5064.2  308.63  5084.5  309.47  5135.1   309.7
  5174.2  310.58    5206  310.32  5236.1  311.17  5241.1  310.71  5272.3  311.45
#Mann= 3 , 0 , 0
  4436.8     .07       0  4983.2     .03       0  5023.7     .07       0
Bank Sta=4983.2,5023.7
XS Rating Curve= 0 ,0
Exp/Cntr=0.3,0.1

Chan Stop Cuts=-1
Use User Specified Reach Order=0
Composite Channel Slope=5