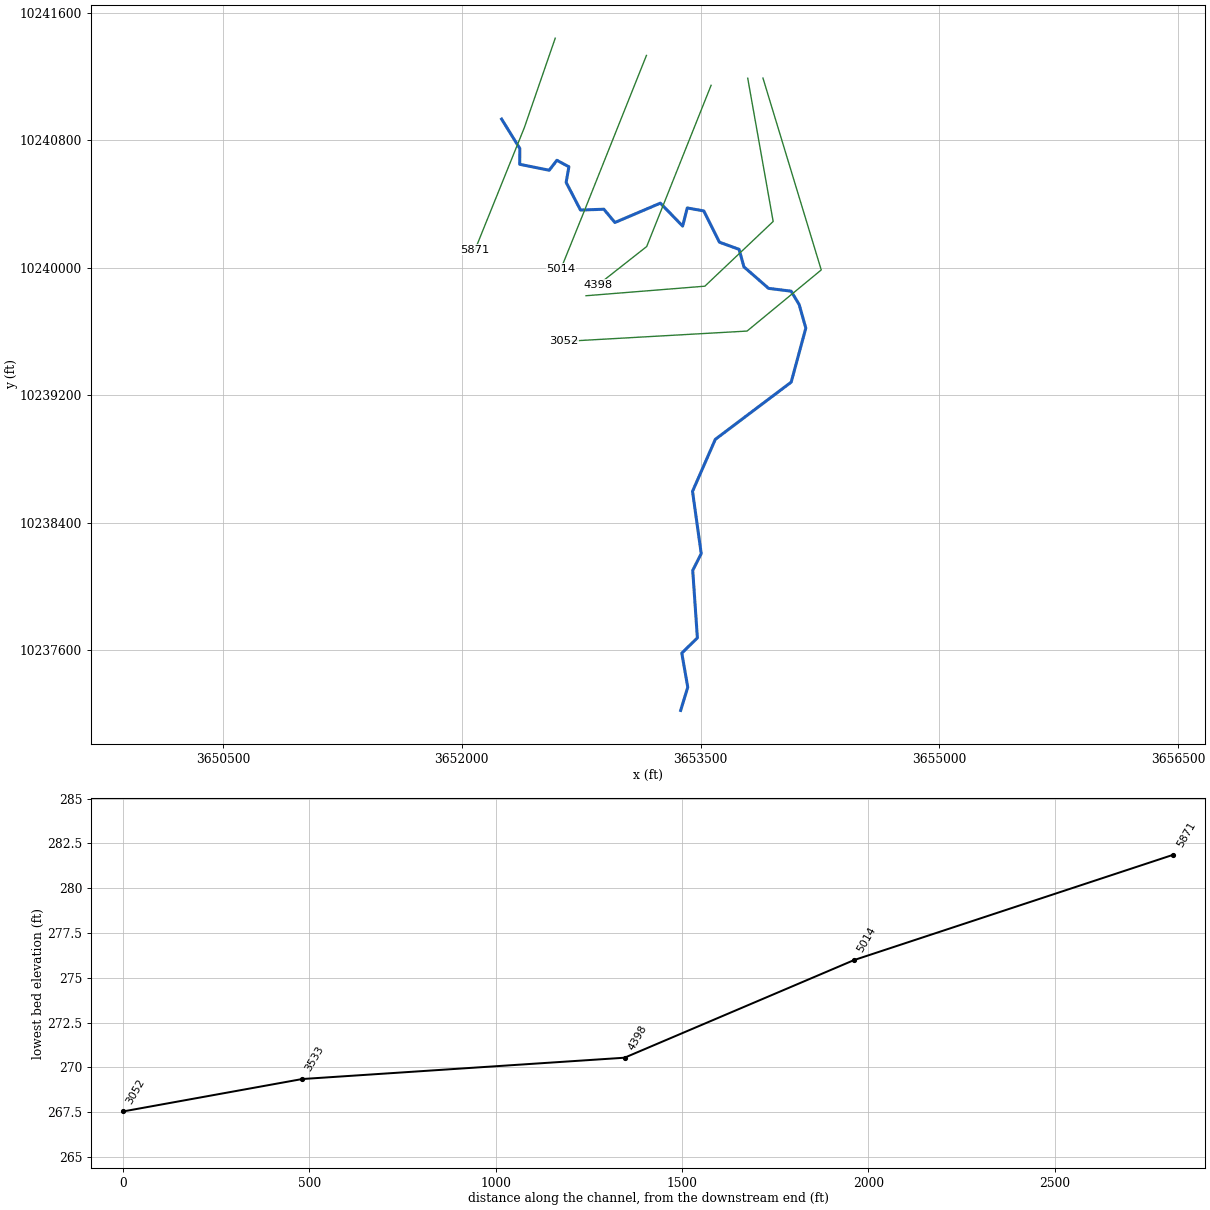
--- UNT011 IN GIBB.prj (project) ---

Proj Title=UNT011 IN GIBB Base Level Engineering
Current Plan=p01
Default Exp/Contr=0.3,0.1
English Units
Geom File=g01
Flow File=f01
Plan File=p01
Y Axis Title=Elevation
X Axis Title(PF)=Main Channel Distance
X Axis Title(XS)=Station
BEGIN DESCRIPTION:
UNT011 IN GIBB
END DESCRIPTION:
DSS Export Rating Curves= 0
DSS Export Rating Curve Sorted= 0
DSS Export Volume Flow Curves= 0
DXF OffsetX= 0
DXF OffsetY= 0
DXF ScaleX= 1
DXF ScaleY= 10

--- UNT011 IN GIBB.p01 (plan) ---

Plan Title=Multiple Run
Short Identifier=Multiple
Geom File=g01
Flow File=f01
Subcritical Flow
K Sum by GR= 0
Std Step Tol= 0.01
Critical Tol= 0.01
Num of Std Step Trials= 20
Max Error Tol= 0.3
Flow Tol Ratio= 0.001
Split Flow NTrial= 30
Split Flow Tol= 0.02
Split Flow Ratio= 0.02
Log Output Level= 0
Friction Slope Method= 1
Unsteady Friction Slope Method= 2
Unsteady Bridges Friction Slope Method= 1
Parabolic Critical Depth
Global Vel Dist=  1 , 1 , 1
Global Log Level= 0
CheckData=True
Encroach Param= -1, 0, 0, 0
BEGIN DESCRIPTION:
Multiple Run
END DESCRIPTION:

--- UNT011 IN GIBB.f01 (steady flow) ---

Flow Title=Multiple
Number of Profiles=7
Profile Names=10-year,25-year,50-year,1pct_min,100-year,1pct_plu,500-year
River Rch & RM= UNT011 IN GIBB,Reach-1,5871
     458     601     714     622     841    1138    1170
Boundary for River Rch & Prof#=UNT011 IN GIBB,Reach-1,1
Up Type=0
Dn Type=3
Dn Slope=0.005
Boundary for River Rch & Prof#=UNT011 IN GIBB,Reach-1,2
Up Type=0
Dn Type=3
Dn Slope=0.005
Boundary for River Rch & Prof#=UNT011 IN GIBB,Reach-1,3
Up Type=0
Dn Type=3
Dn Slope=0.005
Boundary for River Rch & Prof#=UNT011 IN GIBB,Reach-1,4
Up Type=0
Dn Type=3
Dn Slope=0.005
Boundary for River Rch & Prof#=UNT011 IN GIBB,Reach-1,5
Up Type=0
Dn Type=3
Dn Slope=0.005
Boundary for River Rch & Prof#=UNT011 IN GIBB,Reach-1,6
Up Type=0
Dn Type=3
Dn Slope=0.005
Boundary for River Rch & Prof#=UNT011 IN GIBB,Reach-1,7
Up Type=0
Dn Type=3
Dn Slope=0.005

--- UNT011 IN GIBB.g01 (geometry) ---

Geom Title=Existing Conditions
Program Version=4.10

River Reach=UNT011 IN GIBB  ,Reach-1
Reach XY= 30
      3652249.96      10240934.4      3652364.54      10240749.5
      3652363.67     10240650.54      3652549.13     10240613.18
      3652597.18     10240675.72       3652672.7     10240634.92
      3652655.34     10240536.83      3652745.62     10240363.22
      3652892.32     10240368.43      3652961.76     10240285.09
      3653247.35     10240406.62      3653387.11     10240262.52
      3653416.15     10240376.39      3653520.22     10240357.68
      3653618.38     10240161.41      3653741.85     10240116.57
      3653772.23     10240006.65      3653926.95      10239871.7
      3654068.53     10239853.97      3654119.03      10239770.4
      3654160.94     10239621.94      3654069.07     10239282.78
      3653592.52     10238923.73      3653449.29     10238596.91
      3653503.97     10238206.28      3653450.59     10238100.81
       3653479.8     10237677.08      3653381.89     10237581.24
      3653419.36     10237367.26      3653374.74     10237221.48

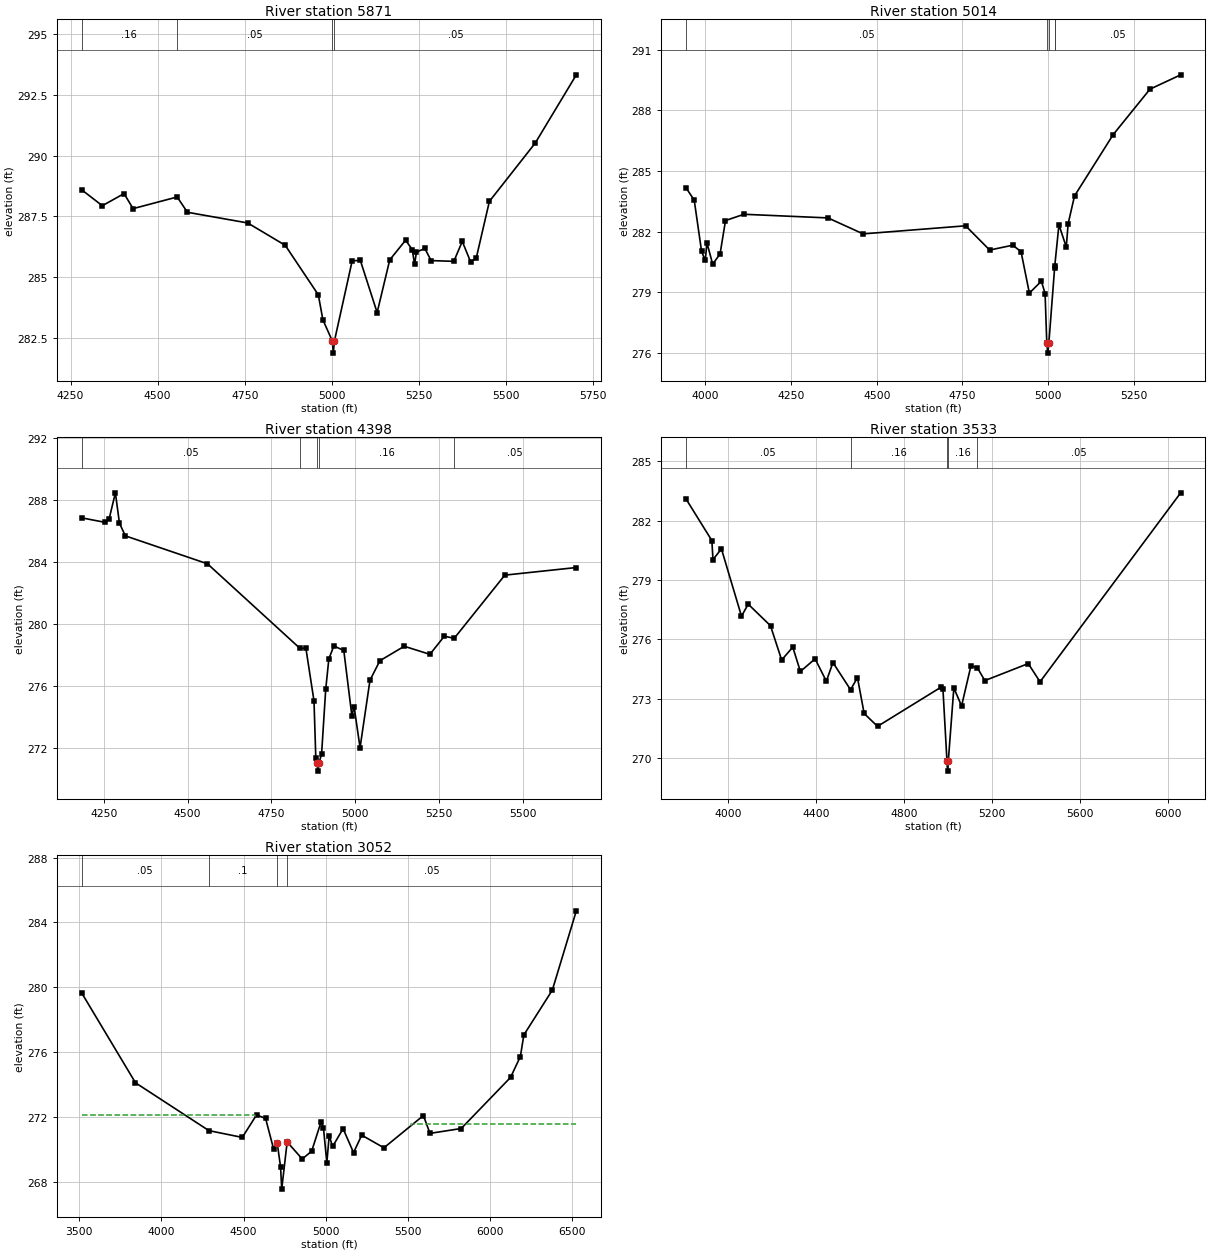
Type RM Length L Ch R = 1 ,5871    ,857,857,857
BEGIN DESCRIPTION:
UNT011 IN GIBB 5.0
END DESCRIPTION:
XS GIS Cut Line= 3
      3652586.84     10241442.29      3652393.11     10240881.57
      3652083.74     10240115.31
#Sta/Elev= 30
  4281.6   288.6  4341.3  287.94  4403.6  288.44  4429.5  287.82    4556   288.3
  4585.4  287.67  4758.4  287.23    4866  286.31    4961  284.27  4974.1  283.24
  5001.2  282.37  5003.9  281.87  5007.2  282.37  5058.1  285.67  5081.5  285.69
  5129.7  283.54  5165.9  285.71  5211.4  286.52  5230.6  286.13  5237.1  285.52
  5242.5  286.03  5266.6  286.18  5284.6  285.68  5349.8  285.65    5374  286.47
  5398.1  285.62    5414  285.78  5451.8  288.12  5583.3  290.52  5701.2  293.33
#Mann= 4 ,-1 , 0
  4281.6     .16       0    4556     .05       0  5001.2     .03       0
  5007.2     .05       0
Bank Sta=5001.2,5007.2
XS Rating Curve= 0 ,0
Exp/Cntr=0.3,0.1

Type RM Length L Ch R = 1 ,5014    ,616,616,616
BEGIN DESCRIPTION:
UNT011 IN GIBB 4.0
END DESCRIPTION:
XS GIS Cut Line= 3
      3653159.85      10241334.2      3652755.09     10240321.67
      3652622.89     10239995.05
#Sta/Elev= 30
  3943.5  284.18  3967.8  283.56  3989.3  281.02  3999.8  280.58  4005.1  281.44
  4021.6  280.39  4043.2   280.9    4059  282.55  4112.9  282.86  4357.9  282.68
  4460.3  281.89  4759.2  282.29  4829.4  281.09  4896.6  281.33  4920.8  281.01
  4945.1  278.96  4980.1  279.55  4990.9  278.94  4995.9  276.49  4998.7  275.99
  5001.9  276.49  5018.6  280.18  5019.1   280.3  5031.3  282.34  5052.7  281.24
  5058.1  282.39  5076.8  283.77  5189.4   286.8  5296.7  289.05  5386.3  289.76
#Mann= 5 ,-1 , 0
  3943.5     .05       0  4995.9     .03       0  5001.9     .05       0
  5018.6     .16       0  5019.1     .05       0
Bank Sta=4995.9,5001.9
XS Rating Curve= 0 ,0
Exp/Cntr=0.3,0.1

Type RM Length L Ch R = 1 ,4398    ,865,865,865
BEGIN DESCRIPTION:
UNT011 IN GIBB 3.1
END DESCRIPTION:
XS GIS Cut Line= 3
       3653566.1     10241146.68      3653161.34     10240134.17
      3652858.16     10239895.77
#Sta/Elev= 30
  4183.6  286.85  4253.6  286.56  4265.7  286.76  4284.6  288.46  4296.7  286.51
  4314.2  285.69  4559.3  283.89  4835.5  278.44  4852.9  278.46  4877.1  275.06
  4882.5   271.4    4886  271.04  4888.8  270.54    4892  271.04  4899.8  271.66
  4912.1  275.81  4921.4  277.77  4936.4   278.6    4966  278.31  4990.2  274.09
  4996.7   274.7  5014.5  272.05  5044.1  276.39  5073.7  277.65  5146.4  278.58
  5222.9  278.06    5266  279.23  5295.4  279.09  5446.4  283.16  5659.7  283.65
#Mann= 5 ,-1 , 0
  4183.6     .05       0  4835.5     .16       0    4886     .07       0
    4892     .16       0  5295.4     .05       0
Bank Sta=4886,4892
XS Rating Curve= 0 ,0
Exp/Cntr=0.3,0.1

Type RM Length L Ch R = 1 ,3533    ,481,481,481
BEGIN DESCRIPTION:
UNT011 IN GIBB 3.0
END DESCRIPTION:
XS GIS Cut Line= 4
      3653796.04     10241191.08      3653955.85     10240291.59
      3653526.65     10239885.22      3652779.99     10239825.26
#Sta/Elev= 30
  3806.2   283.1  3924.5  280.99  3929.6  280.03  3968.1  280.57  4059.5  277.17
    4090  277.78  4191.6  276.69  4242.4  274.96  4293.1  275.61  4327.7  274.38
  4394.7  275.02  4445.9  273.89    4476  274.83  4556.2  273.46  4587.7  274.07
  4618.2  272.26  4679.1  271.61  4970.1   273.6    4977  273.51  4995.4  269.85
  4998.1  269.35  5001.4  269.85  5026.7  273.55  5061.9  272.64  5104.4  274.66
  5133.2  274.58  5167.9  273.92  5365.6  274.78  5419.3  273.86  6059.9   283.4
#Mann= 5 ,-1 , 0
  3806.2     .05       0  4556.2     .16       0  4995.4     .07       0
  5001.4     .16       0  5133.2     .05       0
Bank Sta=4995.4,5001.4
XS Rating Curve= 0 ,0
Exp/Cntr=0.3,0.1

Type RM Length L Ch R = 1 ,3052    ,0,0,0
BEGIN DESCRIPTION:
UNT011 IN GIBB 1.0
END DESCRIPTION:
XS GIS Cut Line= 4
      3653891.73     10241192.03      3654257.87     10239987.31
      3653791.92     10239603.45      3652641.79     10239538.35
#Sta/Elev= 30
  3513.1  279.66  3841.9   274.1  4289.2  271.15  4492.6  270.73  4579.6  272.12
  4634.6   271.9  4684.1  269.99  4705.5  270.37  4725.9  268.91  4732.9  267.54
    4766  270.45  4857.9   269.4  4915.3  269.88  4972.6  271.69    4987  271.33
  5007.8  269.18  5022.1  270.83    5043  270.17  5106.8  271.27  5170.7  269.79
  5220.2  270.87  5355.7  270.09  5596.1  272.08  5636.2  270.98  5826.5  271.28
  6126.9  274.43    6187  275.72  6208.1  277.05  6381.7  279.82  6527.9  284.71
#Mann= 4 ,-1 , 0
  3513.1     .05       0  4289.2      .1       0  4705.5     .03       0
    4766     .05       0
#XS Ineff= 2 , 0
         4572.16   272.1 5520.85          271.55
Permanent Ineff=
       F       F
Bank Sta=4705.5,4766
XS Rating Curve= 0 ,0
Exp/Cntr=0.3,0.1

Chan Stop Cuts=-1
Use User Specified Reach Order=0
Composite Channel Slope=5