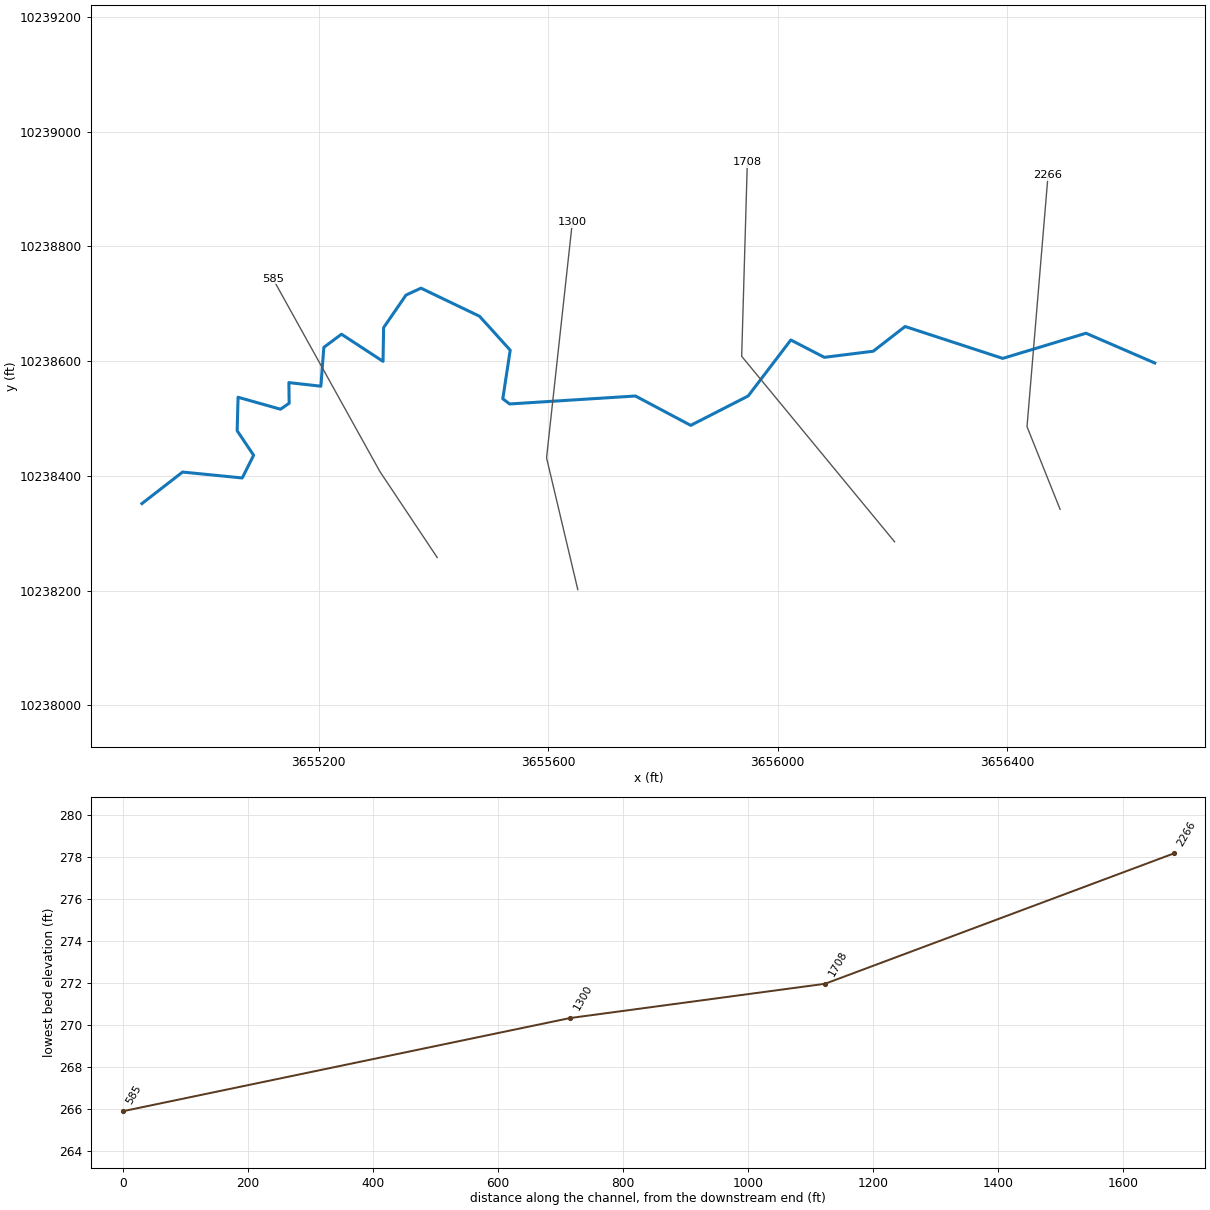
--- UNT012 IN GIBB.prj (project) ---

Proj Title=UNT012 IN GIBB Base Level Engineering
Current Plan=p01
Default Exp/Contr=0.3,0.1
English Units
Geom File=g01
Flow File=f01
Plan File=p01
Y Axis Title=Elevation
X Axis Title(PF)=Main Channel Distance
X Axis Title(XS)=Station
BEGIN DESCRIPTION:
UNT012 IN GIBB
END DESCRIPTION:
DSS Export Rating Curves= 0
DSS Export Rating Curve Sorted= 0
DSS Export Volume Flow Curves= 0
DXF OffsetX= 0
DXF OffsetY= 0
DXF ScaleX= 1
DXF ScaleY= 10

--- UNT012 IN GIBB.p01 (plan) ---

Plan Title=Multiple Run
Short Identifier=Multiple
Geom File=g01
Flow File=f01
Subcritical Flow
K Sum by GR= 0
Std Step Tol= 0.01
Critical Tol= 0.01
Num of Std Step Trials= 20
Max Error Tol= 0.3
Flow Tol Ratio= 0.001
Split Flow NTrial= 30
Split Flow Tol= 0.02
Split Flow Ratio= 0.02
Log Output Level= 0
Friction Slope Method= 1
Unsteady Friction Slope Method= 2
Unsteady Bridges Friction Slope Method= 1
Parabolic Critical Depth
Global Vel Dist=  1 , 1 , 1
Global Log Level= 0
CheckData=True
Encroach Param= -1, 0, 0, 0
BEGIN DESCRIPTION:
Multiple Run
END DESCRIPTION:

--- UNT012 IN GIBB.f01 (steady flow) ---

Flow Title=Multiple
Number of Profiles=7
Profile Names=10-year,25-year,50-year,1pct_min,100-year,1pct_plu,500-year
River Rch & RM= UNT012 IN GIBB,Reach-1,2266
     172     212     242     204     275     372     355
Boundary for River Rch & Prof#=UNT012 IN GIBB,Reach-1,1
Up Type=0
Dn Type=3
Dn Slope=0.005
Boundary for River Rch & Prof#=UNT012 IN GIBB,Reach-1,2
Up Type=0
Dn Type=3
Dn Slope=0.005
Boundary for River Rch & Prof#=UNT012 IN GIBB,Reach-1,3
Up Type=0
Dn Type=3
Dn Slope=0.005
Boundary for River Rch & Prof#=UNT012 IN GIBB,Reach-1,4
Up Type=0
Dn Type=3
Dn Slope=0.005
Boundary for River Rch & Prof#=UNT012 IN GIBB,Reach-1,5
Up Type=0
Dn Type=3
Dn Slope=0.005
Boundary for River Rch & Prof#=UNT012 IN GIBB,Reach-1,6
Up Type=0
Dn Type=3
Dn Slope=0.005
Boundary for River Rch & Prof#=UNT012 IN GIBB,Reach-1,7
Up Type=0
Dn Type=3
Dn Slope=0.005

--- UNT012 IN GIBB.g01 (geometry) ---

Geom Title=Existing Conditions
Program Version=4.10

River Reach=UNT012 IN GIBB  ,Reach-1
Reach XY= 30
      3656657.11     10238596.64      3656537.22     10238648.49
      3656392.14     10238604.64      3656222.02     10238660.22
      3656166.46     10238617.15      3656081.28     10238606.48
      3656022.86     10238636.74      3655948.54     10238539.16
      3655848.46     10238487.95       3655752.1      10238539.1
      3655532.89     10238525.23      3655520.95     10238534.29
      3655533.87     10238618.96      3655480.46     10238678.07
      3655378.38     10238727.03      3655352.34     10238715.05
      3655313.28     10238658.28      3655312.24     10238599.43
      3655239.84     10238646.82      3655209.11     10238623.91
       3655203.9      10238556.2      3655148.17     10238562.45
      3655148.69     10238526.51      3655133.59     10238516.09
      3655059.63     10238536.93      3655058.07     10238478.59
      3655086.71     10238435.88      3655066.92      10238396.3
      3654962.95     10238406.59      3654892.11     10238351.64

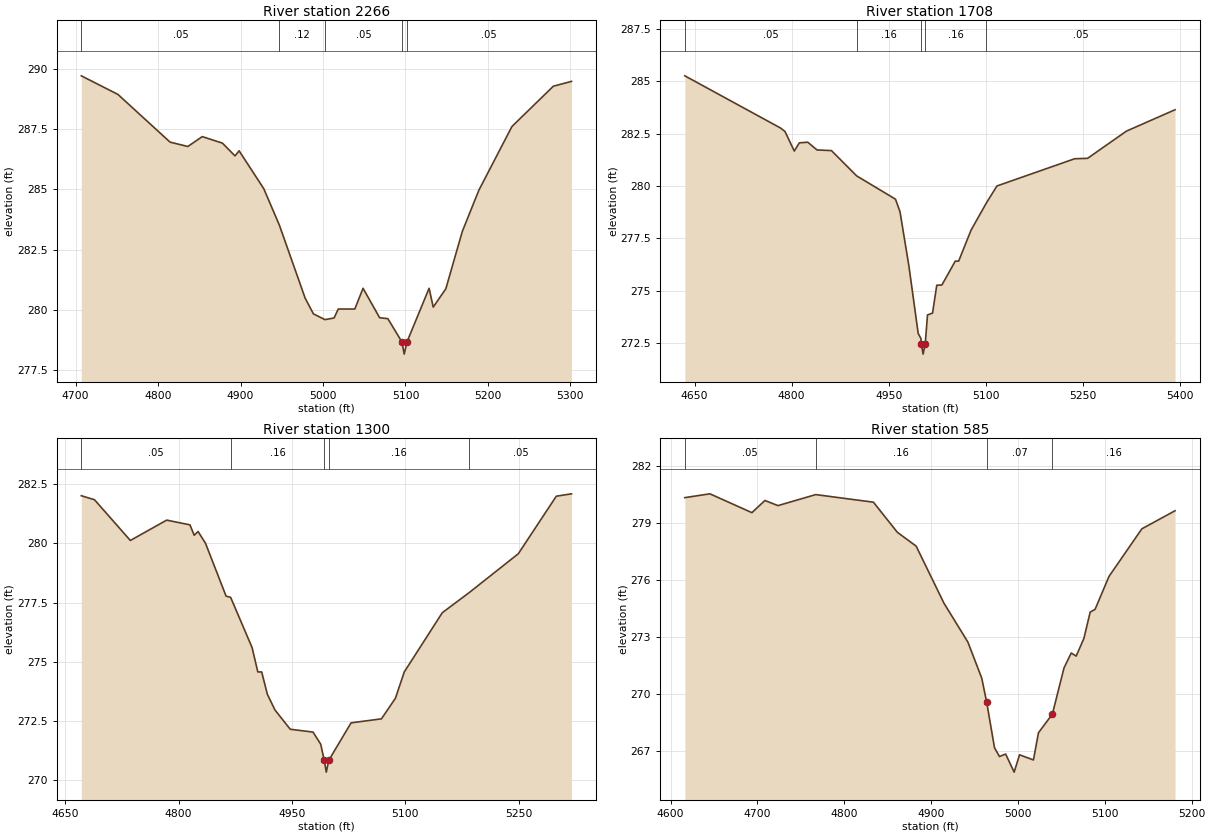
Type RM Length L Ch R = 1 ,2266    ,558,558,558
BEGIN DESCRIPTION:
UNT012 IN GIBB 4.0
END DESCRIPTION:
XS GIS Cut Line= 3
      3656492.09     10238341.68      3656434.48      10238485.7
      3656471.09     10238923.56
#Sta/Elev= 30
  4706.9  289.71  4751.3  288.94  4814.6  286.96  4836.1  286.78  4853.6  287.19
    4878  286.92  4893.3  286.39  4898.3   286.6  4928.2  285.03  4947.1  283.52
  4978.4  280.49  4988.4  279.84  5002.4   279.6  5013.5  279.67  5018.5  280.04
  5038.6  280.04  5048.6   280.9  5068.7  279.68  5078.7  279.64  5095.8  278.67
  5098.5  278.17  5101.8  278.67  5128.7   280.9  5133.7  280.12    5149  280.88
    5169  283.26  5189.1  284.97  5229.2  287.61  5279.4  289.28  5301.4  289.48
#Mann= 5 ,-1 , 0
  4706.9     .05       0  4947.1     .12       0  5002.4     .05       0
  5095.8     .07       0  5101.8     .05       0
Bank Sta=5095.8,5101.8
XS Rating Curve= 0 ,0
Exp/Cntr=0.3,0.1

Type RM Length L Ch R = 1 ,1708    ,408,408,408
BEGIN DESCRIPTION:
UNT012 IN GIBB 3.0
END DESCRIPTION:
XS GIS Cut Line= 3
      3656203.74     10238285.04      3655937.24     10238608.31
      3655947.09     10238946.72
#Sta/Elev= 30
    4635  285.26  4783.3  282.76  4789.8   282.6  4804.1  281.67    4812  282.06
    4825  282.09  4839.3  281.72  4861.5  281.69  4900.6  280.48  4960.5  279.37
  4967.5  278.77  4981.3  276.17  4995.6  272.96  4999.9  272.71  5000.5  272.47
  5003.2  271.97  5006.5  272.47    5010  273.84  5017.8  273.93  5024.3  275.26
  5032.2  275.27  5052.9  276.41  5058.1  276.41  5077.3  277.89    5101  279.19
  5117.3     280  5237.4   281.3  5257.4  281.32  5317.4  282.62  5392.5  283.64
#Mann= 5 ,-1 , 0
    4635     .05       0  4900.6     .16       0  5000.5     .07       0
  5006.5     .16       0    5101     .05       0
Bank Sta=5000.5,5006.5
XS Rating Curve= 0 ,0
Exp/Cntr=0.3,0.1

Type RM Length L Ch R = 1 ,1300    ,715,715,715
BEGIN DESCRIPTION:
UNT012 IN GIBB 2.0
END DESCRIPTION:
XS GIS Cut Line= 3
      3655651.64     10238201.72       3655597.2     10238431.46
       3655642.1     10238841.61
#Sta/Elev= 30
  4671.2  282.01  4688.7  281.84  4736.1  280.12  4784.2  280.98    4815  280.78
  4820.6  280.34  4825.7   280.5  4835.6     280  4862.8  277.77  4868.8  277.72
  4897.2   275.6  4904.8  274.57  4909.9  274.57  4917.5  273.62  4927.6  272.96
  4947.7  272.15  4977.9  272.03    4988  271.52  4992.7  270.84  4995.4  270.34
  4998.7  270.84  5028.2  272.42  5068.4  272.59  5086.9  273.46  5098.6  274.57
  5148.9  277.07  5184.5  277.92  5249.5  279.56  5299.8  281.99  5319.9  282.09
#Mann= 5 ,-1 , 0
  4671.2     .05       0  4868.8     .16       0  4992.7     .07       0
  4998.7     .16       0  5184.5     .05       0
Bank Sta=4992.7,4998.7
XS Rating Curve= 0 ,0
Exp/Cntr=0.3,0.1

Type RM Length L Ch R = 1 ,585     ,0,0,0
BEGIN DESCRIPTION:
UNT012 IN GIBB 1.0
END DESCRIPTION:
XS GIS Cut Line= 3
      3655406.71     10238257.58      3655306.69     10238407.61
       3655120.4     10238743.38
#Sta/Elev= 30
  4616.5  280.34  4645.4  280.54  4693.7  279.55  4708.7  280.19  4723.7  279.92
  4767.2   280.5  4833.6   280.1  4861.1  278.52  4882.8  277.79  4914.8  274.79
  4942.3  272.75  4958.3  270.85    4964  269.58    4973  267.19  4978.7  266.73
  4985.8  266.86  4995.6  265.91  5001.8  266.82  5017.8  266.55  5023.6  267.98
  5039.6  268.96    5053  271.39  5061.3  272.17    5067  272.01  5075.9  272.94
  5083.1  274.32  5088.8  274.47  5104.8   276.2  5142.6   278.7  5180.8  279.65
#Mann= 4 ,-1 , 0
  4616.5     .05       0  4767.2     .16       0    4964     .07       0
  5039.6     .16       0
Bank Sta=4964,5039.6
XS Rating Curve= 0 ,0
Exp/Cntr=0.3,0.1

Chan Stop Cuts=-1
Use User Specified Reach Order=0
Composite Channel Slope=5