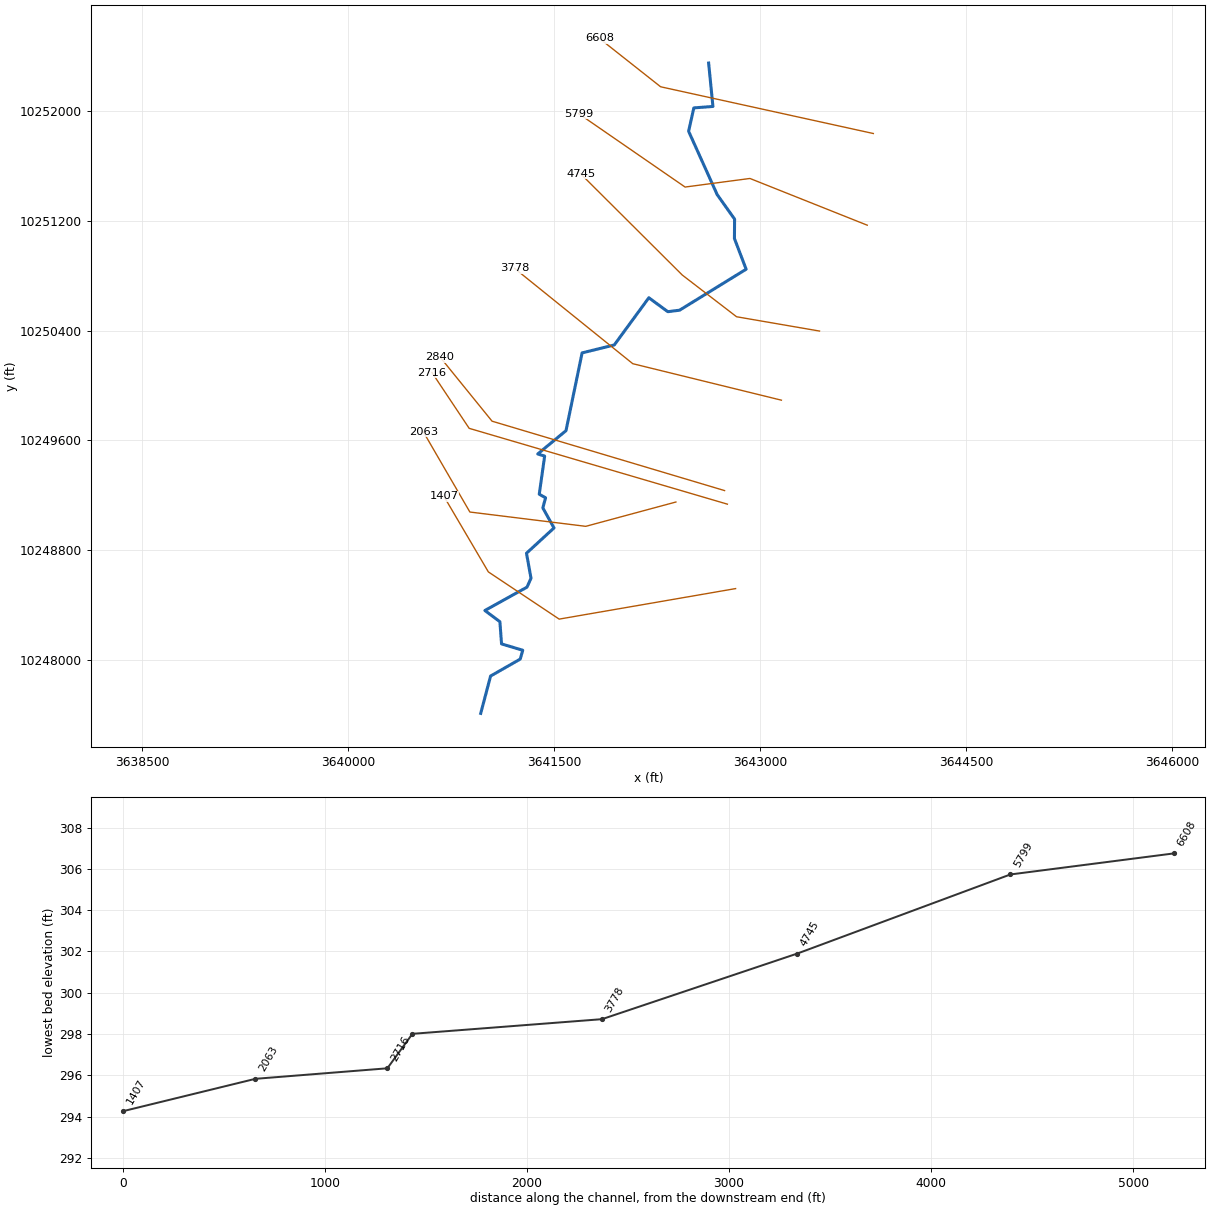
--- UNT015 IN GIBB.prj (project) ---

Proj Title=UNT015 IN GIBB Base Level Engineering
Current Plan=p01
Default Exp/Contr=0.3,0.1
English Units
Geom File=g01
Flow File=f01
Plan File=p01
BEGIN DESCRIPTION:
UNT015 IN GIBB
END DESCRIPTION:

--- UNT015 IN GIBB.p01 (plan) ---

Plan Title=Multiple Run
Short Identifier=Multiple
Geom File=g01
Flow File=f01
Subcritical Flow
K Sum by GR= 0
Std Step Tol= 0.01
Critical Tol= 0.01
Num of Std Step Trials= 20
Max Error Tol= 0.3
Flow Tol Ratio= 0.001
Split Flow NTrial= 30
Split Flow Tol= 0.02
Split Flow Ratio= 0.02
Log Output Level= 0
Friction Slope Method= 1
Unsteady Friction Slope Method= 2
Unsteady Bridges Friction Slope Method= 1
Parabolic Critical Depth
Global Vel Dist=  1 , 1 , 1
Global Log Level= 0
CheckData=True
Encroach Param= -1, 0, 0, 0
BEGIN DESCRIPTION:
Multiple Run
END DESCRIPTION:

--- UNT015 IN GIBB.f01 (steady flow) ---

Flow Title=Multiple
Number of Profiles=7
Profile Names=10-year,25-year,50-year,1pct_min,100-year,1pct_plu,500-year
River Rch & RM= UNT015 IN GIBB,Reach-1,6608
     619     827     994     876    1185    1603    1685
River Rch & RM= UNT015 IN GIBB,Reach-1,2716
     619     825     991     872    1179    1595    1672
Boundary for River Rch & Prof#=UNT015 IN GIBB,Reach-1,1
Up Type=0
Dn Type=3
Dn Slope=0.005
Boundary for River Rch & Prof#=UNT015 IN GIBB,Reach-1,2
Up Type=0
Dn Type=3
Dn Slope=0.005
Boundary for River Rch & Prof#=UNT015 IN GIBB,Reach-1,3
Up Type=0
Dn Type=3
Dn Slope=0.005
Boundary for River Rch & Prof#=UNT015 IN GIBB,Reach-1,4
Up Type=0
Dn Type=3
Dn Slope=0.005
Boundary for River Rch & Prof#=UNT015 IN GIBB,Reach-1,5
Up Type=0
Dn Type=3
Dn Slope=0.005
Boundary for River Rch & Prof#=UNT015 IN GIBB,Reach-1,6
Up Type=0
Dn Type=3
Dn Slope=0.005
Boundary for River Rch & Prof#=UNT015 IN GIBB,Reach-1,7
Up Type=0
Dn Type=3
Dn Slope=0.005

--- UNT015 IN GIBB.g01 (geometry) ---

Geom Title=Existing Conditions

River Reach=UNT015 IN GIBB,Reach-1
Reach XY= 30
      3642624.33     10252347.59      3642655.58     10252031.62
      3642516.69     10252021.20      3642478.49     10251851.06
      3642686.83     10251389.26      3642813.35     10251211.37
      3642812.11     10251070.32      3642897.34     10250846.56
      3642412.94     10250548.26      3642327.01     10250537.32
      3642188.98     10250638.88      3641937.42     10250295.13
      3641703.05     10250237.32      3641585.80     10249671.05
      3641379.69     10249501.17      3641430.27     10249486.07
      3641391.01     10249208.23      3641437.07     10249182.56
      3641417.07     10249108.54      3641498.57     10248962.93
      3641298.15     10248778.53      3641331.06     10248596.60
      3641301.64     10248531.63      3640995.05     10248361.72
      3641104.42     10248280.12      3641116.58     10248118.67
      3641270.86     10248072.33      3641252.62     10248007.91
      3641036.81     10247884.60      3640964.81     10247612.74

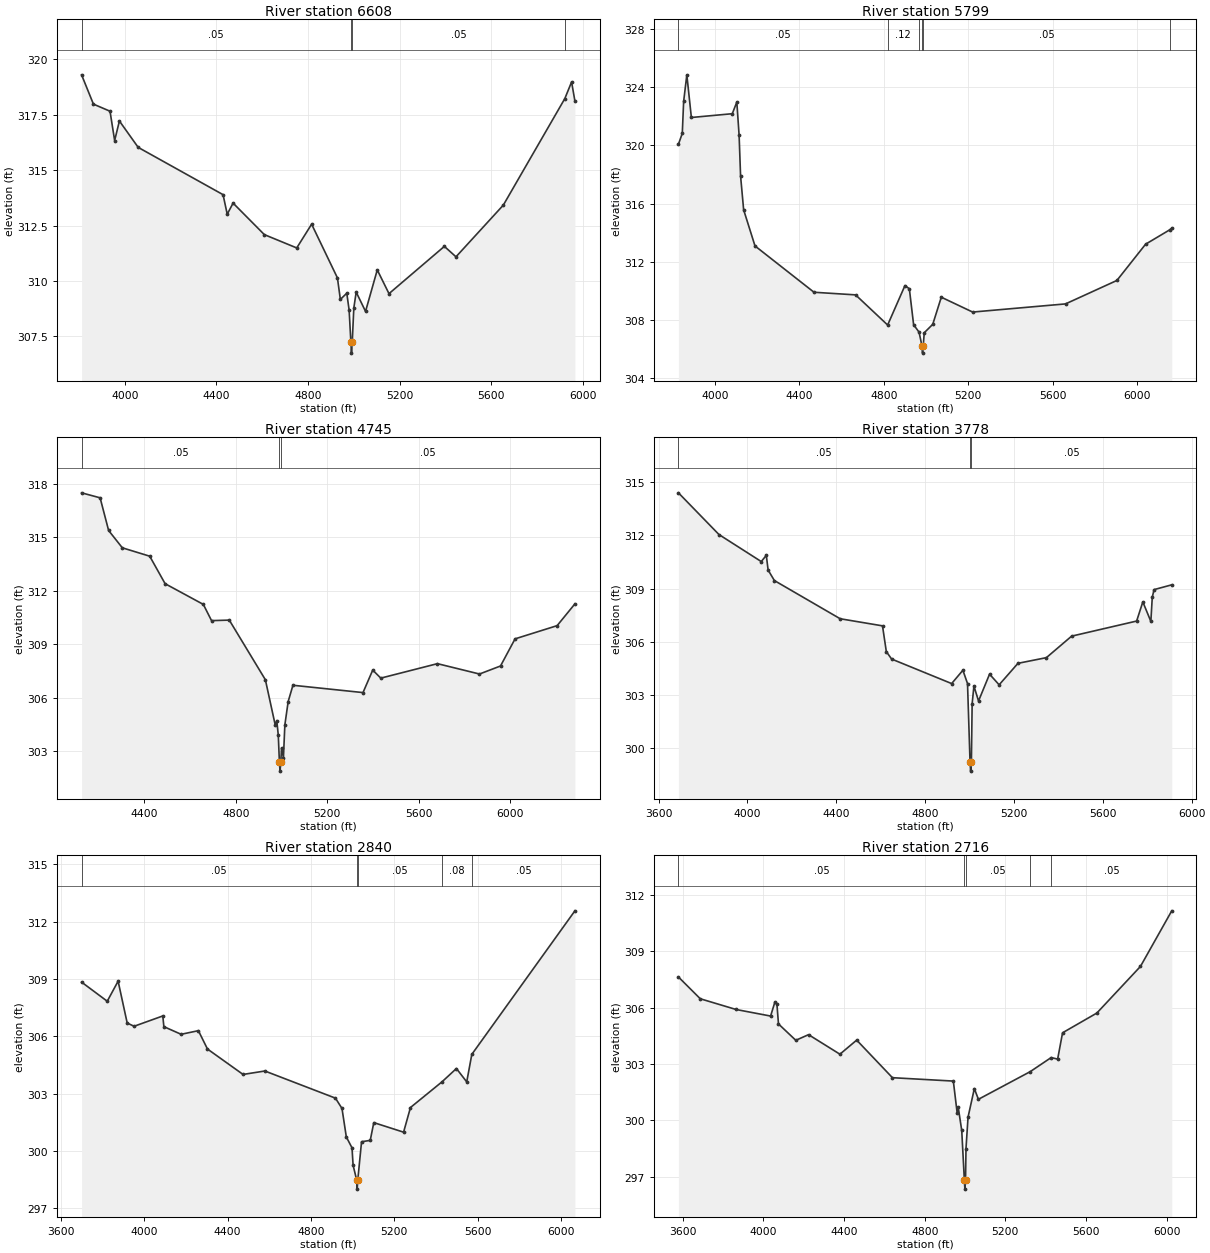
Type RM Length L Ch R = 1,6608,809,809,809
BEGIN DESCRIPTION:
UNT015 IN GIBB 8.0
END DESCRIPTION:
XS GIS Cut Line= 3
      3643823.43     10251834.64      3642274.79     10252174.92
      3641828.26     10252527.61
#Sta/Elev= 30
  3811.4  319.29  3863.1  317.97  3935.6  317.65  3955.8  316.33  3976.6  317.21
  4058.7  316.02  4429.3  313.89  4447.5  313.01  4473.1  313.51  4609.6  312.09
  4751.1  311.49  4816.1  312.56  4928.8  310.14  4941.6  309.17  4969.7  309.45
  4979.9  308.69  4987.5  307.25  4990.2  306.75  4993.5  307.25  5000.4  308.78
  5010.7  309.50  5051.6  308.63  5102.8  310.50  5154.0  309.43  5395.8  311.56
  5446.6  311.09  5653.4  313.42  5922.0  318.22  5951.5  318.97  5966.0  318.11
#Mann=4,-1,0
  3811.4    0.05       0  4987.5    0.03       0  4993.5    0.05       0
  5922.0    0.08       0
Bank Sta=4987.5,4993.5
Exp/Cntr=0.3,0.1

Type RM Length L Ch R = 1,5799,1054,1054,1054
BEGIN DESCRIPTION:
UNT015 IN GIBB 7.1
END DESCRIPTION:
XS GIS Cut Line= 4
      3643779.09     10251167.12      3642924.96     10251507.38
      3642452.74     10251444.88      3641678.19     10251979.16
#Sta/Elev= 30
  3827.0  320.07  3845.3  320.82  3851.7  323.01  3866.8  324.84  3888.3  321.91
  4082.1  322.17  4103.6  322.97  4114.4  320.69  4121.4  317.89  4135.9  315.57
  4189.7  313.09  4469.2  309.91  4666.1  309.73  4818.0  307.66  4900.0  310.37
  4920.8  310.15  4941.0  307.68  4966.8  307.17  4980.5  306.23  4983.3  305.73
  4986.5  306.23  4991.4  307.13  5031.7  307.71  5072.1  309.57  5220.6  308.55
  5660.5  309.11  5903.8  310.72  6039.8  313.21  6154.4  314.20  6163.7  314.31
#Mann=6,-1,0
  3827.0    0.05       0  4818.0    0.12       0  4966.8    0.05       0
  4980.5    0.03       0  4986.5    0.05       0  6154.4    0.08       0
Bank Sta=4980.5,4986.5
Exp/Cntr=0.3,0.1

Type RM Length L Ch R = 1,4745,967,967,967
BEGIN DESCRIPTION:
UNT015 IN GIBB 7.0
END DESCRIPTION:
XS GIS Cut Line= 4
      3643431.90     10250396.27      3642827.74     10250500.44
      3642432.26     10250804.37      3641692.14     10251541.61
#Sta/Elev= 30
  4126.0  317.49  4207.0  317.21  4244.2  315.38  4304.1  314.41  4423.8  313.94
  4491.1  312.40  4658.2  311.24  4694.1  310.33  4771.7  310.36  4929.4  307.02
  4972.9  304.46  4979.3  304.73  4985.8  303.92  4990.8  302.40  4993.5  301.90
  4996.8  302.40  5000.1  303.20  5008.3  302.64  5014.6  304.49  5029.1  305.80
  5049.9  306.71  5356.2  306.30  5398.7  307.56  5434.0  307.11  5681.5  307.92
  5865.4  307.34  5957.3  307.79  6020.9  309.31  6204.8  310.05  6282.5  311.27
#Mann=3,-1,0
  4126.0    0.05       0  4990.8    0.03       0  4996.8    0.05       0
Bank Sta=4990.8,4996.8
Exp/Cntr=0.3,0.1

Type RM Length L Ch R = 1,3778,938,938,938
BEGIN DESCRIPTION:
UNT015 IN GIBB 6.0
END DESCRIPTION:
XS GIS Cut Line= 3
      3643154.27     10249893.05      3642071.85     10250158.79
      3641210.74     10250853.24
#Sta/Elev= 30
  3689.6  314.39  3872.2  312.04  4062.5  310.52  4085.2  310.87  4093.4  310.04
  4121.6  309.45  4417.7  307.30  4608.3  306.90  4625.5  305.45  4649.4  305.03
  4919.5  303.65  4970.2  304.40  4991.0  303.65  5002.4  299.22  5005.1  298.72
  5008.4  299.22  5011.8  302.51  5019.8  303.51  5040.6  302.67  5090.2  304.18
  5133.3  303.58  5218.1  304.79  5346.1  305.11  5459.6  306.32  5752.3  307.17
  5780.2  308.25  5816.3  307.15  5822.7  308.51  5830.7  308.94  5910.4  309.21
#Mann=3,-1,0
  3689.6    0.05       0  5002.4    0.03       0  5008.4    0.05       0
Bank Sta=5002.4,5008.4
Exp/Cntr=0.3,0.1

Type RM Length L Ch R = 1,2840,124,124,124
BEGIN DESCRIPTION:
UNT015 IN GIBB 4.0
END DESCRIPTION:
XS GIS Cut Line= 4
      3642740.14     10249234.97      3641884.08     10249490.47
      3641047.40     10249740.18      3640668.12     10250207.78
#Sta/Elev= 30
  3698.6  308.84  3821.8  307.84  3874.0  308.89  3917.6  306.70  3950.7  306.53
  4088.5  307.07  4093.7  306.51  4176.6  306.11  4259.4  306.30  4303.0  305.34
  4473.9  304.01  4578.5  304.19  4917.5  302.77  4948.9  302.23  4969.7  300.74
  4997.0  300.17  5002.2  299.26  5018.9  298.51  5021.7  298.01  5024.9  298.51
  5042.8  300.49  5084.5  300.56  5101.6  301.49  5244.6  300.99  5277.7  302.28
  5428.7  303.62  5498.3  304.32  5547.8  303.62  5572.2  305.06  6067.2  312.57
#Mann=5,-1,0
  3698.6    0.05       0  5018.9    0.03       0  5024.9    0.05       0
  5428.7    0.08       0  5572.2    0.05       0
Bank Sta=5018.9,5024.9
Exp/Cntr=0.3,0.1

Type RM Length L Ch R = 1,2716,653,653,653
BEGIN DESCRIPTION:
UNT015 IN GIBB 4.1
END DESCRIPTION:
XS GIS Cut Line= 4
      3642760.96     10249136.01      3641885.09     10249393.19
      3640880.73     10249688.10      3640609.87     10250094.39
#Sta/Elev= 30
  3578.0  307.63  3686.5  306.47  3863.8  305.90  4035.4  305.55  4056.2  306.28
  4066.6  306.20  4074.5  305.13  4160.4  304.26  4223.7  304.56  4379.3  303.52
  4462.5  304.27  4639.9  302.27  4942.1  302.09  4961.1  300.39  4966.3  300.70
  4983.8  299.46  4996.7  296.84  4999.5  296.34  5002.7  296.84  5004.9  298.50
  5015.1  300.17  5046.3  301.69  5066.5  301.12  5323.3  302.59  5427.4  303.34
  5459.7  303.26  5484.1  304.66  5654.2  305.71  5870.5  308.19  6025.9  311.15
#Mann=5,-1,0
  3578.0    0.05       0  4996.7    0.04       0  5002.7    0.05       0
  5323.3    0.08       0  5427.4    0.05       0
Bank Sta=4996.7,5002.7
Exp/Cntr=0.3,0.1

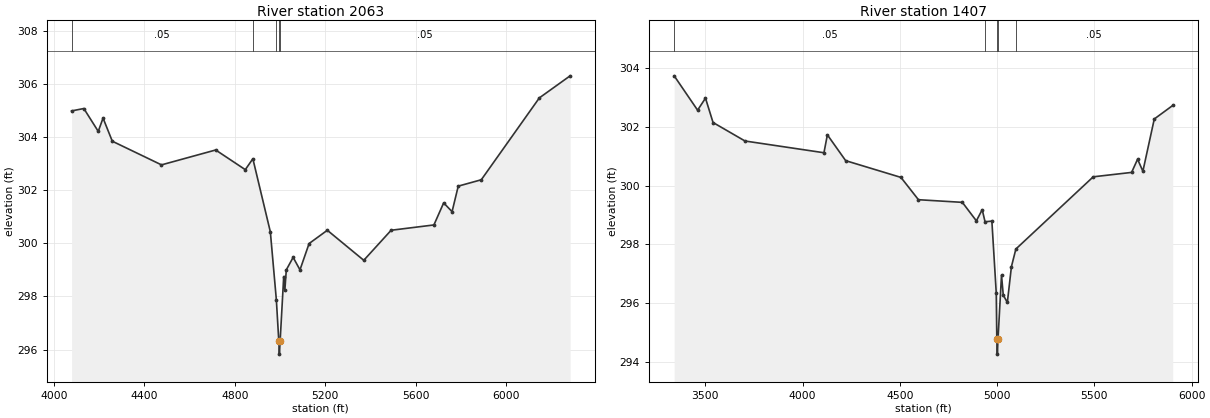
Type RM Length L Ch R = 1,2063,656,656,656
BEGIN DESCRIPTION:
UNT015 IN GIBB 3.0
END DESCRIPTION:
XS GIS Cut Line= 4
      3642385.93     10249151.64      3641729.69     10248974.56
      3640885.94     10249078.73      3640547.41     10249662.04
#Sta/Elev= 30
  4078.0  304.98  4132.1  305.07  4195.9  304.21  4217.1  304.71  4258.0  303.84
  4475.5  302.95  4715.1  303.51  4846.0  302.77  4879.5  303.18  4956.8  300.43
  4983.4  297.87  4994.1  296.33  4996.8  295.83  5000.1  296.33  5015.9  298.75
  5020.9  298.23  5027.3  299.00  5057.6  299.47  5087.8  299.00  5128.1  299.99
  5208.7  300.49  5369.9  299.36  5490.8  300.49  5680.0  300.69  5723.1  301.52
  5760.3  301.19  5787.6  302.15  5889.5  302.39  6146.2  305.47  6282.3  306.30
#Mann=5,-1,0
  4078.0    0.05       0  4879.5    0.12       0  4983.4    0.05       0
  4994.1    0.03       0  5000.1    0.05       0
Bank Sta=4994.1,5000.1
Exp/Cntr=0.3,0.1

Type RM Length L Ch R = 1,1407,0,0,0
BEGIN DESCRIPTION:
UNT015 IN GIBB 1.0
END DESCRIPTION:
XS GIS Cut Line= 4
      3642820.77     10248521.27      3641536.07     10248299.05
      3641020.54     10248642.78      3640696.46     10249193.75
#Sta/Elev= 30
  3340.0  303.74  3460.4  302.57  3501.0  302.98  3539.8  302.15  3704.0  301.52
  4109.9  301.12  4127.5  301.73  4221.6  300.85  4505.7  300.28  4595.6  299.52
  4821.3  299.43  4893.4  298.80  4923.4  299.18  4937.9  298.77  4973.1  298.79
  4995.5  296.35  4998.5  294.76  5001.3  294.26  5004.5  294.76  5022.6  296.95
  5031.6  296.27  5052.6  296.02  5073.6  297.24  5096.4  297.84  5494.1  300.30
  5691.3  300.45  5722.1  300.90  5749.3  300.49  5807.9  302.27  5902.6  302.73
#Mann=5,-1,0
  3340.0    0.05       0  4937.9    0.16       0  4998.5    0.07       0
  5004.5    0.16       0  5096.4    0.05       0
Bank Sta=4998.5,5004.5
Exp/Cntr=0.3,0.1

Chan Stop Cuts=-1