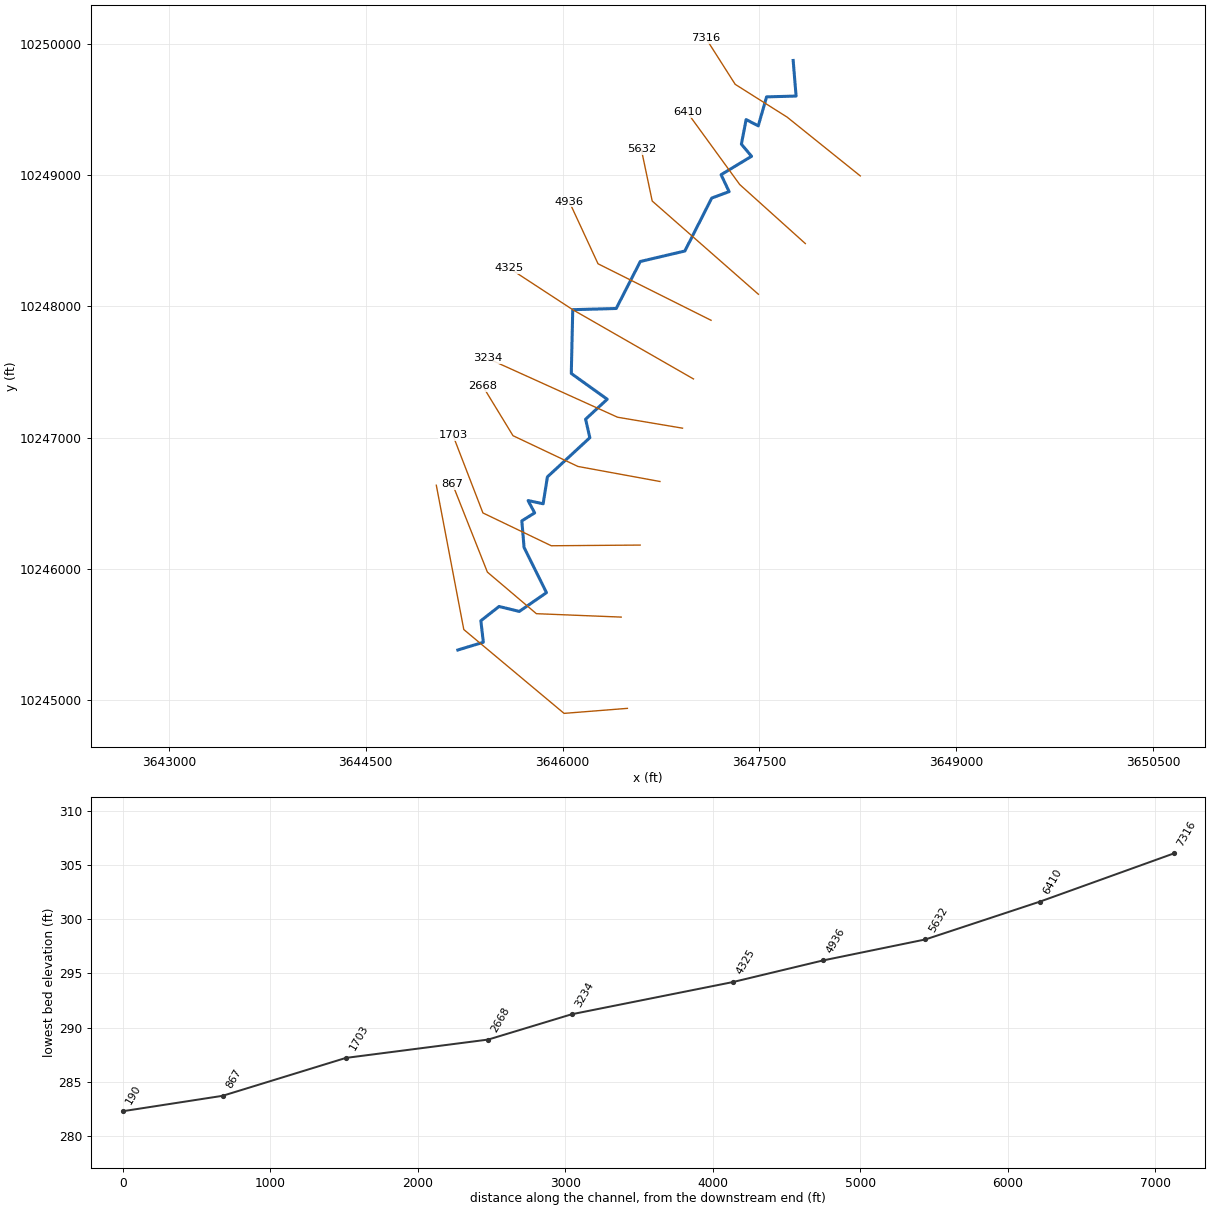
--- UNT016 IN GIBB.prj (project) ---

Proj Title=UNT016 IN GIBB Base Level Engineering
Current Plan=p01
Default Exp/Contr=0.3,0.1
English Units
Geom File=g01
Flow File=f01
Plan File=p01
BEGIN DESCRIPTION:
UNT016 IN GIBB
END DESCRIPTION:

--- UNT016 IN GIBB.p01 (plan) ---

Plan Title=Multiple Run
Short Identifier=Multiple
Geom File=g01
Flow File=f01
Subcritical Flow
K Sum by GR= 0
Std Step Tol= 0.01
Critical Tol= 0.01
Num of Std Step Trials= 20
Max Error Tol= 0.3
Flow Tol Ratio= 0.001
Split Flow NTrial= 30
Split Flow Tol= 0.02
Split Flow Ratio= 0.02
Log Output Level= 0
Friction Slope Method= 1
Unsteady Friction Slope Method= 2
Unsteady Bridges Friction Slope Method= 1
Parabolic Critical Depth
Global Vel Dist=  1 , 1 , 1
Global Log Level= 0
CheckData=True
Encroach Param= -1, 0, 0, 0
BEGIN DESCRIPTION:
Multiple Run
END DESCRIPTION:

--- UNT016 IN GIBB.f01 (steady flow) ---

Flow Title=Multiple
Number of Profiles=7
Profile Names=10-year,25-year,50-year,1pct_min,100-year,1pct_plu,500-year
River Rch & RM= UNT016 IN GIBB,Reach-1,7316
     473     622     740     647     874    1182    1219
River Rch & RM= UNT016 IN GIBB,Reach-1,4936
     617     823     989     871    1177    1592    1671
Boundary for River Rch & Prof#=UNT016 IN GIBB,Reach-1,1
Up Type=0
Dn Type=3
Dn Slope=0.005
Boundary for River Rch & Prof#=UNT016 IN GIBB,Reach-1,2
Up Type=0
Dn Type=3
Dn Slope=0.005
Boundary for River Rch & Prof#=UNT016 IN GIBB,Reach-1,3
Up Type=0
Dn Type=3
Dn Slope=0.005
Boundary for River Rch & Prof#=UNT016 IN GIBB,Reach-1,4
Up Type=0
Dn Type=3
Dn Slope=0.005
Boundary for River Rch & Prof#=UNT016 IN GIBB,Reach-1,5
Up Type=0
Dn Type=3
Dn Slope=0.005
Boundary for River Rch & Prof#=UNT016 IN GIBB,Reach-1,6
Up Type=0
Dn Type=3
Dn Slope=0.005
Boundary for River Rch & Prof#=UNT016 IN GIBB,Reach-1,7
Up Type=0
Dn Type=3
Dn Slope=0.005

--- UNT016 IN GIBB.g01 (geometry) ---

Geom Title=Existing Conditions

River Reach=UNT016 IN GIBB,Reach-1
Reach XY= 30
      3647756.86     10249872.88      3647779.09     10249601.92
      3647554.09     10249595.67      3647490.89     10249374.83
      3647398.53     10249422.75      3647362.27     10249235.51
      3647439.64     10249143.07      3647207.73     10249002.66
      3647268.84     10248873.73      3647136.42     10248824.78
      3646931.64     10248421.31      3646592.16     10248341.41
      3646408.71     10247983.41      3646077.46     10247974.34
      3646066.41     10247488.23      3646340.27     10247291.98
      3646175.39     10247140.09      3646207.72     10246999.02
      3645884.55     10246700.70      3645851.86     10246495.65
      3645737.02     10246520.21      3645787.40     10246426.24
      3645689.67     10246365.31      3645706.70     10246162.49
      3645877.45     10245818.61      3645670.32     10245675.46
      3645516.24     10245713.18      3645377.53     10245604.47
      3645396.21     10245440.56      3645202.11     10245381.64

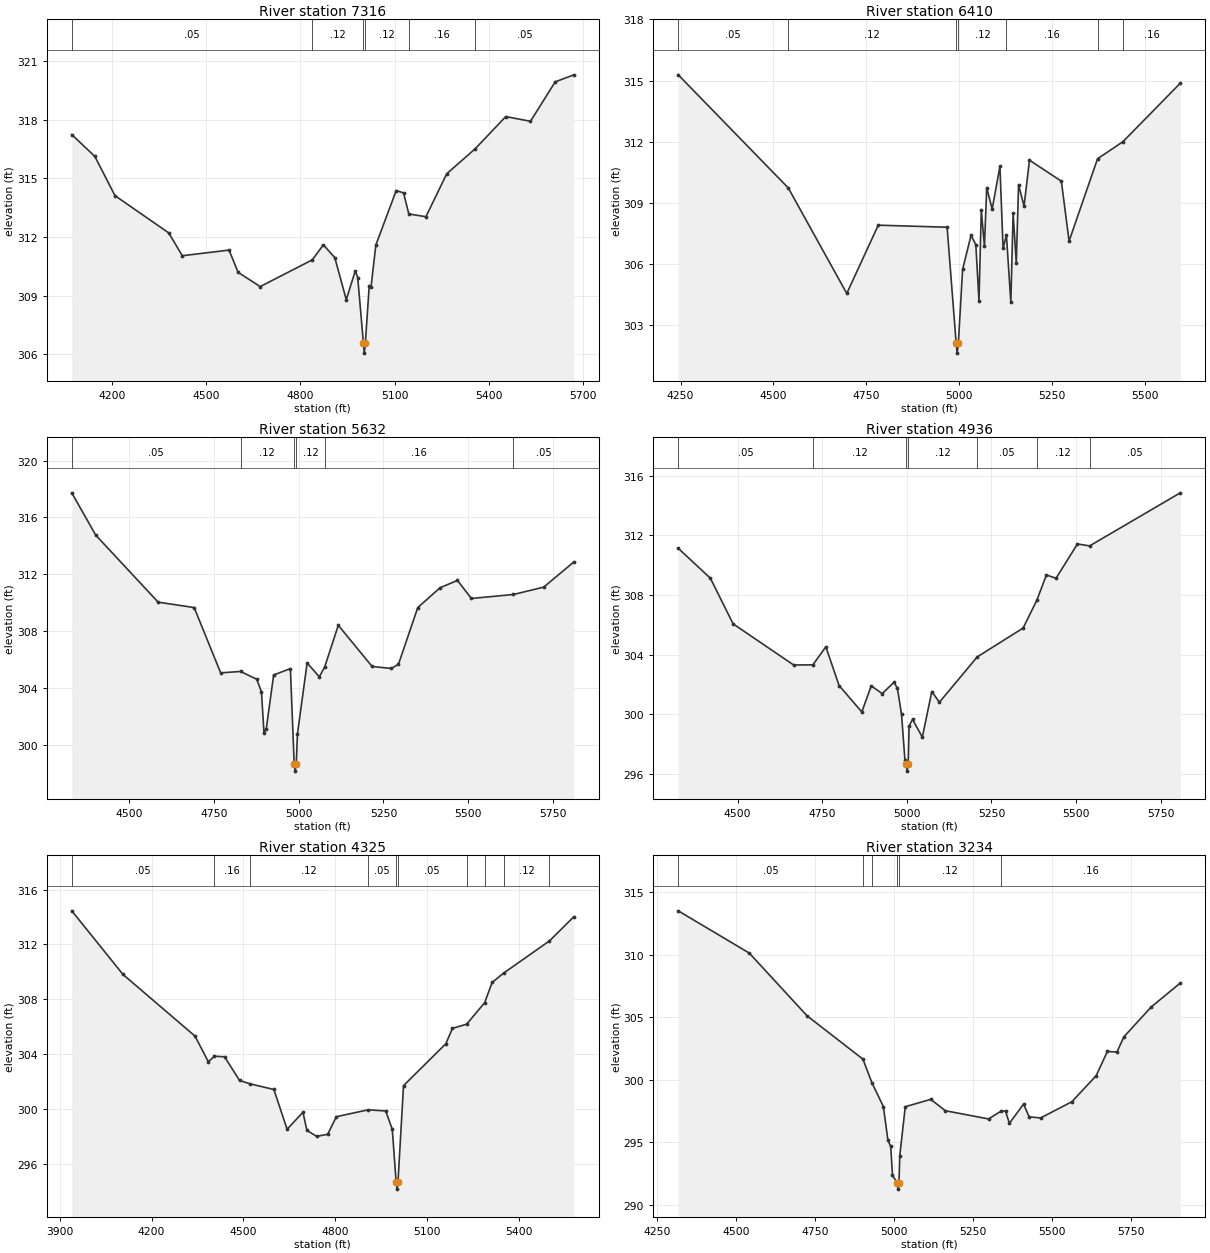
Type RM Length L Ch R = 1,7316,906,906,906
BEGIN DESCRIPTION:
UNT016 IN GIBB 12.0
END DESCRIPTION:
XS GIS Cut Line= 4
      3648268.10     10248993.52      3647710.84     10249441.41
      3647315.01     10249691.41      3647092.08     10250041.68
#Sta/Elev= 30
  4072.4  317.25  4145.9  316.13  4209.9  314.12  4381.1  312.21  4424.3  311.04
  4573.1  311.33  4601.9  310.19  4672.3  309.46  4838.2  310.83  4873.3  311.60
  4909.8  310.94  4946.2  308.79  4975.1  310.27  4982.7  309.92  5000.9  306.55
  5003.6  306.05  5006.9  306.55  5019.2  309.47  5025.1  309.44  5040.4  311.59
  5105.2  314.38  5128.6  314.26  5145.4  313.18  5199.8  313.04  5266.0  315.24
  5357.2  316.53  5453.9  318.17  5532.7  317.93  5611.4  319.95  5670.7  320.31
#Mann=6,-1,0
  4072.4    0.05       0  4838.2    0.12       0  5000.9    0.07       0
  5006.9    0.12       0  5145.4    0.16       0  5357.2    0.05       0
Bank Sta=5000.9,5006.9
Exp/Cntr=0.3,0.1

Type RM Length L Ch R = 1,6410,778,778,778
BEGIN DESCRIPTION:
UNT016 IN GIBB 10.0
END DESCRIPTION:
XS GIS Cut Line= 3
      3647849.42     10248478.08      3647349.40     10248928.10
      3646949.92     10249477.38
#Sta/Elev= 30
  4243.8  315.28  4540.0  309.73  4697.6  304.55  4782.4  307.90  4967.8  307.80
  4992.1  302.12  4994.8  301.62  4998.1  302.12  5009.5  305.73  5032.2  307.40
  5045.1  306.94  5053.6  304.19  5059.8  308.65  5068.3  306.86  5074.4  309.74
  5089.1  308.69  5110.0  310.79  5118.5  306.77  5127.5  307.41  5139.4  304.11
  5145.5  308.49  5154.0  306.05  5160.2  309.88  5174.9  308.84  5189.6  311.09
  5275.4  310.06  5296.2  307.12  5372.9  311.16  5441.3  312.00  5595.7  314.87
#Mann=7,-1,0
  4243.8    0.05       0  4540.0    0.12       0  4992.1    0.07       0
  4998.1    0.12       0  5127.5    0.16       0  5372.9    0.12       0
  5441.3    0.16       0
Bank Sta=4992.1,4998.1
Exp/Cntr=0.3,0.1

Type RM Length L Ch R = 1,5632,696,696,696
BEGIN DESCRIPTION:
UNT016 IN GIBB 9.0
END DESCRIPTION:
XS GIS Cut Line= 3
      3647492.09     10248091.66      3646682.81     10248802.34
      3646599.63     10249197.44
#Sta/Elev= 30
  4330.9  317.73  4401.6  314.75  4585.7  310.03  4691.9  309.65  4770.1  305.05
  4828.7  305.15  4876.5  304.60  4890.3  303.72  4897.8  300.84  4904.5  301.10
  4926.3  304.90  4975.7  305.35  4986.9  298.63  4989.6  298.13  4992.9  298.63
  4996.5  300.74  5025.0  305.75  5061.0  304.77  5076.9  305.47  5117.0  308.40
  5216.7  305.50  5273.6  305.36  5294.5  305.66  5351.4  309.65  5417.4  311.05
  5468.5  311.56  5509.4  310.29  5633.7  310.57  5722.9  311.09  5811.7  312.86
#Mann=6,-1,0
  4330.9    0.05       0  4828.7    0.12       0  4986.9    0.07       0
  4992.9    0.12       0  5076.9    0.16       0  5633.7    0.05       0
Bank Sta=4986.9,4992.9
Exp/Cntr=0.3,0.1

Type RM Length L Ch R = 1,4936,611,611,611
BEGIN DESCRIPTION:
UNT016 IN GIBB 7.0
END DESCRIPTION:
XS GIS Cut Line= 3
      3647131.12     10247893.64      3646269.97     10248324.21
      3646051.23     10248796.41
#Sta/Elev= 30
  4324.6  311.14  4419.6  309.13  4486.7  306.07  4665.6  303.31  4722.4  303.32
  4760.6  304.53  4799.8  301.93  4866.9  300.16  4894.8  301.91  4927.2  301.39
  4961.9  302.15  4972.0  301.76  4984.3  299.99  4994.3  296.93  4998.0  296.69
  5000.8  296.19  5004.0  296.69  5006.6  299.22  5016.7  299.66  5045.7  298.47
  5073.7  301.53  5096.1  300.81  5207.8  303.85  5343.5  305.79  5384.3  307.67
  5412.2  309.35  5440.7  309.13  5503.9  311.43  5539.9  311.30  5807.8  314.86
#Mann=7,-1,0
  4324.6    0.05       0  4722.4    0.12       0  4998.0    0.07       0
  5004.0    0.12       0  5207.8    0.05       0  5384.3    0.12       0
  5539.9    0.05       0
Bank Sta=4998,5004
Exp/Cntr=0.3,0.1

Type RM Length L Ch R = 1,4325,1091,1091,1091
BEGIN DESCRIPTION:
UNT016 IN GIBB 6.0
END DESCRIPTION:
XS GIS Cut Line= 3
      3646997.33     10247446.61      3646077.46     10247974.34
      3645592.08     10248291.66
#Sta/Elev= 30
  3939.5  314.45  4106.9  309.82  4342.4  305.33  4385.5  303.47  4405.7  303.87
  4438.7  303.83  4487.6  302.11  4522.2  301.86  4599.8  301.45  4643.0  298.56
  4694.9  299.79  4707.7  298.48  4739.3  298.04  4775.6  298.19  4804.0  299.47
  4907.5  299.97  4965.1  299.89  4986.7  298.55  4999.3  294.70  5002.1  294.20
  5005.3  294.70  5023.4  301.73  5161.7  304.78  5183.3  305.90  5229.6  306.20
  5288.5  307.77  5313.0  309.24  5350.6  309.92  5500.2  312.26  5579.9  314.02
#Mann=10,-1,0
  3939.5    0.05       0  4405.7    0.16       0  4522.2    0.12       0
  4907.5    0.05       0  4999.3    0.03       0  5005.3    0.05       0
  5229.6    0.12       0  5288.5    0.05       0  5350.6    0.12       0
  5500.2    0.05       0
Bank Sta=4999.3,5005.3
Exp/Cntr=0.3,0.1

Type RM Length L Ch R = 1,3234,566,566,566
BEGIN DESCRIPTION:
UNT016 IN GIBB 4.0
END DESCRIPTION:
XS GIS Cut Line= 3
      3646913.94     10247071.62      3646419.18     10247154.95
      3645429.56     10247602.88
#Sta/Elev= 30
  4317.3  313.53  4542.3  310.14  4724.8  305.12  4901.5  301.65  4929.7  299.77
  4966.3  297.84  4980.5  295.15  4989.4  294.66  4994.9  292.37  5009.5  291.74
  5012.3  291.24  5015.5  291.74  5018.0  293.93  5035.4  297.84  5115.9  298.43
  5162.1  297.52  5298.8  296.86  5339.4  297.50  5352.4  297.49  5364.7  296.51
  5409.6  298.05  5427.2  297.03  5463.4  296.94  5562.2  298.24  5639.1  300.32
  5674.7  302.27  5704.9  302.22  5726.9  303.44  5813.3  305.83  5905.3  307.75
#Mann=6,-1,0
  4317.3    0.05       0  4901.5    0.16       0  4929.7    0.12       0
  5009.5    0.07       0  5015.5    0.12       0  5339.4    0.16       0
Bank Sta=5009.5,5015.5
Exp/Cntr=0.3,0.1

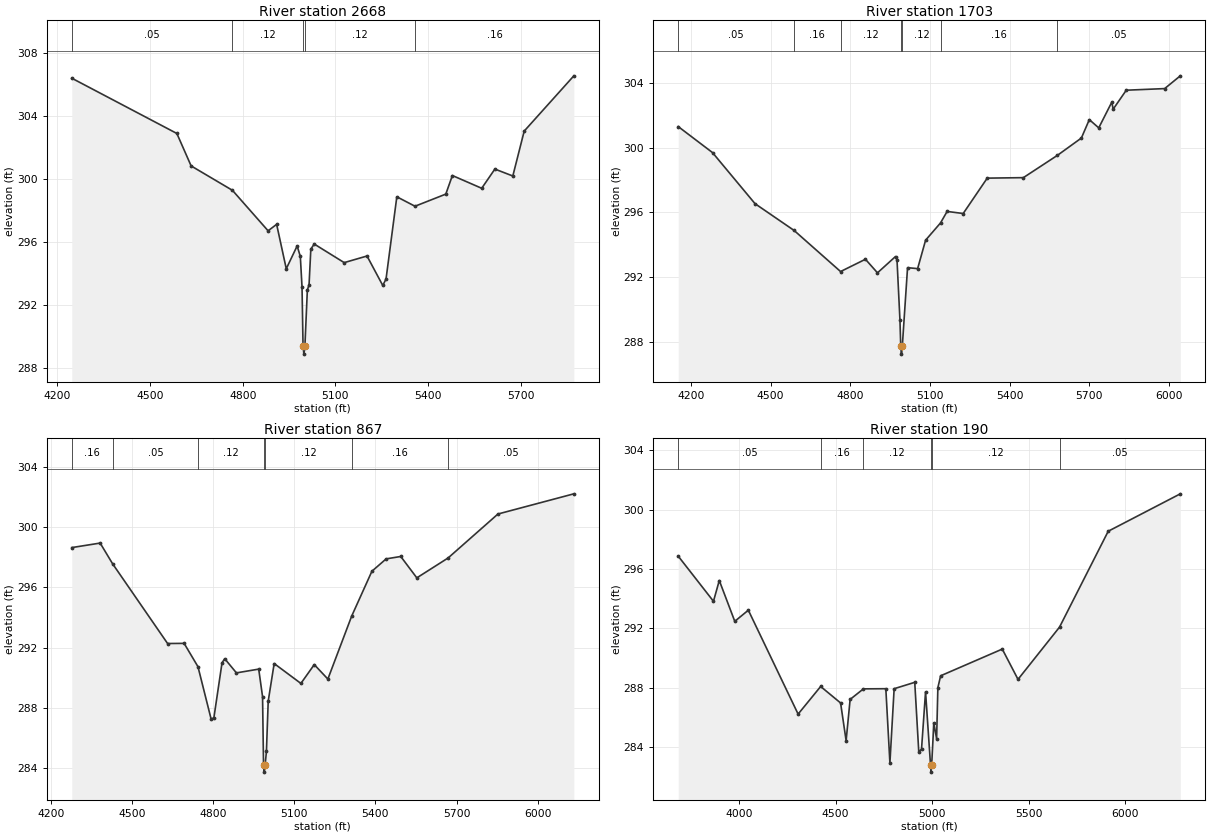
Type RM Length L Ch R = 1,2668,965,965,965
BEGIN DESCRIPTION:
UNT016 IN GIBB 3.0
END DESCRIPTION:
XS GIS Cut Line= 4
      3646742.05     10246665.38      3646117.09     10246779.95
      3645622.30     10247014.33      3645392.09     10247391.68
#Sta/Elev= 30
  4246.8  306.43  4586.9  302.92  4633.1  300.86  4766.8  299.31  4882.2  296.74
  4909.8  297.15  4941.0  294.33  4976.2  295.78  4986.5  295.11  4992.0  293.17
  4995.3  289.41  4998.1  288.91  5001.3  289.41  5009.2  292.97  5014.8  293.33
  5020.5  295.58  5031.5  295.90  5128.5  294.72  5202.3  295.14  5253.3  293.27
  5263.9  293.68  5298.8  298.90  5357.6  298.30  5457.3  299.07  5478.6  300.25
  5573.5  299.44  5616.1  300.66  5674.2  300.22  5711.0  303.07  5871.7  306.58
#Mann=5,-1,0
  4246.8    0.05       0  4766.8    0.12       0  4995.3    0.07       0
  5001.3    0.12       0  5357.6    0.16       0
Bank Sta=4995.3,5001.3
Exp/Cntr=0.3,0.1

Type RM Length L Ch R = 1,1703,836,836,836
BEGIN DESCRIPTION:
UNT016 IN GIBB 2.0
END DESCRIPTION:
XS GIS Cut Line= 4
      3646591.07     10246181.00      3645913.97     10246175.79
      3645393.13     10246425.79      3645164.54     10247018.05
#Sta/Elev= 30
  4152.5  301.30  4281.5  299.69  4441.5  296.53  4588.8  294.87  4763.5  292.33
  4857.1  293.09  4902.4  292.25  4970.3  293.26  4975.9  293.05  4987.0  289.32
  4989.9  287.72  4992.7  287.22  4995.9  287.72  5015.6  292.57  5053.5  292.51
  5083.5  294.27  5139.8  295.34  5164.5  296.05  5225.0  295.92  5315.5  298.11
  5451.5  298.14  5579.7  299.52  5669.8  300.59  5699.7  301.73  5735.2  301.22
  5784.3  302.81  5789.6  302.38  5838.8  303.55  5983.3  303.65  6042.2  304.44
#Mann=7,-1,0
  4152.5    0.05       0  4588.8    0.16       0  4763.5    0.12       0
  4989.9    0.07       0  4995.9    0.12       0  5139.8    0.16       0
  5579.7    0.05       0
Bank Sta=4989.9,4995.9
Exp/Cntr=0.3,0.1

Type RM Length L Ch R = 1,867,677,677,677
BEGIN DESCRIPTION:
Mapping XS c0ed82e2
END DESCRIPTION:
XS GIS Cut Line= 4
      3646447.05     10245632.23      3645800.33     10245658.27
      3645427.07     10245975.11      3645162.30     10246643.54
#Sta/Elev= 30
  4277.7  298.64  4382.6  298.94  4428.8  297.56  4631.9  292.27  4693.0  292.28
  4744.2  290.73  4793.1  287.23  4803.1  287.35  4833.1  290.99  4843.1  291.26
  4886.3  290.32  4968.7  290.57  4982.9  288.74  4986.5  284.23  4989.2  283.73
  4992.5  284.23  4997.2  285.10  5003.8  288.44  5025.8  290.94  5124.6  289.62
  5174.0  290.87  5224.3  289.91  5312.3  294.09  5387.1  297.07  5439.7  297.89
  5493.7  298.05  5553.1  296.63  5668.7  297.95  5853.0  300.87  6133.5  302.21
#Mann=7,-1,0
  4277.7    0.16       0  4428.8    0.05       0  4744.2    0.12       0
  4986.5    0.07       0  4992.5    0.12       0  5312.3    0.16       0
  5668.7    0.05       0
Bank Sta=4986.5,4992.5
Exp/Cntr=0.3,0.1

Type RM Length L Ch R = 1,190,0,0,0
BEGIN DESCRIPTION:
UNT016 IN GIBB 1.0
END DESCRIPTION:
XS GIS Cut Line= 4
      3646493.92     10244936.92      3646011.27     10244898.72
      3645247.38     10245537.61      3645038.00     10246637.05
#Sta/Elev= 30
  3685.0  296.86  3867.4  293.82  3897.5  295.22  3977.7  292.47  4047.9  293.22
  4305.6  286.22  4422.3  288.08  4525.5  286.97  4554.1  284.43  4574.9  287.21
  4643.7  287.92  4759.7  287.93  4780.8  282.93  4802.7  287.93  4909.4  288.36
  4930.2  283.68  4944.5  283.86  4965.3  287.72  4991.0  282.81  4993.7  282.31
  4997.0  282.81  5008.3  285.62  5022.6  284.56  5029.1  288.00  5043.4  288.80
  5362.5  290.60  5444.0  288.56  5658.9  292.08  5911.0  298.54  6284.2  301.06
#Mann=6,-1,0
  3685.0    0.05       0  4422.3    0.16       0  4643.7    0.12       0
  4991.0    0.07       0  4997.0    0.12       0  5658.9    0.05       0
Bank Sta=4991,4997
Exp/Cntr=0.3,0.1

Chan Stop Cuts=-1