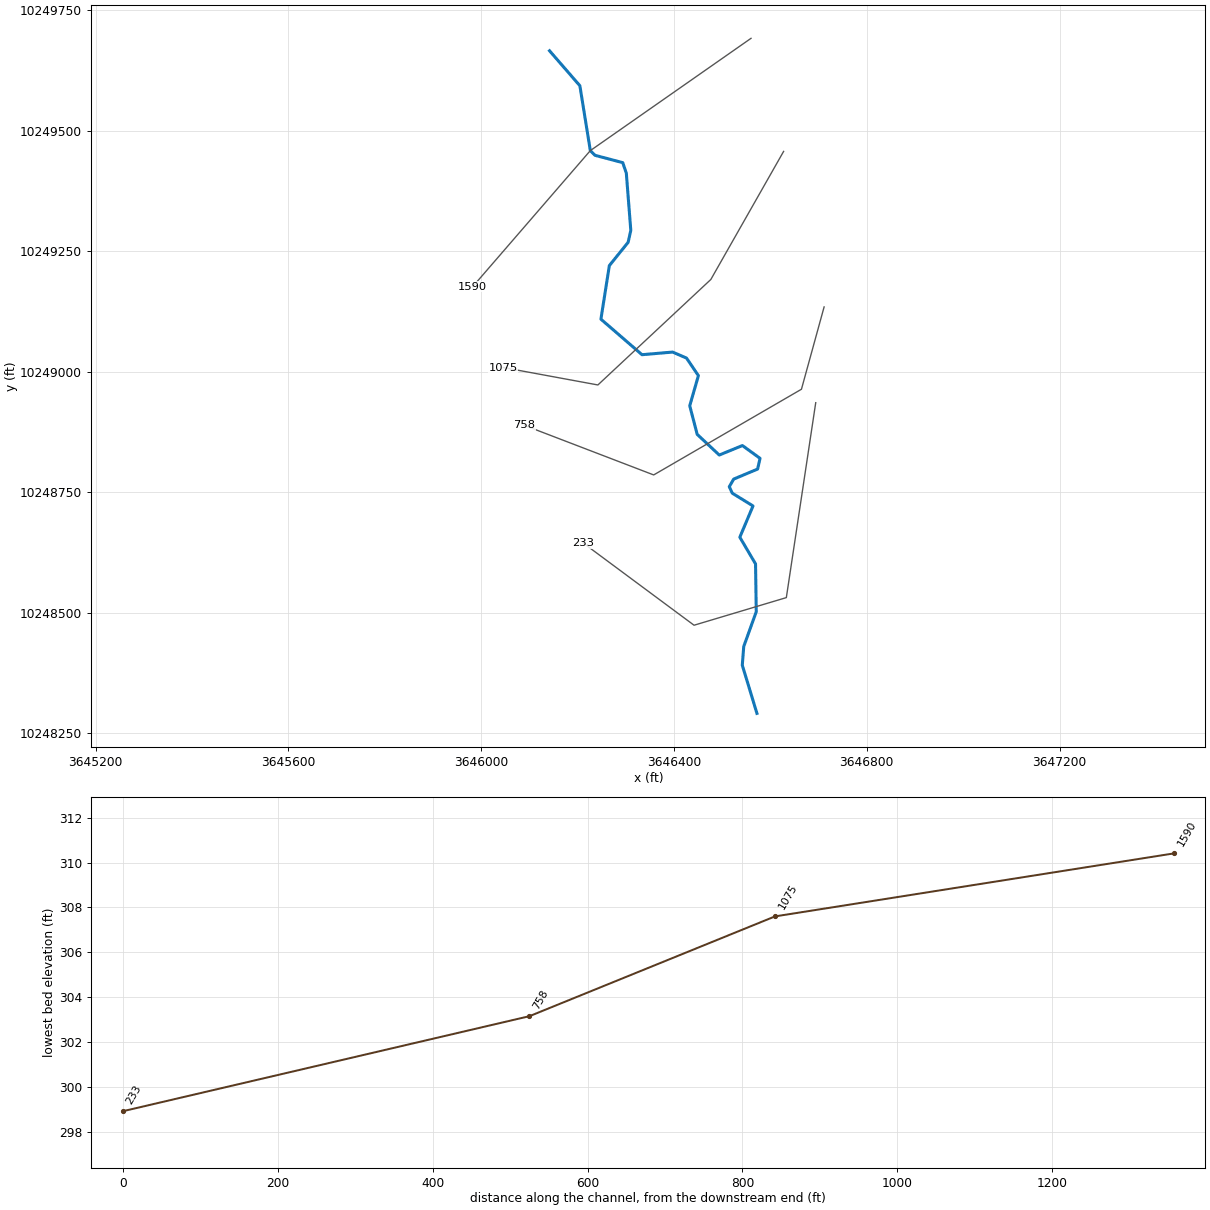
--- UNT017 IN GIBB.prj (project) ---

Proj Title=UNT017 IN GIBB Base Level Engineering
Current Plan=p01
Default Exp/Contr=0.3,0.1
English Units
Geom File=g01
Flow File=f01
Plan File=p01
BEGIN DESCRIPTION:
UNT017 IN GIBB
END DESCRIPTION:

--- UNT017 IN GIBB.p01 (plan) ---

Plan Title=Multiple Run
Short Identifier=Multiple
Geom File=g01
Flow File=f01
Subcritical Flow
K Sum by GR= 0
Std Step Tol= 0.01
Critical Tol= 0.01
Num of Std Step Trials= 20
Max Error Tol= 0.3
Flow Tol Ratio= 0.001
Split Flow NTrial= 30
Split Flow Tol= 0.02
Split Flow Ratio= 0.02
Log Output Level= 0
Friction Slope Method= 1
Unsteady Friction Slope Method= 2
Unsteady Bridges Friction Slope Method= 1
Parabolic Critical Depth
Global Vel Dist=  1 , 1 , 1
Global Log Level= 0
CheckData=True
Encroach Param= -1, 0, 0, 0
BEGIN DESCRIPTION:
Multiple Run
END DESCRIPTION:

--- UNT017 IN GIBB.f01 (steady flow) ---

Flow Title=Multiple
Number of Profiles=7
Profile Names=10-year,25-year,50-year,1pct_min,100-year,1pct_plu,500-year
River Rch & RM= UNT017 IN GIBB,Reach-1,1590
     147     181     205     172     233     315     298
Boundary for River Rch & Prof#=UNT017 IN GIBB,Reach-1,1
Up Type=0
Dn Type=3
Dn Slope=0.005
Boundary for River Rch & Prof#=UNT017 IN GIBB,Reach-1,2
Up Type=0
Dn Type=3
Dn Slope=0.005
Boundary for River Rch & Prof#=UNT017 IN GIBB,Reach-1,3
Up Type=0
Dn Type=3
Dn Slope=0.005
Boundary for River Rch & Prof#=UNT017 IN GIBB,Reach-1,4
Up Type=0
Dn Type=3
Dn Slope=0.005
Boundary for River Rch & Prof#=UNT017 IN GIBB,Reach-1,5
Up Type=0
Dn Type=3
Dn Slope=0.005
Boundary for River Rch & Prof#=UNT017 IN GIBB,Reach-1,6
Up Type=0
Dn Type=3
Dn Slope=0.005
Boundary for River Rch & Prof#=UNT017 IN GIBB,Reach-1,7
Up Type=0
Dn Type=3
Dn Slope=0.005

--- UNT017 IN GIBB.g01 (geometry) ---

Geom Title=Existing Conditions

River Reach=UNT017 IN GIBB,Reach-1
Reach XY= 30
      3646141.75     10249665.64      3646204.68     10249593.16
      3646226.38     10249458.61      3646236.14     10249448.85
      3646293.65     10249433.66      3646301.12     10249411.70
      3646310.35     10249293.13      3646304.80     10249268.47
      3646265.86     10249220.16      3646248.36     10249109.10
      3646333.61     10249035.42      3646397.21     10249040.85
      3646426.01     10249028.40      3646450.65     10248991.99
      3646432.69     10248929.49      3646448.16     10248870.19
      3646493.99     10248827.34      3646542.00     10248847.04
      3646578.60     10248820.47      3646573.50     10248798.24
      3646523.95     10248777.48      3646514.72     10248761.69
      3646520.98     10248748.23      3646564.00     10248721.75
      3646536.59     10248656.98      3646569.23     10248601.63
      3646570.72     10248502.32      3646544.75     10248430.42
      3646541.71     10248391.68      3646572.11     10248291.64

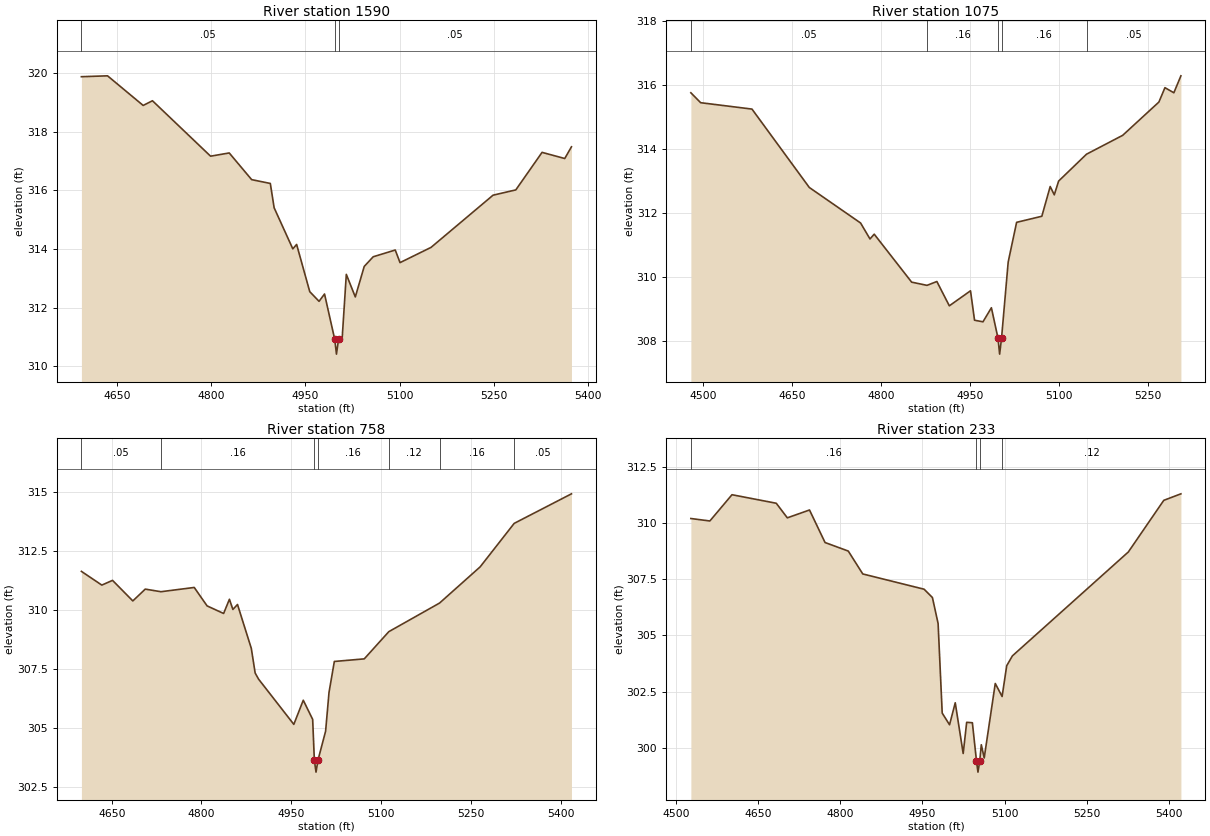
Type RM Length L Ch R = 1,1590,515,515,515
BEGIN DESCRIPTION:
UNT017 IN GIBB 3.0
END DESCRIPTION:
XS GIS Cut Line= 3
      3646559.84     10249691.44      3646226.38     10249458.61
      3645982.06     10249176.23
#Sta/Elev= 30
  4593.3  319.87  4634.9  319.90  4691.6  318.89  4706.4  319.05  4798.9  317.16
  4828.6  317.27  4864.3  316.36  4894.0  316.23  4900.1  315.40  4929.8  314.00
  4935.9  314.15  4956.8  312.54  4971.6  312.21  4980.3  312.46  4996.6  310.91
  4999.3  310.41  5002.6  310.91  5008.4  310.95  5015.0  313.13  5029.3  312.36
  5043.5  313.40  5057.8  313.73  5092.9  313.96  5100.5  313.53  5149.9  314.05
  5248.6  315.83  5284.8  316.01  5326.6  317.29  5362.7  317.08  5373.4  317.48
#Mann=3,-1,0
  4593.3    0.05       0  4996.6    0.03       0  5002.6    0.05       0
Bank Sta=4996.6,5002.6
Exp/Cntr=0.3,0.1

Type RM Length L Ch R = 1,1075,317,317,317
BEGIN DESCRIPTION:
UNT017 IN GIBB 2.0
END DESCRIPTION:
XS GIS Cut Line= 4
      3646627.50     10249457.02      3646476.47     10249191.41
      3646242.09     10248972.66      3646045.65     10249008.85
#Sta/Elev= 30
  4479.4  315.77  4495.9  315.46  4582.4  315.26  4679.0  312.81  4765.4  311.70
  4781.3  311.20  4788.4  311.35  4851.5  309.85  4877.4  309.75  4894.0  309.87
  4915.0  309.11  4950.7  309.58  4957.5  308.66  4971.7  308.61  4985.9  309.05
  4997.0  308.10  4999.8  307.60  5003.0  308.10  5014.2  310.48  5028.4  311.72
  5070.9  311.91  5085.0  312.84  5091.9  312.58  5099.2  313.01  5146.2  313.85
  5207.2  314.44  5268.2  315.48  5278.4  315.93  5293.4  315.77  5305.3  316.30
#Mann=5,-1,0
  4479.4    0.05       0  4877.4    0.16       0  4997.0    0.07       0
  5003.0    0.16       0  5146.2    0.05       0
Bank Sta=4997,5003
Exp/Cntr=0.3,0.1

Type RM Length L Ch R = 1,758,525,525,525
BEGIN DESCRIPTION:
UNT017 IN GIBB 2.1
END DESCRIPTION:
XS GIS Cut Line= 4
      3646711.54     10249134.50      3646664.51     10248963.79
      3646357.87     10248786.08      3646089.57     10248888.86
#Sta/Elev= 30
  4599.4  311.64  4633.5  311.06  4651.4  311.26  4685.3  310.39  4706.1  310.89
  4732.2  310.78  4787.9  310.96  4809.4  310.18  4837.0  309.86  4846.7  310.46
  4852.5  310.03  4860.2  310.24  4883.3  308.38  4889.7  307.34  4895.5  307.08
  4954.3  305.17  4970.1  306.19  4985.8  305.38  4988.6  303.65  4991.4  303.15
  4994.6  303.65  5007.4  304.88  5013.1  306.52  5022.0  307.83  5072.0  307.94
  5113.0  309.09  5197.8  310.30  5265.6  311.83  5322.5  313.67  5418.2  314.92
#Mann=7,-1,0
  4599.4    0.05       0  4732.2    0.16       0  4988.6    0.07       0
  4994.6    0.16       0  5113.0    0.12       0  5197.8    0.16       0
  5322.5    0.05       0
Bank Sta=4988.6,4994.6
Exp/Cntr=0.3,0.1

Type RM Length L Ch R = 1,233,0,0,0
BEGIN DESCRIPTION:
UNT017 IN GIBB 1.0
END DESCRIPTION:
XS GIS Cut Line= 4
      3646694.13     10248935.92      3646633.14     10248531.71
      3646441.60     10248474.43      3646211.52     10248644.95
#Sta/Elev= 30
  4527.1  310.21  4561.8  310.10  4602.2  311.27  4683.1  310.89  4703.3  310.24
  4743.8  310.59  4772.2  309.14  4814.6  308.76  4841.1  307.74  4953.1  307.06
  4968.3  306.69  4978.7  305.53  4986.2  301.54  4999.6  301.02  5010.0  302.00
  5024.5  299.74  5030.9  301.13  5041.3  301.11  5048.8  299.41  5051.5  298.91
  5054.8  299.41  5057.6  300.13  5062.9  299.54  5083.1  302.86  5095.6  302.28
  5104.0  303.65  5114.4  304.09  5326.2  308.72  5390.9  311.02  5422.2  311.31
#Mann=4,-1,0
  4527.1    0.16       0  5048.8    0.07       0  5054.8    0.16       0
  5095.6    0.12       0
Bank Sta=5048.8,5054.8
Exp/Cntr=0.3,0.1

Chan Stop Cuts=-1