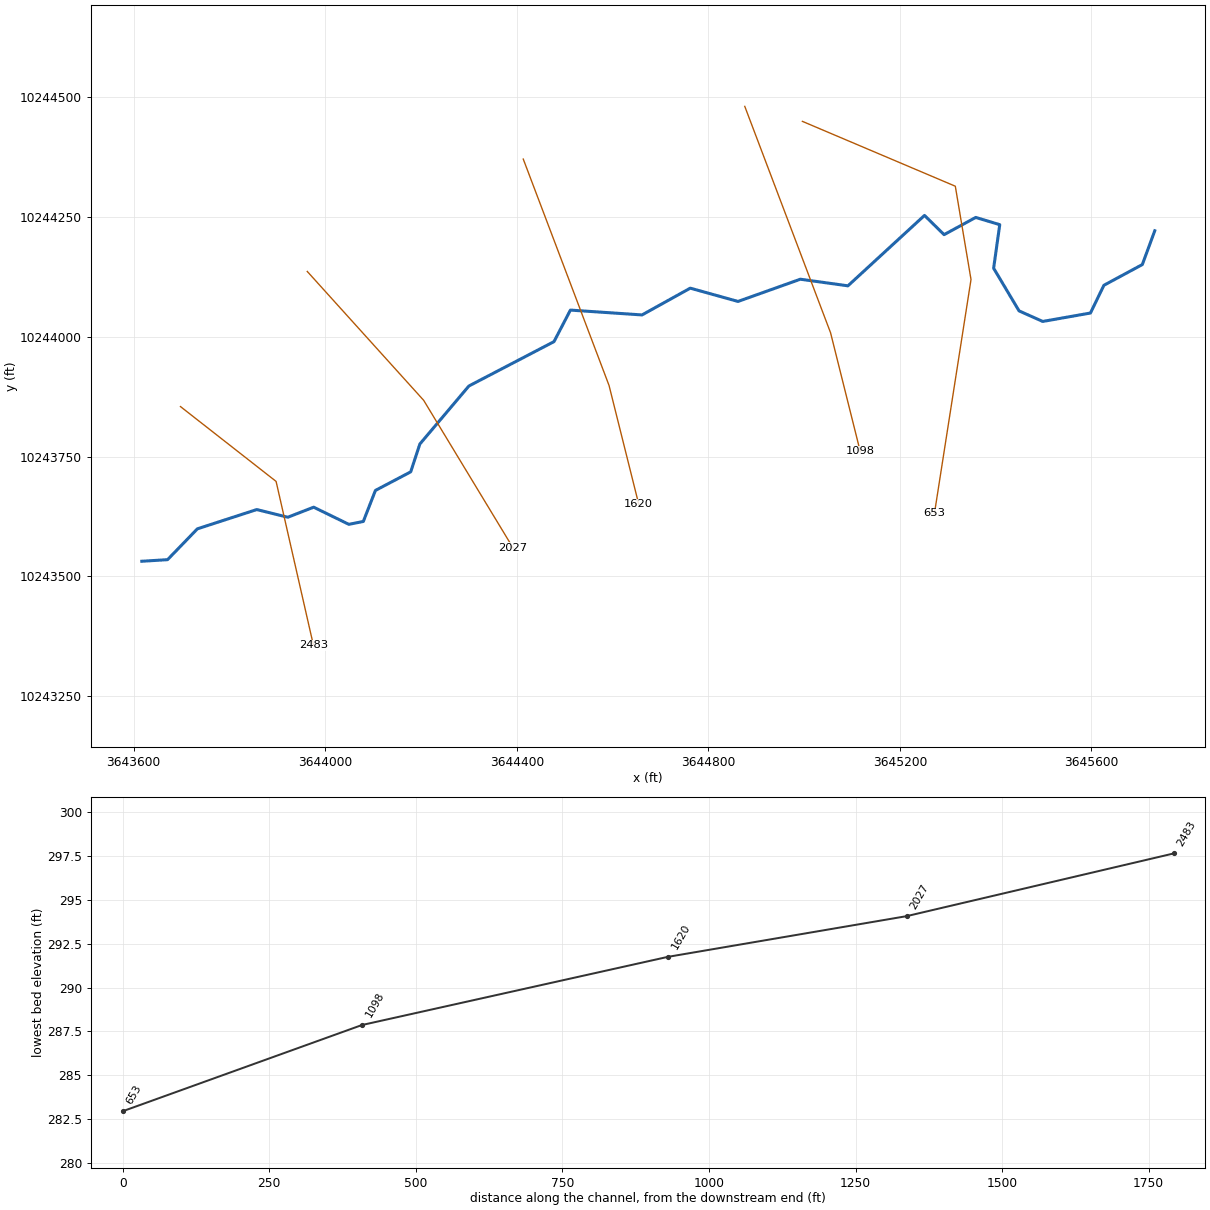
--- UNT018 IN GIBB.prj (project) ---

Proj Title=UNT018 IN GIBB Base Level Engineering
Current Plan=p01
Default Exp/Contr=0.3,0.1
English Units
Geom File=g01
Flow File=f01
Plan File=p01
Y Axis Title=Elevation
X Axis Title(PF)=Main Channel Distance
X Axis Title(XS)=Station
BEGIN DESCRIPTION:
UNT018 IN GIBB
END DESCRIPTION:
DSS Export Rating Curves= 0
DSS Export Rating Curve Sorted= 0
DSS Export Volume Flow Curves= 0
DXF OffsetX= 0
DXF OffsetY= 0
DXF ScaleX= 1
DXF ScaleY= 10

--- UNT018 IN GIBB.p01 (plan) ---

Plan Title=Multiple Run
Short Identifier=Multiple
Geom File=g01
Flow File=f01
Subcritical Flow
K Sum by GR= 0
Std Step Tol= 0.01
Critical Tol= 0.01
Num of Std Step Trials= 20
Max Error Tol= 0.3
Flow Tol Ratio= 0.001
Split Flow NTrial= 30
Split Flow Tol= 0.02
Split Flow Ratio= 0.02
Log Output Level= 0
Friction Slope Method= 1
Unsteady Friction Slope Method= 2
Unsteady Bridges Friction Slope Method= 1
Parabolic Critical Depth
Global Vel Dist=  1 , 1 , 1
Global Log Level= 0
CheckData=True
Encroach Param= -1, 0, 0, 0
BEGIN DESCRIPTION:
Multiple Run
END DESCRIPTION:

--- UNT018 IN GIBB.f01 (steady flow) ---

Flow Title=Multiple
Program Version=4.10
Number of Profiles= 7
Profile Names=10-year,25-year,50-year,1pct_min,100-year,1pct_plu,500-year
River Rch & RM=UNT018 IN GIBB,Reach-1         ,2483
     197     246     283     240     324     439     426
Boundary for River Rch & Prof#=UNT018 IN GIBB,Reach-1         , 1
Up Type= 0
Dn Type= 3
Dn Slope=0.01
Boundary for River Rch & Prof#=UNT018 IN GIBB,Reach-1         , 2
Up Type= 0
Dn Type= 3
Dn Slope=0.01
Boundary for River Rch & Prof#=UNT018 IN GIBB,Reach-1         , 3
Up Type= 0
Dn Type= 3
Dn Slope=0.01
Boundary for River Rch & Prof#=UNT018 IN GIBB,Reach-1         , 4
Up Type= 0
Dn Type= 3
Dn Slope=0.01
Boundary for River Rch & Prof#=UNT018 IN GIBB,Reach-1         , 5
Up Type= 0
Dn Type= 3
Dn Slope=0.01
Boundary for River Rch & Prof#=UNT018 IN GIBB,Reach-1         , 6
Up Type= 0
Dn Type= 3
Dn Slope=0.01
Boundary for River Rch & Prof#=UNT018 IN GIBB,Reach-1         , 7
Up Type= 0
Dn Type= 3
Dn Slope=0.01
DSS Import GetInterval= 0
DSS Import GetPeak= 0
DSS Import FillOption= 0

--- UNT018 IN GIBB.g01 (geometry) ---

Geom Title=Existing Conditions
Program Version=4.10

River Reach=UNT018 IN GIBB  ,Reach-1
Reach XY= 30
      3643617.11     10243531.64      3643670.86     10243534.95
      3643733.12     10243599.32      3643857.13     10243639.58
      3643921.84     10243623.53      3643975.98     10243644.51
      3644049.35     10243608.73      3644079.61     10243614.73
       3644104.9     10243679.53      3644178.51     10243718.28
      3644197.65     10243776.41      3644300.02     10243897.55
      3644477.72      10243990.2      3644511.99     10244056.05
      3644661.51     10244045.95      3644762.25     10244101.85
      3644861.96     10244074.12      3644992.11     10244120.53
      3645091.45     10244106.71      3645251.32     10244253.75
      3645292.22     10244213.59      3645358.31     10244249.53
      3645408.45      10244234.4      3645395.66     10244143.45
      3645448.76     10244054.41      3645498.15     10244032.34
      3645597.82     10244049.93      3645625.91     10244107.86
      3645706.11      10244151.1      3645732.11     10244221.64

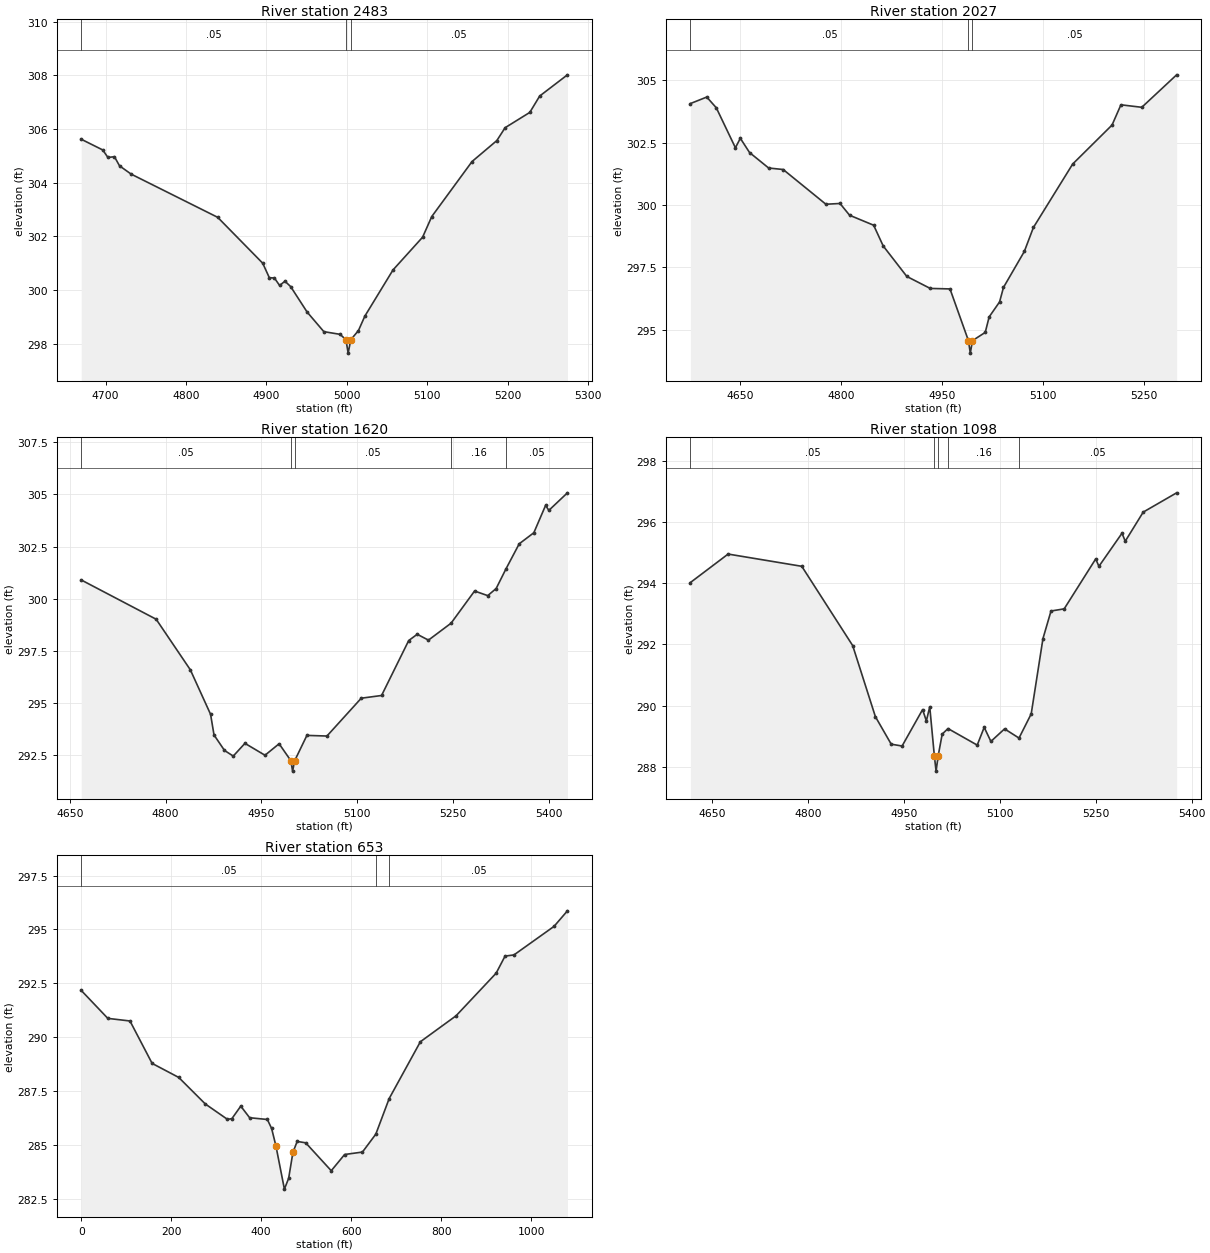
Type RM Length L Ch R = 1 ,2483    ,456,456,456
BEGIN DESCRIPTION:
UNT018 IN GIBB 4.0
END DESCRIPTION:
XS GIS Cut Line= 3
      3643697.83      10243854.6      3643897.47     10243698.36
      3643975.47     10243356.04
#Sta/Elev= 30
  4669.8  305.62  4696.6  305.22    4703  304.94  4711.1  304.97  4717.4  304.63
  4731.9  304.32  4839.5  302.71  4895.5     301  4903.7  300.46    4910  300.45
  4916.5  300.17  4923.1  300.33  4930.2  300.13  4950.7  299.18  4971.5  298.45
  4991.7  298.35    4999  298.15  5001.7  297.65    5005  298.15  5014.5  298.49
  5022.5  299.03  5057.5  300.75  5094.3  301.97  5105.7  302.74  5155.8  304.79
  5186.6  305.57  5196.9  306.05  5227.6  306.62  5239.9  307.23  5274.4  308.02
#Mann= 3 ,-1 , 0
  4669.8     .05       0    4999     .03       0    5005     .05       0
Bank Sta=4999,5005
XS Rating Curve= 0 ,0
Exp/Cntr=0.3,0.1

Type RM Length L Ch R = 1 ,2027    ,407,407,407
BEGIN DESCRIPTION:
UNT018 IN GIBB 3.0
END DESCRIPTION:
XS GIS Cut Line= 3
       3643962.6      10244136.7      3644205.63     10243867.63
      3644392.24     10243559.51
#Sta/Elev= 30
  4576.1  304.06  4600.4  304.32  4614.6  303.89    4643  302.29  4650.3  302.67
    4664   302.1  4692.4  301.48    4714  301.42  4777.5  300.03  4798.5  300.06
  4812.7  299.59  4848.5  299.19  4862.7  298.36  4897.8  297.14  4932.6  296.66
    4962  296.64  4989.4  294.57  4992.2  294.07  4995.4  294.57  5014.4   294.9
  5020.2  295.52  5035.7  296.12  5041.5   296.7  5072.5  298.14    5086   299.1
  5144.4  301.64  5202.9   303.2  5216.1  304.01  5247.1  303.91  5298.9  305.21
#Mann= 3 ,-1 , 0
  4576.1     .05       0  4989.4     .03       0  4995.4     .05       0
Bank Sta=4989.4,4995.4
XS Rating Curve= 0 ,0
Exp/Cntr=0.3,0.1

Type RM Length L Ch R = 1 ,1620    ,522,522,522
BEGIN DESCRIPTION:
UNT018 IN GIBB 2.0
END DESCRIPTION:
XS GIS Cut Line= 3
      3644413.55     10244371.35       3644592.7     10243898.61
       3644654.7     10243650.59
#Sta/Elev= 30
    4668   300.9  4785.3  299.02  4838.8   296.6  4870.5  294.47  4875.9  293.48
  4892.3  292.74    4906  292.47  4924.3  293.08  4955.7  292.51  4977.8  293.06
  4996.2  292.25  4998.9  291.75  5002.2  292.25  5021.3  293.46  5052.7  293.43
  5106.4  295.24  5138.2  295.37  5180.7     298    5194   298.3  5211.6  298.02
    5247  298.83  5283.8  300.37  5304.4  300.15  5317.6  300.49  5332.8  301.42
  5353.7  302.63  5376.6  303.16    5395  304.47  5400.1  304.23  5429.2  305.07
#Mann= 5 ,-1 , 0
    4668     .05       0  4996.2     .03       0  5002.2     .05       0
    5247     .16       0  5332.8     .05       0
Bank Sta=4996.2,5002.2
XS Rating Curve= 0 ,0
Exp/Cntr=0.3,0.1

Type RM Length L Ch R = 1 ,1098    ,408,408,408
BEGIN DESCRIPTION:
UNT018 IN GIBB 1.1
END DESCRIPTION:
XS GIS Cut Line= 3
      3644876.04     10244481.45      3645055.19     10244008.69
      3645117.14     10243760.88
#Sta/Elev= 30
  4615.5  294.02  4674.5  294.95  4789.8  294.55  4869.5  291.96    4905  289.64
  4929.8  288.74  4946.8  288.68  4978.9  289.87  4984.8   289.5  4990.1  289.96
  4997.3  288.36    5000  287.86  5003.3  288.36  5009.6  289.07  5018.7  289.25
  5064.4  288.71  5075.3  289.29  5085.8  288.83  5107.2  289.24  5129.8  288.94
  5148.9  289.73  5167.3  292.19  5179.9  293.09  5200.5  293.16  5249.8  294.79
  5254.9  294.55    5291  295.63  5296.1  295.37  5324.2  296.32  5376.5  296.95
#Mann= 5 ,-1 , 0
  4615.5     .05       0  4997.3     .03       0  5003.3     .05       0
  5018.7     .16       0  5129.8     .05       0
Bank Sta=4997.3,5003.3
XS Rating Curve= 0 ,0
Exp/Cntr=0.3,0.1

Type RM Length L Ch R = 1 ,653     ,0,0,0
BEGIN DESCRIPTION:
UNT018 IN GIBB 1.0
END DESCRIPTION:
XS GIS Cut Line= 4
      3644996.41      10244450.1      3645315.65     10244314.72
      3645348.43     10244119.92      3645272.18     10243632.14
#Sta/Elev= 30
       0292.169359.10907290.8712108.3666290.7499157.6242288.7805216.7333288.1292
275.8423286.8969325.0999286.1823334.9514286.2167354.6544286.7966374.3575286.2587
413.7635286.1765423.2317285.7588432.6998284.9591451.6362282.9435461.1044283.4469
470.5725284.6485480.0407285.1584498.9771285.0938555.7861283.7979585.5051284.5511
625.1304284.6644654.8494285.4965684.5683287.1499753.9126289.7863833.1631290.9899
922.3201292.9694942.1327293.7623961.9454 293.8171051.102295.14381080.821295.8644
#Mann= 3 ,-1 , 0
       0     .05       0654.8494     .03       0684.5683     .05       0
Bank Sta=432.6998,470.5725
XS Rating Curve= 0 ,0
Exp/Cntr=0.3,0.1
Stream Node=UNT018 IN GIBB  ,Reach-1         , 0 , 0 ,Upstream end
Stream Node=UNT018 IN GIBB  ,Reach-1         , 0 , 1 ,Downstream end

Chan Stop Cuts=-1
Use User Specified Reach Order=0
Composite Channel Slope=5