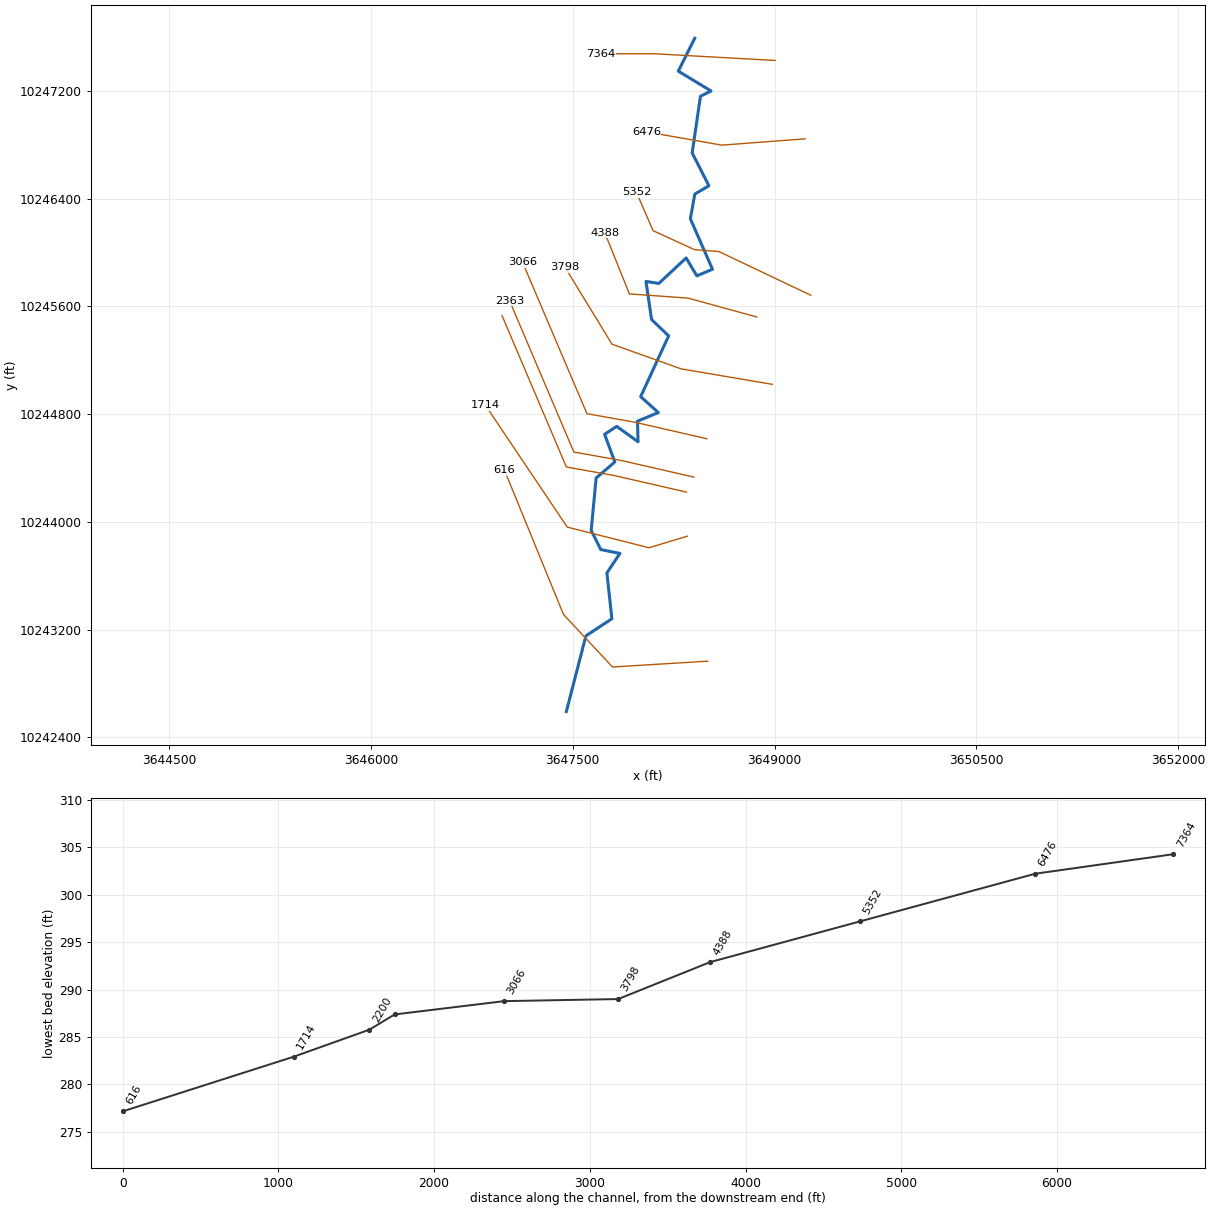
--- UNT019 IN GIBB.prj (project) ---

Proj Title=UNT019 IN GIBB Base Level Engineering
Current Plan=p01
Default Exp/Contr=0.3,0.1
English Units
Geom File=g01
Flow File=f01
Plan File=p01
Y Axis Title=Elevation
X Axis Title(PF)=Main Channel Distance
X Axis Title(XS)=Station
BEGIN DESCRIPTION:
UNT019 IN GIBB
END DESCRIPTION:
DSS Export Rating Curves= 0
DSS Export Rating Curve Sorted= 0
DSS Export Volume Flow Curves= 0
DXF OffsetX= 0
DXF OffsetY= 0
DXF ScaleX= 1
DXF ScaleY= 10

--- UNT019 IN GIBB.p01 (plan) ---

Plan Title=Multiple Run
Short Identifier=Multiple
Geom File=g01
Flow File=f01
Subcritical Flow
K Sum by GR= 0
Std Step Tol= 0.01
Critical Tol= 0.01
Num of Std Step Trials= 20
Max Error Tol= 0.3
Flow Tol Ratio= 0.001
Split Flow NTrial= 30
Split Flow Tol= 0.02
Split Flow Ratio= 0.02
Log Output Level= 0
Friction Slope Method= 1
Unsteady Friction Slope Method= 2
Unsteady Bridges Friction Slope Method= 1
Parabolic Critical Depth
Global Vel Dist=  1 , 1 , 1
Global Log Level= 0
CheckData=True
Encroach Param= -1, 0, 0, 0
BEGIN DESCRIPTION:
Multiple Run
END DESCRIPTION:

--- UNT019 IN GIBB.f01 (steady flow) ---

Flow Title=Multiple
Program Version=4.10
Number of Profiles= 7
Profile Names=10-year,25-year,50-year,1pct_min,100-year,1pct_plu,500-year
River Rch & RM=UNT019 IN GIBB,Reach-1         ,7364
     336     431     504     434     587     793     793
River Rch & RM=UNT019 IN GIBB,Reach-1         ,2200
     373     481     566     489     661     894     902
Boundary for River Rch & Prof#=UNT019 IN GIBB,Reach-1         , 1
Up Type= 0
Dn Type= 3
Dn Slope=0.006
Boundary for River Rch & Prof#=UNT019 IN GIBB,Reach-1         , 2
Up Type= 0
Dn Type= 3
Dn Slope=0.006
Boundary for River Rch & Prof#=UNT019 IN GIBB,Reach-1         , 3
Up Type= 0
Dn Type= 3
Dn Slope=0.006
Boundary for River Rch & Prof#=UNT019 IN GIBB,Reach-1         , 4
Up Type= 0
Dn Type= 3
Dn Slope=0.006
Boundary for River Rch & Prof#=UNT019 IN GIBB,Reach-1         , 5
Up Type= 0
Dn Type= 3
Dn Slope=0.006
Boundary for River Rch & Prof#=UNT019 IN GIBB,Reach-1         , 6
Up Type= 0
Dn Type= 3
Dn Slope=0.006
Boundary for River Rch & Prof#=UNT019 IN GIBB,Reach-1         , 7
Up Type= 0
Dn Type= 3
Dn Slope=0.006
DSS Import GetInterval= 0
DSS Import GetPeak= 0
DSS Import FillOption= 0

--- UNT019 IN GIBB.g01 (geometry) ---

Geom Title=Existing Conditions
Program Version=4.10

River Reach=UNT019 IN GIBB  ,Reach-1
Reach XY= 30
      3648406.52     10247591.63      3648284.54     10247347.12
      3648527.68     10247200.34      3648449.08     10247160.62
      3648387.57      10246740.2      3648511.68     10246496.43
      3648407.24     10246434.43        3648374.     10246251.27
      3648538.44     10245876.34      3648422.02     10245827.27
      3648342.92     10245960.28      3648139.03     10245770.75
      3648044.11     10245785.88      3648085.67     10245503.07
      3648212.73     10245381.57      3648004.65     10244930.33
      3648136.04     10244812.14      3647981.13     10244748.37
       3647985.2     10244595.34      3647826.81     10244709.59
      3647736.65     10244650.84      3647812.72     10244445.57
      3647673.68     10244325.99      3647636.91     10243936.56
      3647708.34     10243794.77      3647850.59     10243766.26
      3647753.71      10243621.4      3647790.82     10243281.18
      3647597.71     10243154.12      3647452.11     10242591.64

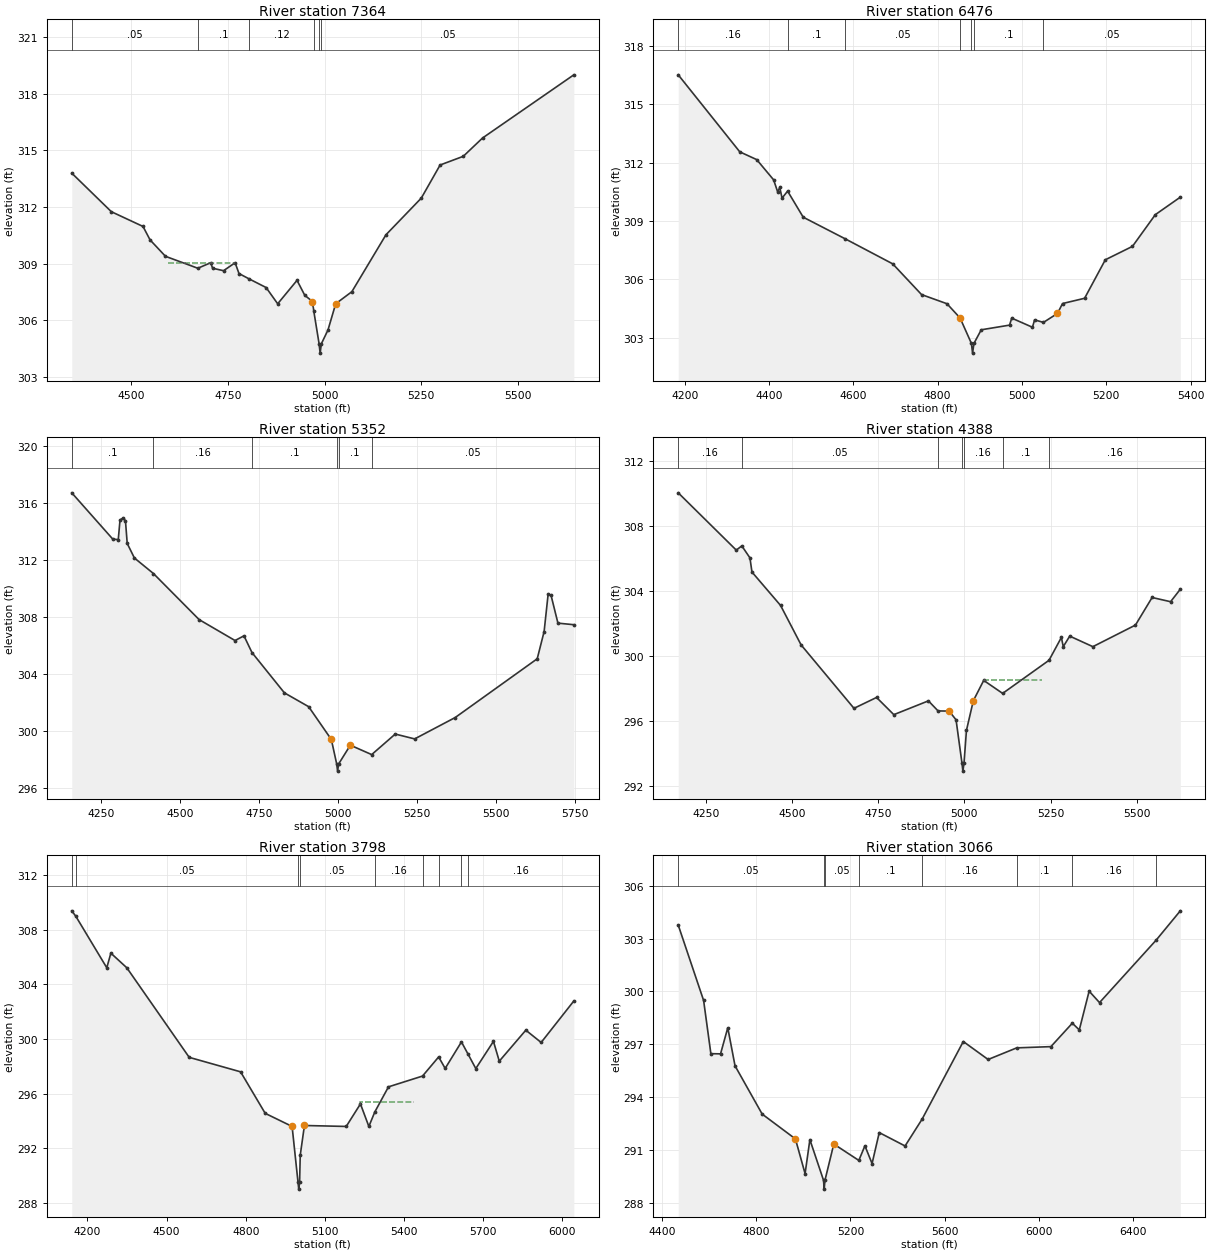
Type RM Length L Ch R = 1 ,7364    ,888,888,888
BEGIN DESCRIPTION:
UNT019 IN GIBB 11.0
END DESCRIPTION:
XS GIS Cut Line= 3
      3649004.48     10247426.59      3648104.45     10247476.59
      3647705.77     10247476.59
#Sta/Elev= 30
  4345.5  313.79    4448  311.75    4530  310.97  4548.2  310.26  4588.2  309.39
  4671.9  308.76  4705.2  309.05  4710.2  308.76  4738.5  308.63  4768.5  309.05
  4778.5  308.48  4804.4   308.2  4848.7  307.74  4878.7  306.88  4928.8  308.12
  4948.8  307.33  4968.8     307  4972.3  306.48  4985.9  304.77  4988.6  304.27
  4991.9  304.77  5008.9  305.49  5028.9  306.88  5070.8  307.52  5159.1  310.53
  5250.6  312.47  5299.3  314.22  5359.3  314.68  5409.3  315.65  5645.6  318.99
#Mann= 6 ,-1 , 0
  4345.5     .05       0  4671.9      .1       0  4804.4     .12       0
  4972.3     .05       0  4985.9     .03       0  4991.9     .05       0
#XS Ineff= 1 ,-1
 4594.55 4768.18  309.05
Permanent Ineff=
       F
Bank Sta=4968.8,5028.9
XS Rating Curve= 0 ,0
Exp/Cntr=0.3,0.1

Type RM Length L Ch R = 1 ,6476    ,1124,1124,1124
BEGIN DESCRIPTION:
UNT019 IN GIBB 9.0
END DESCRIPTION:
XS GIS Cut Line= 3
      3649227.73     10246844.78      3648607.95      10246797.9
      3648046.92      10246896.6
#Sta/Elev= 30
  4184.5  316.52  4330.5  312.56  4370.7  312.16  4410.8  311.12  4420.4   310.5
  4425.4  310.73  4430.8  310.18    4444  310.54    4481   309.2  4581.3  308.08
  4693.4   306.8  4761.8  305.22  4822.1  304.75  4853.1  304.02  4880.1  302.71
  4882.8  302.21  4886.1  302.71  4903.4  303.41  4970.6  303.65  4975.7  304.01
  5024.9  303.54    5030  303.92    5051  303.79  5084.2  304.25  5096.3  304.76
  5148.6  305.03  5197.8  307.01  5262.2   307.7  5316.4  309.33  5375.7  310.23
#Mann= 7 ,-1 , 0
  4184.5     .16       0    4444      .1       0  4581.3     .05       0
  4853.1      .1       0  4880.1     .07       0  4886.1      .1       0
    5051     .05       0
Bank Sta=4853.1,5084.2
XS Rating Curve= 0 ,0
Exp/Cntr=0.3,0.1

Type RM Length L Ch R = 1 ,5352    ,964,964,964
BEGIN DESCRIPTION:
UNT019 IN GIBB 7.0
END DESCRIPTION:
XS GIS Cut Line= 5
      3649269.39     10245683.33      3648585.21     10246008.17
      3648404.83     10246021.86      3648097.54     10246162.49
      3647973.04     10246447.78
#Sta/Elev= 30
  4157.7  316.71  4287.5  313.46  4304.7  313.43  4310.3  314.81  4320.7  314.95
  4327.5  314.74    4333  313.16  4355.7  312.14  4415.9  311.05  4560.3  307.82
  4673.9  306.35  4702.2  306.68  4727.4  305.51    4830  302.68  4906.7  301.71
  4978.4  299.41  4995.4  297.69  4998.2  297.19  5001.4  297.69  5038.5  299.01
    5106  298.35  5180.5  299.79  5241.9  299.45  5370.1  300.95  5629.4  305.07
  5651.2  306.98  5663.8  309.58    5673  309.53  5694.9  307.57  5745.2  307.46
#Mann= 6 ,-1 , 0
  4157.7      .1       0  4415.9     .16       0  4727.4      .1       0
  4995.4     .07       0  5001.4      .1       0    5106     .05       0
Bank Sta=4978.4,5038.5
XS Rating Curve= 0 ,0
Exp/Cntr=0.3,0.1

Type RM Length L Ch R = 1 ,4388    ,590,590,590
BEGIN DESCRIPTION:
UNT019 IN GIBB 6.0
END DESCRIPTION:
XS GIS Cut Line= 4
      3648868.34     10245521.87      3648356.02      10245662.2
      3647921.23     10245693.21      3647738.19     10246146.79
#Sta/Elev= 30
  4170.1  310.04  4338.4  306.51  4354.5  306.77  4378.1  306.03  4383.9  305.16
  4466.9   303.1  4526.4  300.67  4679.8  296.76  4745.3  297.43  4795.4  296.37
  4895.7  297.22  4923.7   296.6  4955.9  296.59  4975.9  296.05    4993  293.39
  4995.7  292.89    4999  293.39    5006   295.4    5026  297.23  5056.1  298.48
    5111  297.68  5245.5  299.72  5281.4  301.13  5286.8  300.56  5305.6  301.21
  5372.7  300.56  5496.2  301.89  5544.5  303.59  5598.1  303.33  5626.3   304.1
#Mann= 7 ,-1 , 0
  4170.1     .16       0  4354.5     .05       0  4923.7     .16       0
    4993     .07       0    4999     .16       0    5111      .1       0
  5245.5     .16       0
#XS Ineff= 1 ,-1
  5057.5 5226.25  298.51
Permanent Ineff=
       F
Bank Sta=4955.9,5026
XS Rating Curve= 0 ,0
Exp/Cntr=0.3,0.1

Type RM Length L Ch R = 1 ,3798    ,732,732,732
BEGIN DESCRIPTION:
UNT019 IN GIBB 5.0
END DESCRIPTION:
XS GIS Cut Line= 4
      3648982.93     10245021.87      3648305.87     10245136.45
      3647791.55     10245319.82      3647442.08     10245891.68
#Sta/Elev= 30
  4140.6  309.38  4156.3  308.97  4273.3  305.21  4288.8  306.28  4349.2  305.21
  4585.7  298.65  4780.4  297.59  4873.7  294.55  4975.7  293.59  4998.1   289.5
  5000.9     289  5004.1   289.5  5006.5  291.48  5022.4  293.66  5180.8  293.59
  5234.7  295.24  5266.6  293.59  5289.1  294.65  5340.9  296.49    5470  297.28
  5531.1  298.68  5555.8  297.84  5617.5  299.78  5642.4  298.89  5671.9  297.83
  5738.8  299.82  5760.9  298.37  5861.5  300.64  5919.6  299.74  6043.5  302.78
#Mann= 9 ,-1 , 0
  4140.6     .16       0  4156.3     .05       0  4998.1     .03       0
  5004.1     .05       0  5289.1     .16       0    5470      .1       0
  5531.1     .16       0  5617.5      .1       0  5642.4     .16       0
#XS Ineff= 1 ,-1
 5231.53  5437.5  295.39
Permanent Ineff=
       F
Bank Sta=4975.7,5022.4
XS Rating Curve= 0 ,0
Exp/Cntr=0.3,0.1

Type RM Length L Ch R = 1 ,3066    ,703,703,703
BEGIN DESCRIPTION:
UNT019 IN GIBB 3.0
END DESCRIPTION:
XS GIS Cut Line= 4
      3648497.21     10244617.62      3647961.88     10244740.28
      3647605.36     10244803.81      3647127.45     10245927.35
#Sta/Elev= 30
  4468.6  303.77  4576.4  299.49  4607.2  296.47  4648.3  296.46    4679  297.94
  4709.8  295.78  4825.1  293.04  4966.3  291.63  5007.3  289.66  5027.7  291.59
  5085.7  289.28  5088.4  288.78  5091.7  289.28  5129.3  291.34  5235.6  290.41
  5261.4  291.24  5291.8  290.23  5322.3  291.99    5432  291.23  5504.6  292.76
  5679.2  297.16  5784.7  296.14  5906.1   296.8  6051.3  296.87  6142.3   298.2
  6171.9  297.82  6213.7  300.02  6257.8  299.37  6497.9  302.91  6600.9  304.58
#Mann= 8 ,-1 , 0
  4468.6     .05       0  5085.7     .03       0  5091.7     .05       0
  5235.6      .1       0  5504.6     .16       0  5906.1      .1       0
  6142.3     .16       0  6497.9     .05       0
Bank Sta=4966.3,5129.3
XS Rating Curve= 0 ,0
Exp/Cntr=0.3,0.1

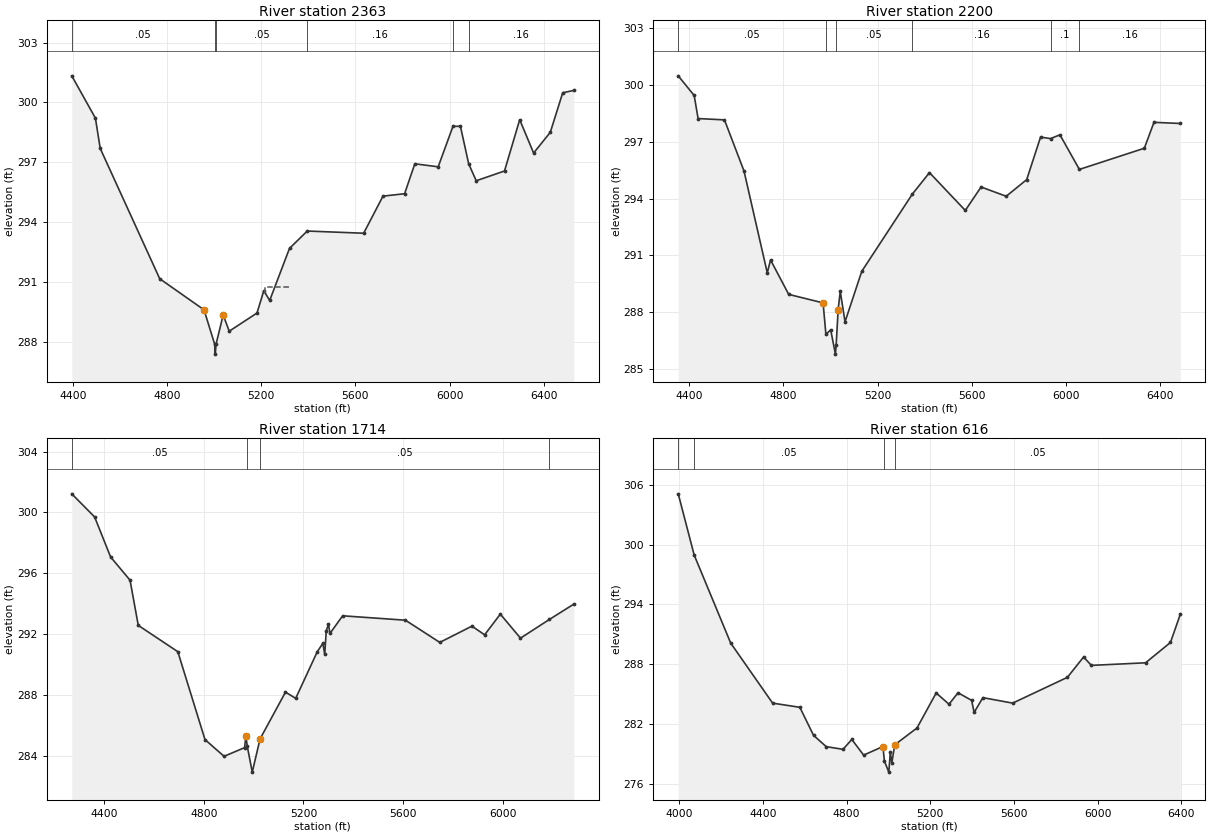
Type RM Length L Ch R = 1 ,2363    ,163,163,163
BEGIN DESCRIPTION:
UNT019 IN GIBB 3.2
END DESCRIPTION:
XS GIS Cut Line= 4
      3648399.96     10244332.91      3647864.65     10244455.56
      3647508.13     10244519.09      3647029.94      10245643.3
#Sta/Elev= 30
    4395  301.33  4495.4  299.21  4515.9  297.69  4768.6  291.16  4956.9   289.6
    5002  287.88  5004.7  287.38    5008  287.88  5038.2  289.34    5064  288.53
  5181.9  289.44  5210.9  290.56  5235.8  290.07    5320  292.68  5395.4  293.55
  5635.1  293.44  5717.2   295.3    5809  295.42  5852.4  296.92  5951.7  296.77
  6014.5   298.8  6046.2   298.8  6081.2  296.92  6113.3  296.07  6233.4  296.56
    6298  299.13  6357.1  297.46    6428   298.5  6480.7  300.48    6528   300.6
#Mann= 6 ,-1 , 0
    4395     .05       0    5002     .03       0    5008     .05       0
  5395.4     .16       0  6014.5      .1       0  6081.2     .16       0
#XS Ineff= 1 ,-1
 5217.05 5319.32  290.73
Permanent Ineff=
       F
Bank Sta=4956.9,5038.2
XS Rating Curve= 0 ,0
Exp/Cntr=0.3,0.1

Type RM Length L Ch R = 1 ,2200    ,486,486,486
BEGIN DESCRIPTION:
UNT019 IN GIBB 3.1
END DESCRIPTION:
XS GIS Cut Line= 4
      3648344.37      10244221.8       3647809.1     10244344.45
      3647452.58     10244407.98      3646974.38     10245532.22
#Sta/Elev= 30
  4352.9  300.49  4420.6  299.45  4437.3  298.23  4549.3  298.16  4632.2  295.46
  4731.2  290.07  4745.1  290.75  4822.2  288.93  4968.3  288.48  4980.3  286.81
  5000.6  287.06  5020.6  285.77  5023.9  286.27  5032.3  288.13  5041.2  289.09
  5061.5  287.48  5132.6  290.15  5347.8  294.24  5420.3  295.37  5572.4  293.37
  5639.5  294.61  5746.3  294.12  5833.3     295  5892.2  297.25  5934.6  297.17
  5974.5  297.37  6057.1  295.54  6333.1  296.66    6374  298.03  6485.9  297.97
#Mann= 6 ,-1 , 0
  4352.9     .05       0  4980.3     .03       0  5023.9     .05       0
  5347.8     .16       0  5934.6      .1       0  6057.1     .16       0
Bank Sta=4968.3,5032.3
XS Rating Curve= 0 ,0
Exp/Cntr=0.3,0.1

Type RM Length L Ch R = 1 ,1714    ,1098,1098,1098
BEGIN DESCRIPTION:
UNT019 IN GIBB 2.0
END DESCRIPTION:
XS GIS Cut Line= 4
      3648351.34     10243894.19      3648066.59     10243808.25
      3647459.05      10243961.8      3646849.88     10244867.88
#Sta/Elev= 30
  4269.9  301.22  4361.6   299.7  4425.8  297.07  4503.9  295.54  4536.9  292.57
  4695.7  290.84  4804.8  285.06  4881.4  283.96  4963.8  284.53    4969  285.31
  4974.2  284.65  4994.6  282.92  5025.8   285.1    5128  288.18    5169  287.77
  5255.7  290.84  5278.1  291.39  5285.6  290.66  5291.7  292.21  5300.6  292.64
  5306.6  292.04  5357.6   293.2  5609.6  292.91  5747.6  291.45  5876.6  292.52
  5927.6  291.95  5990.6  293.31  6071.6  291.73  6187.7  292.96  6285.8  293.97
#Mann= 4 ,-1 , 0
  4269.9     .05       0  4974.2     .03       0  5025.8     .05       0
  6187.7     .16       0
Bank Sta=4969,5025.8
XS Rating Curve= 0 ,0
Exp/Cntr=0.3,0.1

Type RM Length L Ch R = 1 ,616     ,0,0,0
BEGIN DESCRIPTION:
UNT019 IN GIBB 1.0
END DESCRIPTION:
XS GIS Cut Line= 4
      3648502.57     10242966.05      3647795.45      10242922.9
      3647430.87     10243313.53      3646992.15     10244385.35
#Sta/Elev= 30
  3995.1  305.11  4071.2  298.97    4246  290.12  4446.4  284.09  4576.6  283.67
    4642  280.86  4702.7  279.72    4783  279.45  4825.1  280.44  4881.7  278.87
  4974.1  279.73  4980.9  278.28  5002.1  277.16  5009.2  279.16  5016.4  278.07
  5030.2   279.9  5136.7  281.59  5228.6  285.11  5289.9  283.98  5333.1  285.13
  5397.9  284.37  5410.1  283.16  5451.9  284.64  5594.4  284.09    5856  286.68
  5933.5  288.72  5970.6  287.88  6229.9  288.14  6348.8  290.18    6396  293.01
#Mann= 4 ,-1 , 0
  3995.1     .16       0  4071.2     .05       0  4980.9     .03       0
  5030.2     .05       0
Bank Sta=4974.1,5030.2
XS Rating Curve= 0 ,0
Exp/Cntr=0.3,0.1

Chan Stop Cuts=-1
Use User Specified Reach Order=0
Composite Channel Slope=5