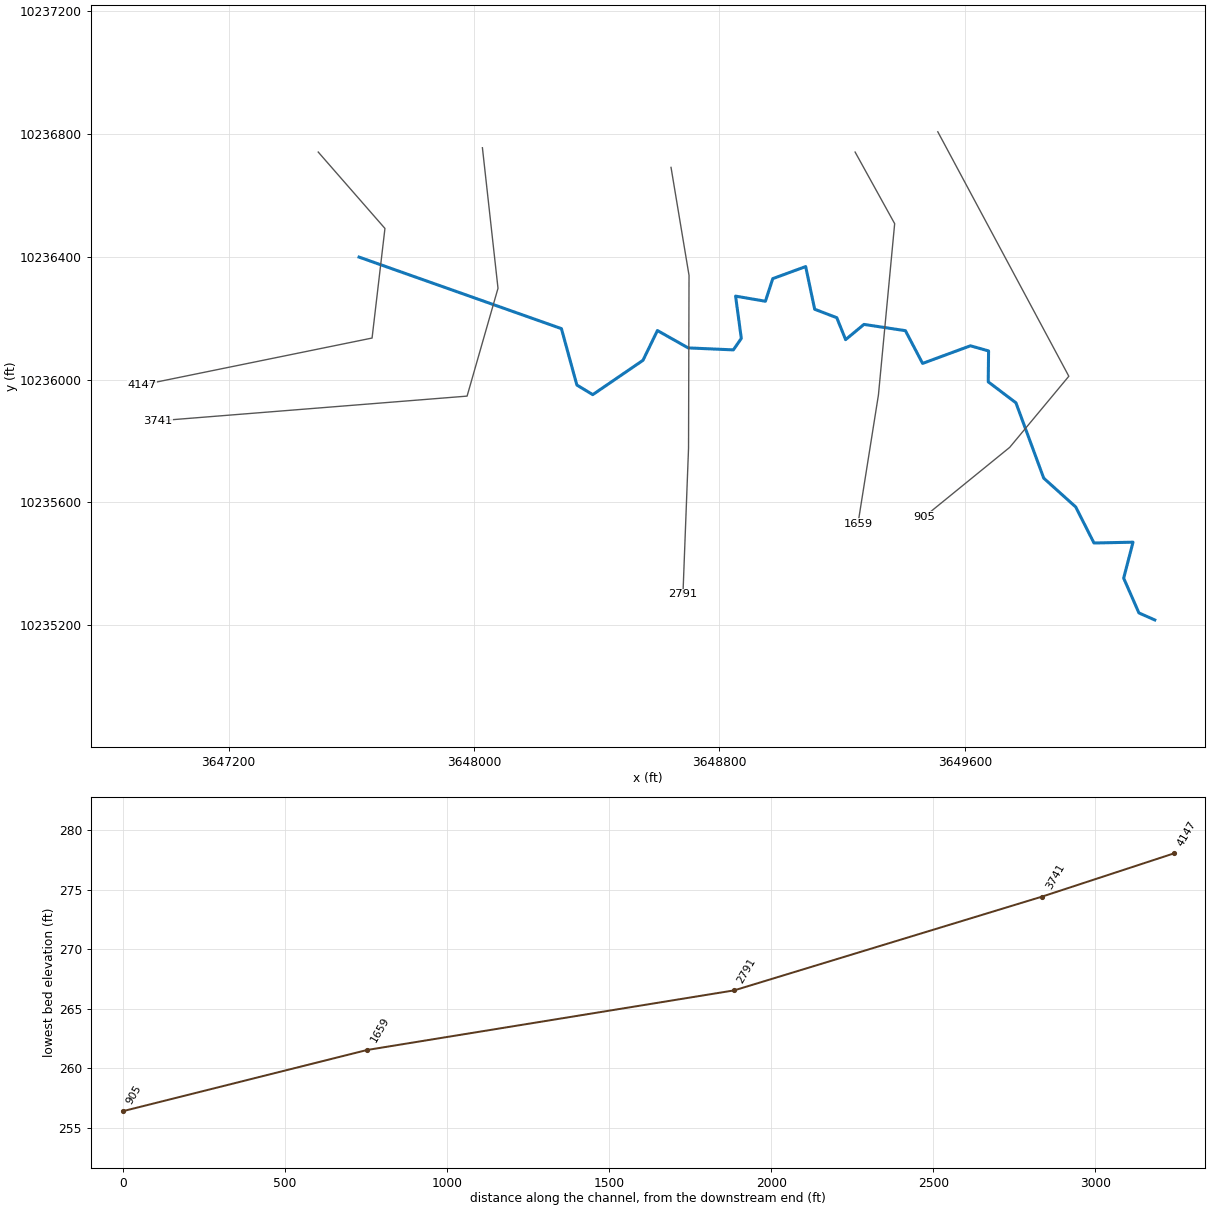
--- UNT020 IN GIBB.prj (project) ---

Proj Title=UNT020 IN GIBB Base Level Engineering
Current Plan=p01
Default Exp/Contr=0.3,0.1
English Units
Geom File=g01
Flow File=f01
Plan File=p01
BEGIN DESCRIPTION:
UNT020 IN GIBB
END DESCRIPTION:

--- UNT020 IN GIBB.p01 (plan) ---

Plan Title=Multiple Run
Short Identifier=Multiple
Geom File=g01
Flow File=f01
Subcritical Flow
K Sum by GR= 0
Std Step Tol= 0.01
Critical Tol= 0.01
Num of Std Step Trials= 20
Max Error Tol= 0.3
Flow Tol Ratio= 0.001
Split Flow NTrial= 30
Split Flow Tol= 0.02
Split Flow Ratio= 0.02
Log Output Level= 0
Friction Slope Method= 1
Unsteady Friction Slope Method= 2
Unsteady Bridges Friction Slope Method= 1
Parabolic Critical Depth
Global Vel Dist=  1 , 1 , 1
Global Log Level= 0
CheckData=True
Encroach Param= -1, 0, 0, 0
BEGIN DESCRIPTION:
Multiple Run
END DESCRIPTION:

--- UNT020 IN GIBB.f01 (steady flow) ---

Flow Title=Multiple
Number of Profiles=7
Profile Names=10-year,25-year,50-year,1pct_min,100-year,1pct_plu,500-year
River Rch & RM= UNT020 IN GIBB,Reach-1,4147
     470     624     749     660     892    1206    1266
Boundary for River Rch & Prof#=UNT020 IN GIBB,Reach-1,1
Up Type=0
Dn Type=3
Dn Slope=0.005
Boundary for River Rch & Prof#=UNT020 IN GIBB,Reach-1,2
Up Type=0
Dn Type=3
Dn Slope=0.005
Boundary for River Rch & Prof#=UNT020 IN GIBB,Reach-1,3
Up Type=0
Dn Type=3
Dn Slope=0.005
Boundary for River Rch & Prof#=UNT020 IN GIBB,Reach-1,4
Up Type=0
Dn Type=3
Dn Slope=0.005
Boundary for River Rch & Prof#=UNT020 IN GIBB,Reach-1,5
Up Type=0
Dn Type=3
Dn Slope=0.005
Boundary for River Rch & Prof#=UNT020 IN GIBB,Reach-1,6
Up Type=0
Dn Type=3
Dn Slope=0.005
Boundary for River Rch & Prof#=UNT020 IN GIBB,Reach-1,7
Up Type=0
Dn Type=3
Dn Slope=0.005

--- UNT020 IN GIBB.g01 (geometry) ---

Geom Title=Existing Conditions

River Reach=UNT020 IN GIBB,Reach-1
Reach XY= 30
      3647625.24     10236399.25      3648284.79     10236166.08
      3648335.21     10235982.21      3648386.96     10235950.93
      3648550.65     10236062.80      3648597.81     10236159.87
      3648697.88     10236103.29      3648845.14     10236096.82
      3648871.18     10236134.14      3648852.50     10236272.00
      3648949.75     10236255.32      3648973.74     10236329.08
      3649080.99     10236368.35      3649110.33     10236229.29
      3649182.31     10236201.72      3649211.19     10236130.22
      3649270.95     10236179.83      3649406.07     10236159.44
      3649462.08     10236052.72      3649618.05     10236110.13
      3649677.14     10236093.37      3649676.04     10235992.63
      3649766.36     10235924.26      3649856.92     10235678.70
      3649961.21     10235584.81      3650020.71     10235467.31
      3650148.01     10235470.00      3650117.48     10235352.70
      3650167.23     10235239.36      3650218.87     10235216.54

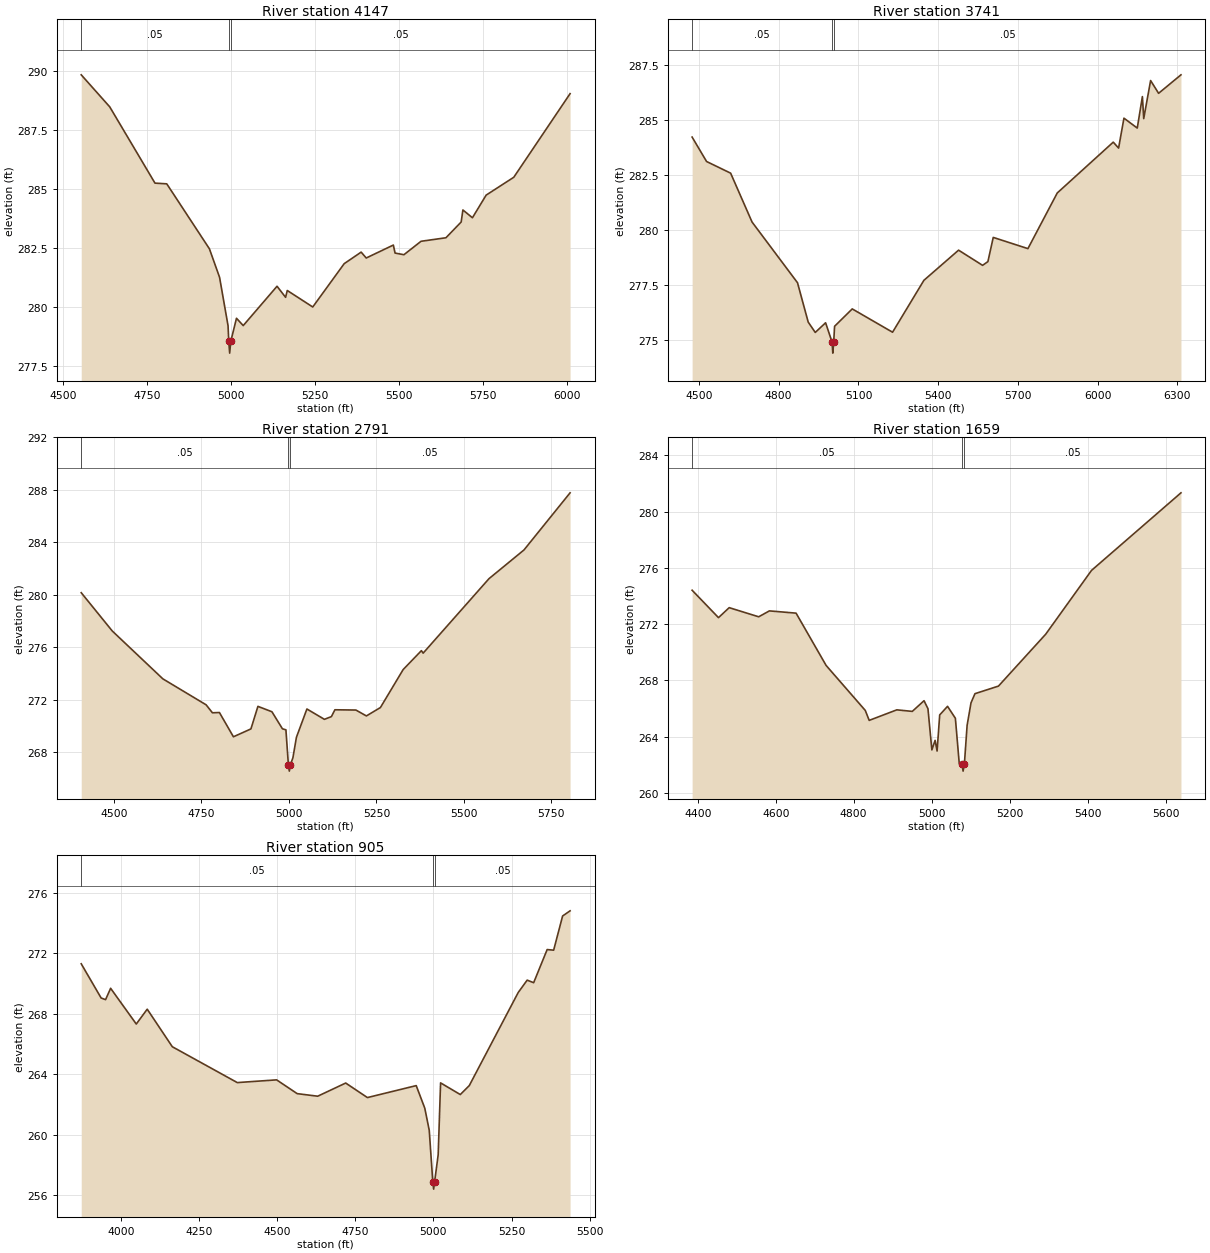
Type RM Length L Ch R = 1,4147,406,406,406
BEGIN DESCRIPTION:
UNT020 IN GIBB 7.0
END DESCRIPTION:
XS GIS Cut Line= 4
      3647492.12     10236741.63      3647709.59     10236492.64
      3647667.62     10236135.39      3646917.09     10235982.23
#Sta/Elev= 30
  4553.9  289.85  4638.8  288.49  4773.6  285.25  4808.7  285.22  4935.8  282.46
  4966.0  281.25  4991.3  279.19  4993.4  278.53  4996.1  278.03  4999.4  278.53
  5016.4  279.51  5036.5  279.20  5137.2  280.87  5162.7  280.40  5167.7  280.69
  5243.6  279.99  5337.3  281.83  5387.8  282.32  5402.9  282.07  5483.7  282.62
  5488.8  282.28  5515.2  282.21  5566.2  282.78  5640.4  282.93  5685.8  283.60
  5690.9  284.11  5719.3  283.78  5760.1  284.74  5842.5  285.50  6010.2  289.05
#Mann=3,-1,0
  4553.9    0.05       0  4993.4    0.03       0  4999.4    0.05       0
Bank Sta=4993.4,4999.4
Exp/Cntr=0.3,0.1

Type RM Length L Ch R = 1,3741,950,950,950
BEGIN DESCRIPTION:
UNT020 IN GIBB 6.0
END DESCRIPTION:
XS GIS Cut Line= 4
      3648027.30     10236755.66      3648078.10     10236297.66
      3647977.34     10235946.13      3646968.26     10235865.40
#Sta/Elev= 30
  4474.4  284.23  4528.8  283.12  4619.3  282.59  4699.8  280.37  4870.8  277.61
  4911.1  275.82  4937.6  275.35  4976.5  275.79  5000.9  274.91  5003.6  274.41
  5006.9  274.91  5010.3  275.63  5076.7  276.42  5228.4  275.36  5346.3  277.72
  5476.7  279.09  5567.0  278.40  5587.0  278.57  5607.1  279.67  5737.5  279.16
  5847.9  281.69  6058.5  284.00  6078.6  283.73  6098.7  285.09  6148.8  284.64
  6168.1  286.07  6173.1  285.07  6199.0  286.80  6229.1  286.22  6313.2  287.06
#Mann=3,-1,0
  4474.4    0.05       0  5000.9    0.03       0  5006.9    0.05       0
Bank Sta=5000.9,5006.9
Exp/Cntr=0.3,0.1

Type RM Length L Ch R = 1,2791,1132,1132,1132
BEGIN DESCRIPTION:
UNT020 IN GIBB 4.0
END DESCRIPTION:
XS GIS Cut Line= 4
      3648642.10     10236691.67      3648700.76     10236339.69
      3648699.17     10235776.49      3648680.94     10235299.97
#Sta/Elev= 30
  4406.4  280.15  4495.1  277.23  4639.6  273.58  4763.2  271.60  4781.3  270.99
  4801.3  271.01  4841.3  269.16  4891.3  269.76  4911.3  271.48  4951.3  271.07
  4981.3  269.77  4991.3  269.69  4998.3  267.04  5001.0  266.54  5004.3  267.04
  5011.3  267.56  5021.3  269.12  5051.3  271.28  5101.3  270.49  5121.3  270.70
  5131.3  271.22  5191.3  271.20  5221.3  270.75  5261.3  271.39  5326.4  274.29
  5378.4  275.73  5383.4  275.54  5571.5  281.22  5671.5  283.41  5803.3  287.77
#Mann=3,-1,0
  4406.4    0.05       0  4998.3    0.03       0  5004.3    0.05       0
Bank Sta=4998.3,5004.3
Exp/Cntr=0.3,0.1

Type RM Length L Ch R = 1,1659,754,754,754
BEGIN DESCRIPTION:
UNT020 IN GIBB 2.0
END DESCRIPTION:
XS GIS Cut Line= 4
      3649242.11     10236741.64      3649371.05     10236508.26
      3649318.16     10235950.09      3649251.25     10235529.07
#Sta/Elev= 30
  4385.7  274.41  4453.3  272.46  4480.8  273.17  4556.4  272.52  4583.9  272.94
  4652.3  272.78  4729.3  269.06  4829.7  265.86  4839.8  265.15  4910.6  265.90
  4950.3  265.79  4980.4  266.55  4990.5  265.98  5000.5  263.05  5008.8  263.73
  5013.9  262.97  5020.6  265.54  5040.7  266.15  5060.8  265.30  5070.8  262.06
  5077.9  262.04  5080.6  261.54  5083.9  262.04  5090.9  264.80  5100.9  266.40
  5111.0  267.05  5171.3  267.59  5292.4  271.28  5409.9  275.82  5639.3  281.34
#Mann=3,-1,0
  4385.7    0.05       0  5077.9    0.03       0  5083.9    0.05       0
Bank Sta=5077.9,5083.9
Exp/Cntr=0.3,0.1

Type RM Length L Ch R = 1,905,0,0,0
BEGIN DESCRIPTION:
UNT020 IN GIBB 1.0
END DESCRIPTION:
XS GIS Cut Line= 4
      3649511.66     10236807.77      3649938.75     10236010.87
      3649746.05     10235779.10      3649467.39     10235552.53
#Sta/Elev= 30
  3872.8  271.29  3936.5  269.03  3950.7  268.92  3966.9  269.67  4049.0  267.31
  4084.0  268.29  4164.3  265.81  4372.3  263.44  4498.2  263.62  4564.0  262.71
  4629.7  262.54  4719.3  263.41  4788.8  262.45  4945.0  263.24  4972.4  261.75
  4986.7  260.29  4998.0  256.90  5000.8  256.40  5004.0  256.90  5015.3  258.67
  5023.0  263.42  5086.1  262.65  5114.8  263.24  5271.4  269.39  5300.1  270.21
  5320.9  270.04  5364.1  272.23  5384.9  272.19  5413.6  274.45  5437.5  274.79
#Mann=3,-1,0
  3872.8    0.05       0  4998.0    0.03       0  5004.0    0.05       0
Bank Sta=4998,5004
Exp/Cntr=0.3,0.1

Chan Stop Cuts=-1