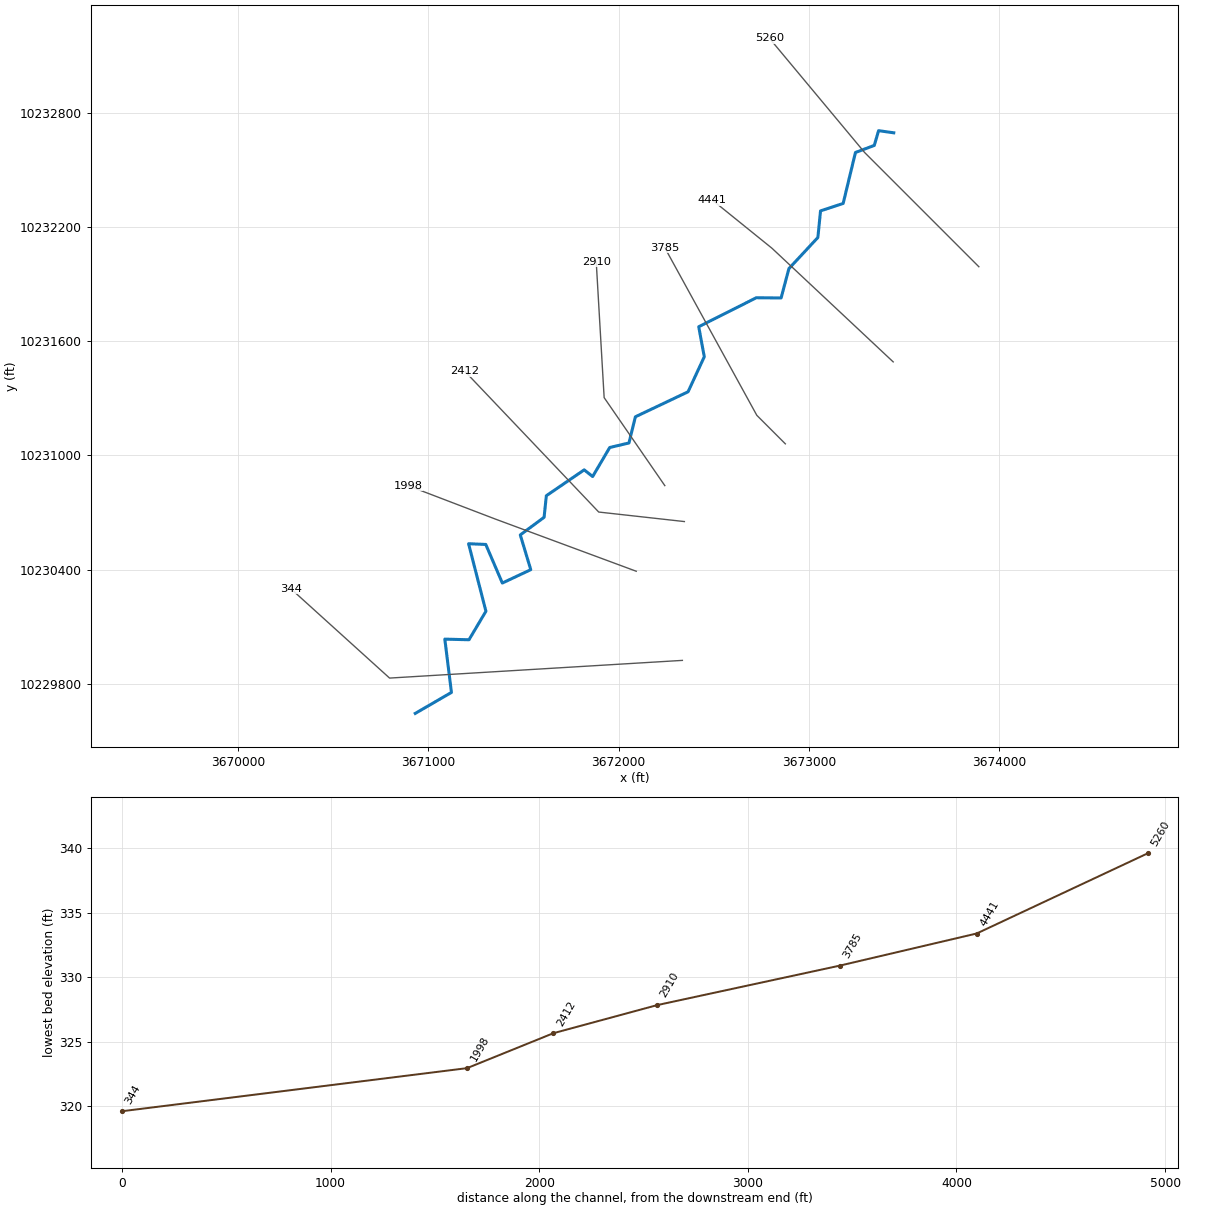
--- UNT022 IN GIBB.prj (project) ---

Proj Title=UNT022 IN GIBB Base Level Engineering
Current Plan=p01
Default Exp/Contr=0.3,0.1
English Units
Geom File=g01
Flow File=f01
Plan File=p01
Y Axis Title=Elevation
X Axis Title(PF)=Main Channel Distance
X Axis Title(XS)=Station
BEGIN DESCRIPTION:
UNT022 IN GIBB
END DESCRIPTION:
DSS Export Rating Curves= 0
DSS Export Rating Curve Sorted= 0
DSS Export Volume Flow Curves= 0
DXF OffsetX= 0
DXF OffsetY= 0
DXF ScaleX= 1
DXF ScaleY= 10

--- UNT022 IN GIBB.p01 (plan) ---

Plan Title=Multiple Run
Short Identifier=Multiple
Geom File=g01
Flow File=f01
Subcritical Flow
K Sum by GR= 0
Std Step Tol= 0.01
Critical Tol= 0.01
Num of Std Step Trials= 20
Max Error Tol= 0.3
Flow Tol Ratio= 0.001
Split Flow NTrial= 30
Split Flow Tol= 0.02
Split Flow Ratio= 0.02
Log Output Level= 0
Friction Slope Method= 1
Unsteady Friction Slope Method= 2
Unsteady Bridges Friction Slope Method= 1
Parabolic Critical Depth
Global Vel Dist=  1 , 1 , 1
Global Log Level= 0
CheckData=True
Encroach Param= -1, 0, 0, 0
BEGIN DESCRIPTION:
Multiple Run
END DESCRIPTION:

--- UNT022 IN GIBB.f01 (steady flow) ---

Flow Title=Multiple
Program Version=4.10
Number of Profiles= 7
Profile Names=10-year,25-year,50-year,1pct_min,100-year,1pct_plu,500-year
River Rch & RM=UNT022 IN GIBB,Reach-1         ,5260
     915    1256    1540    1383    1870    2529    2756
Boundary for River Rch & Prof#=UNT022 IN GIBB,Reach-1         , 1
Up Type= 0
Dn Type= 3
Dn Slope=0.01
Boundary for River Rch & Prof#=UNT022 IN GIBB,Reach-1         , 2
Up Type= 0
Dn Type= 3
Dn Slope=0.01
Boundary for River Rch & Prof#=UNT022 IN GIBB,Reach-1         , 3
Up Type= 0
Dn Type= 3
Dn Slope=0.01
Boundary for River Rch & Prof#=UNT022 IN GIBB,Reach-1         , 4
Up Type= 0
Dn Type= 3
Dn Slope=0.01
Boundary for River Rch & Prof#=UNT022 IN GIBB,Reach-1         , 5
Up Type= 0
Dn Type= 3
Dn Slope=0.01
Boundary for River Rch & Prof#=UNT022 IN GIBB,Reach-1         , 6
Up Type= 0
Dn Type= 3
Dn Slope=0.01
Boundary for River Rch & Prof#=UNT022 IN GIBB,Reach-1         , 7
Up Type= 0
Dn Type= 3
Dn Slope=0.01
DSS Import GetInterval= 0
DSS Import GetPeak= 0
DSS Import FillOption= 0

--- UNT022 IN GIBB.g01 (geometry) ---

Geom Title=Existing Conditions
Program Version=4.10

River Reach=UNT022 IN GIBB  ,Reach-1
Reach XY= 30
      3673445.06     10232695.36      3673365.38     10232706.52
      3673342.71     10232628.99      3673243.76     10232591.84
       3673179.2      10232324.1      3673060.28     10232285.04
      3673046.39     10232145.28      3672894.13     10231981.62
       3672853.2     10231827.52      3672722.94     10231828.69
      3672420.32     10231676.41      3672449.49      10231518.5
      3672364.35     10231334.52      3672087.48     10231203.15
      3672053.85     10231065.69      3671952.71     10231041.85
      3671863.01     10230889.35      3671818.63     10230924.31
      3671619.61     10230788.45      3671607.91     10230675.06
      3671482.81     10230582.55      3671537.84     10230399.95
      3671388.49     10230329.71      3671301.48     10230532.48
      3671211.12     10230536.29      3671302.26     10230181.47
      3671213.29     10230031.73      3671086.33     10230034.99
      3671121.06     10229755.04      3670931.17     10229644.91

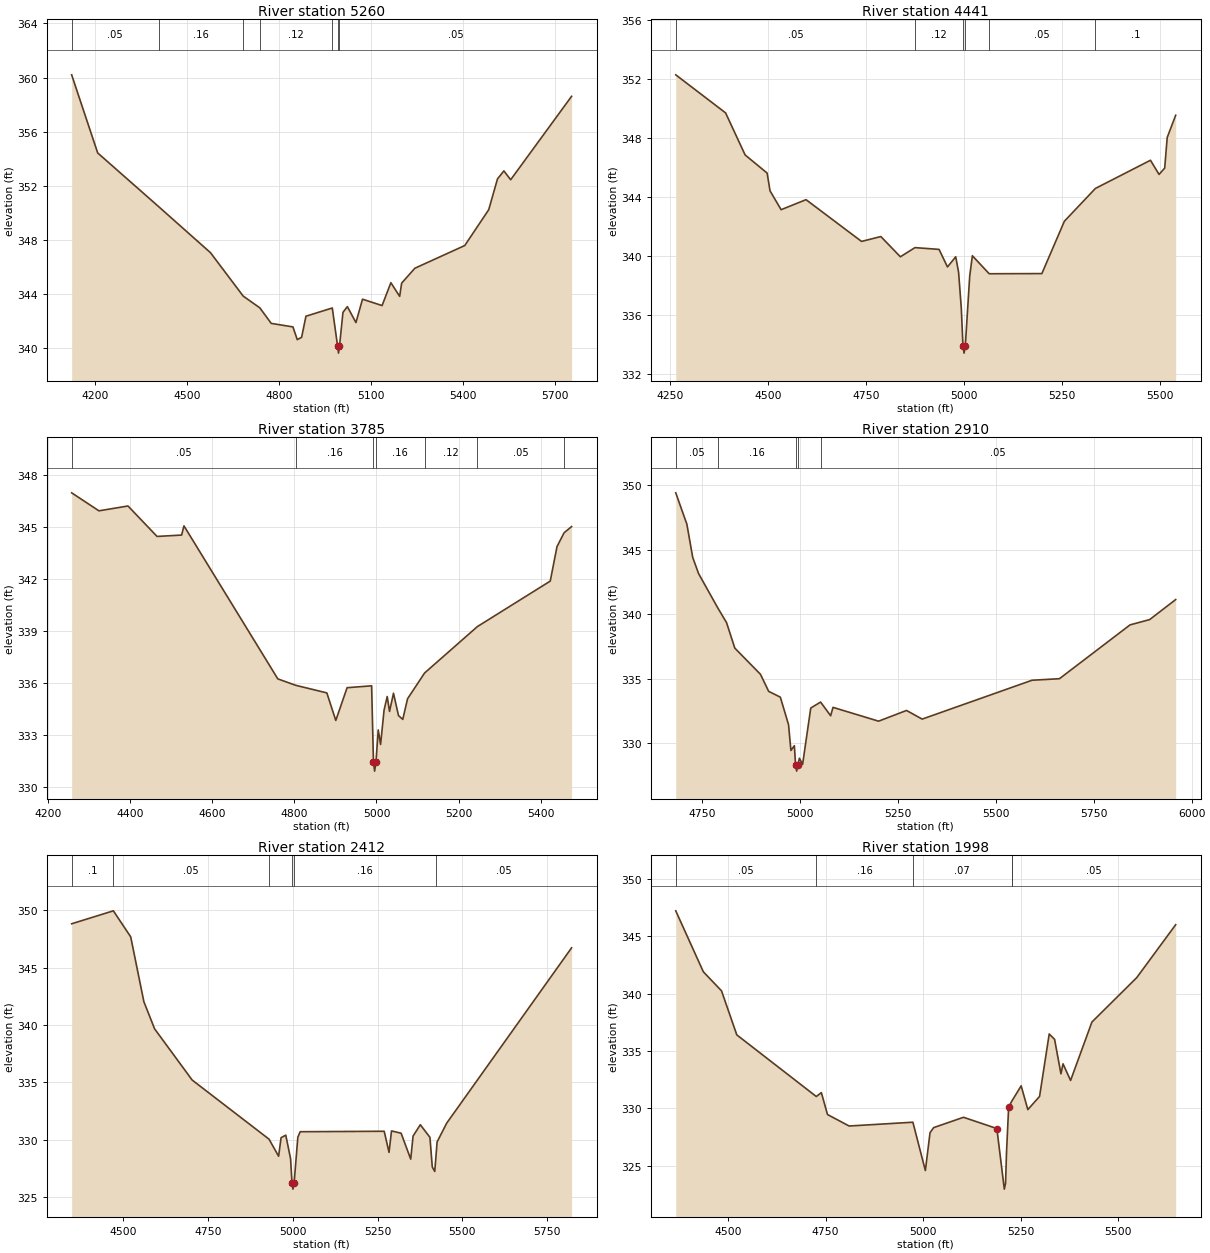
Type RM Length L Ch R = 1 ,5260    ,819,819,819
BEGIN DESCRIPTION:
UNT022 IN GIBB 10.0
END DESCRIPTION:
XS GIS Cut Line= 3
      3673892.12     10231991.62      3673292.11     10232591.64
      3672792.09     10233191.66
#Sta/Elev= 30
  4123.2   360.2  4208.1  354.42  4407.2  350.44  4575.8  347.04  4682.4  343.83
  4736.6  342.96  4773.8  341.81  4844.5  341.55  4858.6  340.61  4872.8  340.78
  4886.9  342.34  4972.8  342.95  4990.2  340.11    4993  339.61  4996.2  340.11
  5007.6  342.63  5021.9  343.05  5049.9  341.87  5071.3   343.6  5135.1  343.13
  5163.8  344.82  5192.4  343.81  5198.9  344.79  5241.9  345.89  5404.6  347.57
  5482.7  350.22  5511.3   352.5  5532.1  353.09  5554.3  352.44  5752.8  358.61
#Mann= 7 ,-1 , 0
  4123.2     .05       0  4407.2     .16       0  4682.4     .05       0
  4736.6     .12       0  4972.8     .05       0  4990.2     .03       0
  4996.2     .05       0
Bank Sta=4990.2,4996.2
XS Rating Curve= 0 ,0
Exp/Cntr=0.3,0.1

Type RM Length L Ch R = 1 ,4441    ,656,656,656
BEGIN DESCRIPTION:
UNT022 IN GIBB 8.0
END DESCRIPTION:
XS GIS Cut Line= 3
      3673442.07     10231491.67      3672805.33     10232088.63
      3672492.07     10232341.67
#Sta/Elev= 30
  4263.7  352.26  4390.9  349.68  4440.7  346.83  4496.9   345.6  4504.2   344.4
  4532.5  343.12  4596.1   343.8  4737.7  340.97    4787   341.3  4836.8  339.93
  4874.1  340.55  4935.5  340.43    4957  339.24    4978  339.93  4985.3  338.89
  4992.2  336.47  4996.5   333.9  4999.3   333.4  5002.5   333.9  5013.7  338.62
  5020.5     340  5063.4  338.78  5197.8  338.79  5255.3  342.34  5334.4  344.56
  5474.9  346.47  5496.8  345.51  5511.2  345.94  5517.6  348.01  5539.2  349.52
#Mann= 6 ,-1 , 0
  4263.7     .05       0  4874.1     .12       0  4996.5     .07       0
  5002.5     .12       0  5063.4     .05       0  5334.4      .1       0
Bank Sta=4996.5,5002.5
XS Rating Curve= 0 ,0
Exp/Cntr=0.3,0.1

Type RM Length L Ch R = 1 ,3785    ,875,875,875
BEGIN DESCRIPTION:
UNT022 IN GIBB 6.0
END DESCRIPTION:
XS GIS Cut Line= 3
      3672875.45     10231061.07      3672725.44     10231211.09
      3672242.12     10232091.61
#Sta/Elev= 30
  4258.2  346.99  4324.6  345.95  4395.3  346.23    4466  344.47  4525.8  344.55
  4531.5  345.08  4759.9  336.24  4803.3  335.87  4879.2  335.43    4901  333.84
  4928.5  335.73  4988.2  335.84  4992.7  331.41  4995.5  330.91  4998.7  331.41
  5004.3  333.29    5010  332.45  5018.5  334.44  5026.1  335.22  5031.8  334.36
  5041.4  335.41  5053.6  334.12    5064   333.9  5075.6  335.09  5117.1  336.58
  5245.5  339.26  5422.9  341.89  5439.3  343.88  5456.5  344.68  5474.8  345.04
#Mann= 7 ,-1 , 0
  4258.2     .05       0  4803.3     .16       0  4992.7     .07       0
  4998.7     .16       0  5117.1     .12       0  5245.5     .05       0
  5456.5      .1       0
Bank Sta=4992.7,4998.7
XS Rating Curve= 0 ,0
Exp/Cntr=0.3,0.1

Type RM Length L Ch R = 1 ,2910    ,498,498,498
BEGIN DESCRIPTION:
UNT022 IN GIBB 5.0
END DESCRIPTION:
XS GIS Cut Line= 3
       3672242.1     10230841.65      3671923.39      10231303.9
      3671881.79     10232017.91
#Sta/Elev= 30
  4682.5  349.41  4710.9  346.98  4725.8  344.41  4740.7  343.16  4789.2  340.53
  4812.3  339.35  4833.3  337.38  4898.9  335.35  4919.8  334.03  4949.6  333.58
  4970.6  331.44  4976.6  329.45  4985.4  329.82  4988.5  328.35  4991.3  327.85
  4994.5  328.35  4998.3  328.85  5006.4  328.37  5027.3  332.74  5052.4   333.2
  5078.1  332.14  5084.1  332.79  5200.5  331.72  5271.8  332.55  5311.8  331.88
  5592.3  334.89  5662.4  335.01  5842.7  339.18  5892.8  339.59  5959.2  341.14
#Mann= 5 ,-1 , 0
  4682.5     .05       0  4789.2     .16       0  4988.5     .07       0
  4994.5     .16       0  5052.4     .05       0
Bank Sta=4988.5,4994.5
XS Rating Curve= 0 ,0
Exp/Cntr=0.3,0.1

Type RM Length L Ch R = 1 ,2412    ,414,414,414
BEGIN DESCRIPTION:
UNT022 IN GIBB 4.0
END DESCRIPTION:
XS GIS Cut Line= 3
      3672344.92     10230652.75      3671894.88     10230702.75
      3671192.13     10231441.62
#Sta/Elev= 30
  4349.1  348.83  4471.9  349.96    4523  347.69  4561.8  342.03  4593.4  339.66
  4704.1  335.19  4930.5  330.03  4958.7  328.54  4965.9  330.16  4979.8  330.38
  4993.9  328.33  4998.2  326.17  5000.9  325.67  5004.2  326.17  5015.3   330.2
  5022.2  330.68  5269.7  330.72  5283.9  328.88  5291.2  330.75  5319.5  330.55
  5347.8  328.29  5354.7   330.3  5376.1  331.29  5404.4  330.19  5411.3  327.61
  5418.6  327.21  5421.5  328.29  5425.5  329.79  5453.8  331.43  5821.6  346.73
#Mann= 6 ,-1 , 0
  4349.1      .1       0  4471.9     .05       0  4930.5     .16       0
  4998.2     .07       0  5004.2     .16       0  5421.5     .05       0
Bank Sta=4998.2,5004.2
XS Rating Curve= 0 ,0
Exp/Cntr=0.3,0.1

Type RM Length L Ch R = 1 ,1998    ,1654,1654,1654
BEGIN DESCRIPTION:
UNT022 IN GIBB 3.0
END DESCRIPTION:
XS GIS Cut Line= 3
      3672092.13     10230391.63      3671353.94     10230665.01
      3670892.15     10230841.63
#Sta/Elev= 30
  4365.9  347.21  4436.6   341.9  4483.2  340.24  4522.4   336.4  4726.2  331.03
  4739.2  331.37  4754.9  329.46  4810.4  328.46  4973.8  328.79  5005.8  324.58
  5017.8  327.88  5027.1  328.32  5103.6  329.22  5189.1  328.24  5208.2  322.96
  5211.4  323.46  5213.8  326.12  5219.3   330.1  5226.8  330.59  5251.4  331.96
  5268.5  329.89  5298.6  331.04  5323.3  336.48  5337.1  336.01  5353.4  333.01
  5358.7  333.88  5378.1  332.43  5432.8  337.52  5547.7  341.39  5647.5     346
#Mann= 5 ,-1 , 0
  4365.9     .05       0  4726.2     .16       0  4973.8     .07       0
  5226.8     .16       0  5226.8     .05       0
Bank Sta=5189.1,5219.3
XS Rating Curve= 0 ,0
Exp/Cntr=0.3,0.1

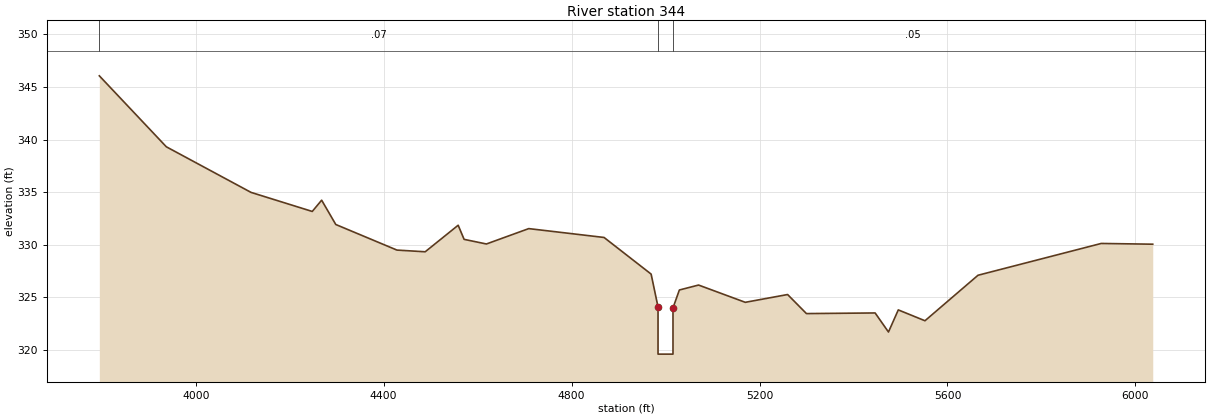
Type RM Length L Ch R = 1 ,344     ,0,0,0
BEGIN DESCRIPTION:
UNT022 IN GIBB 1.0
END DESCRIPTION:
XS GIS Cut Line= 3
      3672334.47     10229923.32      3670795.98     10229830.36
      3670276.25     10230300.63
#Sta/Elev= 30
  3794.8  346.05  3937.4  339.31  4117.7  334.98    4248  333.17    4268  334.24
  4298.1  331.93  4428.3   329.5  4488.4  329.34  4558.6  331.86  4571.2  330.52
  4618.7  330.08  4708.8  331.54  4869.1   330.7  4969.3  327.22 4983.98   324.1
 4983.99  319.62 5015.84  319.62 5015.85  324.01  5029.4  325.71  5070.3  326.18
  5169.7  324.54  5259.8  325.28  5299.9  323.47  5446.1  323.53  5474.5  321.72
  5495.4  323.82  5552.2  322.79  5665.1  327.11  5927.3  330.13    6037  330.06
#Mann= 3 , 0 , 0
  3794.8     .07       0 4983.98     .04       0 5015.85     .05       0
Bank Sta=4983.98,5015.85
XS Rating Curve= 0 ,0
Exp/Cntr=0.3,0.1

Chan Stop Cuts=-1
Use User Specified Reach Order=0
Composite Channel Slope=5