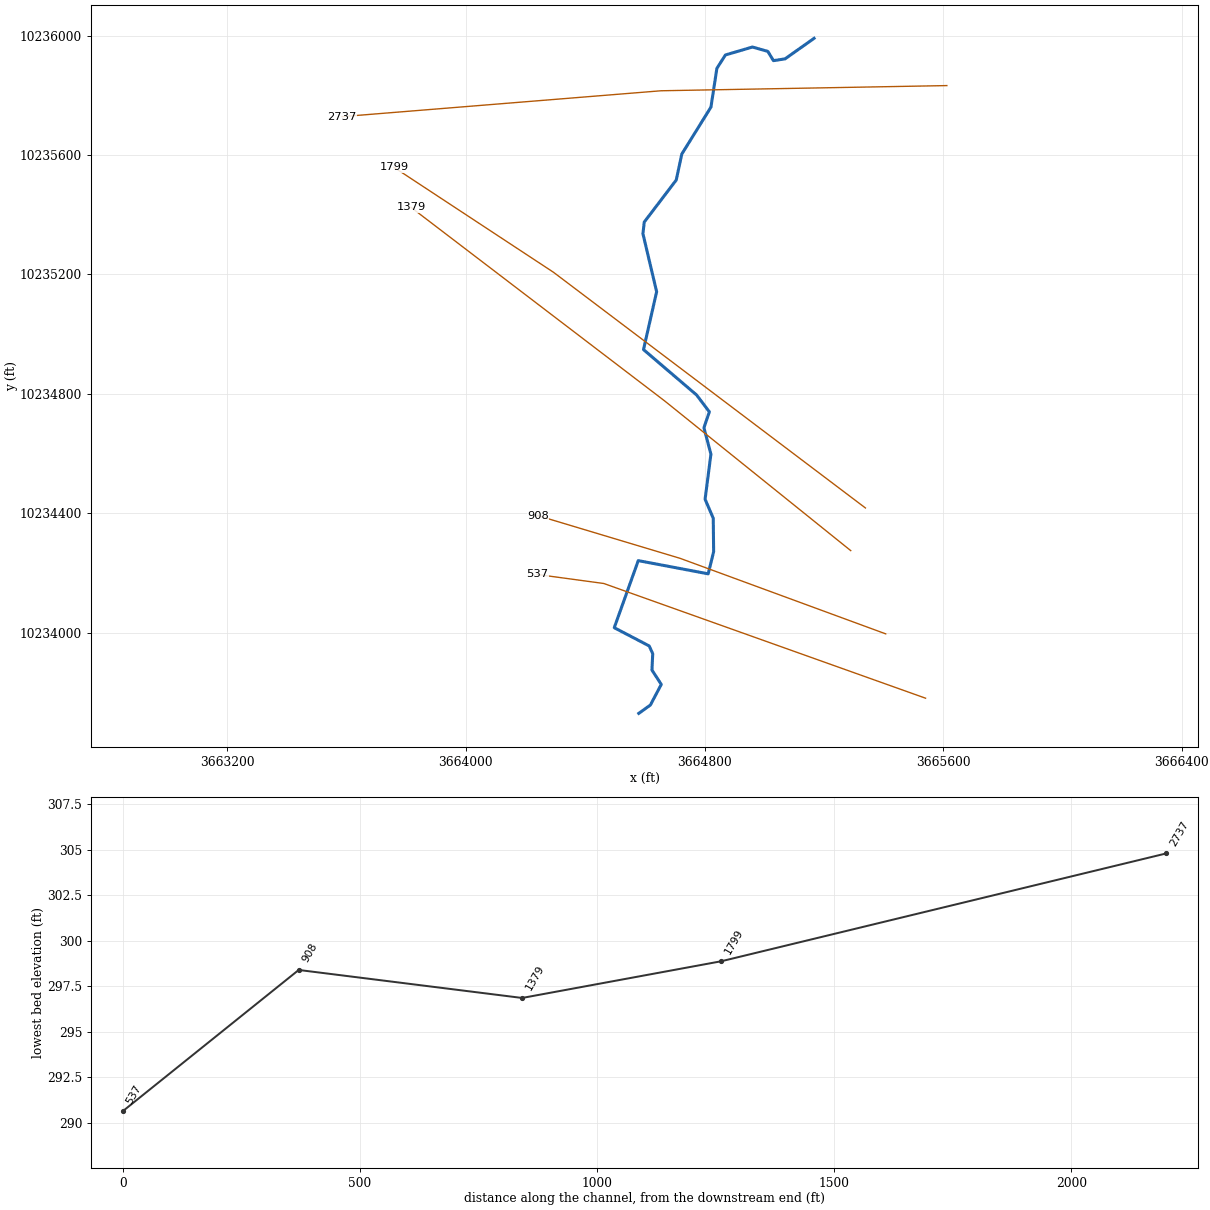
--- UNT024 IN GIBB.prj (project) ---

Proj Title=UNT024 IN GIBB Base Level Engineering
Current Plan=p01
Default Exp/Contr=0.3,0.1
English Units
Geom File=g01
Flow File=f01
Plan File=p01
BEGIN DESCRIPTION:
UNT024 IN GIBB
END DESCRIPTION:

--- UNT024 IN GIBB.p01 (plan) ---

Plan Title=Multiple Run
Short Identifier=Multiple
Geom File=g01
Flow File=f01
Subcritical Flow
K Sum by GR= 0
Std Step Tol= 0.01
Critical Tol= 0.01
Num of Std Step Trials= 20
Max Error Tol= 0.3
Flow Tol Ratio= 0.001
Split Flow NTrial= 30
Split Flow Tol= 0.02
Split Flow Ratio= 0.02
Log Output Level= 0
Friction Slope Method= 1
Unsteady Friction Slope Method= 2
Unsteady Bridges Friction Slope Method= 1
Parabolic Critical Depth
Global Vel Dist=  1 , 1 , 1
Global Log Level= 0
CheckData=True
Encroach Param= -1, 0, 0, 0
BEGIN DESCRIPTION:
Multiple Run
END DESCRIPTION:

--- UNT024 IN GIBB.f01 (steady flow) ---

Flow Title=Multiple
Number of Profiles=7
Profile Names=10-year,25-year,50-year,1pct_min,100-year,1pct_plu,500-year
River Rch & RM= UNT024 IN GIBB,Reach-1,2737
     933    1292    1593    1439    1946    2632    2905
Boundary for River Rch & Prof#=UNT024 IN GIBB,Reach-1,1
Up Type=0
Dn Type=3
Dn Slope=0.005
Boundary for River Rch & Prof#=UNT024 IN GIBB,Reach-1,2
Up Type=0
Dn Type=3
Dn Slope=0.005
Boundary for River Rch & Prof#=UNT024 IN GIBB,Reach-1,3
Up Type=0
Dn Type=3
Dn Slope=0.005
Boundary for River Rch & Prof#=UNT024 IN GIBB,Reach-1,4
Up Type=0
Dn Type=3
Dn Slope=0.005
Boundary for River Rch & Prof#=UNT024 IN GIBB,Reach-1,5
Up Type=0
Dn Type=3
Dn Slope=0.005
Boundary for River Rch & Prof#=UNT024 IN GIBB,Reach-1,6
Up Type=0
Dn Type=3
Dn Slope=0.005
Boundary for River Rch & Prof#=UNT024 IN GIBB,Reach-1,7
Up Type=0
Dn Type=3
Dn Slope=0.005

--- UNT024 IN GIBB.g01 (geometry) ---

Geom Title=Existing Conditions

River Reach=UNT024 IN GIBB,Reach-1
Reach XY= 30
      3665167.19     10235991.39      3665070.05     10235922.64
      3665030.99     10235916.65      3665012.24     10235947.64
      3664960.68     10235962.23      3664870.05     10235935.66
      3664841.41     10235890.61      3664821.62     10235760.92
      3664723.96     10235603.63      3664705.21     10235516.39
      3664598.11     10235375.71      3664593.65     10235336.61
      3664639.59     10235142.17      3664595.58     10234948.34
      3664773.35     10234796.25      3664816.28     10234739.74
      3664798.05     10234686.36      3664821.49     10234597.82
      3664801.96     10234446.77      3664829.30     10234382.97
      3664830.61     10234270.99      3664812.38     10234196.77
      3664578.00     10234241.05      3664497.57     10234016.26
      3664614.76     10233955.06      3664626.48     10233929.02
      3664623.88     10233874.33      3664655.13     10233826.16
      3664618.67     10233757.15      3664579.74     10233729.15

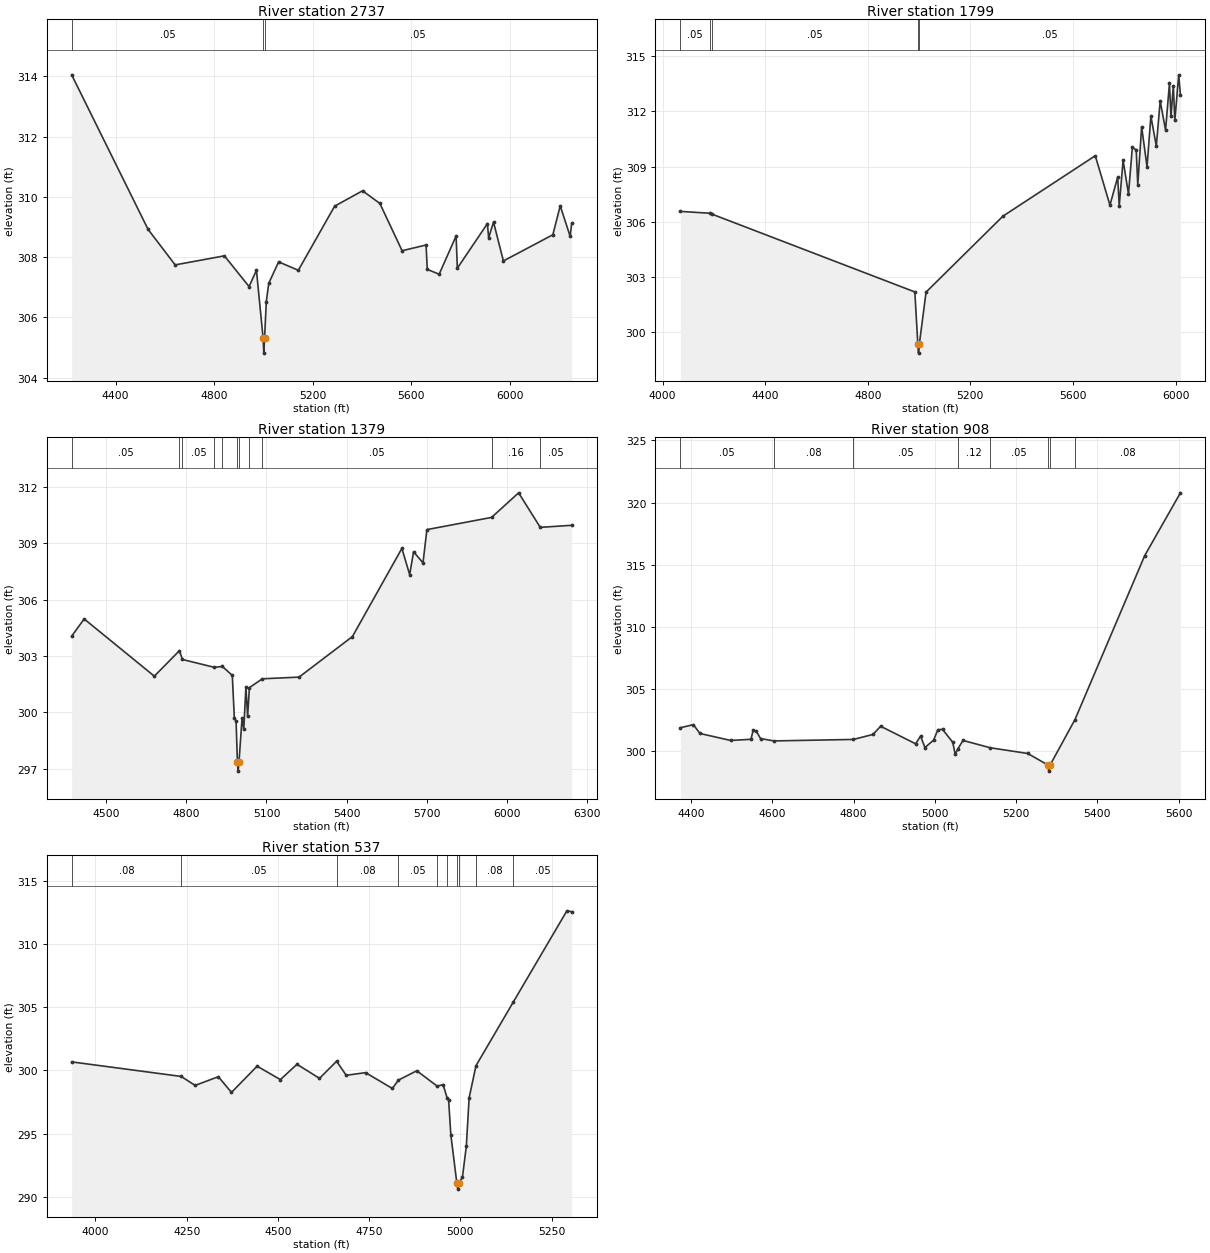
Type RM Length L Ch R = 1,2737,938,938,938
BEGIN DESCRIPTION:
UNT024 IN GIBB 5.0
END DESCRIPTION:
XS GIS Cut Line= 3
      3665612.19     10235833.04      3664654.56     10235815.69
      3663585.76     10235728.99
#Sta/Elev= 30
  4222.0  314.05  4532.1  308.92  4642.2  307.74  4842.2  308.04  4942.2  307.02
  4972.2  307.56  4999.2  305.31  5002.0  304.81  5005.2  305.31  5012.2  306.52
  5022.2  307.13  5062.2  307.84  5142.2  307.56  5289.7  309.69  5403.0  310.20
  5473.2  309.78  5563.5  308.21  5660.8  308.40  5665.8  307.59  5714.0  307.43
  5782.8  308.70  5787.8  307.63  5909.9  309.11  5914.9  308.64  5934.7  309.16
  5974.8  307.87  6175.5  308.74  6205.6  309.70  6245.7  308.69  6252.1  309.12
#Mann=3,-1,0
  4222.0    0.05       0  4999.2    0.04       0  5005.2    0.05       0
Bank Sta=4999.2,5005.2
Exp/Cntr=0.3,0.1

Type RM Length L Ch R = 1,1799,420,420,420
BEGIN DESCRIPTION:
UNT024 IN GIBB 4.0
END DESCRIPTION:
XS GIS Cut Line= 3
      3665339.31     10234417.51      3664293.96     10235207.38
      3663759.56     10235558.96
#Sta/Elev= 30
  4069.2  306.57  4184.7  306.47  4190.8  306.43  4983.5  302.20  4995.1  299.38
  4997.8  298.88  5001.1  299.38  5027.2  302.19  5326.9  306.31  5687.1  309.59
  5744.3  306.91  5774.5  308.43  5780.5  306.87  5795.6  309.34  5816.6  307.52
  5831.7  310.05  5846.8  309.90  5852.8  308.01  5867.9  311.16  5888.9  308.99
  5904.0  311.74  5925.1  310.11  5940.2  312.56  5961.2  310.98  5976.3  313.51
  5982.3  311.72  5991.4  313.38  5997.4  311.51  6012.5  313.98  6019.1  312.89
#Mann=5,-1,0
  4069.2    0.05       0  4184.7    0.16       0  4190.8    0.05       0
  4995.1    0.03       0  5001.1    0.05       0
Bank Sta=4995.1,5001.1
Exp/Cntr=0.3,0.1

Type RM Length L Ch R = 1,1379,471,471,471
BEGIN DESCRIPTION:
UNT024 IN GIBB 3.0
END DESCRIPTION:
XS GIS Cut Line= 3
      3665290.06     10234274.56      3664666.63     10234776.12
      3663816.43     10235424.89
#Sta/Elev= 30
  4371.6  304.05  4418.3  304.97  4680.7  301.92  4774.5  303.28  4785.5  302.81
  4905.3  302.39  4935.0  302.44  4972.2  301.96  4979.9  299.67  4986.3  299.53
  4991.3  297.36  4994.0  296.86  4997.3  297.36  5008.7  299.70  5015.1  299.09
  5023.1  301.35  5029.5  299.78  5036.1  301.31  5084.5  301.78  5221.8  301.87
  5421.3  304.03  5606.3  308.73  5635.4  307.33  5649.9  308.55  5685.2  307.96
  5699.8  309.73  5941.6  310.38  6042.7  311.69  6123.7  309.85  6241.2  309.96
#Mann=11,-1,0
  4371.6    0.05       0  4774.5    0.12       0  4785.5    0.05       0
  4905.3    0.12       0  4935.0    0.05       0  4991.3   0.035       0
  4997.3    0.05       0  5036.1    0.12       0  5084.5    0.05       0
  5941.6    0.16       0  6123.7    0.05       0
Bank Sta=4991.3,4997.3
Exp/Cntr=0.3,0.1

Type RM Length L Ch R = 1,908,371,371,371
BEGIN DESCRIPTION:
UNT024 IN GIBB 2.0
END DESCRIPTION:
XS GIS Cut Line= 3
      3665407.26     10233995.63      3664718.19     10234248.75
      3664242.06     10234391.66
#Sta/Elev= 30
  4373.4  301.89  4405.4  302.14  4421.5  301.43  4496.9  300.87  4547.2  300.96
  4552.5  301.67  4560.0  301.64  4570.7  301.02  4603.5  300.83  4799.4  300.95
  4847.6  301.35  4866.5  302.01  4952.6  300.60  4964.8  301.22  4975.5  300.30
  4996.8  300.89  5007.4  301.73  5018.9  301.76  5044.0  300.72  5050.1  299.76
  5057.1  300.21  5069.2  300.87  5136.4  300.28  5228.7  299.82  5277.9  298.90
  5280.6  298.40  5283.9  298.90  5345.0  302.55  5516.7  315.74  5604.6  320.79
#Mann=8,-1,0
  4373.4    0.05       0  4603.5    0.08       0  4799.4    0.05       0
  5057.1    0.12       0  5136.4    0.05       0  5277.9    0.04       0
  5283.9    0.05       0  5345.0    0.08       0
Bank Sta=5277.9,5283.9
Exp/Cntr=0.3,0.1

Type RM Length L Ch R = 1,537,0,0,0
BEGIN DESCRIPTION:
UNT024 IN GIBB 1.0
END DESCRIPTION:
XS GIS Cut Line= 3
      3665540.86     10233779.99      3664462.72     10234164.38
      3664238.98     10234194.77
#Sta/Elev= 30
  3934.9  300.68  4235.1  299.53  4273.3  298.82  4336.8  299.51  4372.9  298.27
  4443.2  300.34  4506.9  299.28  4552.4  300.49  4614.1  299.38  4661.0  300.73
  4687.3  299.62  4740.4  299.83  4813.8  298.58  4830.4  299.24  4880.8  299.98
  4936.7  298.76  4952.8  298.89  4963.9  297.83  4967.9  297.70  4974.0  294.94
  4990.4  291.13  4993.2  290.63  4996.4  291.13  5005.8  291.56  5016.5  294.02
  5024.2  297.84  5043.0  300.38  5145.3  305.41  5292.1  312.61  5305.3  312.54
#Mann=10,-1,0
  3934.9    0.08       0  4235.1    0.05       0  4661.0    0.08       0
  4830.4    0.05       0  4936.7    0.16       0  4963.9    0.05       0
  4990.4    0.04       0  4996.4    0.05       0  5043.0    0.08       0
  5145.3    0.05       0
Bank Sta=4990.4,4996.4
Exp/Cntr=0.3,0.1

Chan Stop Cuts=-1