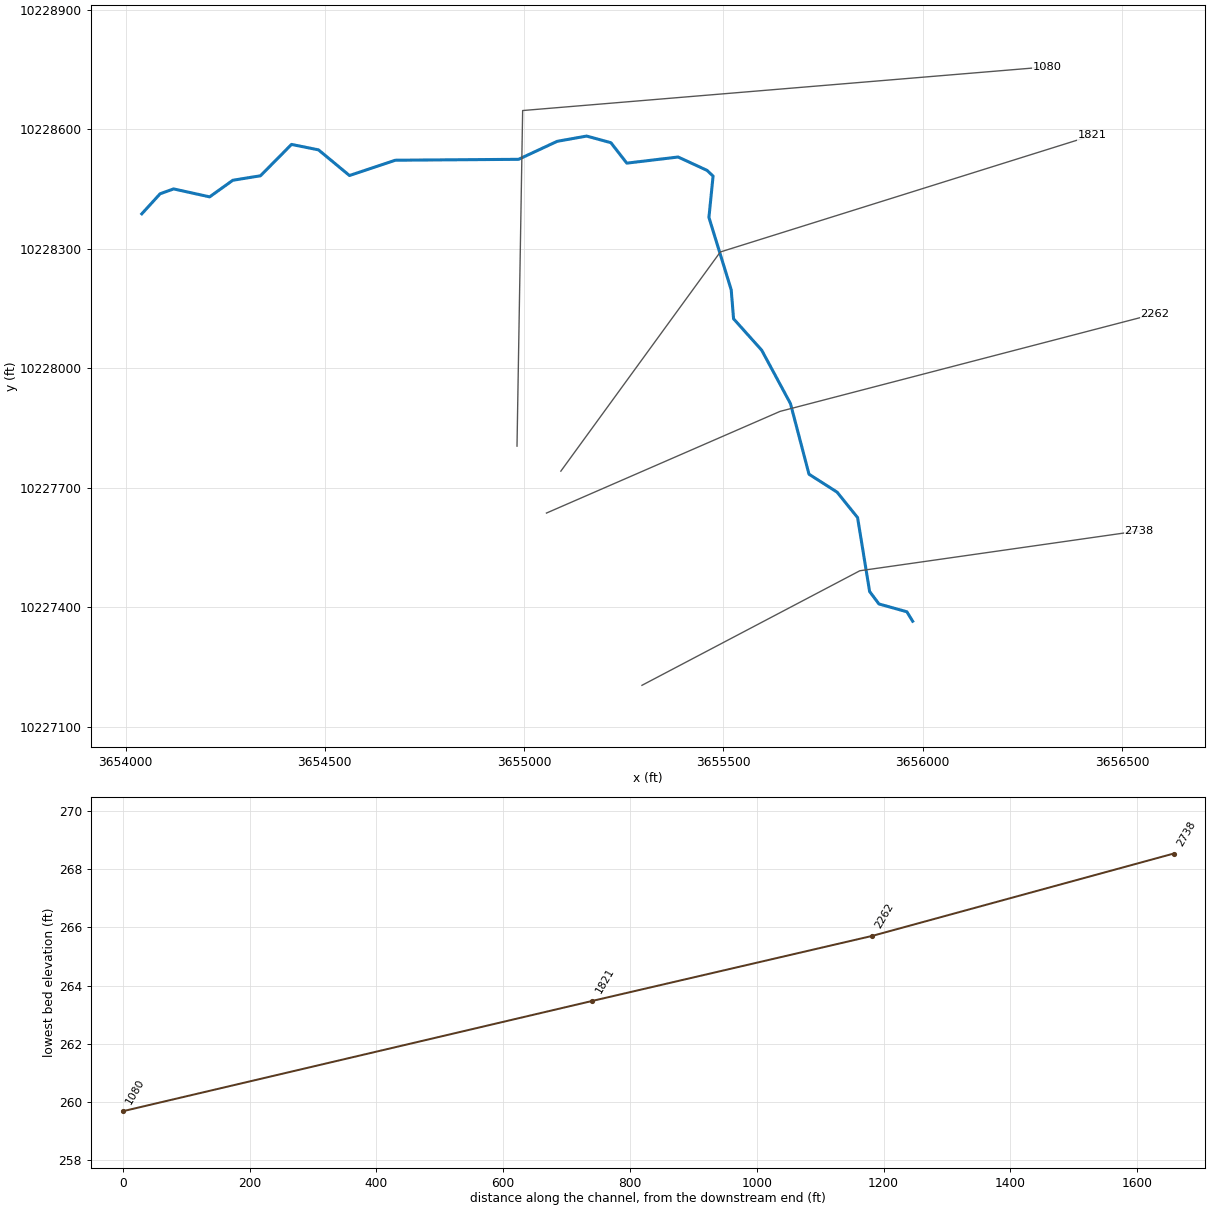
--- UNT025 IN GIBB.prj (project) ---

Proj Title=UNT025 IN GIBB Base Level Engineering
Current Plan=p01
Default Exp/Contr=0.3,0.1
English Units
Geom File=g01
Flow File=f01
Plan File=p01
BEGIN DESCRIPTION:
UNT025 IN GIBB
END DESCRIPTION:

--- UNT025 IN GIBB.p01 (plan) ---

Plan Title=Multiple Run
Short Identifier=Multiple
Geom File=g01
Flow File=f01
Subcritical Flow
K Sum by GR= 0
Std Step Tol= 0.01
Critical Tol= 0.01
Num of Std Step Trials= 20
Max Error Tol= 0.3
Flow Tol Ratio= 0.001
Split Flow NTrial= 30
Split Flow Tol= 0.02
Split Flow Ratio= 0.02
Log Output Level= 0
Friction Slope Method= 1
Unsteady Friction Slope Method= 2
Unsteady Bridges Friction Slope Method= 1
Parabolic Critical Depth
Global Vel Dist=  1 , 1 , 1
Global Log Level= 0
CheckData=True
Encroach Param= -1, 0, 0, 0
BEGIN DESCRIPTION:
Multiple Run
END DESCRIPTION:

--- UNT025 IN GIBB.f01 (steady flow) ---

Flow Title=Multiple
Number of Profiles=7
Profile Names=10-year,25-year,50-year,1pct_min,100-year,1pct_plu,500-year
River Rch & RM= UNT025 IN GIBB,Reach-1,2738
     423     555     661     578     782    1057    1093
Boundary for River Rch & Prof#=UNT025 IN GIBB,Reach-1,1
Up Type=0
Dn Type=3
Dn Slope=0.005
Boundary for River Rch & Prof#=UNT025 IN GIBB,Reach-1,2
Up Type=0
Dn Type=3
Dn Slope=0.005
Boundary for River Rch & Prof#=UNT025 IN GIBB,Reach-1,3
Up Type=0
Dn Type=3
Dn Slope=0.005
Boundary for River Rch & Prof#=UNT025 IN GIBB,Reach-1,4
Up Type=0
Dn Type=3
Dn Slope=0.005
Boundary for River Rch & Prof#=UNT025 IN GIBB,Reach-1,5
Up Type=0
Dn Type=3
Dn Slope=0.005
Boundary for River Rch & Prof#=UNT025 IN GIBB,Reach-1,6
Up Type=0
Dn Type=3
Dn Slope=0.005
Boundary for River Rch & Prof#=UNT025 IN GIBB,Reach-1,7
Up Type=0
Dn Type=3
Dn Slope=0.005

--- UNT025 IN GIBB.g01 (geometry) ---

Geom Title=Existing Conditions

River Reach=UNT025 IN GIBB,Reach-1
Reach XY= 30
      3655974.61     10227365.01      3655960.12     10227388.69
      3655890.13     10227408.28      3655866.66     10227439.58
      3655836.47     10227625.08      3655785.04     10227688.95
      3655714.58     10227734.00      3655668.18     10227911.02
      3655596.01     10228045.07      3655525.38     10228124.03
      3655519.50     10228196.60      3655463.59     10228378.39
      3655473.97     10228482.08      3655458.92     10228496.40
      3655386.28     10228530.00      3655257.52     10228514.59
      3655217.63     10228565.93      3655156.87     10228582.55
      3655083.03     10228569.40      3654985.99     10228524.21
      3654676.94     10228521.93      3654561.85     10228483.55
      3654484.12     10228547.94      3654416.44     10228561.59
      3654338.66     10228482.93      3654269.22     10228471.64
      3654211.06     10228429.98      3654120.78     10228449.94
      3654086.92     10228437.79      3654040.92     10228387.44

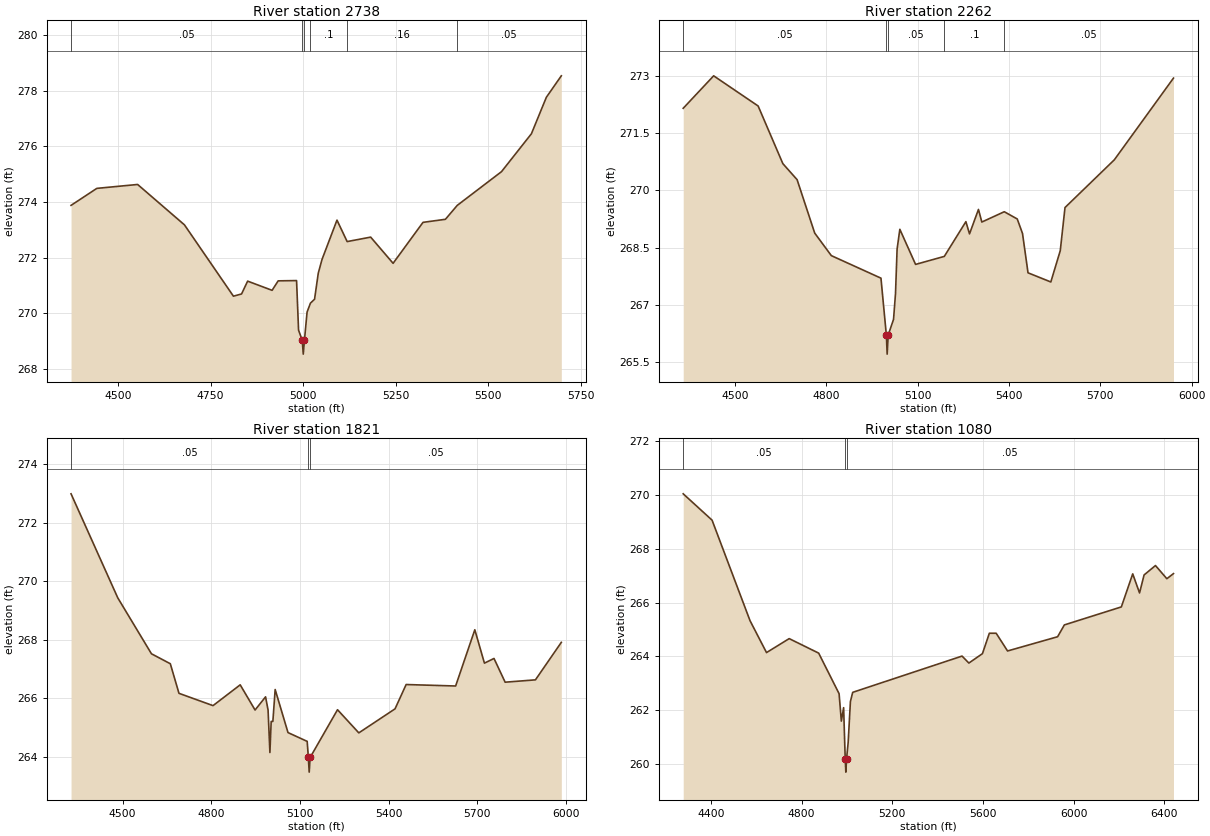
Type RM Length L Ch R = 1,2738,476,476,476
BEGIN DESCRIPTION:
UNT025 IN GIBB 4.0
END DESCRIPTION:
XS GIS Cut Line= 3
      3655295.59     10227204.14      3655842.11     10227491.64
      3656542.07     10227591.64
#Sta/Elev= 30
  4373.2  273.88  4442.9  274.49  4553.1  274.63  4679.6  273.18  4811.9  270.62
  4833.9  270.70  4850.3  271.16  4916.4  270.83  4932.8  271.17  4982.5  271.18
  4987.9  269.40  4997.8  269.04  5000.6  268.54  5003.8  269.04  5010.9  270.05
  5020.0  270.37  5031.1  270.51  5041.2  271.45  5051.3  271.94  5091.7  273.35
  5119.2  272.58  5182.7  272.74  5243.3  271.80  5324.1  273.27  5384.7  273.38
  5416.7  273.88  5536.2  275.09  5617.0  276.45  5657.4  277.76  5697.8  278.53
#Mann=6,-1,0
  4373.2    0.05       0  4997.8    0.03       0  5003.8    0.05       0
  5020.0     0.1       0  5119.2    0.16       0  5416.7    0.05       0
Bank Sta=4997.8,5003.8
Exp/Cntr=0.3,0.1

Type RM Length L Ch R = 1,2262,441,441,441
BEGIN DESCRIPTION:
UNT025 IN GIBB 3.0
END DESCRIPTION:
XS GIS Cut Line= 3
      3655056.00     10227636.43      3655642.11     10227891.64
      3656582.00     10228136.41
#Sta/Elev= 30
  4329.8  272.15  4429.8  273.00  4575.9  272.21  4657.1  270.70  4703.9  270.28
  4761.8  268.88  4816.4  268.29  4979.4  267.70  4997.1  266.21  4999.8  265.71
  5003.1  266.21  5020.7  266.62  5027.2  267.30  5032.4  268.46  5041.4  268.98
  5093.1  268.06  5187.5  268.27  5258.4  269.18  5270.3  268.86  5299.7  269.50
  5310.8  269.17  5384.5  269.44  5427.1  269.25  5444.4  268.87  5462.5  267.84
  5537.4  267.60  5568.4  268.42  5584.0  269.55  5746.0  270.80  5940.3  272.94
#Mann=5,-1,0
  4329.8    0.05       0  4997.1    0.03       0  5003.1    0.05       0
  5187.5     0.1       0  5384.5    0.05       0
Bank Sta=4997.1,5003.1
Exp/Cntr=0.3,0.1

Type RM Length L Ch R = 1,1821,741,741,741
BEGIN DESCRIPTION:
UNT025 IN GIBB 2.0
END DESCRIPTION:
XS GIS Cut Line= 3
      3655092.12     10227741.67      3655492.11     10228291.64
      3656425.76     10228584.33
#Sta/Elev= 30
  4325.6  272.98  4483.6  269.43  4597.6  267.52  4661.4  267.18  4690.7  266.17
  4805.9  265.75  4897.8  266.46  4948.1  265.60  4983.6  266.05  4992.1  265.60
  4998.3  264.15  5002.6  265.21  5008.3  265.21  5016.1  266.30  5059.5  264.83
  5124.4  264.53  5128.4  263.98  5131.2  263.48  5134.4  263.98  5227.0  265.61
  5299.1  264.82  5421.6  265.64  5459.2  266.47  5626.6  266.42  5691.5  268.34
  5724.0  267.20  5756.4  267.36  5794.1  266.55  5896.6  266.63  5984.1  267.91
#Mann=3,-1,0
  4325.6    0.05       0  5128.4    0.03       0  5134.4    0.05       0
Bank Sta=5128.4,5134.4
Exp/Cntr=0.3,0.1

Type RM Length L Ch R = 1,1080,0,0,0
BEGIN DESCRIPTION:
UNT025 IN GIBB 1.0
END DESCRIPTION:
XS GIS Cut Line= 3
      3654982.12     10227804.44      3654996.28     10228646.62
      3656311.22     10228756.22
#Sta/Elev= 30
  4277.9  270.05  4405.1  269.07  4572.4  265.33  4645.2  264.14  4745.2  264.66
  4875.2  264.12  4965.2  262.61  4975.2  261.59  4985.2  262.09  4992.2  260.19
  4995.0  259.69  4998.2  260.19  5005.2  260.79  5015.2  262.32  5025.2  262.66
  5507.4  264.01  5537.5  263.75  5597.3  264.10  5627.8  264.86  5657.9  264.86
  5708.1  264.20  5928.8  264.73  5958.6  265.17  6209.8  265.84  6260.0  267.07
  6290.1  266.36  6310.1  267.03  6360.3  267.38  6410.5  266.89  6439.7  267.08
#Mann=3,-1,0
  4277.9    0.05       0  4992.2    0.03       0  4998.2    0.05       0
Bank Sta=4992.2,4998.2
Exp/Cntr=0.3,0.1

Chan Stop Cuts=-1