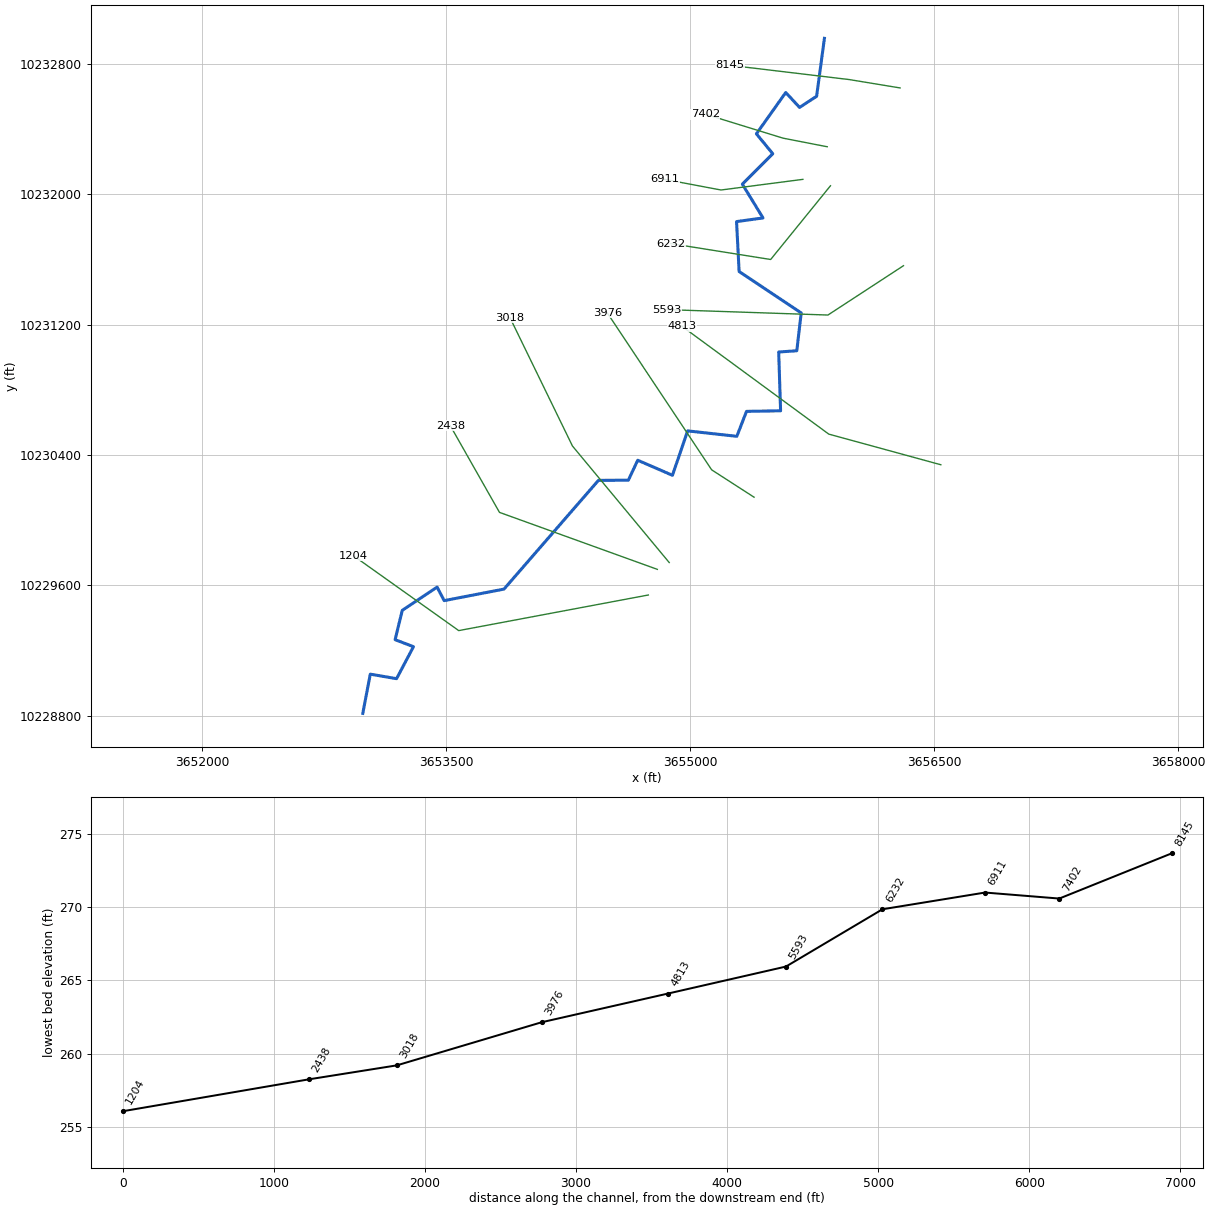
--- UNT026 IN GIBB.prj (project) ---

Proj Title=UNT026 IN GIBB Base Level Engineering
Current Plan=p01
Default Exp/Contr=0.3,0.1
English Units
Geom File=g01
Flow File=f01
Plan File=p01
BEGIN DESCRIPTION:
UNT026 IN GIBB
END DESCRIPTION:

--- UNT026 IN GIBB.p01 (plan) ---

Plan Title=Multiple Run
Short Identifier=Multiple
Geom File=g01
Flow File=f01
Subcritical Flow
K Sum by GR= 0
Std Step Tol= 0.01
Critical Tol= 0.01
Num of Std Step Trials= 20
Max Error Tol= 0.3
Flow Tol Ratio= 0.001
Split Flow NTrial= 30
Split Flow Tol= 0.02
Split Flow Ratio= 0.02
Log Output Level= 0
Friction Slope Method= 1
Unsteady Friction Slope Method= 2
Unsteady Bridges Friction Slope Method= 1
Parabolic Critical Depth
Global Vel Dist=  1 , 1 , 1
Global Log Level= 0
CheckData=True
Encroach Param= -1, 0, 0, 0
BEGIN DESCRIPTION:
Multiple Run
END DESCRIPTION:

--- UNT026 IN GIBB.f01 (steady flow) ---

Flow Title=Multiple
Number of Profiles=7
Profile Names=10-year,25-year,50-year,1pct_min,100-year,1pct_plu,500-year
River Rch & RM= UNT026 IN GIBB,Reach-1,8145
     513     673     799     695     940    1271    1301
River Rch & RM= UNT026 IN GIBB,Reach-1,7402
     723     964    1159    1019    1378    1864    1951
Boundary for River Rch & Prof#=UNT026 IN GIBB,Reach-1,1
Up Type=0
Dn Type=3
Dn Slope=0.005
Boundary for River Rch & Prof#=UNT026 IN GIBB,Reach-1,2
Up Type=0
Dn Type=3
Dn Slope=0.005
Boundary for River Rch & Prof#=UNT026 IN GIBB,Reach-1,3
Up Type=0
Dn Type=3
Dn Slope=0.005
Boundary for River Rch & Prof#=UNT026 IN GIBB,Reach-1,4
Up Type=0
Dn Type=3
Dn Slope=0.005
Boundary for River Rch & Prof#=UNT026 IN GIBB,Reach-1,5
Up Type=0
Dn Type=3
Dn Slope=0.005
Boundary for River Rch & Prof#=UNT026 IN GIBB,Reach-1,6
Up Type=0
Dn Type=3
Dn Slope=0.005
Boundary for River Rch & Prof#=UNT026 IN GIBB,Reach-1,7
Up Type=0
Dn Type=3
Dn Slope=0.005

--- UNT026 IN GIBB.g01 (geometry) ---

Geom Title=Existing Conditions

River Reach=UNT026 IN GIBB,Reach-1
Reach XY= 30
      3655824.69     10232956.88      3655776.67     10232601.34
      3655671.86     10232533.03      3655586.90     10232624.49
      3655406.52     10232371.01      3655507.13     10232248.80
      3655320.07     10232062.35      3655447.07     10231854.89
      3655284.38     10231832.62      3655300.23     10231526.39
      3655681.93     10231272.44      3655654.83     10231040.14
      3655543.51     10231032.48      3655555.19     10230671.74
      3655345.64     10230668.28      3655286.16     10230515.18
      3654983.71     10230548.53      3654890.30     10230275.98
      3654676.86     10230368.42      3654619.02     10230245.86
      3654435.16     10230244.95      3653854.49     10229577.88
      3653486.77     10229507.08      3653443.22     10229590.06
      3653229.14     10229447.41      3653185.04     10229267.44
      3653297.96     10229224.49      3653193.99     10229028.21
      3653032.46     10229056.00      3652986.32     10228815.36

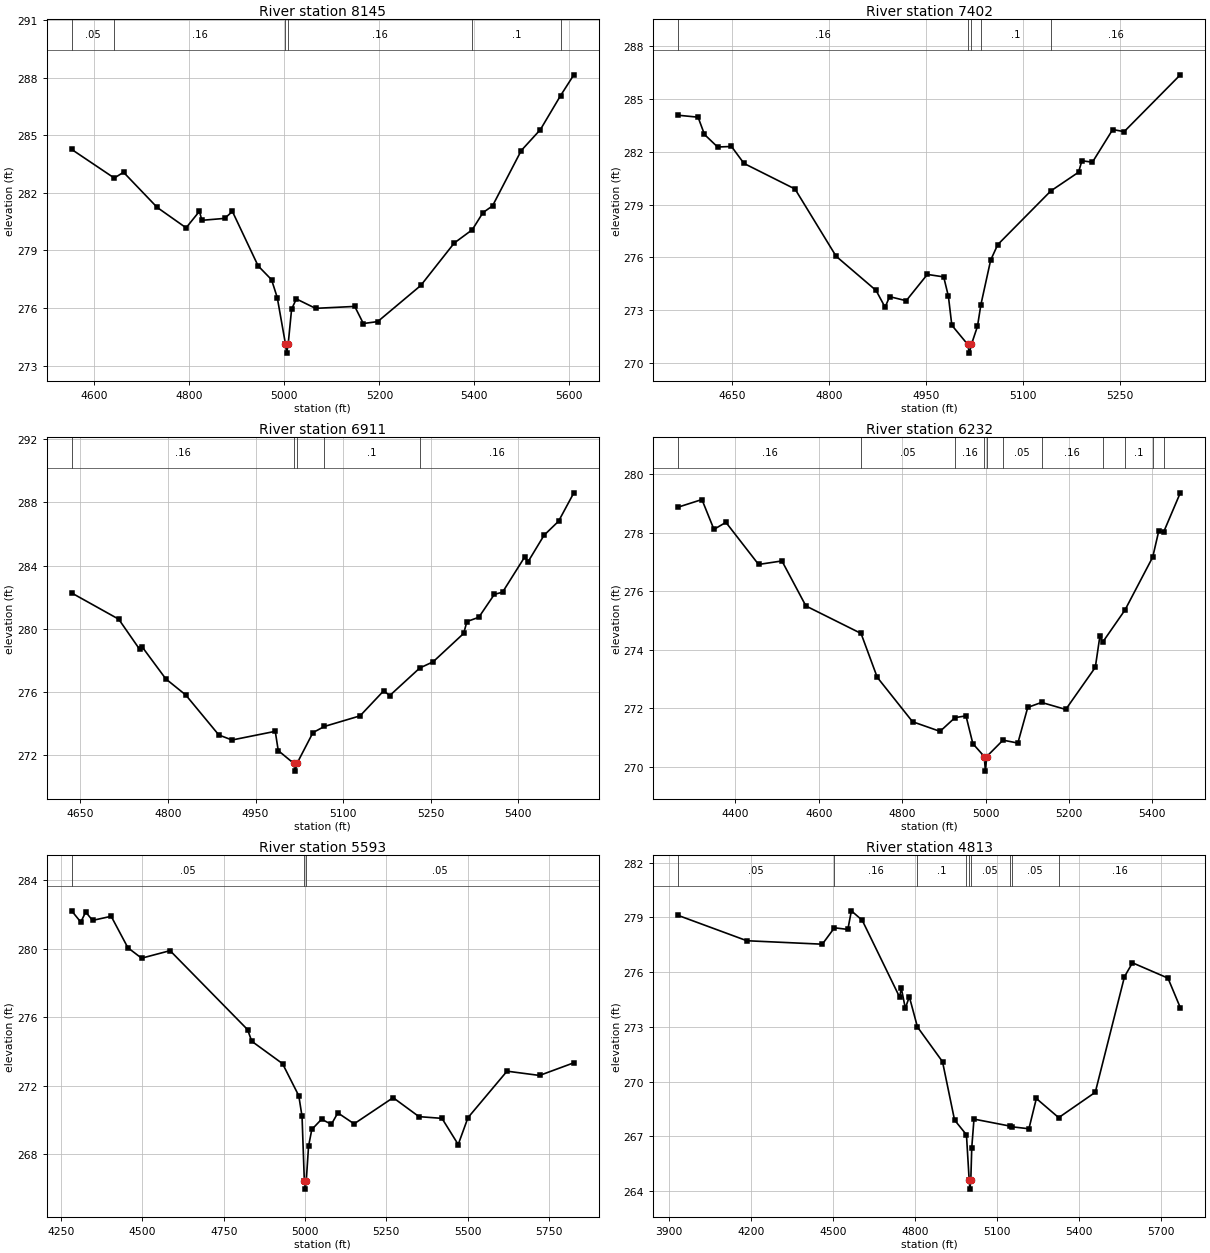
Type RM Length L Ch R = 1,8145,743,743,743
BEGIN DESCRIPTION:
UNT026 IN GIBB 11.0
END DESCRIPTION:
XS GIS Cut Line= 3
      3656289.85     10232652.56      3655977.29     10232703.93
      3655242.15     10232791.64
#Sta/Elev= 30
  4552.2  284.26  4641.9  282.77  4661.4  283.07  4732.3  281.24  4793.1  280.18
  4821.2  281.04  4826.3  280.57  4874.2  280.67  4890.6  281.03  4944.7  278.20
  4973.0  277.48  4985.0  276.55  5002.1  274.16  5004.8  273.66  5008.1  274.16
  5015.2  275.95  5025.2  276.48  5065.6  275.99  5148.1  276.09  5166.2  275.20
  5196.4  275.30  5287.1  277.18  5357.6  279.39  5395.5  280.08  5418.0  280.97
  5438.1  281.32  5498.6  284.20  5538.9  285.29  5581.4  287.06  5609.3  288.14
#Mann=6,-1,0
  4552.2    0.05       0  4641.9    0.16       0  5002.1    0.07       0
  5008.1    0.16       0  5395.5     0.1       0  5581.4    0.16       0
Bank Sta=5002.1,5008.1
Exp/Cntr=0.3,0.1

Type RM Length L Ch R = 1,7402,491,491,491
BEGIN DESCRIPTION:
UNT026 IN GIBB 9.0
END DESCRIPTION:
XS GIS Cut Line= 3
      3655842.11     10232291.64      3655569.56     10232344.63
      3655092.14     10232491.63
#Sta/Elev= 30
  4566.2  284.06  4597.1  283.95  4607.0  282.97  4627.3  282.26  4648.8  282.29
  4668.1  281.33  4747.1  279.88  4810.7  276.07  4872.6  274.13  4886.5  273.18
  4893.5  273.78  4919.2  273.55  4951.9  275.04  4977.2  274.90  4984.5  273.80
  4989.8  272.16  5014.2  271.08  5017.0  270.58  5020.2  271.08  5029.5  272.10
  5034.8  273.33  5049.9  275.85  5060.9  276.73  5143.0  279.77  5185.9  280.83
  5191.1  281.48  5207.4  281.40  5238.8  283.25  5256.5  283.13  5343.4  286.35
#Mann=5,-1,0
  4566.2    0.16       0  5014.2    0.07       0  5020.2    0.16       0
  5034.8     0.1       0  5143.0    0.16       0
Bank Sta=5014.2,5020.2
Exp/Cntr=0.3,0.1

Type RM Length L Ch R = 1,6911,679,679,679
BEGIN DESCRIPTION:
UNT026 IN GIBB 8.0
END DESCRIPTION:
XS GIS Cut Line= 3
      3655692.08     10232091.64      3655188.76     10232026.35
      3654842.09     10232091.64
#Sta/Elev= 30
  4634.9  282.27  4715.5  280.61  4751.2  278.71  4756.2  278.83  4796.2  276.83
  4830.4  275.81  4887.0  273.28  4909.6  272.96  4983.7  273.51  4988.8  272.29
  5015.1  271.49  5017.8  270.99  5021.1  271.49  5048.3  273.43  5068.0  273.82
  5129.0  274.49  5169.6  276.08  5179.7  275.77  5231.3  277.52  5254.1  277.91
  5306.5  279.71  5312.0  280.46  5332.4  280.73  5359.0  282.18  5373.1  282.32
  5411.4  284.57  5416.5  284.23  5444.3  285.93  5469.0  286.81  5495.2  288.61
#Mann=5,-1,0
  4634.9    0.16       0  5015.1    0.07       0  5021.1    0.16       0
  5068.0     0.1       0  5231.3    0.16       0
Bank Sta=5015.1,5021.1
Exp/Cntr=0.3,0.1

Type RM Length L Ch R = 1,6232,639,639,639
BEGIN DESCRIPTION:
UNT026 IN GIBB 7.0
END DESCRIPTION:
XS GIS Cut Line= 3
      3655861.95     10232052.46      3655494.13     10231600.01
      3654880.85     10231697.59
#Sta/Elev= 30
  4262.9  278.88  4320.0  279.14  4348.8  278.12  4377.5  278.36  4455.8  276.92
  4511.8  277.04  4569.3  275.50  4701.5  274.56  4740.3  273.06  4825.0  271.54
  4890.9  271.21  4926.8  271.68  4953.1  271.74  4969.6  270.79  4996.9  270.35
  4999.7  269.85  5002.9  270.35  5041.9  270.91  5077.5  270.81  5101.2  272.03
  5134.3  272.20  5192.3  271.96  5263.2  273.40  5274.2  274.47  5280.8  274.26
  5334.3  275.36  5400.8  277.17  5415.1  278.05  5427.1  278.03  5467.0  279.37
#Mann=11,-1,0
  4262.9    0.16       0  4701.5    0.05       0  4926.8    0.16       0
  4996.9    0.07       0  5002.9    0.16       0  5041.9    0.05       0
  5134.3    0.16       0  5280.8    0.05       0  5334.3     0.1       0
  5400.8    0.16       0  5427.1     0.1       0
Bank Sta=4996.9,5002.9
Exp/Cntr=0.3,0.1

Type RM Length L Ch R = 1,5593,780,780,780
BEGIN DESCRIPTION:
UNT026 IN GIBB 6.0
END DESCRIPTION:
XS GIS Cut Line= 3
      3656310.72     10231561.91      3655846.28     10231259.24
      3654856.69     10231292.47
#Sta/Elev= 30
  4282.3  282.22  4310.4  281.56  4325.5  282.15  4346.6  281.66  4403.9  281.90
  4455.3  280.06  4497.4  279.45  4585.0  279.89  4823.4  275.27  4836.2  274.59
  4930.9  273.28  4980.9  271.40  4990.9  270.19  4997.9  266.44  5000.7  265.94
  5003.9  266.44  5010.9  268.45  5020.9  269.43  5051.0  270.03  5081.0  269.73
  5101.0  270.40  5151.0  269.76  5271.1  271.29  5350.6  270.18  5421.2  270.08
  5471.2  268.55  5501.2  270.12  5621.3  272.84  5721.3  272.59  5826.8  273.33
#Mann=3,-1,0
  4282.3    0.05       0  4997.9   0.035       0  5003.9    0.05       0
Bank Sta=4997.9,5003.9
Exp/Cntr=0.3,0.1

Type RM Length L Ch R = 1,4813,837,837,837
BEGIN DESCRIPTION:
UNT026 IN GIBB 5.0
END DESCRIPTION:
XS GIS Cut Line= 3
      3656540.28     10230340.81      3655851.50     10230528.66
      3654947.65     10231191.02
#Sta/Elev= 30
  3934.9  279.11  4186.0  277.72  4461.6  277.53  4505.9  278.43  4554.9  278.34
  4567.8  279.36  4607.5  278.84  4744.0  274.63  4750.2  275.12  4764.9  274.02
  4779.5  274.65  4809.2  272.99  4900.7  271.09  4944.7  267.89  4988.2  267.08
  4998.1  264.60  5000.8  264.10  5004.1  264.60  5007.6  266.38  5015.7  267.94
  5146.1  267.56  5152.8  267.52  5216.4  267.41  5243.5  269.07  5325.1  268.02
  5458.8  269.41  5565.5  275.75  5594.7  276.51  5724.3  275.67  5769.4  274.05
#Mann=9,-1,0
  3934.9    0.05       0  4505.9    0.16       0  4809.2     0.1       0
  4988.2    0.05       0  4998.1   0.035       0  5004.1    0.05       0
  5146.1     0.1       0  5152.8    0.05       0  5325.1    0.16       0
Bank Sta=4998.1,5004.1
Exp/Cntr=0.3,0.1

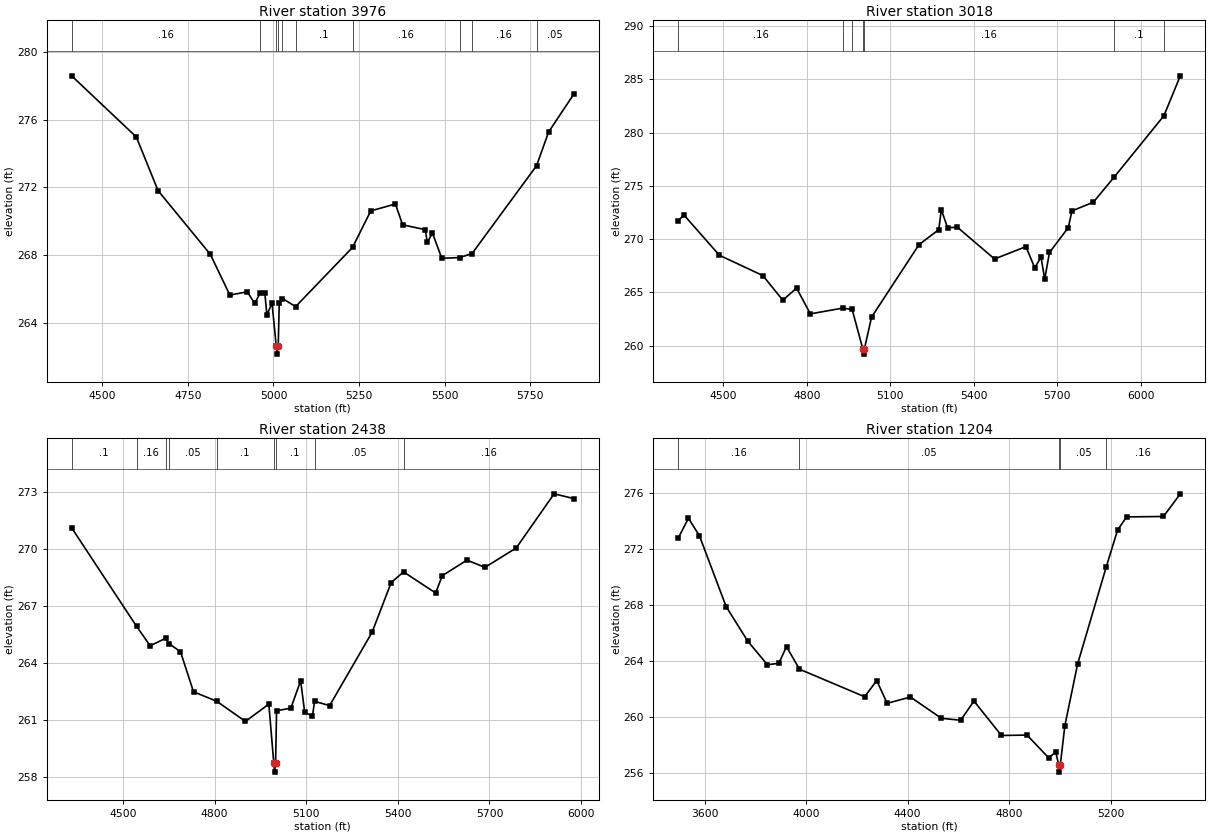
Type RM Length L Ch R = 1,3976,958,958,958
BEGIN DESCRIPTION:
UNT026 IN GIBB 4.0
END DESCRIPTION:
XS GIS Cut Line= 3
      3655392.07     10230141.66      3655131.36     10230309.49
      3654489.46     10231272.74
#Sta/Elev= 30
  4410.2  278.60  4599.3  274.98  4662.7  271.81  4815.5  268.04  4872.6  265.63
  4923.7  265.83  4944.7  265.14  4961.4  265.75  4974.8  265.73  4980.8  264.46
  4995.8  265.16  5007.9  262.64  5010.6  262.14  5013.9  262.64  5016.9  265.16
  5026.3  265.43  5064.7  264.95  5231.0  268.45  5284.3  270.61  5356.4  271.02
  5377.4  269.79  5443.6  269.50  5449.6  268.75  5464.6  269.30  5491.9  267.81
  5543.8  267.85  5580.4  268.09  5768.8  273.28  5804.1  275.28  5877.8  277.52
#Mann=10,-1,0
  4410.2    0.16       0  4961.4     0.1       0  5007.9    0.07       0
  5013.9     0.1       0  5026.3    0.05       0  5064.7     0.1       0
  5231.0    0.16       0  5543.8     0.1       0  5580.4    0.16       0
  5768.8    0.05       0
Bank Sta=5007.9,5013.9
Exp/Cntr=0.3,0.1

Type RM Length L Ch R = 1,3018,580,580,580
BEGIN DESCRIPTION:
UNT026 IN GIBB 3.0
END DESCRIPTION:
XS GIS Cut Line= 3
      3654870.41     10229740.72      3654275.54     10230455.60
      3653892.10     10231241.65
#Sta/Elev= 30
  4337.1  271.71  4357.9  272.26  4485.4  268.48  4641.7  266.57  4713.3  264.26
  4762.7  265.40  4812.2  262.98  4929.0  263.52  4962.5  263.39  5000.6  259.70
  5003.3  259.20  5006.6  259.70  5032.2  262.67  5202.8  269.48  5273.8  270.88
  5282.9  272.75  5305.4  271.06  5340.6  271.11  5474.2  268.13  5586.9  269.29
  5618.8  267.29  5641.0  268.32  5654.5  266.24  5671.5  268.74  5739.1  271.07
  5752.3  272.64  5829.2  273.46  5904.5  275.83  6082.7  281.57  6141.7  285.32
#Mann=7,-1,0
  4337.1    0.16       0  4929.0     0.1       0  4962.5    0.16       0
  5000.6    0.07       0  5006.6    0.16       0  5904.5     0.1       0
  6082.7    0.05       0
Bank Sta=5000.6,5006.6
Exp/Cntr=0.3,0.1

Type RM Length L Ch R = 1,2438,1234,1234,1234
BEGIN DESCRIPTION:
UNT026 IN GIBB 2.0
END DESCRIPTION:
XS GIS Cut Line= 3
      3654797.35     10229698.94      3653826.75     10230048.57
      3653524.07     10230580.88
#Sta/Elev= 30
  4332.2  271.11  4544.5  265.93  4589.3  264.90  4640.0  265.30  4650.9  265.01
  4688.5  264.59  4731.1  262.48  4807.2  261.98  4901.1  260.92  4977.7  261.83
  4993.8  258.75  4996.5  258.25  4999.8  258.75  5003.1  261.48  5049.9  261.62
  5081.8  263.06  5095.2  261.39  5120.6  261.21  5127.4  261.98  5176.6  261.75
  5315.6  265.61  5378.3  268.23  5418.7  268.79  5523.8  267.68  5545.5  268.59
  5626.2  269.41  5685.3  269.03  5787.6  270.05  5911.6  272.90  5976.2  272.65
#Mann=9,-1,0
  4332.2     0.1       0  4544.5    0.16       0  4640.0     0.1       0
  4650.9    0.05       0  4807.2     0.1       0  4993.8    0.07       0
  4999.8     0.1       0  5127.4    0.05       0  5418.7    0.16       0
Bank Sta=4993.8,4999.8
Exp/Cntr=0.3,0.1

Type RM Length L Ch R = 1,1204,0,0,0
BEGIN DESCRIPTION:
UNT026 IN GIBB 1.0
END DESCRIPTION:
XS GIS Cut Line= 3
      3654742.13     10229541.65      3653576.27     10229323.21
      3652929.20     10229782.42
#Sta/Elev= 30
  3495.5  272.79  3536.2  274.22  3579.5  272.97  3684.7  267.91  3770.2  265.43
  3847.5  263.75  3892.3  263.85  3922.8  265.04  3973.9  263.43  4230.9  261.46
  4278.4  262.62  4319.6  260.99  4411.2  261.44  4533.3  259.92  4609.1  259.78
  4661.7  261.15  4770.2  258.69  4870.7  258.72  4956.5  257.09  4984.2  257.51
  4996.0  256.57  4998.8  256.07  5002.0  256.57  5019.9  259.38  5070.4  263.81
  5183.6  270.77  5227.8  273.38  5263.5  274.32  5408.7  274.35  5475.1  275.97
#Mann=5,-1,0
  3495.5    0.16       0  3973.9    0.05       0  4996.0    0.03       0
  5002.0    0.05       0  5183.6    0.16       0
Bank Sta=4996,5002
Exp/Cntr=0.3,0.1

Chan Stop Cuts=-1