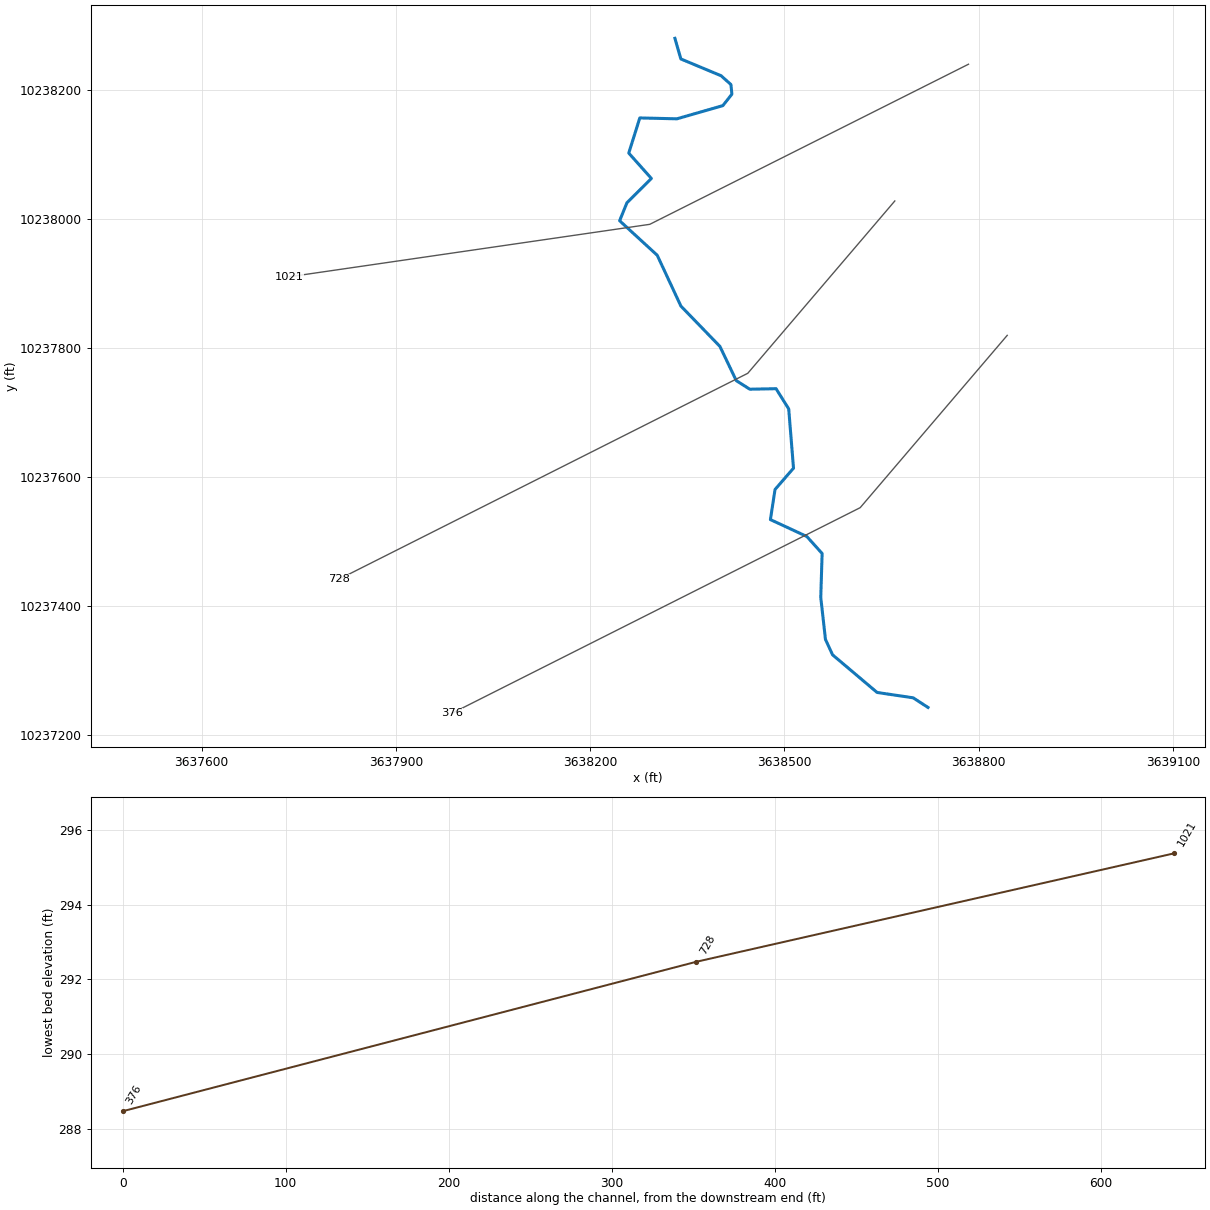
--- UNT028 IN GIBB.prj (project) ---

Proj Title=UNT028 IN GIBB Base Level Engineering
Current Plan=p01
Default Exp/Contr=0.3,0.1
English Units
Geom File=g01
Flow File=f01
Plan File=p01
BEGIN DESCRIPTION:
UNT028 IN GIBB
END DESCRIPTION:

--- UNT028 IN GIBB.p01 (plan) ---

Plan Title=Multiple Run
Short Identifier=Multiple
Geom File=g01
Flow File=f01
Subcritical Flow
K Sum by GR= 0
Std Step Tol= 0.01
Critical Tol= 0.01
Num of Std Step Trials= 20
Max Error Tol= 0.3
Flow Tol Ratio= 0.001
Split Flow NTrial= 30
Split Flow Tol= 0.02
Split Flow Ratio= 0.02
Log Output Level= 0
Friction Slope Method= 1
Unsteady Friction Slope Method= 2
Unsteady Bridges Friction Slope Method= 1
Parabolic Critical Depth
Global Vel Dist=  1 , 1 , 1
Global Log Level= 0
CheckData=True
Encroach Param= -1, 0, 0, 0
BEGIN DESCRIPTION:
Multiple Run
END DESCRIPTION:

--- UNT028 IN GIBB.f01 (steady flow) ---

Flow Title=Multiple
Number of Profiles=7
Profile Names=10-year,25-year,50-year,1pct_min,100-year,1pct_plu,500-year
River Rch & RM= UNT028 IN GIBB,Reach-1,1021
     179     221     254     214     290     392     377
Boundary for River Rch & Prof#=UNT028 IN GIBB,Reach-1,1
Up Type=0
Dn Type=3
Dn Slope=0.005
Boundary for River Rch & Prof#=UNT028 IN GIBB,Reach-1,2
Up Type=0
Dn Type=3
Dn Slope=0.005
Boundary for River Rch & Prof#=UNT028 IN GIBB,Reach-1,3
Up Type=0
Dn Type=3
Dn Slope=0.005
Boundary for River Rch & Prof#=UNT028 IN GIBB,Reach-1,4
Up Type=0
Dn Type=3
Dn Slope=0.005
Boundary for River Rch & Prof#=UNT028 IN GIBB,Reach-1,5
Up Type=0
Dn Type=3
Dn Slope=0.005
Boundary for River Rch & Prof#=UNT028 IN GIBB,Reach-1,6
Up Type=0
Dn Type=3
Dn Slope=0.005
Boundary for River Rch & Prof#=UNT028 IN GIBB,Reach-1,7
Up Type=0
Dn Type=3
Dn Slope=0.005

--- UNT028 IN GIBB.g01 (geometry) ---

Geom Title=Existing Conditions

River Reach=UNT028 IN GIBB,Reach-1
Reach XY= 30
      3638330.90     10238280.03      3638340.11     10238248.06
      3638402.23     10238222.03      3638417.40     10238208.38
      3638418.90     10238193.41      3638404.94     10238175.70
      3638334.04     10238155.24      3638276.70     10238156.60
      3638259.64     10238102.08      3638294.59     10238062.78
      3638256.81     10238025.01      3638245.54     10237997.20
      3638303.60     10237943.69      3638340.20     10237864.83
      3638400.38     10237802.39      3638425.69     10237749.26
      3638446.56     10237735.97      3638487.10     10237736.77
      3638506.64     10237705.43      3638514.05     10237613.54
      3638485.51     10237580.47      3638478.38     10237533.80
      3638534.55     10237507.65      3638558.24     10237481.21
      3638556.12     10237413.25      3638563.37     10237348.11
      3638574.32     10237324.13      3638643.13     10237265.75
      3638698.84     10237257.45      3638721.71     10237242.51

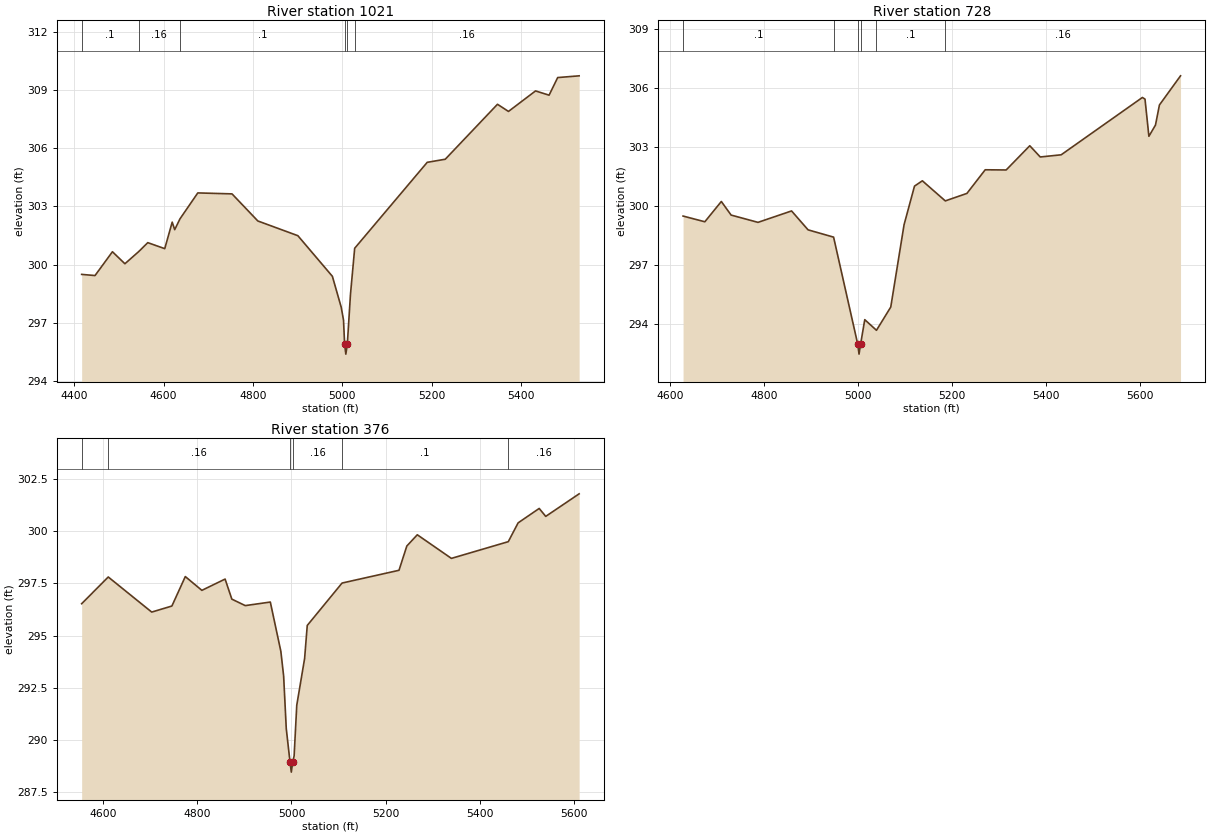
Type RM Length L Ch R = 1,1021,293,293,293
BEGIN DESCRIPTION:
UNT028 IN GIBB 2.0
END DESCRIPTION:
XS GIS Cut Line= 3
      3638784.26     10238239.90      3638292.11     10237991.64
      3637735.54     10237910.30
#Sta/Elev= 30
  4416.7  299.49  4446.6  299.43  4485.6  300.66  4513.5  300.04  4544.5  300.67
  4564.7  301.13  4602.7  300.82  4619.4  302.19  4625.0  301.80  4636.8  302.36
  4676.7  303.70  4753.3  303.65  4811.1  302.25  4900.7  301.49  4978.0  299.39
  4997.8  297.79  5002.9  297.13  5005.4  295.87  5008.1  295.37  5011.4  295.87
  5018.5  298.46  5027.9  300.84  5190.3  305.28  5230.7  305.44  5347.6  308.28
  5372.2  307.91  5432.8  308.97  5463.1  308.75  5482.4  309.66  5530.4  309.75
#Mann=6,-1,0
  4416.7     0.1       0  4544.5    0.16       0  4636.8     0.1       0
  5005.4    0.07       0  5011.4     0.1       0  5027.9    0.16       0
Bank Sta=5005.4,5011.4
Exp/Cntr=0.3,0.1

Type RM Length L Ch R = 1,728,352,352,352
BEGIN DESCRIPTION:
UNT028 IN GIBB 1.1
END DESCRIPTION:
XS GIS Cut Line= 3
      3638670.49     10238027.87      3638443.42     10237760.64
      3637812.06     10237441.30
#Sta/Elev= 30
  4627.8  299.48  4674.1  299.19  4709.2  300.22  4730.0  299.53  4787.2  299.16
  4858.6  299.74  4893.7  298.78  4948.0  298.41  4999.4  292.97  5002.1  292.47
  5005.4  292.97  5014.3  294.22  5039.2  293.68  5069.6  294.86  5097.9  299.04
  5120.1  301.00  5136.8  301.27  5185.6  300.25  5231.6  300.63  5270.5  301.83
  5315.1  301.82  5365.3  303.05  5387.6  302.48  5432.1  302.59  5604.8  305.50
  5610.4  305.42  5618.7  303.53  5632.7  304.10  5641.1  305.12  5686.0  306.60
#Mann=6,-1,0
  4627.8     0.1       0  4948.0    0.16       0  4999.4    0.07       0
  5005.4    0.16       0  5039.2     0.1       0  5185.6    0.16       0
Bank Sta=4999.4,5005.4
Exp/Cntr=0.3,0.1

Type RM Length L Ch R = 1,376,0,0,0
BEGIN DESCRIPTION:
UNT028 IN GIBB 1.0
END DESCRIPTION:
XS GIS Cut Line= 3
      3638844.08     10237819.51      3638617.03     10237552.31
      3637986.35     10237233.32
#Sta/Elev= 30
  4554.0  296.53  4610.5  297.81  4702.9  296.13  4745.8  296.42  4774.3  297.83
  4809.5  297.17  4858.9  297.71  4873.2  296.75  4901.7  296.44  4955.0  296.61
  4977.4  294.25  4983.3  293.07  4988.9  290.55  4996.8  288.97  4999.6  288.47
  5002.8  288.97  5005.6  289.25  5011.2  291.67  5027.9  293.91  5033.5  295.49
  5107.5  297.52  5228.5  298.13  5245.1  299.29  5267.4  299.83  5339.9  298.70
  5460.8  299.50  5481.7  300.40  5526.5  301.09  5540.4  300.71  5611.4  301.79
#Mann=6,-1,0
  4554.0     0.1       0  4610.5    0.16       0  4996.8    0.07       0
  5002.8    0.16       0  5107.5     0.1       0  5460.8    0.16       0
Bank Sta=4996.8,5002.8
Exp/Cntr=0.3,0.1

Chan Stop Cuts=-1