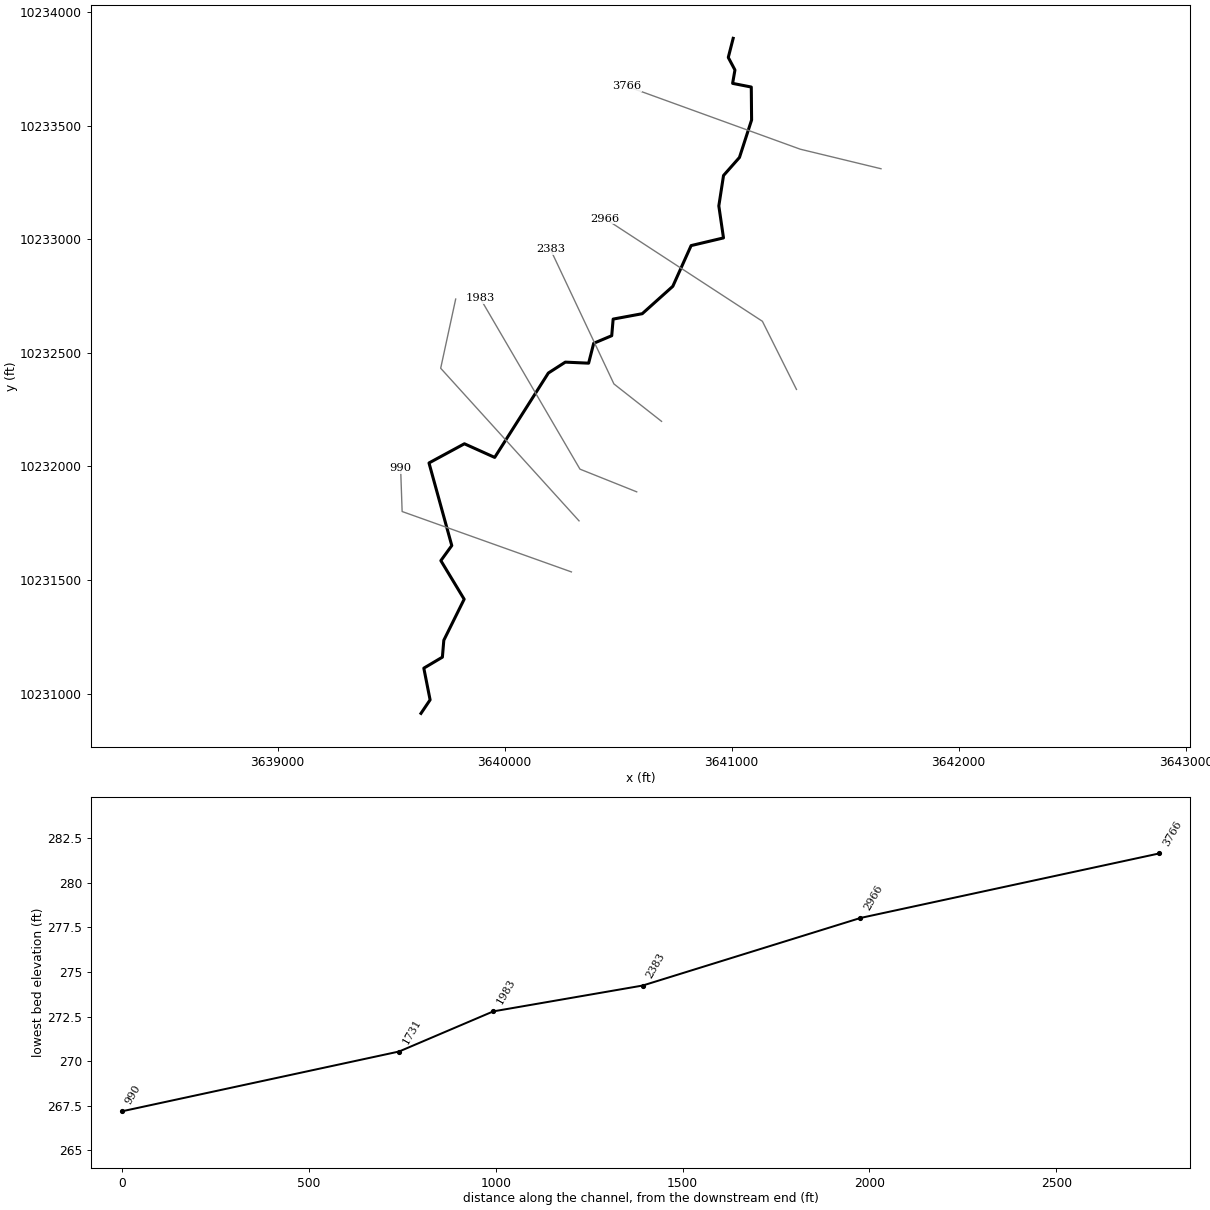
--- UNT029 IN GIBB.prj (project) ---

Proj Title=UNT029 IN GIBB Base Level Engineering
Current Plan=p01
Default Exp/Contr=0.3,0.1
English Units
Geom File=g01
Flow File=f01
Plan File=p01
Y Axis Title=Elevation
X Axis Title(PF)=Main Channel Distance
X Axis Title(XS)=Station
BEGIN DESCRIPTION:
UNT029 IN GIBB
END DESCRIPTION:
DSS Export Rating Curves= 0
DSS Export Rating Curve Sorted= 0
DSS Export Volume Flow Curves= 0
DXF OffsetX= 0
DXF OffsetY= 0
DXF ScaleX= 1
DXF ScaleY= 10

--- UNT029 IN GIBB.p01 (plan) ---

Plan Title=Multiple Run
Short Identifier=Multiple
Geom File=g01
Flow File=f01
Subcritical Flow
K Sum by GR= 0
Std Step Tol= 0.01
Critical Tol= 0.01
Num of Std Step Trials= 20
Max Error Tol= 0.3
Flow Tol Ratio= 0.001
Split Flow NTrial= 30
Split Flow Tol= 0.02
Split Flow Ratio= 0.02
Log Output Level= 0
Friction Slope Method= 1
Unsteady Friction Slope Method= 2
Unsteady Bridges Friction Slope Method= 1
Parabolic Critical Depth
Global Vel Dist=  1 , 1 , 1
Global Log Level= 0
CheckData=True
Encroach Param= -1, 0, 0, 0
BEGIN DESCRIPTION:
Multiple Run
END DESCRIPTION:

--- UNT029 IN GIBB.f01 (steady flow) ---

Flow Title=Multiple
Program Version=4.10
Number of Profiles= 7
Profile Names=10-year,25-year,50-year,1pct_min,100-year,1pct_plu,500-year
River Rch & RM=UNT029 IN GIBB,Reach-1         ,3766
     274     347     403     344     465     629     619
Boundary for River Rch & Prof#=UNT029 IN GIBB,Reach-1         , 1
Up Type= 0
Dn Type= 3
Dn Slope=0.006
Boundary for River Rch & Prof#=UNT029 IN GIBB,Reach-1         , 2
Up Type= 0
Dn Type= 3
Dn Slope=0.006
Boundary for River Rch & Prof#=UNT029 IN GIBB,Reach-1         , 3
Up Type= 0
Dn Type= 3
Dn Slope=0.006
Boundary for River Rch & Prof#=UNT029 IN GIBB,Reach-1         , 4
Up Type= 0
Dn Type= 3
Dn Slope=0.006
Boundary for River Rch & Prof#=UNT029 IN GIBB,Reach-1         , 5
Up Type= 0
Dn Type= 3
Dn Slope=0.006
Boundary for River Rch & Prof#=UNT029 IN GIBB,Reach-1         , 6
Up Type= 0
Dn Type= 3
Dn Slope=0.006
Boundary for River Rch & Prof#=UNT029 IN GIBB,Reach-1         , 7
Up Type= 0
Dn Type= 3
Dn Slope=0.006
DSS Import GetInterval= 0
DSS Import GetPeak= 0
DSS Import FillOption= 0

--- UNT029 IN GIBB.g01 (geometry) ---

Geom Title=Existing Conditions
Program Version=4.10

River Reach=UNT029 IN GIBB  ,Reach-1
Reach XY= 30
      3641006.69     10233885.56       3640985.1     10233801.43
      3641014.52     10233746.12      3641004.19     10233687.19
      3641086.45     10233671.06      3641087.85     10233526.08
      3641034.36     10233360.86      3640964.23     10233281.51
      3640943.49     10233147.53      3640964.04     10233006.56
      3640821.48     10232972.76      3640740.81     10232793.43
      3640606.26     10232672.78      3640478.05     10232649.06
      3640471.83     10232575.89      3640392.43     10232542.46
      3640370.07     10232454.88      3640267.37      10232459.5
      3640192.65     10232411.46      3639956.38     10232039.82
      3639822.98     10232099.89      3639667.02     10232015.41
      3639767.35     10231651.58      3639719.25     10231585.21
       3639821.9     10231415.31      3639732.28     10231234.56
      3639726.03     10231160.13      3639644.22     10231111.64
      3639671.86     10230972.06      3639631.71     10230912.51

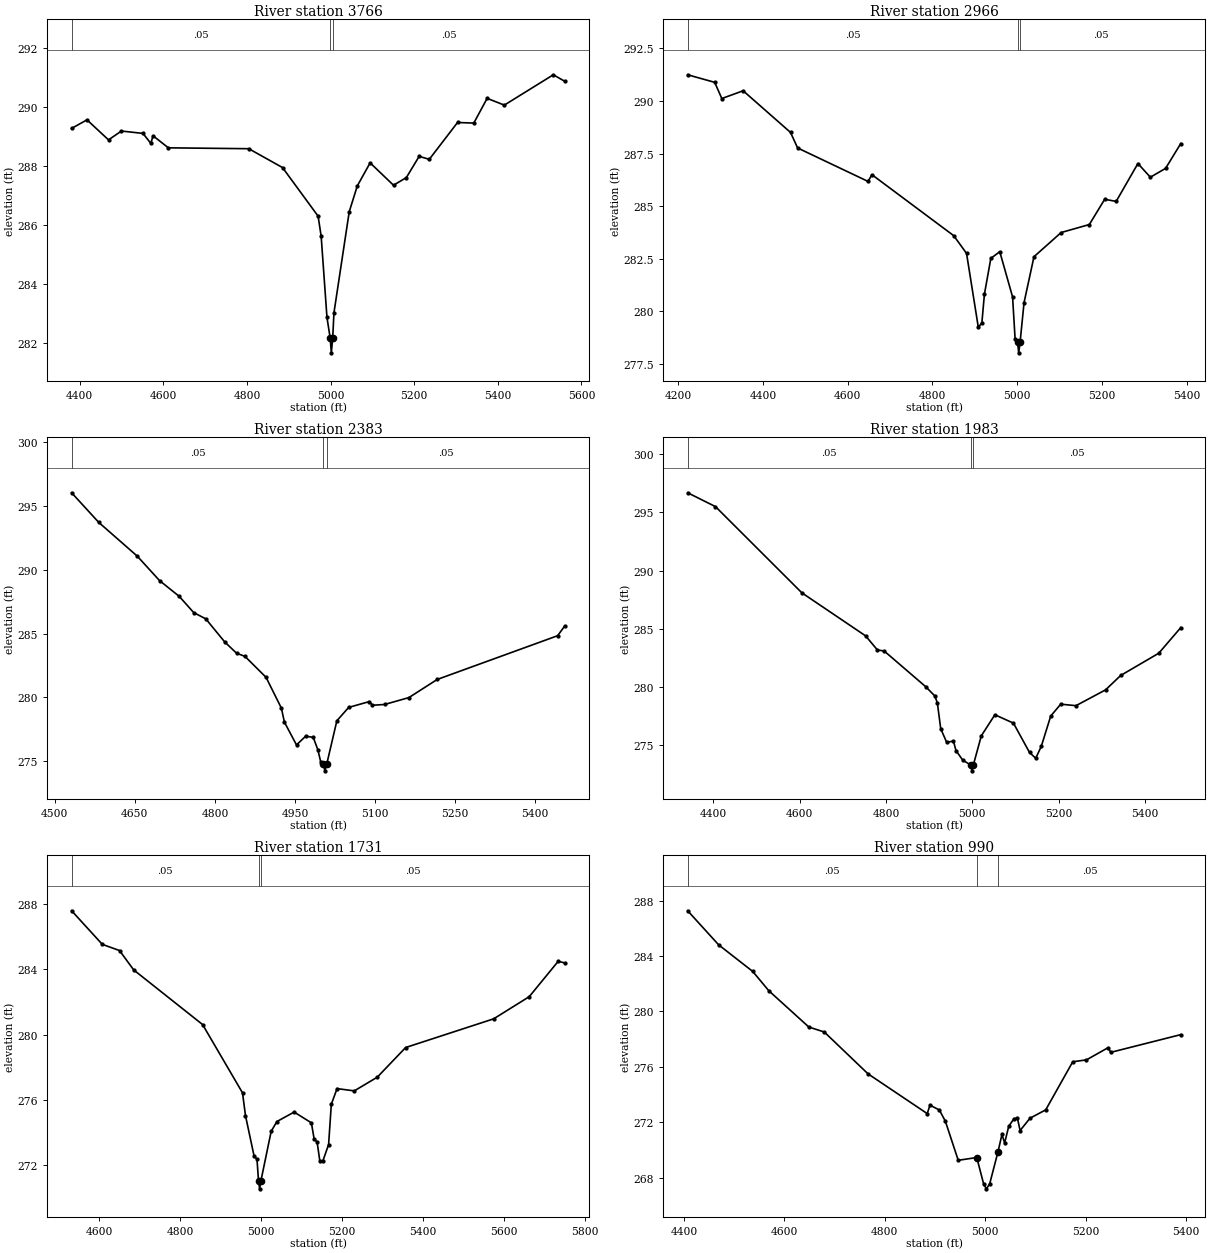
Type RM Length L Ch R = 1 ,3766    ,800,800,800
BEGIN DESCRIPTION:
UNT029 IN GIBB 6.0
END DESCRIPTION:
XS GIS Cut Line= 3
      3641657.81     10233311.21      3641301.89     10233397.38
      3640537.71     10233674.58
#Sta/Elev= 30
  4380.8  289.27  4417.5  289.56    4469  288.88  4499.8  289.18  4551.3   289.1
  4570.3  288.76  4575.4  289.02  4612.1  288.61  4804.4  288.58  4885.1  287.94
  4970.2  286.29  4977.5  285.61  4991.4  282.85  4999.1  282.15  5001.8  281.65
  5005.1  282.15  5008.1  283.01  5044.6  286.44    5064  287.32  5094.6   288.1
  5150.5  287.34  5181.2   287.6  5211.8  288.32  5236.1  288.22  5303.6  289.47
  5342.5  289.45  5374.4  290.29  5415.5  290.06  5532.6  291.09  5559.9  290.87
#Mann= 3 ,-1 , 0
  4380.8     .05       0  4999.1     .03       0  5005.1     .05       0
Bank Sta=4999.1,5005.1
XS Rating Curve= 0 ,0
Exp/Cntr=0.3,0.1

Type RM Length L Ch R = 1 ,2966    ,583,583,583
BEGIN DESCRIPTION:
UNT029 IN GIBB 5.0
END DESCRIPTION:
XS GIS Cut Line= 3
      3641285.47     10232339.31      3641135.45     10232639.35
      3640442.09     10233091.66
#Sta/Elev= 30
  4222.5  291.25  4286.3  290.89    4303  290.12  4353.3  290.49  4465.1  288.51
  4481.9  287.77    4648  286.18  4657.2   286.5  4850.2   283.6  4880.4  282.76
  4908.2  279.24  4916.6  279.46  4922.6  280.82  4937.7  282.52  4958.8  282.84
    4989  280.69    4995  278.68  5000.7  278.53  5003.5  278.03  5006.7  278.53
  5016.1  280.42  5039.5   282.6  5103.6  283.75  5170.1  284.13  5206.3  285.33
  5233.4  285.23  5284.7  287.03  5314.1  286.38    5350   286.8  5385.8  287.98
#Mann= 3 ,-1 , 0
  4222.5     .05       0  5000.7     .03       0  5006.7     .05       0
Bank Sta=5000.7,5006.7
XS Rating Curve= 0 ,0
Exp/Cntr=0.3,0.1

Type RM Length L Ch R = 1 ,2383    ,400,400,400
BEGIN DESCRIPTION:
UNT029 IN GIBB 4.0
END DESCRIPTION:
XS GIS Cut Line= 3
       3640691.3      10232198.6      3640481.49     10232363.45
      3640201.12     10232957.82
#Sta/Elev= 30
  4531.5  296.03  4582.3  293.71  4654.6  291.06  4696.2  289.15  4733.2  287.91
  4760.3  286.64  4782.9  286.15  4818.4  284.34  4840.5  283.46  4856.3  283.21
  4895.8  281.57  4924.6  279.15  4930.2  278.06  4952.9  276.27  4970.2  276.96
  4984.3  276.86    4993  275.88  4998.5   274.9  5003.4  274.74  5006.1  274.24
  5009.4  274.74  5028.5  278.16  5050.6  279.21  5089.6  279.67  5095.1  279.38
  5117.9  279.44  5163.5  279.98  5216.5   281.4  5442.3  284.83  5455.5  285.59
#Mann= 3 ,-1 , 0
  4531.5     .05       0  5003.4     .03       0  5009.4     .05       0
Bank Sta=5003.4,5009.4
XS Rating Curve= 0 ,0
Exp/Cntr=0.3,0.1

Type RM Length L Ch R = 1 ,1983    ,252,252,252
BEGIN DESCRIPTION:
UNT029 IN GIBB 3.0
END DESCRIPTION:
XS GIS Cut Line= 3
      3640581.89      10231888.2      3640331.86     10231988.21
      3639892.09     10232741.67
#Sta/Elev= 30
  4340.9  296.69  4405.3   295.5  4605.3  288.09  4752.9  284.39  4780.2  283.18
  4795.9  283.09  4891.8  280.03  4913.3  279.22  4919.1  278.61  4926.8  276.41
  4940.6  275.24  4956.3  275.35  4962.1  274.53  4977.8  273.71  4996.3  273.29
    4999  272.79  5002.3  273.29  5020.8   275.8  5052.2  277.61  5095.2  276.89
  5132.4  274.37  5146.8  273.87  5159.7   274.9  5181.5   277.5  5204.7  278.52
  5239.9  278.39  5308.5  279.75  5343.6  280.99  5431.7   282.9  5482.6   285.1
#Mann= 3 ,-1 , 0
  4340.9     .05       0  4996.3     .03       0  5002.3     .05       0
Bank Sta=4996.3,5002.3
XS Rating Curve= 0 ,0
Exp/Cntr=0.3,0.1

Type RM Length L Ch R = 1 ,1731    ,741,741,741
BEGIN DESCRIPTION:
UNT029 IN GIBB 2.0
END DESCRIPTION:
XS GIS Cut Line= 3
      3640327.88     10231760.34      3639718.48     10232432.54
      3639784.56     10232737.35
#Sta/Elev= 30
  4531.5   287.6  4607.3  285.54  4649.9  285.16    4685  283.97  4855.3  280.62
    4954  276.43  4961.4  275.03  4982.4  272.58  4989.8  272.35  4993.6  271.04
  4996.3  270.54  4999.6  271.04  5024.9  274.07  5039.1  274.67  5081.7  275.25
  5124.3  274.59    5131  273.62  5138.5  273.41  5145.2  272.25  5152.7  272.25
  5166.9  273.26  5173.6  275.73  5187.8  276.69  5230.4  276.55  5287.2  277.39
  5357.4  279.21    5575  280.97    5663  282.33  5734.6   284.5  5750.7   284.4
#Mann= 3 ,-1 , 0
  4531.5     .05       0  4993.6     .03       0  4999.6     .05       0
Bank Sta=4993.6,4999.6
XS Rating Curve= 0 ,0
Exp/Cntr=0.3,0.1

Type RM Length L Ch R = 1 ,990     ,0,0,0
BEGIN DESCRIPTION:
UNT029 IN GIBB 1.0
END DESCRIPTION:
XS GIS Cut Line= 3
      3640294.21     10231535.55      3639548.71     10231801.53
       3639542.1     10231991.69
#Sta/Elev= 30
  4407.7  287.26  4469.4   284.8  4537.3  282.88  4569.2  281.49  4648.9  278.87
  4679.7  278.51  4766.8  275.49  4884.7  272.62  4890.1  273.23  4908.9  272.88
  4920.9  272.06  4946.4  269.25  4983.3  269.45 4996.94  267.55  5002.4  267.19
 5008.97  267.54  5025.7  269.88  5033.5  271.12  5038.8   270.5    5047  271.71
  5057.6  272.26  5064.3  272.28  5069.6   271.4  5089.4  272.29  5120.6  272.89
  5174.4  276.36  5201.8   276.5  5244.9  277.38  5249.9  277.04  5389.5  278.32
#Mann= 3 , 0 , 0
  4407.7     .05       0  4983.3     .03       0  5025.7     .05       0
Bank Sta=4983.3,5025.7
XS Rating Curve= 0 ,0
Exp/Cntr=0.3,0.1

Chan Stop Cuts=-1
Use User Specified Reach Order=0
Composite Channel Slope=5