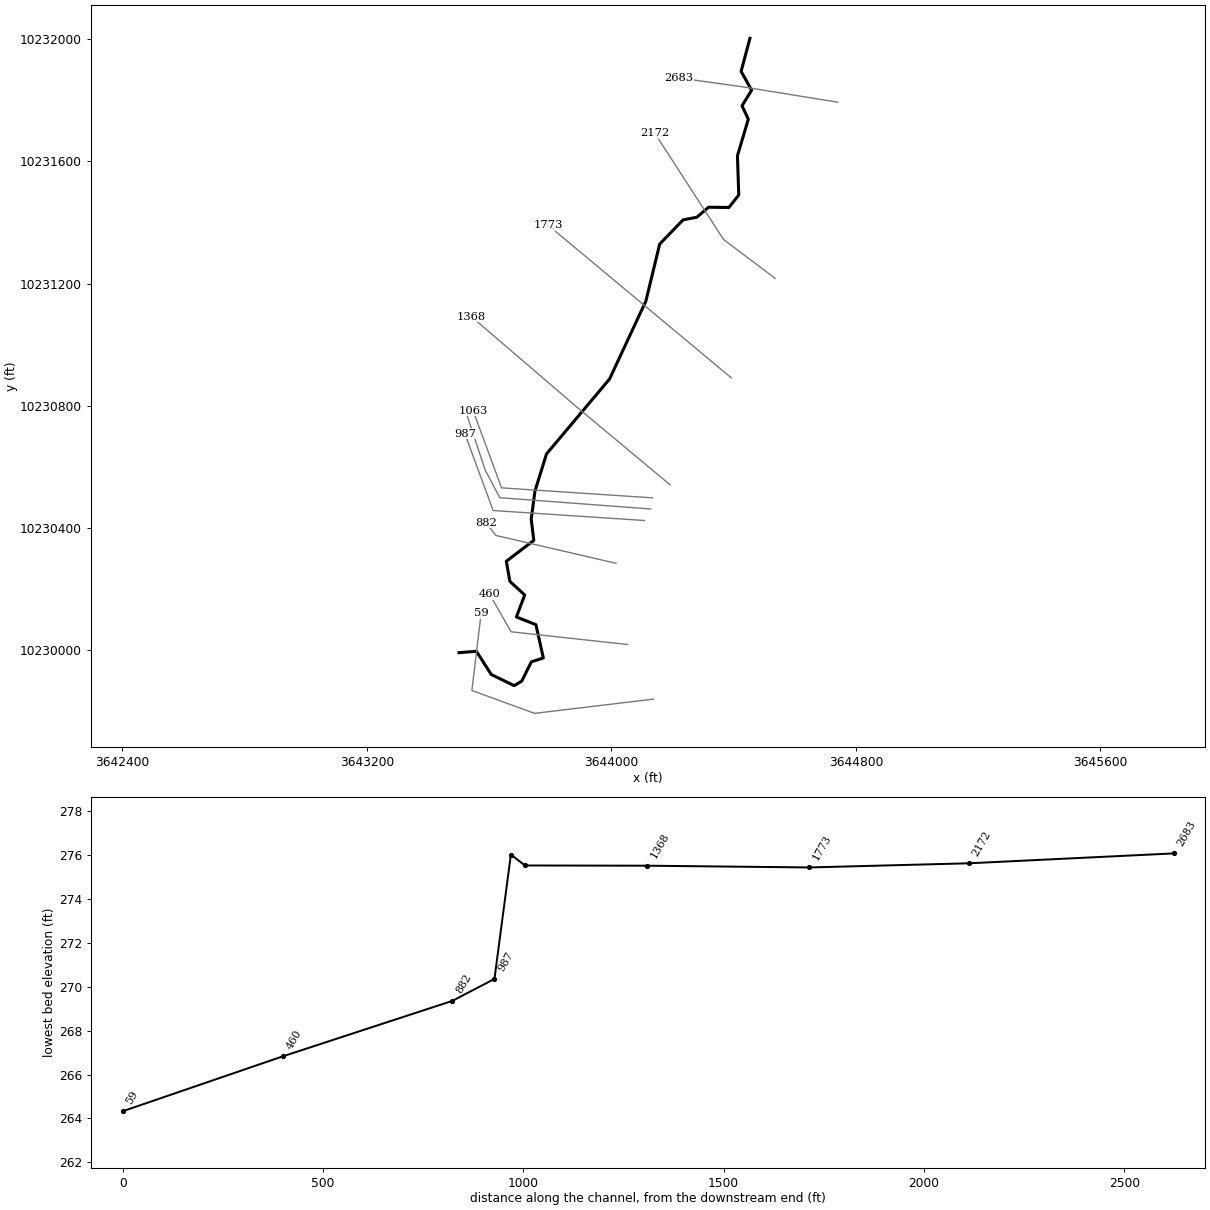
--- UNT031 IN GIBB.prj (project) ---

Proj Title=UNT031 IN GIBB Base Level Engineering
Current Plan=p01
Default Exp/Contr=0.3,0.1
English Units
Geom File=g01
Flow File=f01
Plan File=p01
Y Axis Title=Elevation
X Axis Title(PF)=Main Channel Distance
X Axis Title(XS)=Station
BEGIN DESCRIPTION:
UNT031 IN GIBB
END DESCRIPTION:
DSS Export Rating Curves= 0
DSS Export Rating Curve Sorted= 0
DSS Export Volume Flow Curves= 0
DXF OffsetX= 0
DXF OffsetY= 0
DXF ScaleX= 1
DXF ScaleY= 10

--- UNT031 IN GIBB.p01 (plan) ---

Plan Title=Multiple Run
Short Identifier=Multiple
Geom File=g01
Flow File=f01
Subcritical Flow
K Sum by GR= 0
Std Step Tol= 0.01
Critical Tol= 0.01
Num of Std Step Trials= 20
Max Error Tol= 0.3
Flow Tol Ratio= 0.001
Split Flow NTrial= 30
Split Flow Tol= 0.02
Split Flow Ratio= 0.02
Log Output Level= 0
Friction Slope Method= 1
Unsteady Friction Slope Method= 2
Unsteady Bridges Friction Slope Method= 1
Parabolic Critical Depth
Global Vel Dist=  1 , 1 , 1
Global Log Level= 0
CheckData=True
Encroach Param= -1, 0, 0, 0
BEGIN DESCRIPTION:
Multiple Run
END DESCRIPTION:

--- UNT031 IN GIBB.f01 (steady flow) ---

Flow Title=Multiple
Number of Profiles=7
Profile Names=10-year,25-year,50-year,1pct_min,100-year,1pct_plu,500-year
River Rch & RM= UNT031 IN GIBB,Reach-1,2683
     224     281     324     276     373     504     492
Boundary for River Rch & Prof#=UNT031 IN GIBB,Reach-1,1
Up Type=0
Dn Type=3
Dn Slope=0.005
Boundary for River Rch & Prof#=UNT031 IN GIBB,Reach-1,2
Up Type=0
Dn Type=3
Dn Slope=0.005
Boundary for River Rch & Prof#=UNT031 IN GIBB,Reach-1,3
Up Type=0
Dn Type=3
Dn Slope=0.005
Boundary for River Rch & Prof#=UNT031 IN GIBB,Reach-1,4
Up Type=0
Dn Type=3
Dn Slope=0.005
Boundary for River Rch & Prof#=UNT031 IN GIBB,Reach-1,5
Up Type=0
Dn Type=3
Dn Slope=0.005
Boundary for River Rch & Prof#=UNT031 IN GIBB,Reach-1,6
Up Type=0
Dn Type=3
Dn Slope=0.005
Boundary for River Rch & Prof#=UNT031 IN GIBB,Reach-1,7
Up Type=0
Dn Type=3
Dn Slope=0.005

--- UNT031 IN GIBB.g01 (geometry) ---

Geom Title=Existing Conditions
Program Version=4.10

River Reach=UNT031 IN GIBB  ,Reach-1
Reach XY= 30
      3644453.26     10232002.17      3644424.41     10231894.11
      3644458.79     10231832.48      3644427.46     10231781.49
      3644447.93     10231737.64      3644412.38     10231617.96
       3644416.7     10231489.61      3644384.51     10231448.95
      3644317.92      10231449.7      3644279.61     10231417.04
      3644234.34     10231408.16      3644158.02     10231329.15
      3644112.88     10231142.69      3643994.13     10230887.83
      3643787.88     10230642.69      3643750.03     10230521.16
      3643737.83     10230429.16      3643746.25     10230359.91
      3643656.31     10230291.48      3643668.01     10230225.88
      3643716.46     10230181.36      3643689.38     10230109.33
      3643753.07     10230084.19      3643777.48     10229975.16
       3643738.3      10229962.6      3643706.69     10229899.38
      3643681.96     10229884.74      3643607.13     10229921.11
      3643558.44      10229997.1      3643501.71     10229992.51

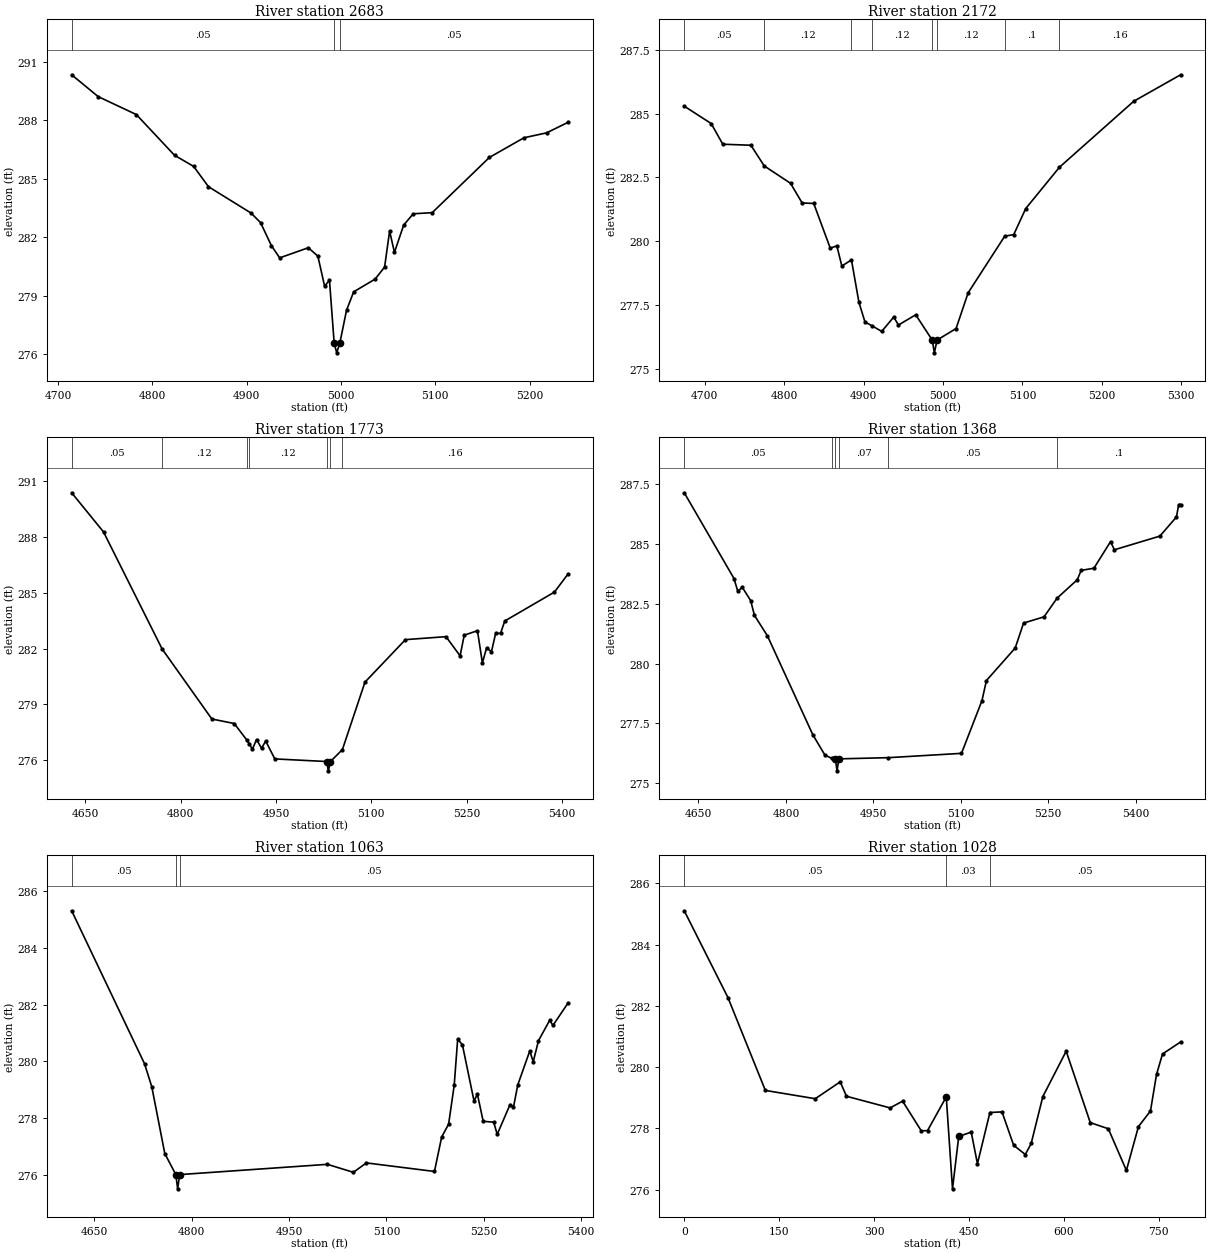
Type RM Length L Ch R = 1 ,2683    ,511,511,511
BEGIN DESCRIPTION:
UNT031 IN GIBB 5.0
END DESCRIPTION:
XS GIS Cut Line= 3
      3644739.84     10231793.32      3644442.11     10231841.64
      3644219.53     10231872.96
#Sta/Elev= 30
  4714.3  290.34  4742.4  289.22  4782.9   288.3  4823.4  286.21  4843.7  285.64
  4859.4   284.6  4904.5  283.25  4914.6  282.76  4926.1  281.58  4934.9  280.95
  4965.3  281.47  4975.4  281.04  4982.6  279.49  4987.7  279.81  4992.7  276.58
  4995.4  276.08  4998.7  276.58  5005.8  278.26  5013.4  279.21  5036.1  279.86
  5046.2  280.48  5051.5  282.33  5056.6  281.23  5066.4  282.63  5076.5  283.21
  5096.7  283.27  5157.3   286.1    5194  287.11  5217.9  287.36  5240.7   287.9
#Mann= 3 ,-1 , 0
  4714.3     .05       0  4992.7     .03       0  4998.7     .05       0
Bank Sta=4992.7,4998.7
XS Rating Curve= 0 ,0
Exp/Cntr=0.3,0.1

Type RM Length L Ch R = 1 ,2172    ,399,399,399
BEGIN DESCRIPTION:
UNT031 IN GIBB 4.0
END DESCRIPTION:
XS GIS Cut Line= 3
      3644535.48     10231217.21       3644366.7     10231344.51
      3644142.08     10231691.68
#Sta/Elev= 30
  4674.2  285.29  4708.1  284.61  4722.7   283.8  4758.1  283.76  4774.9  282.95
    4808  282.27  4822.6   281.5  4837.2  281.48    4858  279.73  4866.3  279.82
  4872.6  279.03  4884.7  279.27  4894.1  277.61  4901.7  276.84  4910.5  276.69
  4922.8  276.47  4937.9  277.03  4943.9  276.72  4965.6  277.12  4986.4  276.13
  4989.1  275.63  4992.4  276.13  5016.4  276.58  5031.6  277.98  5077.7   280.2
    5089  280.26  5104.1  281.28  5146.6   282.9    5240  285.48  5299.1  286.52
#Mann= 8 ,-1 , 0
  4674.2     .05       0  4774.9     .12       0  4884.7     .05       0
  4910.5     .12       0  4986.4     .07       0  4992.4     .12       0
  5077.7      .1       0  5146.6     .16       0
Bank Sta=4986.4,4992.4
XS Rating Curve= 0 ,0
Exp/Cntr=0.3,0.1

Type RM Length L Ch R = 1 ,1773    ,405,405,405
BEGIN DESCRIPTION:
UNT031 IN GIBB 3.0
END DESCRIPTION:
XS GIS Cut Line= 3
      3644392.11     10230891.64      3644092.11     10231141.64
      3643792.13     10231391.62
#Sta/Elev= 30
  4628.5  290.36  4678.6  288.26  4770.8  281.98  4849.1  278.22  4884.3  277.98
  4903.7  277.11  4907.9  276.89  4912.9   276.6  4919.4  277.12  4927.3  276.65
  4933.8  277.04  4948.1  276.08  5029.7  275.94  5032.4  275.44  5035.7  275.94
  5054.5  276.58    5090   280.2  5153.7  282.48  5217.5  282.64  5239.7  281.61
  5246.2  282.72    5267  282.96  5274.8  281.23  5281.3  282.03  5289.1  281.84
  5295.6  282.81  5303.4  282.82    5310  283.48  5388.1  285.03  5409.5     286
#Mann= 7 ,-1 , 0
  4628.5     .05       0  4770.8     .12       0  4903.7     .05       0
  4907.9     .12       0  5029.7     .07       0  5035.7     .12       0
  5054.5     .16       0
Bank Sta=5029.7,5035.7
XS Rating Curve= 0 ,0
Exp/Cntr=0.3,0.1

Type RM Length L Ch R = 1 ,1368    ,305,305,305
BEGIN DESCRIPTION:
UNT031 IN GIBB 2.0
END DESCRIPTION:
XS GIS Cut Line= 3
      3644192.13     10230541.62      3643892.11     10230791.64
      3643542.12     10231091.63
#Sta/Elev= 30
  4625.6  287.13  4710.9  283.55  4717.4  283.02  4725.2  283.18  4739.5  282.63
    4746  282.01  4768.2  281.16  4846.3  277.02  4867.1  276.17    4879  276.04
  4884.9  276.02  4887.7  275.52  4890.9  276.02  4975.8  276.07  5101.2  276.25
  5136.3  278.45    5144  279.29  5193.4  280.65  5207.7  281.69  5242.8  281.95
  5265.2  282.73  5299.9   283.5  5306.5  283.89  5328.4  283.98  5356.9  285.09
  5363.5  284.75  5441.5  285.32    5470  286.12  5473.8  286.64  5477.1  286.64
#Mann= 6 ,-1 , 0
  4625.6     .05       0    4879     .07       0  4884.9    .033       0
  4890.9     .07       0  4975.8     .05       0  5265.2      .1       0
Bank Sta=4884.9,4890.9
XS Rating Curve= 0 ,0
Exp/Cntr=0.3,0.1

Type RM Length L Ch R = 1 ,1063    ,35,35,35
BEGIN DESCRIPTION:
UNT031 IN GIBB 1.1
END DESCRIPTION:
XS GIS Cut Line= 3
       3644135.3     10230498.97       3643640.7     10230531.68
      3643547.63     10230784.31
#Sta/Elev= 30
  4614.9  285.29  4727.2  279.92  4738.4  279.11  4758.4  276.77  4775.4  276.03
  4778.2  275.53  4781.4  276.03    5009  276.39    5049  276.11  5069.1  276.44
    5174  276.14  5185.1  277.35  5195.8   277.8  5204.4  279.16  5209.8  280.79
  5217.1  280.58  5234.9  278.62  5240.2  278.85  5249.1   277.9  5265.3  277.87
  5270.7  277.44  5290.5  278.49  5295.8   278.4  5302.4  279.18  5320.9  280.37
  5326.2  279.99  5334.3  280.73  5351.4  281.44  5356.7  281.27  5379.8  282.05
#Mann= 3 ,-1 , 0
  4614.9     .05       0  4775.4    .033       0  4781.4     .05       0
Bank Sta=4775.4,4781.4
XS Rating Curve= 0 ,0
Exp/Cntr=0.3,0.1

Type RM Length L Ch R = 1 ,1028    ,41,41,41
XS GIS Cut Line= 4
     3644128.783    10230462.594     3643635.076    10230499.487
     3643587.333    10230589.547     3643525.484    10230776.179
#Sta/Elev= 30
       0   285.1   69.01  282.27  128.16  279.24  207.03  278.97  246.46  279.52
  256.32  279.05  325.33  278.67  345.04  278.89  374.62  277.92  384.48  277.93
  414.05  279.03  423.91  276.03  433.77  277.74  453.49  277.88  463.34  276.85
  483.06  278.52  502.14  278.54  520.58  277.45  539.02  277.15  548.24  277.51
  566.68  279.04  603.56  280.52  641.63  278.19  670.18  277.99  698.73  276.63
  717.77  278.06   736.8  278.57  746.32  279.76  755.84  280.43  784.39  280.82
#Mann= 3 ,-1 , 0
       0     .05       0  414.05     .03       0  483.06     .05       0
Bank Sta=414.05,433.77
XS Rating Curve= 0 ,0
Exp/Cntr=0.3,0.1

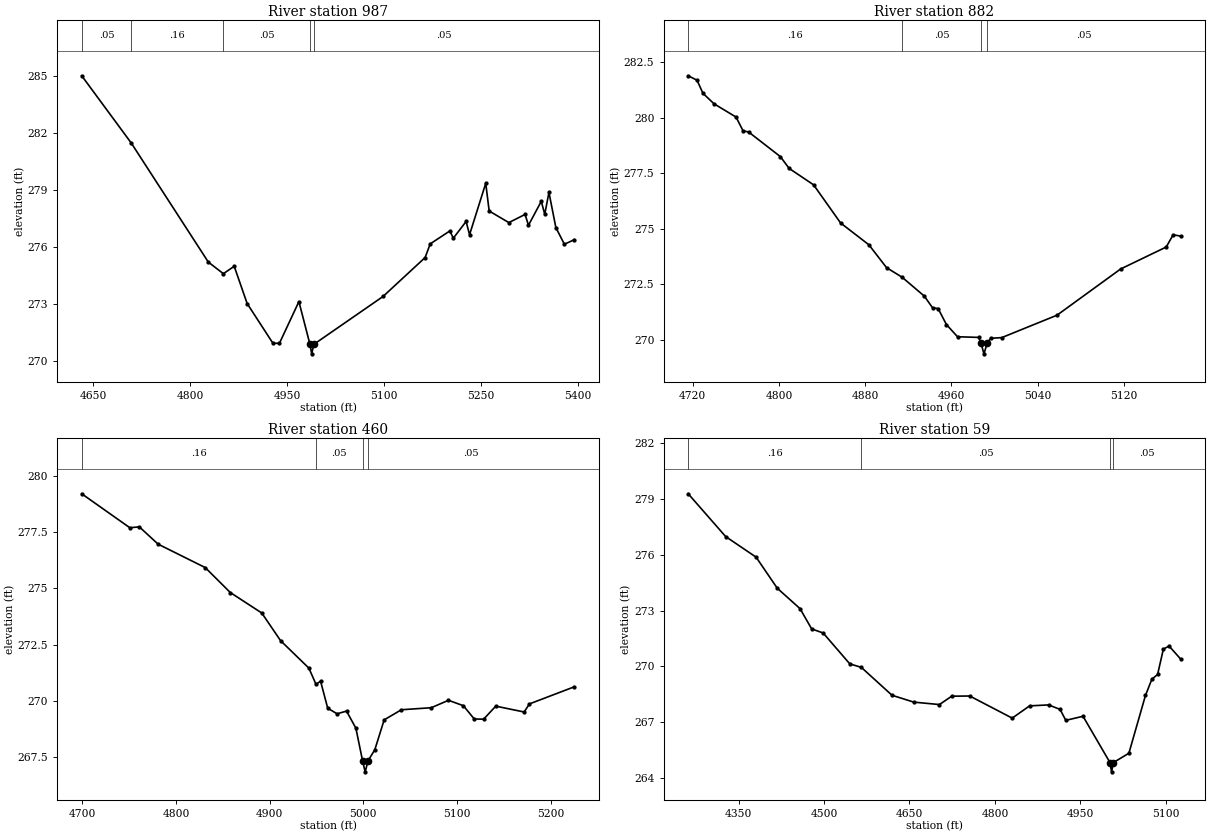
Type RM Length L Ch R = 1 ,987     ,105,105,105
BEGIN DESCRIPTION:
UNT031 IN GIBB 1.2
END DESCRIPTION:
XS GIS Cut Line= 3
      3644107.78     10230424.87      3643613.26     10230457.57
      3643520.82     10230708.48
#Sta/Elev= 30
  4631.9     285  4708.6  281.46    4828  275.19  4851.3  274.58  4868.1  274.97
  4888.1  273.01  4928.2  270.91  4938.2  270.92  4968.3  273.11  4985.4  270.86
  4988.1  270.36  4991.4  270.86  5098.6  273.38  5163.8  275.43  5171.7  276.15
  5202.1  276.83  5207.5  276.45  5227.3  277.33  5232.6  276.63  5257.7  279.34
    5263  277.88  5293.5  277.27  5318.6   277.7  5323.9  277.13  5343.7  278.39
  5349.1  277.71  5355.6  278.86  5366.3  277.01  5379.5  276.13  5394.9  276.37
#Mann= 5 ,-1 , 0
  4631.9     .05       0  4708.6     .16       0  4851.3     .05       0
  4985.4     .03       0  4991.4     .05       0
Bank Sta=4985.4,4991.4
XS Rating Curve= 0 ,0
Exp/Cntr=0.3,0.1

Type RM Length L Ch R = 1 ,882     ,422,422,422
BEGIN DESCRIPTION:
Mapping XS 43219f5d
END DESCRIPTION:
XS GIS Cut Line= 3
      3644015.41     10230284.86      3643622.19       10230376.
      3643589.23     10230417.83
#Sta/Elev= 30
  4715.8  281.88    4724  281.68  4729.5  281.09  4739.7  280.62  4760.2  280.02
  4766.7   279.4  4771.8  279.35  4801.3  278.24  4809.4  277.71  4832.1  276.97
  4857.2  275.25  4883.4  274.27  4899.8  273.24  4914.2  272.81  4934.8  271.96
  4942.5  271.43  4947.6   271.4  4955.3  270.68  4965.6  270.13  4985.2   270.1
  4987.3  269.86  4990.1  269.36  4993.3  269.86  4996.3  270.06  5006.6  270.09
  5057.9   271.1  5116.9  273.18  5159.2  274.17  5165.6  274.72  5172.7  274.66
#Mann= 4 ,-1 , 0
  4715.8     .16       0  4914.2     .05       0  4987.3     .03       0
  4993.3     .05       0
Bank Sta=4987.3,4993.3
XS Rating Curve= 0 ,0
Exp/Cntr=0.3,0.1

Type RM Length L Ch R = 1 ,460     ,401,401,401
BEGIN DESCRIPTION:
Mapping XS fc54775a
END DESCRIPTION:
XS GIS Cut Line= 3
      3644053.22     10230019.23      3643671.67      10230060.9
      3643601.36     10230184.59
#Sta/Elev= 30
  4699.2   279.2  4750.6  277.69  4760.7  277.73  4780.8  276.96  4831.1  275.92
  4857.9  274.81  4891.5   273.9  4911.6  272.67  4941.8  271.45  4949.4  270.73
  4954.3  270.87  4961.9  269.67  4971.9  269.42    4982  269.54    4992  268.78
  4999.1  267.34  5001.9  266.84  5005.1  267.34  5012.2  267.82  5022.2  269.15
  5040.6   269.6  5072.5  269.69  5090.9  270.02  5106.8  269.78  5118.4  269.19
  5128.4  269.18  5141.4  269.76  5171.7   269.5  5177.4  269.86  5225.3  270.62
#Mann= 4 ,-1 , 0
  4699.2     .16       0  4949.4     .05       0  4999.1     .03       0
  5005.1     .05       0
Bank Sta=4999.1,5005.1
XS Rating Curve= 0 ,0
Exp/Cntr=0.3,0.1

Type RM Length L Ch R = 1 ,59      ,0,0,0
BEGIN DESCRIPTION:
UNT031 IN GIBB 1.0
END DESCRIPTION:
XS GIS Cut Line= 4
       3644137.3     10229840.63      3643748.82     10229793.97
      3643543.75     10229868.84      3643574.01     10230122.05
#Sta/Elev= 30
  4261.7  279.29  4327.4  276.99  4380.9  275.88    4418  274.21    4458  273.11
  4478.4  272.02  4498.6   271.8  4545.3  270.14  4565.6  269.95  4619.4  268.45
  4657.8  268.08  4702.7  267.95  4724.2   268.4  4755.9  268.41  4830.4  267.22
    4861  267.88  4894.3  267.93  4914.4  267.69  4924.5   267.1  4954.7  267.32
    5002  264.83  5004.8  264.33    5008  264.83  5035.2  265.33  5064.3  268.44
  5075.5  269.31  5085.6  269.57  5095.7  270.93  5105.7   271.1  5126.3  270.39
#Mann= 4 ,-1 , 0
  4261.7     .16       0  4565.6     .05       0    5002     .03       0
    5008     .05       0
Bank Sta=5002,5008
XS Rating Curve= 0 ,0
Exp/Cntr=0.3,0.1

Chan Stop Cuts=-1
Use User Specified Reach Order=0
Composite Channel Slope=5