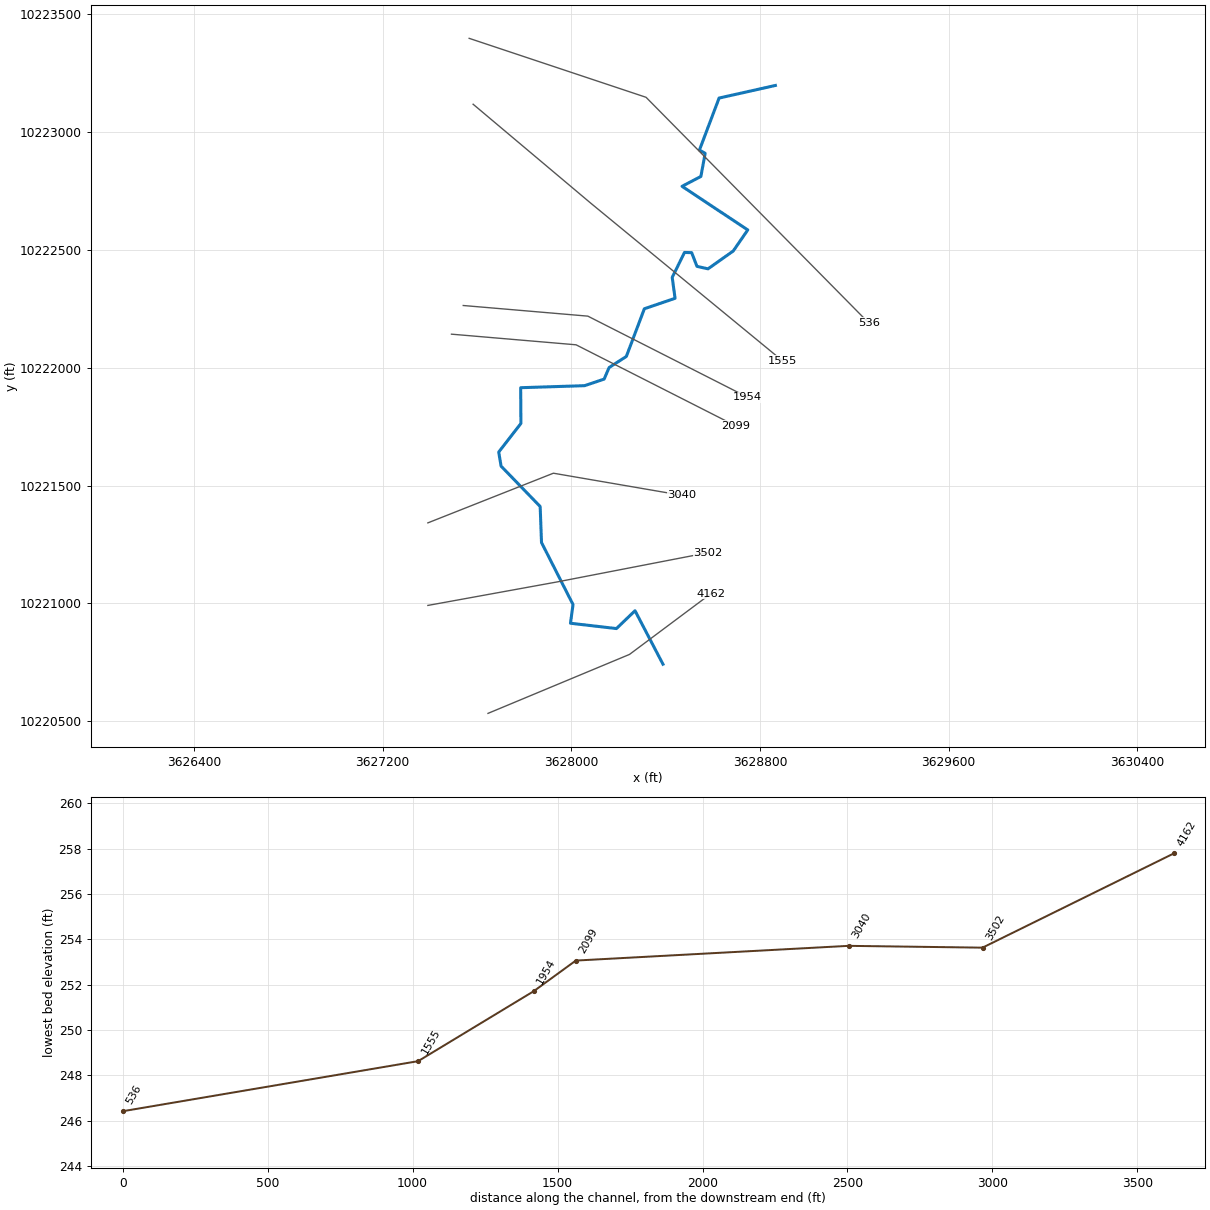
--- UNT034 IN GIBB.prj (project) ---

Proj Title=UNT034 IN GIBB Base Level Engineering
Current Plan=p01
Default Exp/Contr=0.3,0.1
English Units
Geom File=g01
Flow File=f01
Plan File=p01
Y Axis Title=Elevation
X Axis Title(PF)=Main Channel Distance
X Axis Title(XS)=Station
BEGIN DESCRIPTION:
UNT034 IN GIBB
END DESCRIPTION:
DSS Export Rating Curves= 0
DSS Export Rating Curve Sorted= 0
DSS Export Volume Flow Curves= 0
DXF OffsetX= 0
DXF OffsetY= 0
DXF ScaleX= 1
DXF ScaleY= 10

--- UNT034 IN GIBB.p01 (plan) ---

Plan Title=Multiple Run
Short Identifier=Multiple
Geom File=g01
Flow File=f01
Subcritical Flow
K Sum by GR= 0
Std Step Tol= 0.01
Critical Tol= 0.01
Num of Std Step Trials= 20
Max Error Tol= 0.3
Flow Tol Ratio= 0.001
Split Flow NTrial= 30
Split Flow Tol= 0.02
Split Flow Ratio= 0.02
Log Output Level= 0
Friction Slope Method= 1
Unsteady Friction Slope Method= 2
Unsteady Bridges Friction Slope Method= 1
Parabolic Critical Depth
Global Vel Dist=  1 , 1 , 1
Global Log Level= 0
CheckData=True
Encroach Param= -1, 0, 0, 0
BEGIN DESCRIPTION:
Multiple Run
END DESCRIPTION:

--- UNT034 IN GIBB.f01 (steady flow) ---

Flow Title=Multiple
Program Version=4.10
Number of Profiles= 7
Profile Names=10-year,25-year,50-year,1pct_min,100-year,1pct_plu,500-year
River Rch & RM=UNT034 IN GIBB,Reach-1         ,4162
     341     439     516     445     602     814     818
River Rch & RM=UNT034 IN GIBB,Reach-1         ,1555
     590     787     946     833    1127    1524    1600
River Rch & RM=UNT034 IN GIBB,Reach-1         ,536
     590     787     946     833    1127    1524    1600
Boundary for River Rch & Prof#=UNT034 IN GIBB,Reach-1         , 1
Up Type= 0
Dn Type= 3
Dn Slope=0.005
Boundary for River Rch & Prof#=UNT034 IN GIBB,Reach-1         , 2
Up Type= 0
Dn Type= 3
Dn Slope=0.005
Boundary for River Rch & Prof#=UNT034 IN GIBB,Reach-1         , 3
Up Type= 0
Dn Type= 3
Dn Slope=0.005
Boundary for River Rch & Prof#=UNT034 IN GIBB,Reach-1         , 4
Up Type= 0
Dn Type= 3
Dn Slope=0.005
Boundary for River Rch & Prof#=UNT034 IN GIBB,Reach-1         , 5
Up Type= 0
Dn Type= 3
Dn Slope=0.005
Boundary for River Rch & Prof#=UNT034 IN GIBB,Reach-1         , 6
Up Type= 0
Dn Type= 3
Dn Slope=0.005
Boundary for River Rch & Prof#=UNT034 IN GIBB,Reach-1         , 7
Up Type= 0
Dn Type= 3
Dn Slope=0.005
DSS Import GetInterval= 0
DSS Import GetPeak= 0
DSS Import FillOption= 0

--- UNT034 IN GIBB.g01 (geometry) ---

Geom Title=Existing Conditions

River Reach=UNT034 IN GIBB,Reach-1
Reach XY= 30
      3628388.78     10220742.43      3628270.32     10220969.22
      3628191.47     10220893.54      3627996.68     10220916.10
      3628007.43     10220995.26      3627873.84     10221258.24
      3627868.17     10221411.04      3627702.48     10221582.16
      3627692.42     10221641.85      3627786.50     10221763.14
      3627785.54     10221914.67      3628056.41     10221923.29
      3628139.34     10221951.11      3628160.58     10222000.24
      3628233.49     10222047.12      3628309.88     10222249.37
      3628440.09     10222293.64      3628427.94     10222382.19
      3628480.02     10222488.09      3628510.40     10222487.22
      3628532.97     10222429.06      3628579.85     10222418.64
      3628686.62     10222494.16      3628748.25     10222583.57
      3628469.60     10222768.47      3628549.46     10222810.14
      3628567.69     10222908.23      3628543.39     10222922.12
      3628626.72     10223142.60      3628865.33     10223196.03

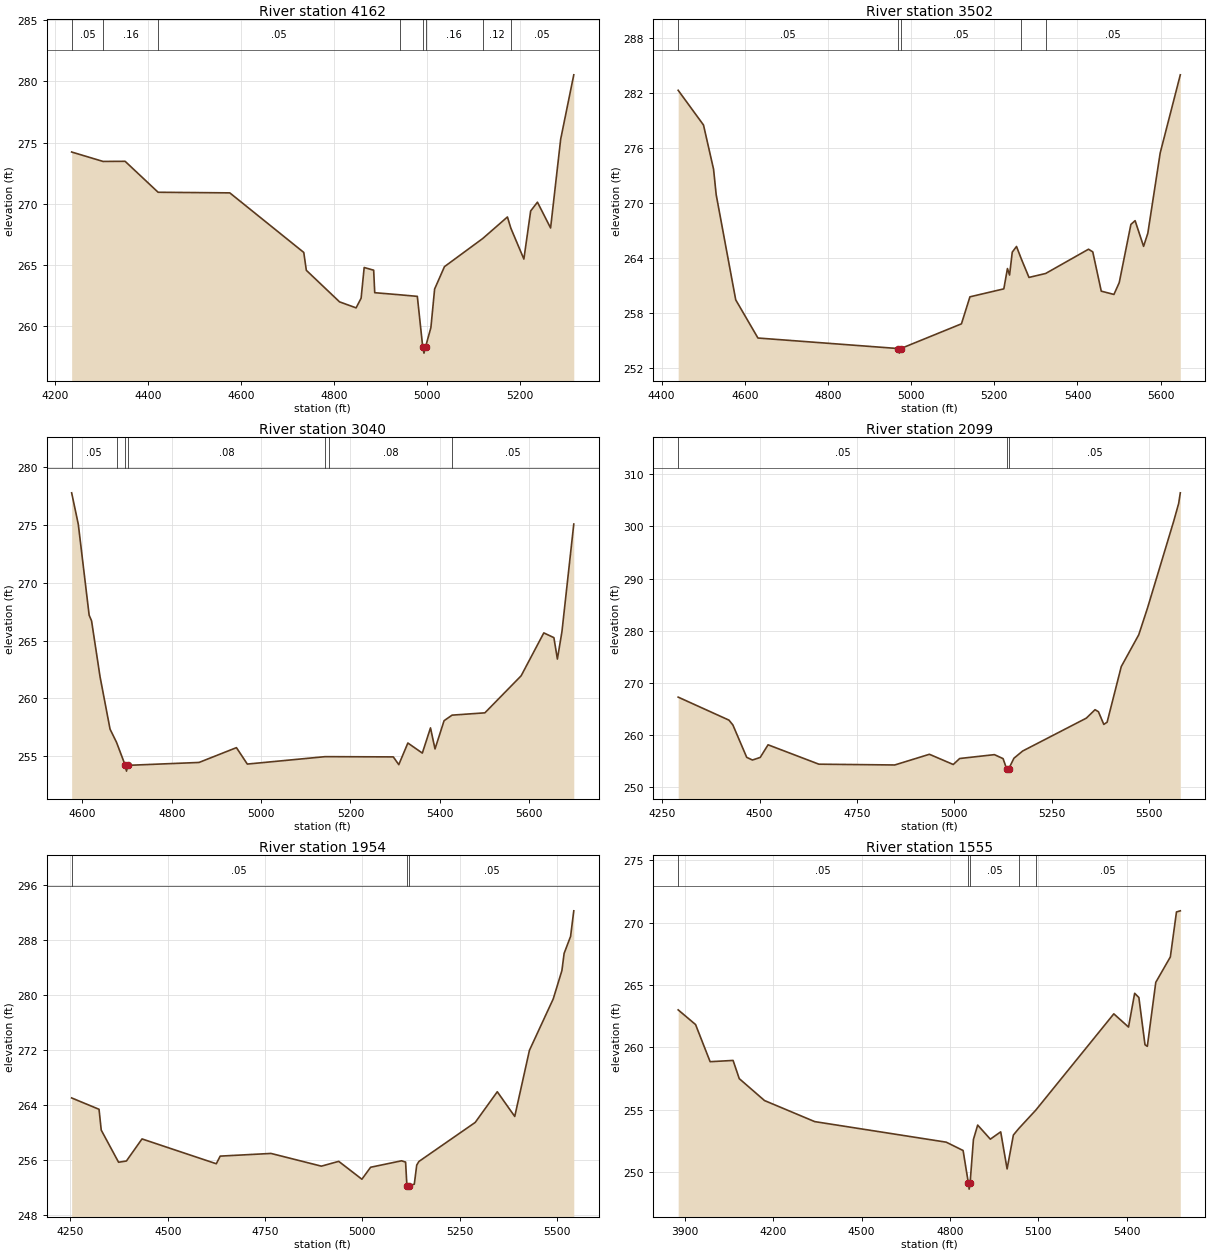
Type RM Length L Ch R = 1,4162,660,660,660
BEGIN DESCRIPTION:
UNT034 IN GIBB 5.0
END DESCRIPTION:
XS GIS Cut Line= 3
      3627646.99     10220534.01      3628246.97     10220784.00
      3628592.13     10221041.66
#Sta/Elev= 30
  4235.9  274.23  4303.5  273.46  4351.0  273.47  4422.0  270.94  4576.3  270.89
  4735.5  266.02  4741.0  264.56  4812.5  261.98  4848.1  261.49  4858.9  262.28
  4865.5  264.79  4885.9  264.57  4888.2  262.73  4941.7  262.56  4979.9  262.43
  4991.5  258.29  4994.2  257.79  4997.5  258.29  5009.1  259.88  5017.1  263.03
  5038.3  264.86  5120.7  267.16  5173.8  268.92  5181.1  268.01  5209.2  265.48
  5223.8  269.41  5238.4  270.13  5266.7  268.02  5288.4  275.28  5316.6  280.54
#Mann=8,-1,0
  4235.9    0.05       0  4303.5    0.16       0  4422.0    0.05       0
  4941.7    0.16       0  4991.5    0.07       0  4997.5    0.16       0
  5120.7    0.12       0  5181.1    0.05       0
Bank Sta=4991.5,4997.5
Exp/Cntr=0.3,0.1

Type RM Length L Ch R = 1,3502,462,462,462
BEGIN DESCRIPTION:
UNT034 IN GIBB 4.0
END DESCRIPTION:
XS GIS Cut Line= 3
      3627392.14     10220991.65      3627942.11     10221091.64
      3628578.77     10221215.06
#Sta/Elev= 30
  4439.8  282.34  4500.7  278.55  4524.9  273.72  4531.2  270.94  4578.2  259.45
  4631.6  255.28  4969.1  254.13  4971.9  253.63  4975.1  254.13  5121.0  256.83
  5141.4  259.78  5222.9  260.65  5231.6  262.87  5236.7  262.16  5243.2  264.66
  5253.4  265.28  5264.8  263.94  5283.4  261.90  5323.5  262.33  5426.6  264.98
  5436.8  264.69  5457.2  260.40  5487.7  260.04  5500.5  261.34  5528.5  267.69
  5538.6  268.10  5559.0  265.29  5569.2  266.73  5598.9  275.49  5647.3  284.03
#Mann=5,-1,0
  4439.8    0.05       0  4969.1   0.033       0  4975.1    0.05       0
  5264.8    0.12       0  5323.5    0.05       0
Bank Sta=4969.1,4975.1
Exp/Cntr=0.3,0.1

Type RM Length L Ch R = 1,3040,941,941,941
BEGIN DESCRIPTION:
UNT034 IN GIBB 3.0
END DESCRIPTION:
XS GIS Cut Line= 3
      3627392.09     10221341.64      3627924.24     10221552.19
      3628468.26     10221458.64
#Sta/Elev= 30
  4575.8  277.77  4590.7  275.05  4615.0  267.19  4620.4  266.70  4639.4  261.87
  4661.8  257.34  4676.3  256.20  4695.8  254.21  4698.6  253.71  4701.8  254.21
  4861.0  254.46  4944.8  255.74  4969.1  254.32  5143.0  254.96  5151.4  254.96
  5296.0  254.94  5308.3  254.27  5328.6  256.14  5361.0  255.27  5379.3  257.45
  5389.4  255.63  5409.7  258.07  5427.6  258.55  5501.1  258.75  5582.2  261.95
  5633.0  265.66  5655.6  265.25  5663.4  263.40  5673.6  265.77  5700.1  275.07
#Mann=7,-1,0
  4575.8    0.05       0  4676.3    0.08       0  4695.8    0.07       0
  4701.8    0.08       0  5143.0    0.05       0  5151.4    0.08       0
  5427.6    0.05       0
Bank Sta=4695.8,4701.8
Exp/Cntr=0.3,0.1

Type RM Length L Ch R = 1,2099,145,145,145
BEGIN DESCRIPTION:
UNT034 IN GIBB 2.2
END DESCRIPTION:
XS GIS Cut Line= 3
      3627492.14     10222141.64      3628020.35     10222096.55
      3628697.27     10221752.88
#Sta/Elev= 30
  4290.8  267.25  4421.2  262.84  4431.3  261.91  4466.8  255.70  4481.5  255.19
  4501.5  255.69  4521.6  258.11  4652.1  254.39  4846.9  254.24  4935.9  256.29
  4997.1  254.33  5013.6  255.48  5102.8  256.22  5125.0  255.46  5133.9  253.56
  5136.7  253.06  5139.9  253.56  5152.9  255.53  5175.2  256.91  5338.8  263.22
  5361.2  264.84  5369.9  264.45  5383.7  262.02  5392.2  262.45  5428.5  273.11
  5473.4  279.21  5495.8  284.32  5563.1  300.98  5575.9  304.40  5580.1  306.43
#Mann=3,-1,0
  4290.8    0.05       0  5133.9    0.03       0  5139.9    0.05       0
Bank Sta=5133.9,5139.9
Exp/Cntr=0.3,0.1

Type RM Length L Ch R = 1,1954,399,399,399
BEGIN DESCRIPTION:
UNT034 IN GIBB 2.1
END DESCRIPTION:
XS GIS Cut Line= 3
      3627542.03     10222263.17      3628070.26     10222218.08
      3628747.25     10221874.37
#Sta/Elev= 30
  4253.3  264.97  4323.6  263.32  4329.3  260.29  4373.8  255.62  4393.9  255.80
  4434.0  259.01  4624.7  255.40  4634.8  256.51  4765.2  256.90  4894.6  255.05
  4939.1  255.75  4998.6  253.15  5021.0  254.89  5100.5  255.83  5110.8  255.64
  5114.2  252.21  5116.9  251.71  5120.2  252.21  5133.2  252.43  5139.4  255.20
  5145.0  255.73  5289.6  261.41  5346.3  265.87  5391.1  262.28  5428.8  271.89
  5490.0  279.38  5512.2  283.49  5517.9  285.99  5534.5  288.46  5542.7  292.18
#Mann=3,-1,0
  4253.3    0.05       0  5114.2    0.03       0  5120.2    0.05       0
Bank Sta=5114.2,5120.2
Exp/Cntr=0.3,0.1

Type RM Length L Ch R = 1,1555,1019,1019,1019
BEGIN DESCRIPTION:
UNT034 IN GIBB 2.0
END DESCRIPTION:
XS GIS Cut Line= 3
      3627583.98     10223116.42      3628084.07     10222695.78
      3628896.49     10222027.87
#Sta/Elev= 30
  3877.4  263.01  3936.5  261.83  3985.9  258.85  4063.9  258.95  4084.8  257.49
  4170.6  255.73  4341.0  254.04  4787.6  252.39  4845.0  251.72  4862.8  249.12
  4865.5  248.62  4868.8  249.12  4880.1  252.61  4894.5  253.76  4937.5  252.63
  4972.7  253.22  4994.4  250.24  5015.7  252.96  5033.5  253.47  5091.8  254.96
  5356.8  262.69  5406.7  261.63  5427.6  264.34  5441.9  264.00  5462.7  260.21
  5470.6  260.08  5499.3  265.22  5548.8  267.26  5569.6  270.87  5582.6  270.96
#Mann=5,-1,0
  3877.4    0.05       0  4862.8    0.03       0  4868.8    0.05       0
  5033.5    0.16       0  5091.8    0.05       0
Bank Sta=4862.8,4868.8
Exp/Cntr=0.3,0.1

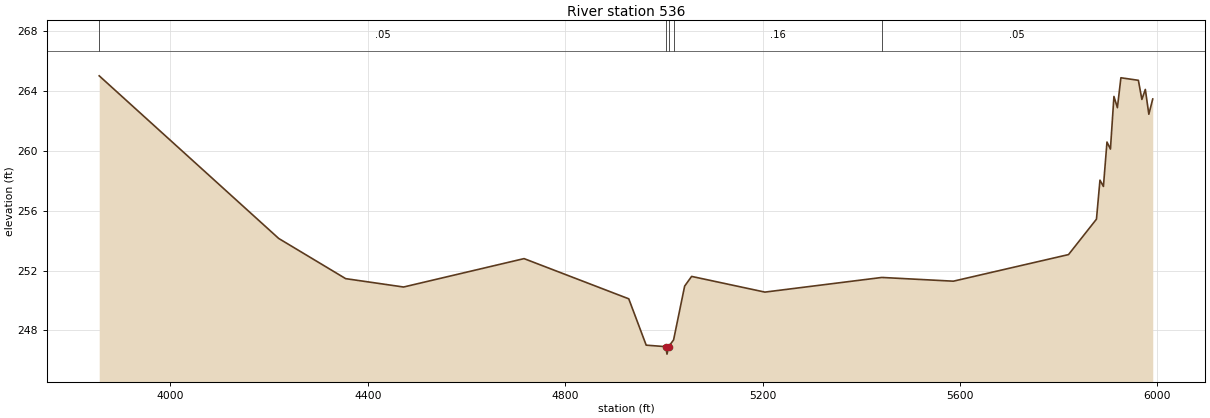
Type RM Length L Ch R = 1,536,0,0,0
BEGIN DESCRIPTION:
UNT034 IN GIBB 1.0
END DESCRIPTION:
XS GIS Cut Line= 3
      3627567.14     10223395.80      3628317.11     10223145.81
      3629261.01     10222189.38
#Sta/Elev= 30
  3856.1  265.03  4219.7  254.15  4355.4  251.46  4472.7  250.90  4716.8  252.80
  4928.9  250.11  4964.2  247.01  5003.6  246.91  5006.4  246.41  5009.6  246.91
  5019.7  247.36  5042.1  250.96  5056.2  251.61  5204.7  250.56  5441.6  251.54
  5586.5  251.29  5819.8  253.07  5876.4  255.44  5883.5  258.05  5890.5  257.63
  5897.7  260.60  5904.7  260.13  5911.8  263.65  5918.8  262.90  5925.9  264.90
  5961.3  264.73  5968.4  263.45  5975.4  264.12  5982.5  262.46  5990.4  263.48
#Mann=5,-1,0
  3856.1    0.05       0  5003.6    0.03       0  5009.6    0.05       0
  5019.7    0.16       0  5441.6    0.05       0
Bank Sta=5003.6,5009.6
Exp/Cntr=0.3,0.1

Chan Stop Cuts=-1