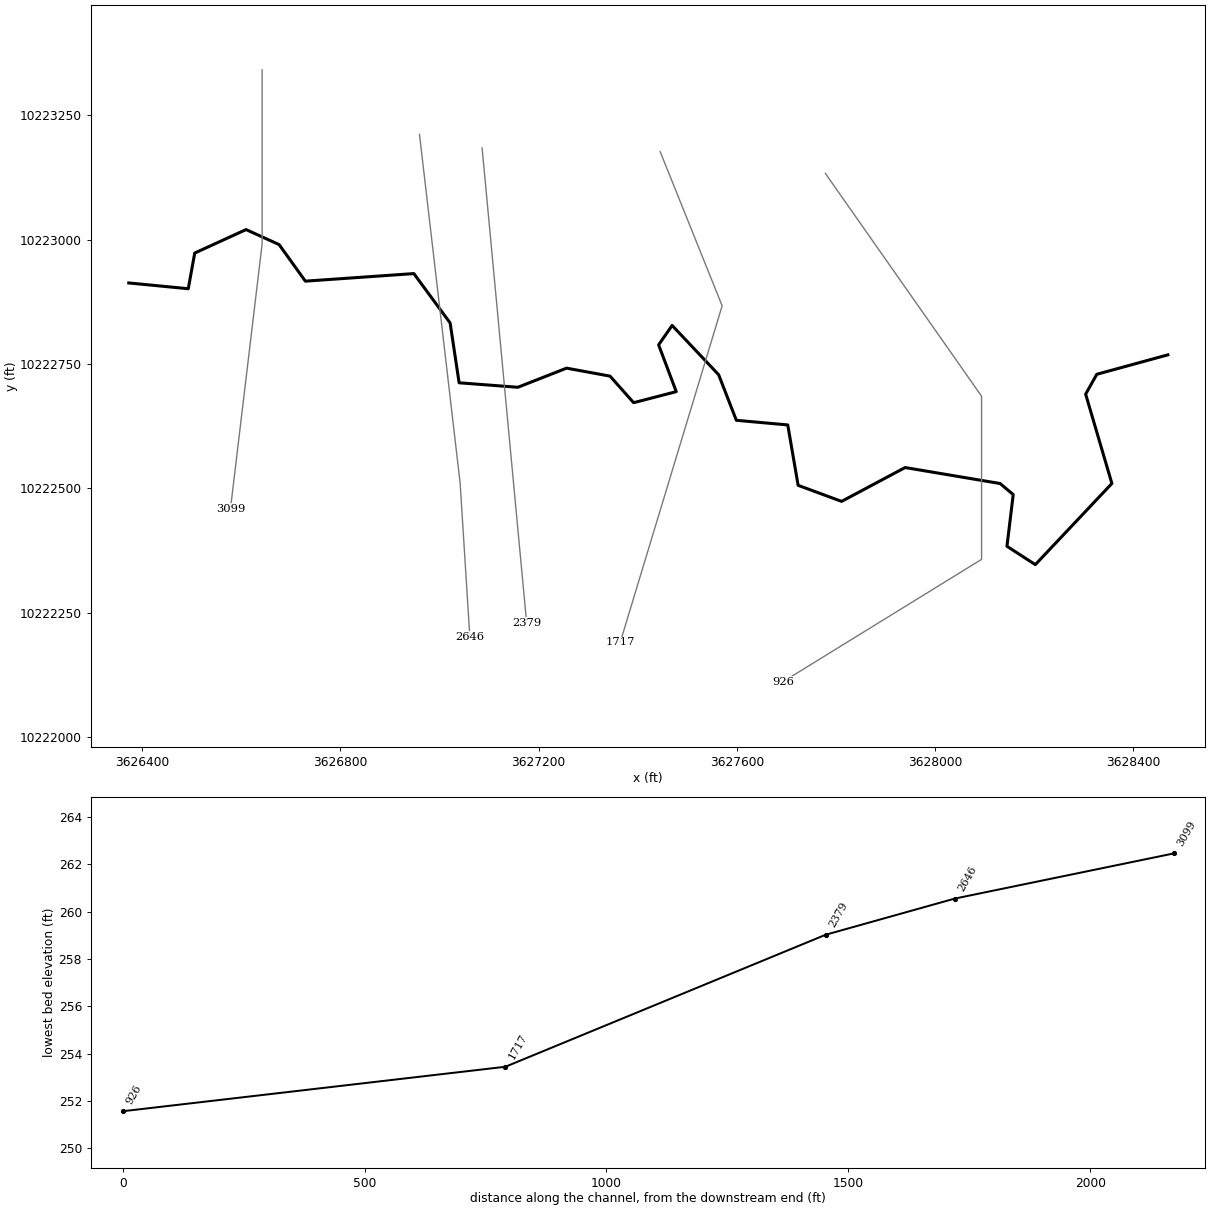
--- UNT035 IN GIBB.prj (project) ---

Proj Title=UNT035 IN GIBB Base Level Engineering
Current Plan=p01
Default Exp/Contr=0.3,0.1
English Units
Geom File=g01
Flow File=f01
Plan File=p01
Y Axis Title=Elevation
X Axis Title(PF)=Main Channel Distance
X Axis Title(XS)=Station
BEGIN DESCRIPTION:
UNT035 IN GIBB
END DESCRIPTION:
DSS Export Rating Curves= 0
DSS Export Rating Curve Sorted= 0
DSS Export Volume Flow Curves= 0
DXF OffsetX= 0
DXF OffsetY= 0
DXF ScaleX= 1
DXF ScaleY= 10

--- UNT035 IN GIBB.p01 (plan) ---

Plan Title=Multiple Run
Short Identifier=Multiple
Geom File=g01
Flow File=f01
Subcritical Flow
K Sum by GR= 0
Std Step Tol= 0.01
Critical Tol= 0.01
Num of Std Step Trials= 20
Max Error Tol= 0.3
Flow Tol Ratio= 0.001
Split Flow NTrial= 30
Split Flow Tol= 0.02
Split Flow Ratio= 0.02
Log Output Level= 0
Friction Slope Method= 1
Unsteady Friction Slope Method= 2
Unsteady Bridges Friction Slope Method= 1
Parabolic Critical Depth
Global Vel Dist=  1 , 1 , 1
Global Log Level= 0
CheckData=True
Encroach Param= -1, 0, 0, 0
BEGIN DESCRIPTION:
Multiple Run
END DESCRIPTION:

--- UNT035 IN GIBB.f01 (steady flow) ---

Flow Title=Multiple
Number of Profiles=7
Profile Names=10-year,25-year,50-year,1pct_min,100-year,1pct_plu,500-year
River Rch & RM= UNT035 IN GIBB,Reach-1,3099
     312     401     471     405     548     741     744
Boundary for River Rch & Prof#=UNT035 IN GIBB,Reach-1,1
Up Type=0
Dn Type=3
Dn Slope=0.005
Boundary for River Rch & Prof#=UNT035 IN GIBB,Reach-1,2
Up Type=0
Dn Type=3
Dn Slope=0.005
Boundary for River Rch & Prof#=UNT035 IN GIBB,Reach-1,3
Up Type=0
Dn Type=3
Dn Slope=0.005
Boundary for River Rch & Prof#=UNT035 IN GIBB,Reach-1,4
Up Type=0
Dn Type=3
Dn Slope=0.005
Boundary for River Rch & Prof#=UNT035 IN GIBB,Reach-1,5
Up Type=0
Dn Type=3
Dn Slope=0.005
Boundary for River Rch & Prof#=UNT035 IN GIBB,Reach-1,6
Up Type=0
Dn Type=3
Dn Slope=0.005
Boundary for River Rch & Prof#=UNT035 IN GIBB,Reach-1,7
Up Type=0
Dn Type=3
Dn Slope=0.005

--- UNT035 IN GIBB.g01 (geometry) ---

Geom Title=Existing Conditions
Program Version=4.10

River Reach=UNT035 IN GIBB  ,Reach-1
Reach XY= 30
      3626373.01     10222913.08      3626493.05     10222901.47
       3626506.1     10222973.23      3626609.69     10223020.43
      3626676.35     10222990.22      3626729.35     10222916.69
      3626948.25     10222931.91      3627021.46     10222832.61
      3627039.58     10222712.29      3627158.12     10222703.25
      3627256.41     10222741.72      3627344.13     10222725.67
      3627391.75     10222672.25      3627477.74     10222694.49
      3627442.13     10222788.57      3627469.37     10222827.63
      3627563.23     10222728.58      3627598.99     10222636.86
       3627702.7     10222627.53      3627723.64     10222506.07
      3627811.35     10222473.78      3627939.56     10222541.85
      3628131.19      10222509.7      3628157.67     10222487.47
      3628145.03     10222383.49      3628202.24     10222346.59
      3628356.76     10222509.79       3628303.8     10222689.48
      3628326.37     10222729.41       3628469.6     10222768.47

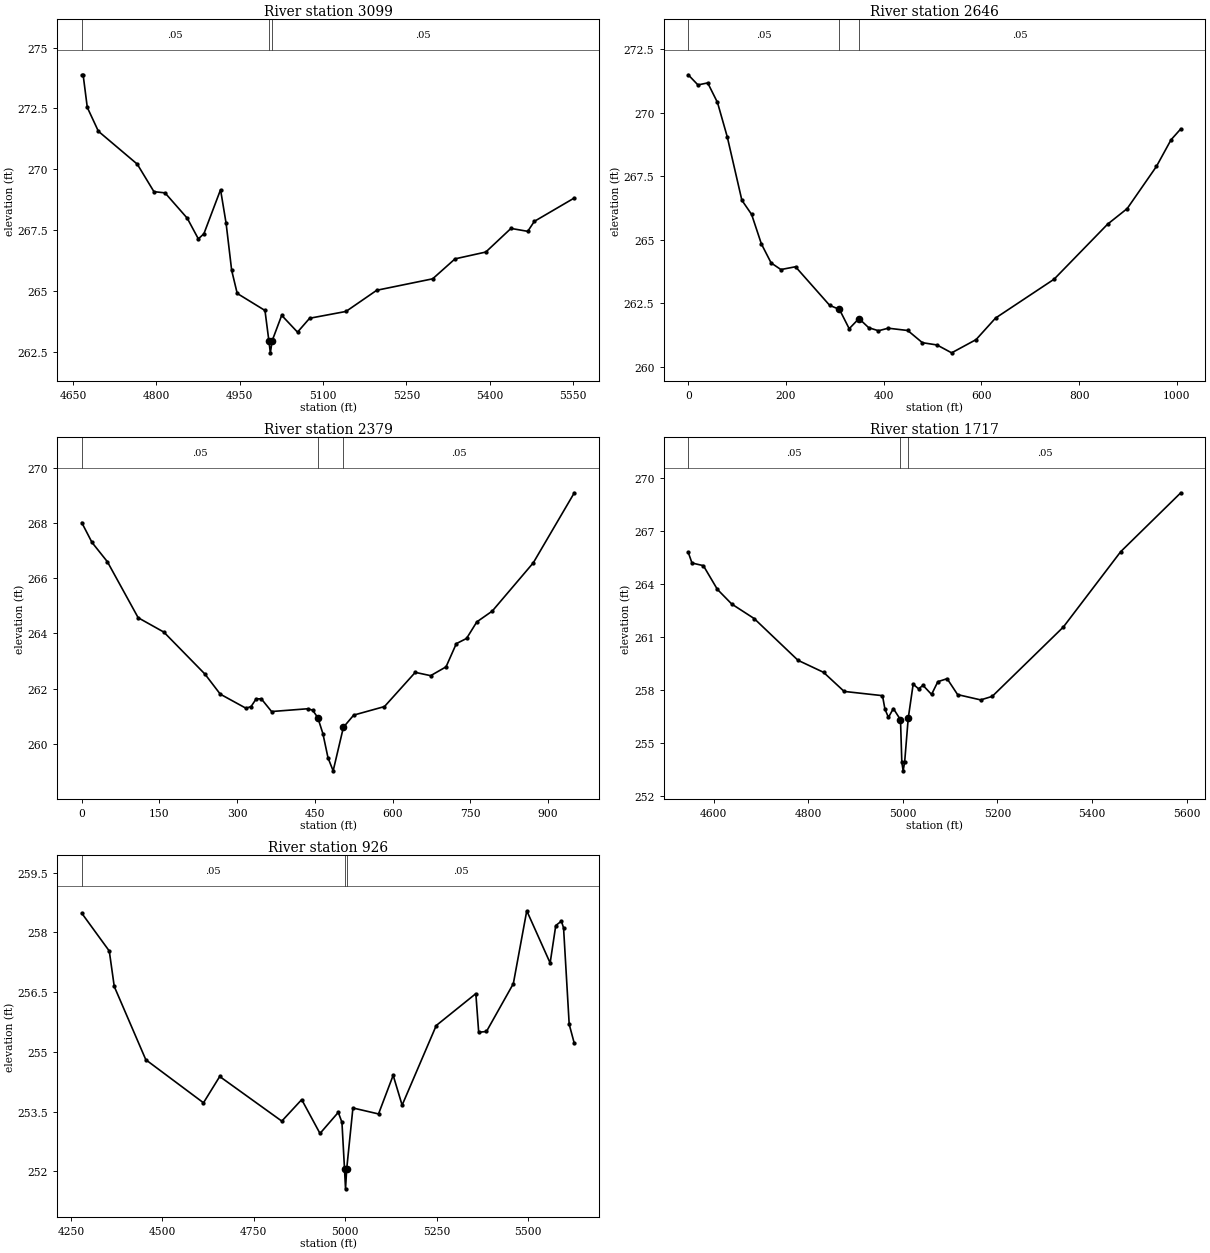
Type RM Length L Ch R = 1 ,3099    ,453,453,453
BEGIN DESCRIPTION:
UNT035 IN GIBB 4.0
END DESCRIPTION:
XS GIS Cut Line= 3
      3626642.11     10223341.62      3626642.11     10222991.64
      3626578.14     10222458.35
#Sta/Elev= 30
  4665.4  273.88  4667.9  273.88  4675.4  272.54  4695.4  271.56  4765.4  270.21
  4795.4  269.08  4815.4  269.03  4855.4  267.99  4875.4  267.14  4885.4  267.35
  4915.4  269.16  4925.4  267.78  4935.4  265.85  4945.4   264.9  4995.4   264.2
  5002.4  262.96  5005.1  262.46  5008.4  262.96  5025.5     264    5054  263.31
  5075.8  263.88  5141.3  264.16  5196.7  265.03  5297.4   265.5  5337.7  266.32
  5393.1   266.6  5438.4  267.57  5468.6  267.45  5480.5  267.86  5552.5  268.82
#Mann= 3 ,-1 , 0
  4665.4     .05       0  5002.4     .03       0  5008.4     .05       0
Bank Sta=5002.4,5008.4
XS Rating Curve= 0 ,0
Exp/Cntr=0.3,0.1

Type RM Length L Ch R = 1 ,2646    ,267,267,267
XS GIS Cut Line= 3
     3626959.653    10223211.812     3627041.685    10222509.989
     3627061.216    10222201.396
#Sta/Elev= 30
       0   271.5   19.97   271.1   39.94  271.18   59.91  270.41   79.88  269.06
  109.83  266.56   129.8     266  149.77  264.84  169.74  264.09  189.71  263.83
  219.67  263.94  289.56  262.42  309.53  262.26   329.5   261.5  349.47   261.9
  369.44  261.54  389.41  261.42  409.38  261.52  449.31  261.43  479.27  260.95
  509.22  260.86  539.18  260.55   589.1  261.07  629.04  261.92  748.83  263.45
  858.54  265.62  898.43  266.23  958.27  267.89  988.18  268.94 1008.13  269.37
#Mann= 3 ,-1 , 0
       0     .05       0  309.53     .03       0  349.47     .05       0
Bank Sta=309.53,349.47
XS Rating Curve= 0 ,0
Exp/Cntr=0.3,0.1

Type RM Length L Ch R = 1 ,2379    ,662,662,662
XS GIS Cut Line= 2
     3627085.955    10223184.469     3627175.799    10222230.042
#Sta/Elev= 30
       0  268.02   19.81   267.3   49.52   266.6  108.94  264.57  158.46  264.05
  237.69  262.53   267.4   261.8  316.92  261.29  326.82  261.35  336.72  261.63
  346.63  261.63  366.43  261.17  435.76  261.27  445.66  261.22  455.57  260.95
  465.47  260.37  475.37  259.49  485.28  259.02  505.08   260.6  524.89  261.04
  584.31  261.35  643.73  262.59  673.45  262.47  703.16  262.79  722.96  263.63
  742.77  263.82  762.58  264.42  792.29  264.81  871.52  266.56  950.75   269.1
#Mann= 3 , 0 , 0
       0     .05       0  455.57     .03       0  505.08     .05       0
Bank Sta=455.57,505.08
XS Rating Curve= 0 ,0
Exp/Cntr=0.3,0.1

Type RM Length L Ch R = 1 ,1717    ,791,791,791
BEGIN DESCRIPTION:
UNT035 IN GIBB 2.0
END DESCRIPTION:
XS GIS Cut Line= 3
      3627445.33     10223177.02      3627570.32     10222867.15
      3627364.58     10222190.04
#Sta/Elev= 30
    4546   265.8    4554  265.19  4578.1  265.04  4607.7   263.7  4638.1  262.87
  4685.5  262.05  4778.2  259.69  4832.2  259.01  4875.8  257.93  4956.9  257.69
  4962.1  256.93  4969.5  256.46  4979.9  256.96    4995  256.33  4997.8  253.94
  5000.6  253.44  5003.8  253.94  5011.3   256.4  5021.8  258.34  5033.1  258.08
  5042.7  258.27  5060.7  257.76    5074  258.48  5093.6  258.65  5115.8  257.75
  5164.6  257.45    5189  257.65  5339.4  261.57  5460.7  265.83  5587.8  269.16
#Mann= 3 , 0 , 0
    4546     .05       0    4995     .03       0  5011.3     .05       0
Bank Sta=4995,5011.3
XS Rating Curve= 0 ,0
Exp/Cntr=0.3,0.1

Type RM Length L Ch R = 1 ,926     ,0,0,0
BEGIN DESCRIPTION:
UNT035 IN GIBB 1.0
END DESCRIPTION:
XS GIS Cut Line= 4
      3627778.68     10223133.24       3628093.8      10222685.3
       3628093.8     10222357.17       3627692.7     10222110.85
#Sta/Elev= 30
  4279.7  258.48    4355  257.53  4368.6  256.64  4454.9   254.8  4612.5  253.72
  4656.9  254.38  4826.6  253.26    4881   253.8    4931  252.95    4981  253.48
    4991  253.23    4998  252.06  5000.8  251.56    5004  252.06    5021  253.59
    5091  253.44    5131  254.41  5155.5  253.66  5248.8  255.66    5357  256.46
  5364.8  255.49  5386.1  255.51  5459.5  256.71  5496.2  258.54  5560.1  257.23
  5575.5  258.17  5590.9  258.28  5596.8  258.11  5612.2  255.69  5626.2  255.21
#Mann= 3 ,-1 , 0
  4279.7     .05       0    4998     .03       0    5004     .05       0
Bank Sta=4998,5004
XS Rating Curve= 0 ,0
Exp/Cntr=0.3,0.1

Chan Stop Cuts=-1
Use User Specified Reach Order=0
Composite Channel Slope=5