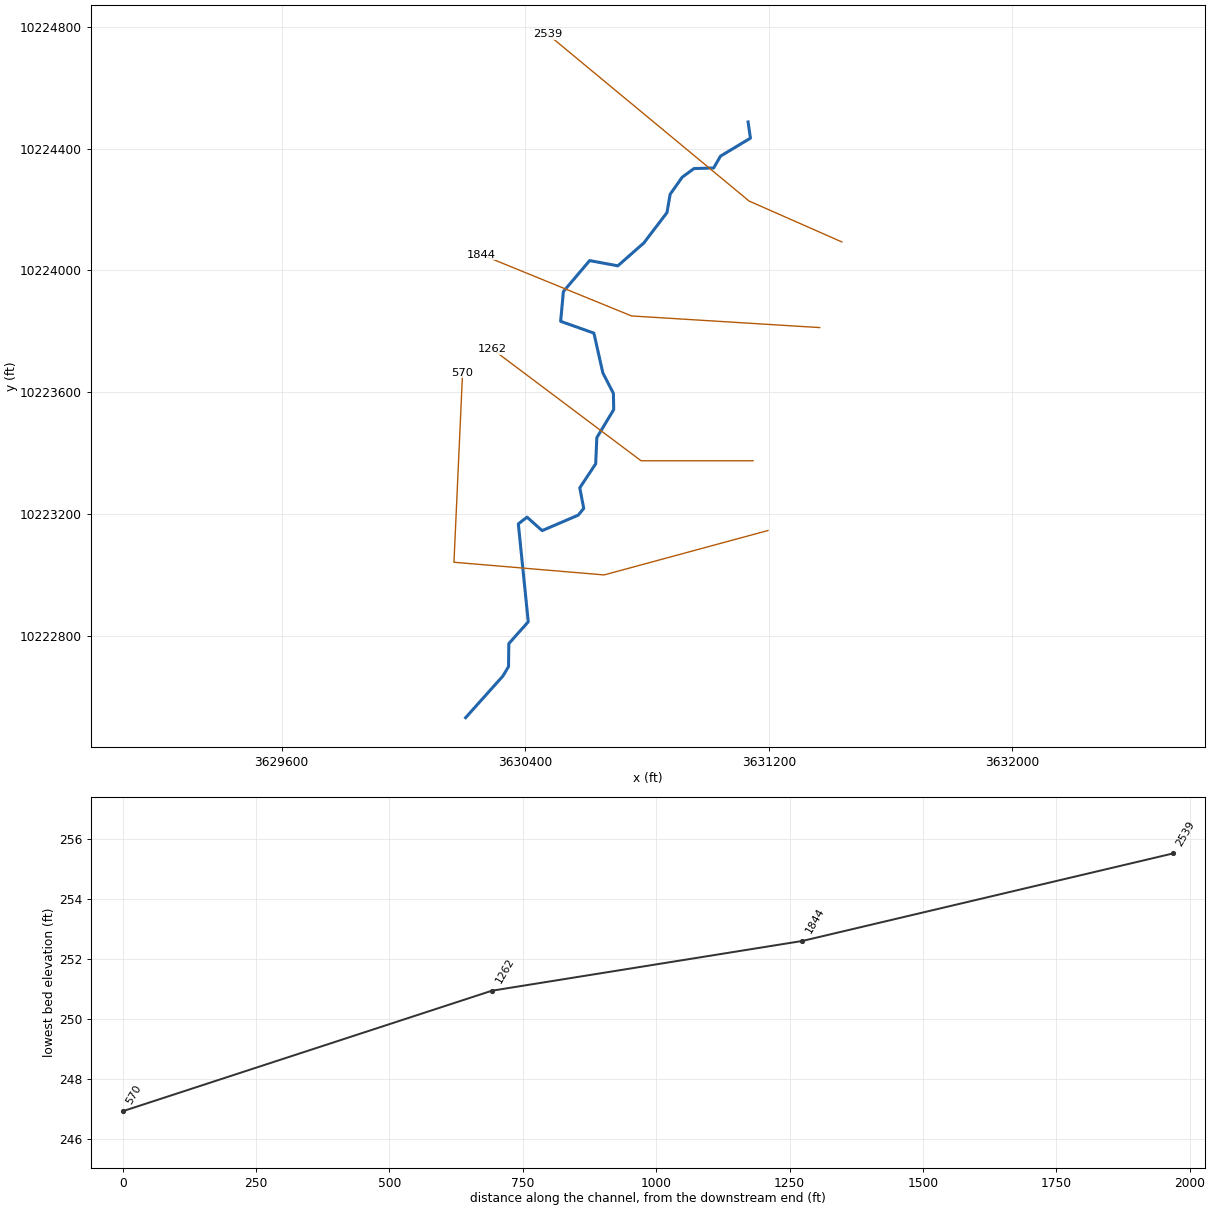
--- UNT036 IN GIBB.prj (project) ---

Proj Title=UNT036 IN GIBB Base Level Engineering
Current Plan=p01
Default Exp/Contr=0.3,0.1
English Units
Geom File=g01
Flow File=f01
Plan File=p01
BEGIN DESCRIPTION:
UNT036 IN GIBB
END DESCRIPTION:

--- UNT036 IN GIBB.p01 (plan) ---

Plan Title=Multiple Run
Short Identifier=Multiple
Geom File=g01
Flow File=f01
Subcritical Flow
K Sum by GR= 0
Std Step Tol= 0.01
Critical Tol= 0.01
Num of Std Step Trials= 20
Max Error Tol= 0.3
Flow Tol Ratio= 0.001
Split Flow NTrial= 30
Split Flow Tol= 0.02
Split Flow Ratio= 0.02
Log Output Level= 0
Friction Slope Method= 1
Unsteady Friction Slope Method= 2
Unsteady Bridges Friction Slope Method= 1
Parabolic Critical Depth
Global Vel Dist=  1 , 1 , 1
Global Log Level= 0
CheckData=True
Encroach Param= -1, 0, 0, 0
BEGIN DESCRIPTION:
Multiple Run
END DESCRIPTION:

--- UNT036 IN GIBB.f01 (steady flow) ---

Flow Title=Multiple
Number of Profiles=7
Profile Names=10-year,25-year,50-year,1pct_min,100-year,1pct_plu,500-year
River Rch & RM= UNT036 IN GIBB,Reach-1,2539
     305     391     458     394     533     721     721
Boundary for River Rch & Prof#=UNT036 IN GIBB,Reach-1,1
Up Type=0
Dn Type=3
Dn Slope=0.005
Boundary for River Rch & Prof#=UNT036 IN GIBB,Reach-1,2
Up Type=0
Dn Type=3
Dn Slope=0.005
Boundary for River Rch & Prof#=UNT036 IN GIBB,Reach-1,3
Up Type=0
Dn Type=3
Dn Slope=0.005
Boundary for River Rch & Prof#=UNT036 IN GIBB,Reach-1,4
Up Type=0
Dn Type=3
Dn Slope=0.005
Boundary for River Rch & Prof#=UNT036 IN GIBB,Reach-1,5
Up Type=0
Dn Type=3
Dn Slope=0.005
Boundary for River Rch & Prof#=UNT036 IN GIBB,Reach-1,6
Up Type=0
Dn Type=3
Dn Slope=0.005
Boundary for River Rch & Prof#=UNT036 IN GIBB,Reach-1,7
Up Type=0
Dn Type=3
Dn Slope=0.005

--- UNT036 IN GIBB.g01 (geometry) ---

Geom Title=Existing Conditions

River Reach=UNT036 IN GIBB,Reach-1
Reach XY= 30
      3631132.07     10224487.79      3631139.79     10224434.73
      3631041.43     10224375.57      3631019.06     10224336.79
      3630954.28     10224334.83      3630915.36     10224306.06
      3630876.00     10224250.15      3630865.78     10224190.30
      3630789.45     10224090.17      3630704.16     10224015.35
      3630611.71     10224032.51      3630525.38     10223930.83
      3630516.42     10223833.04      3630625.68     10223794.25
      3630654.97     10223663.86      3630689.69     10223596.43
      3630690.73     10223543.06      3630635.29     10223451.11
      3630631.53     10223365.00      3630579.25     10223286.12
      3630592.27     10223218.42      3630574.04     10223196.28
      3630455.55     10223145.50      3630406.07     10223189.77
      3630377.43     10223167.63      3630409.98     10222846.02
      3630346.18     10222774.40      3630345.17     10222698.74
      3630326.64     10222667.76      3630204.25     10222531.05

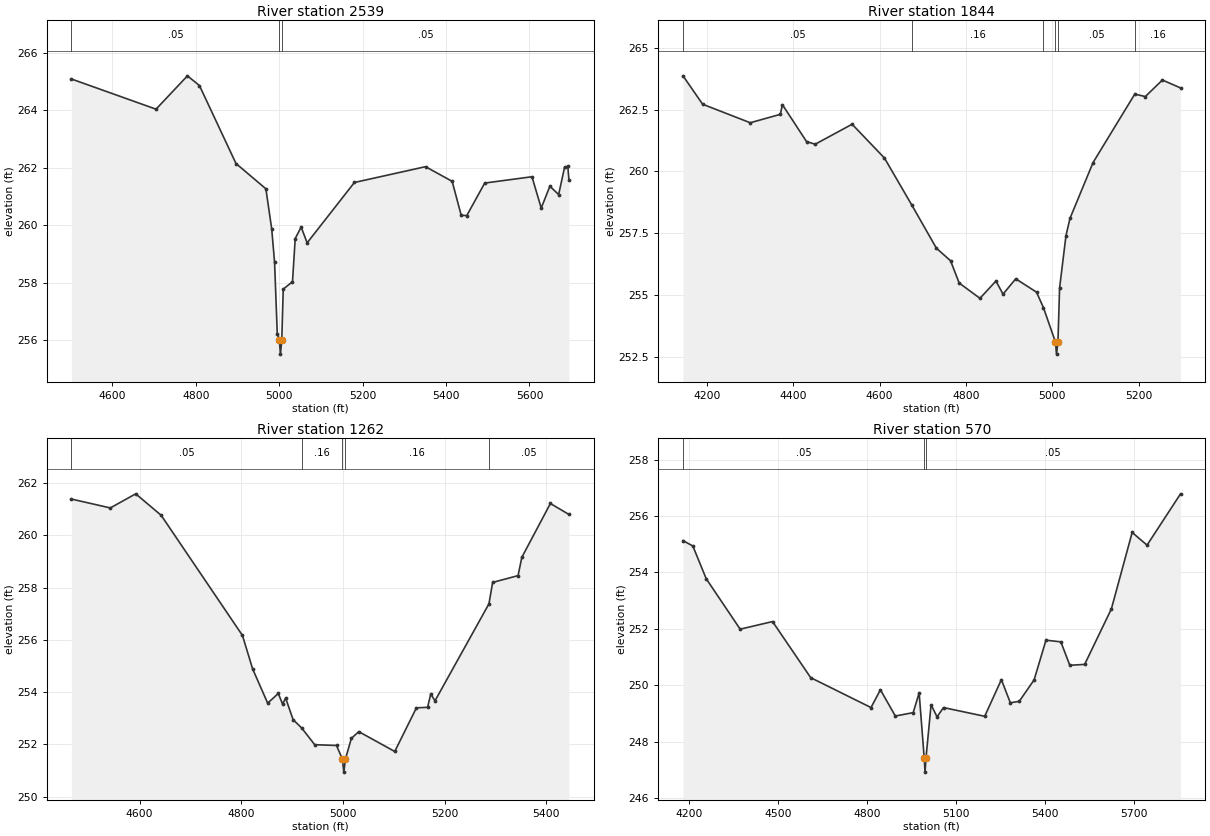
Type RM Length L Ch R = 1,2539,695,695,695
BEGIN DESCRIPTION:
UNT036 IN GIBB 4.0
END DESCRIPTION:
XS GIS Cut Line= 3
      3631440.29     10224093.73      3631135.44     10224228.12
      3630473.12     10224776.77
#Sta/Elev= 30
  4501.5  265.09  4704.4  264.04  4779.8  265.20  4808.6  264.86  4896.2  262.15
  4967.9  261.27  4981.8  259.88  4988.7  258.72  4995.2  256.23  5000.0  256.02
  5002.8  255.52  5006.0  256.02  5009.5  257.78  5031.7  258.04  5038.2  259.54
  5052.5  259.94  5066.8  259.39  5180.1  261.49  5350.8  262.04  5414.6  261.53
  5436.3  260.35  5449.7  260.34  5492.7  261.47  5606.0  261.69  5628.2  260.60
  5649.0  261.36  5670.0  261.07  5684.2  262.02  5692.0  262.05  5694.7  261.57
#Mann=3,-1,0
  4501.5    0.05       0  5000.0    0.03       0  5006.0    0.05       0
Bank Sta=5000,5006
Exp/Cntr=0.3,0.1

Type RM Length L Ch R = 1,1844,582,582,582
BEGIN DESCRIPTION:
UNT036 IN GIBB 3.0
END DESCRIPTION:
XS GIS Cut Line= 3
      3631367.37     10223812.49      3630749.31     10223850.68
      3630256.66     10224051.90
#Sta/Elev= 30
  4145.1  263.87  4190.5  262.72  4300.7  261.97  4370.2  262.31  4375.2  262.70
  4430.9  261.21  4451.0  261.10  4536.4  261.91  4611.3  260.54  4674.8  258.63
  4731.5  256.89  4764.3  256.38  4784.2  255.48  4832.3  254.86  4869.3  255.56
  4885.7  255.03  4915.1  255.65  4963.2  255.11  4979.3  254.48  5006.8  253.10
  5009.5  252.60  5012.8  253.10  5016.6  255.28  5031.4  257.40  5040.7  258.10
  5094.1  260.36  5190.6  263.13  5215.0  263.03  5254.5  263.70  5296.5  263.38
#Mann=6,-1,0
  4145.1    0.05       0  4674.8    0.16       0  4979.3    0.05       0
  5006.8    0.03       0  5012.8    0.05       0  5190.6    0.16       0
Bank Sta=5006.8,5012.8
Exp/Cntr=0.3,0.1

Type RM Length L Ch R = 1,1262,692,692,692
BEGIN DESCRIPTION:
UNT036 IN GIBB 2.0
END DESCRIPTION:
XS GIS Cut Line= 3
      3631148.57     10223374.99      3630780.56     10223374.99
      3630292.08     10223741.66
#Sta/Elev= 30
  4465.9  261.39  4542.4  261.05  4592.4  261.59  4642.4  260.77  4802.4  256.17
  4822.4  254.89  4852.0  253.58  4872.9  253.95  4881.2  253.55  4887.4  253.77
  4902.0  252.95  4918.9  252.63  4944.5  251.99  4987.4  251.96  4999.0  251.44
  5001.8  250.94  5005.0  251.44  5016.6  252.23  5031.2  252.49  5102.0  251.73
  5144.6  253.40  5166.6  253.42  5172.8  253.93  5181.2  253.67  5287.3  257.38
  5294.6  258.20  5344.6  258.46  5352.0  259.16  5408.2  261.22  5444.7  260.80
#Mann=5,-1,0
  4465.9    0.05       0  4918.9    0.16       0  4999.0    0.07       0
  5005.0    0.16       0  5287.3    0.05       0
Bank Sta=4999,5005
Exp/Cntr=0.3,0.1

Type RM Length L Ch R = 1,570,0,0,0
BEGIN DESCRIPTION:
UNT036 IN GIBB 1.0
END DESCRIPTION:
XS GIS Cut Line= 4
      3631197.19     10223145.81      3630659.03     10222999.99
      3630165.98     10223041.65      3630194.25     10223664.33
#Sta/Elev= 30
  4180.9  255.13  4214.0  254.94  4259.0  253.78  4373.4  251.99  4482.5  252.26
  4611.0  250.27  4814.1  249.21  4845.8  249.84  4896.0  248.91  4956.2  249.03
  4976.2  249.73  4993.3  247.42  4996.1  246.92  4999.3  247.42  5016.4  249.31
  5036.5  248.88  5058.3  249.21  5197.0  248.90  5253.2  250.20  5283.3  249.38
  5313.3  249.43  5363.4  250.19  5403.4  251.60  5453.5  251.54  5483.6  250.71
  5533.6  250.74  5623.7  252.71  5693.7  255.42  5743.8  254.97  5856.6  256.79
#Mann=3,-1,0
  4180.9    0.05       0  4993.3    0.03       0  4999.3    0.05       0
Bank Sta=4993.3,4999.3
Exp/Cntr=0.3,0.1

Chan Stop Cuts=-1