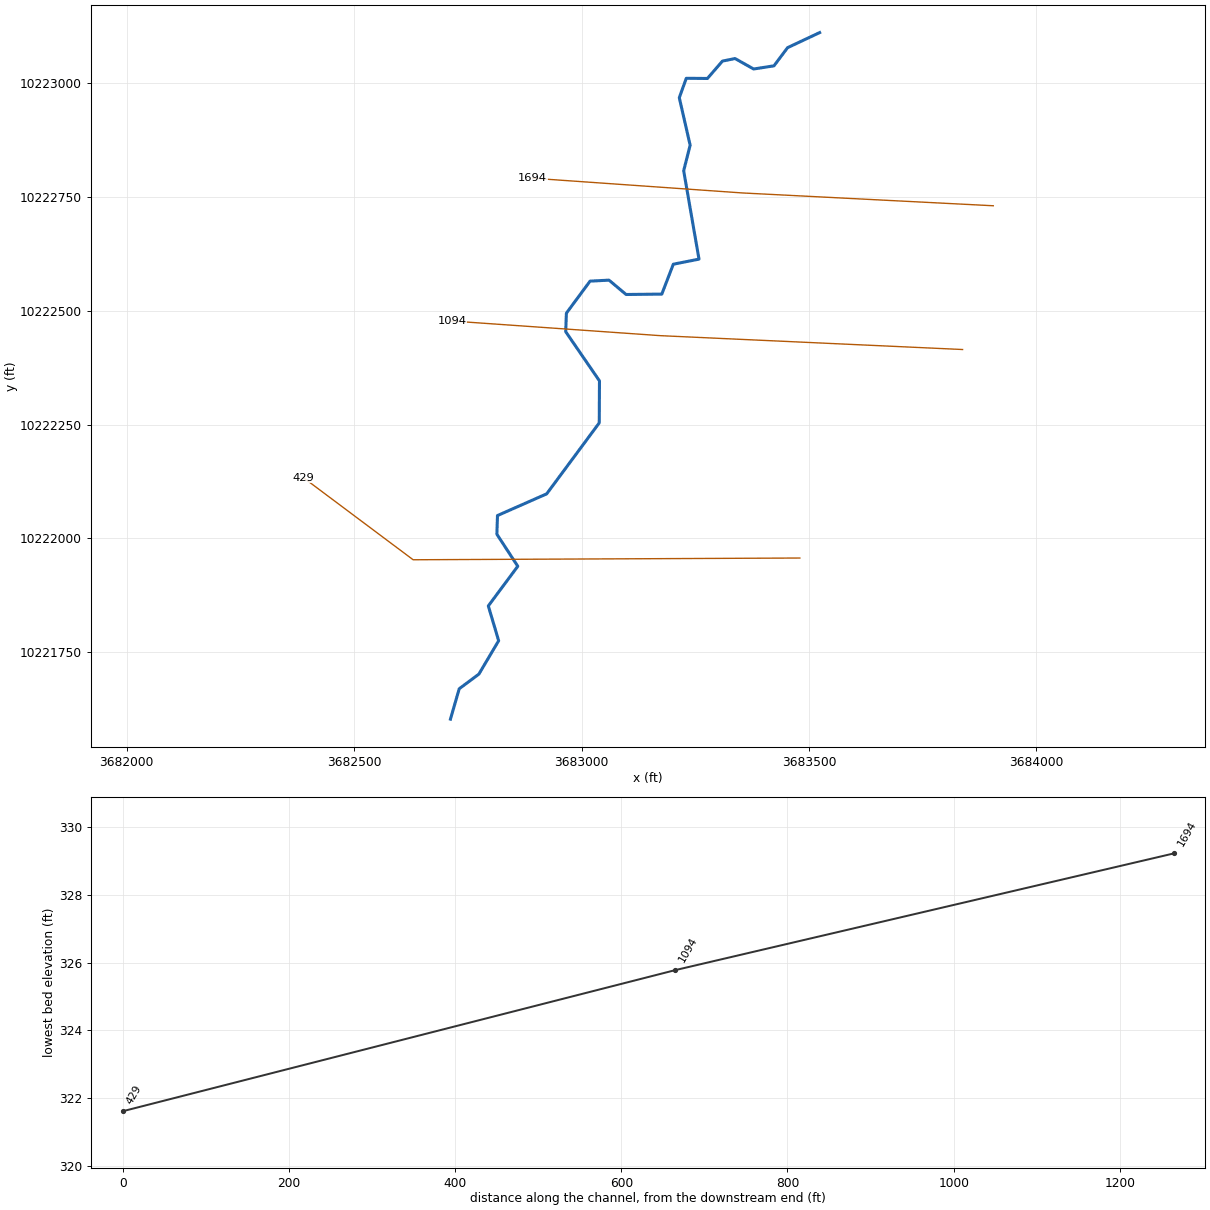
--- UNT038 IN GIBB.prj (project) ---

Proj Title=UNT038 IN GIBB Base Level Engineering
Current Plan=p01
Default Exp/Contr=0.3,0.1
English Units
Geom File=g01
Flow File=f01
Plan File=p01
BEGIN DESCRIPTION:
UNT038 IN GIBB
END DESCRIPTION:

--- UNT038 IN GIBB.p01 (plan) ---

Plan Title=Multiple Run
Short Identifier=Multiple
Geom File=g01
Flow File=f01
Subcritical Flow
K Sum by GR= 0
Std Step Tol= 0.01
Critical Tol= 0.01
Num of Std Step Trials= 20
Max Error Tol= 0.3
Flow Tol Ratio= 0.001
Split Flow NTrial= 30
Split Flow Tol= 0.02
Split Flow Ratio= 0.02
Log Output Level= 0
Friction Slope Method= 1
Unsteady Friction Slope Method= 2
Unsteady Bridges Friction Slope Method= 1
Parabolic Critical Depth
Global Vel Dist=  1 , 1 , 1
Global Log Level= 0
CheckData=True
Encroach Param= -1, 0, 0, 0
BEGIN DESCRIPTION:
Multiple Run
END DESCRIPTION:

--- UNT038 IN GIBB.f01 (steady flow) ---

Flow Title=Multiple
Number of Profiles=7
Profile Names=10-year,25-year,50-year,1pct_min,100-year,1pct_plu,500-year
River Rch & RM= UNT038 IN GIBB,Reach-1,1694
     508     675     810     714     965    1306    1368
Boundary for River Rch & Prof#=UNT038 IN GIBB,Reach-1,1
Up Type=0
Dn Type=3
Dn Slope=0.005
Boundary for River Rch & Prof#=UNT038 IN GIBB,Reach-1,2
Up Type=0
Dn Type=3
Dn Slope=0.005
Boundary for River Rch & Prof#=UNT038 IN GIBB,Reach-1,3
Up Type=0
Dn Type=3
Dn Slope=0.005
Boundary for River Rch & Prof#=UNT038 IN GIBB,Reach-1,4
Up Type=0
Dn Type=3
Dn Slope=0.005
Boundary for River Rch & Prof#=UNT038 IN GIBB,Reach-1,5
Up Type=0
Dn Type=3
Dn Slope=0.005
Boundary for River Rch & Prof#=UNT038 IN GIBB,Reach-1,6
Up Type=0
Dn Type=3
Dn Slope=0.005
Boundary for River Rch & Prof#=UNT038 IN GIBB,Reach-1,7
Up Type=0
Dn Type=3
Dn Slope=0.005

--- UNT038 IN GIBB.g01 (geometry) ---

Geom Title=Existing Conditions

River Reach=UNT038 IN GIBB,Reach-1
Reach XY= 30
      3683523.38     10223111.79      3683452.83     10223078.61
      3683422.88     10223038.68      3683378.18     10223031.73
      3683337.38     10223054.74      3683309.60     10223049.09
      3683276.62     10223010.90      3683230.18     10223011.33
      3683214.79     10222968.62      3683238.65     10222864.20
      3683224.44     10222808.07      3683258.11     10222613.74
      3683201.68     10222602.59      3683176.36     10222536.87
      3683097.86     10222536.02      3683060.27     10222567.57
      3683018.62     10222565.37      3682966.60     10222494.97
      3682965.07     10222454.24      3683039.32     10222346.10
      3683038.85     10222253.76      3682923.29     10222097.75
      3682815.12     10222050.06      3682813.78     10222008.97
      3682859.76     10221938.56      3682794.96     10221851.39
      3682817.69     10221774.86      3682774.24     10221701.46
      3682731.01     10221669.29      3682711.71     10221602.51

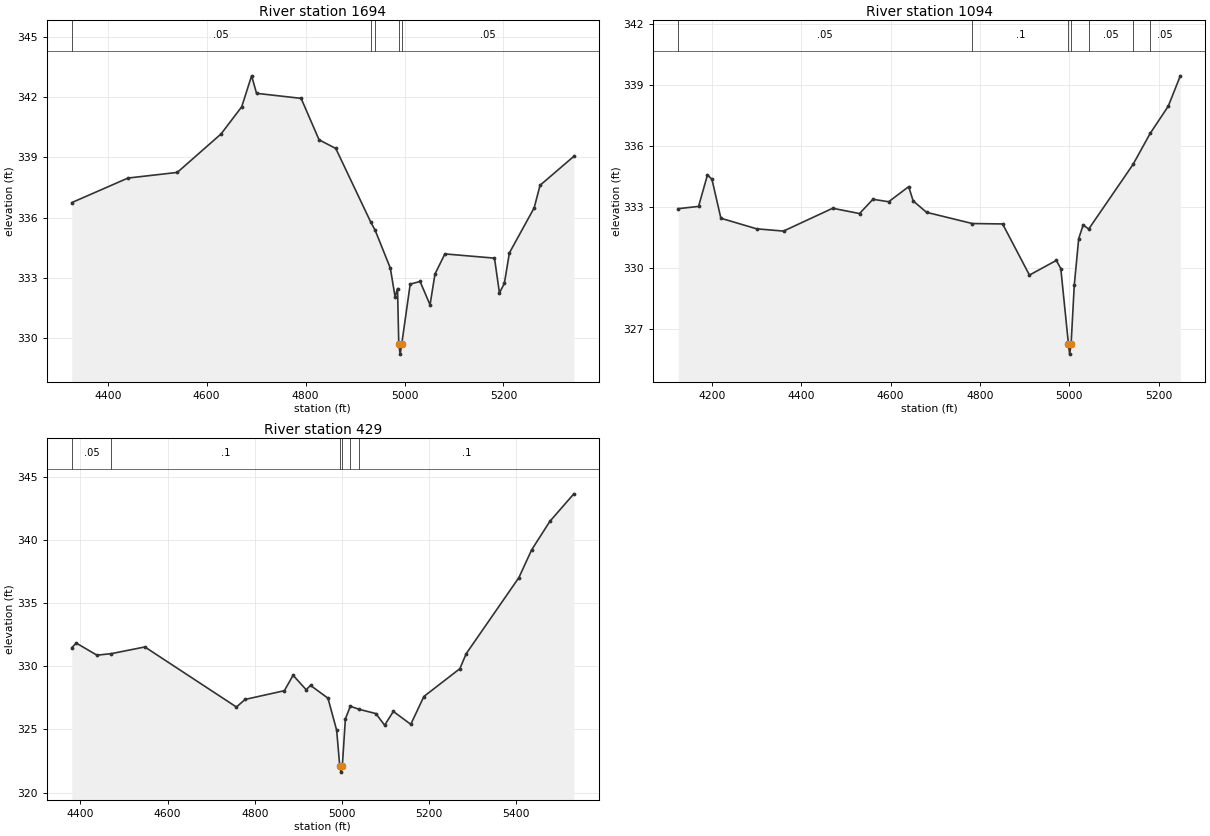
Type RM Length L Ch R = 1,1694,600,600,600
BEGIN DESCRIPTION:
UNT038 IN GIBB 2.0
END DESCRIPTION:
XS GIS Cut Line= 3
      3683905.14     10222731.08      3683352.44     10222759.32
      3682892.09     10222791.64
#Sta/Elev= 30
  4327.3  336.75  4440.9  337.97  4540.6  338.25  4629.0  340.16  4670.8  341.51
  4690.8  343.05  4700.8  342.18  4790.9  341.93  4827.2  339.87  4861.0  339.44
  4931.5  335.79  4940.5  335.38  4971.3  333.49  4980.8  332.07  4985.8  332.48
  4988.3  329.72  4991.1  329.22  4994.3  329.72  5011.4  332.70  5031.4  332.83
  5051.5  331.67  5061.5  333.20  5081.5  334.20  5181.8  333.99  5191.8  332.26
  5201.8  332.74  5211.9  334.25  5262.0  336.49  5273.9  337.61  5342.2  339.05
#Mann=5,-1,0
  4327.3    0.05       0  4931.5     0.1       0  4940.5    0.05       0
  4988.3   0.035       0  4994.3    0.05       0
Bank Sta=4988.3,4994.3
Exp/Cntr=0.3,0.1

Type RM Length L Ch R = 1,1094,665,665,665
BEGIN DESCRIPTION:
UNT038 IN GIBB 2.1
END DESCRIPTION:
XS GIS Cut Line= 3
      3683837.55     10222415.05      3683173.65     10222445.49
      3682715.18     10222477.68
#Sta/Elev= 30
  4124.5  332.92  4170.0  333.03  4190.0  334.58  4200.0  334.36  4220.0  332.45
  4300.1  331.93  4360.2  331.82  4470.3  332.94  4530.4  332.68  4560.4  333.38
  4595.7  333.26  4640.5  334.00  4650.5  333.30  4680.5  332.74  4783.0  332.19
  4850.8  332.17  4910.9  329.66  4971.1  330.38  4981.1  329.98  4998.2  326.28
  5000.9  325.78  5004.2  326.28  5011.2  329.15  5021.2  331.45  5031.2  332.12
  5043.6  331.92  5142.8  335.09  5181.1  336.61  5221.7  337.95  5248.7  339.44
#Mann=7,-1,0
  4124.5    0.05       0  4783.0     0.1       0  4998.2    0.07       0
  5004.2     0.1       0  5043.6    0.05       0  5142.8    0.08       0
  5181.1    0.05       0
Bank Sta=4998.2,5004.2
Exp/Cntr=0.3,0.1

Type RM Length L Ch R = 1,429,0,0,0
BEGIN DESCRIPTION:
UNT038 IN GIBB 1.0
END DESCRIPTION:
XS GIS Cut Line= 3
      3683479.84     10221956.68      3682629.69     10221952.87
      3682388.15     10222133.55
#Sta/Elev= 30
  4380.3  331.46  4390.5  331.83  4438.0  330.87  4470.9  330.99  4548.0  331.52
  4758.0  326.77  4778.0  327.37  4868.0  328.06  4888.0  329.28  4918.0  328.14
  4928.0  328.48  4968.0  327.47  4988.0  324.93  4995.0  322.12  4997.8  321.62
  5001.0  322.12  5008.0  325.83  5019.3  326.83  5040.3  326.58  5078.0  326.25
  5098.0  325.33  5118.0  326.42  5158.0  325.40  5188.0  327.60  5270.6  329.80
  5285.2  330.99  5406.1  337.01  5435.3  339.20  5477.2  341.46  5532.1  343.63
#Mann=6,-1,0
  4380.3    0.05       0  4470.9     0.1       0  4995.0    0.07       0
  5001.0     0.1       0  5019.3    0.05       0  5040.3     0.1       0
Bank Sta=4995,5001
Exp/Cntr=0.3,0.1

Chan Stop Cuts=-1