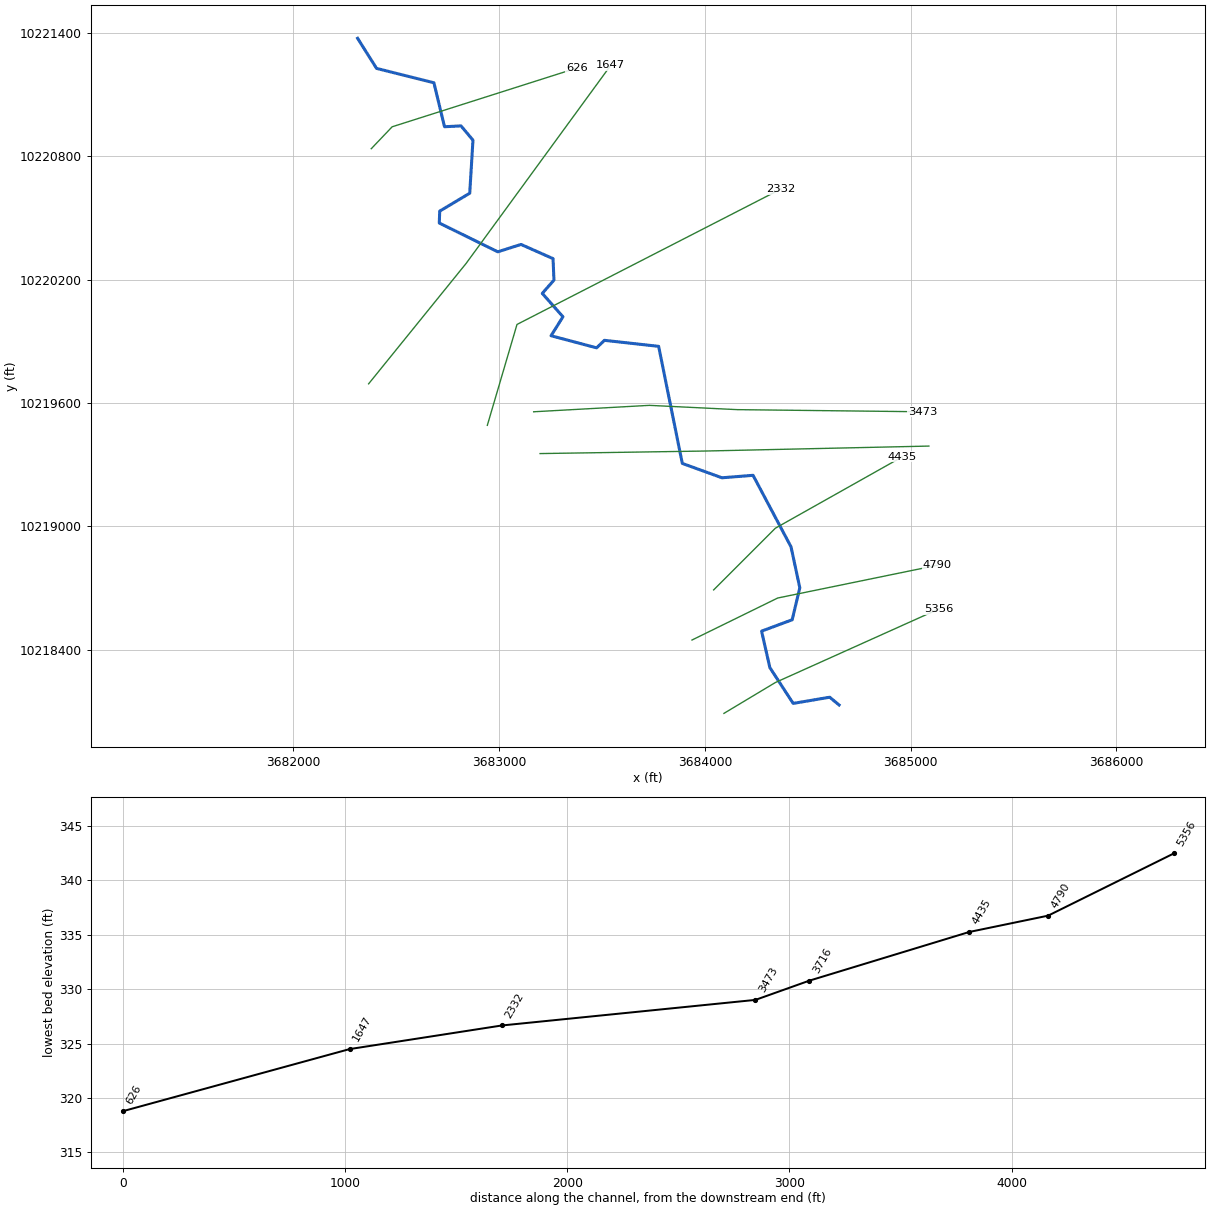
--- UNT039 IN GIBB.prj (project) ---

Proj Title=UNT039 IN GIBB Base Level Engineering
Current Plan=p01
Default Exp/Contr=0.3,0.1
English Units
Geom File=g01
Flow File=f01
Plan File=p01
Y Axis Title=Elevation
X Axis Title(PF)=Main Channel Distance
X Axis Title(XS)=Station
BEGIN DESCRIPTION:
UNT039 IN GIBB
END DESCRIPTION:
DSS Export Rating Curves= 0
DSS Export Rating Curve Sorted= 0
DSS Export Volume Flow Curves= 0
DXF OffsetX= 0
DXF OffsetY= 0
DXF ScaleX= 1
DXF ScaleY= 10

--- UNT039 IN GIBB.p01 (plan) ---

Plan Title=Multiple Run
Short Identifier=Multiple
Geom File=g01
Flow File=f01
Subcritical Flow
K Sum by GR= 0
Std Step Tol= 0.01
Critical Tol= 0.01
Num of Std Step Trials= 20
Max Error Tol= 0.3
Flow Tol Ratio= 0.001
Split Flow NTrial= 30
Split Flow Tol= 0.02
Split Flow Ratio= 0.02
Log Output Level= 0
Friction Slope Method= 1
Unsteady Friction Slope Method= 2
Unsteady Bridges Friction Slope Method= 1
Parabolic Critical Depth
Global Vel Dist=  1 , 1 , 1
Global Log Level= 0
CheckData=True
Encroach Param= -1, 0, 0, 0
BEGIN DESCRIPTION:
Multiple Run
END DESCRIPTION:

--- UNT039 IN GIBB.f01 (steady flow) ---

Flow Title=Multiple
Number of Profiles=7
Profile Names=10-year,25-year,50-year,1pct_min,100-year,1pct_plu,500-year
River Rch & RM= UNT039 IN GIBB,Reach-1,5356
     694     932    1125     995    1345    1819    1923
Boundary for River Rch & Prof#=UNT039 IN GIBB,Reach-1,1
Up Type=0
Dn Type=3
Dn Slope=0.005
Boundary for River Rch & Prof#=UNT039 IN GIBB,Reach-1,2
Up Type=0
Dn Type=3
Dn Slope=0.005
Boundary for River Rch & Prof#=UNT039 IN GIBB,Reach-1,3
Up Type=0
Dn Type=3
Dn Slope=0.005
Boundary for River Rch & Prof#=UNT039 IN GIBB,Reach-1,4
Up Type=0
Dn Type=3
Dn Slope=0.005
Boundary for River Rch & Prof#=UNT039 IN GIBB,Reach-1,5
Up Type=0
Dn Type=3
Dn Slope=0.005
Boundary for River Rch & Prof#=UNT039 IN GIBB,Reach-1,6
Up Type=0
Dn Type=3
Dn Slope=0.005
Boundary for River Rch & Prof#=UNT039 IN GIBB,Reach-1,7
Up Type=0
Dn Type=3
Dn Slope=0.005

--- UNT039 IN GIBB.g01 (geometry) ---

Geom Title=Existing Conditions
Program Version=4.10

River Reach=UNT039 IN GIBB  ,Reach-1
Reach XY= 30
      3684651.71     10218132.51      3684606.13      10218170.1
      3684428.52     10218140.13      3684315.33       10218314.
      3684275.02     10218491.29      3684423.81     10218546.62
      3684460.79     10218701.91      3684418.16       10218901.
      3684233.57     10219248.65      3684082.54     10219236.64
      3683889.74     10219306.47      3683774.74     10219875.52
       3683511.2     10219904.69      3683473.18     10219868.23
      3683251.83     10219927.09      3683309.64     10220019.27
      3683209.12     10220132.82      3683265.89      10220197.4
      3683261.49     10220301.78      3683105.87     10220370.79
      3682993.03     10220334.91      3682708.51     10220474.89
      3682710.76     10220532.71      3682856.56     10220619.77
       3682872.3     10220877.72      3682814.21     10220946.91
      3682734.02     10220942.82      3682682.48     10221156.52
      3682403.69      10221226.4      3682311.71     10221372.51

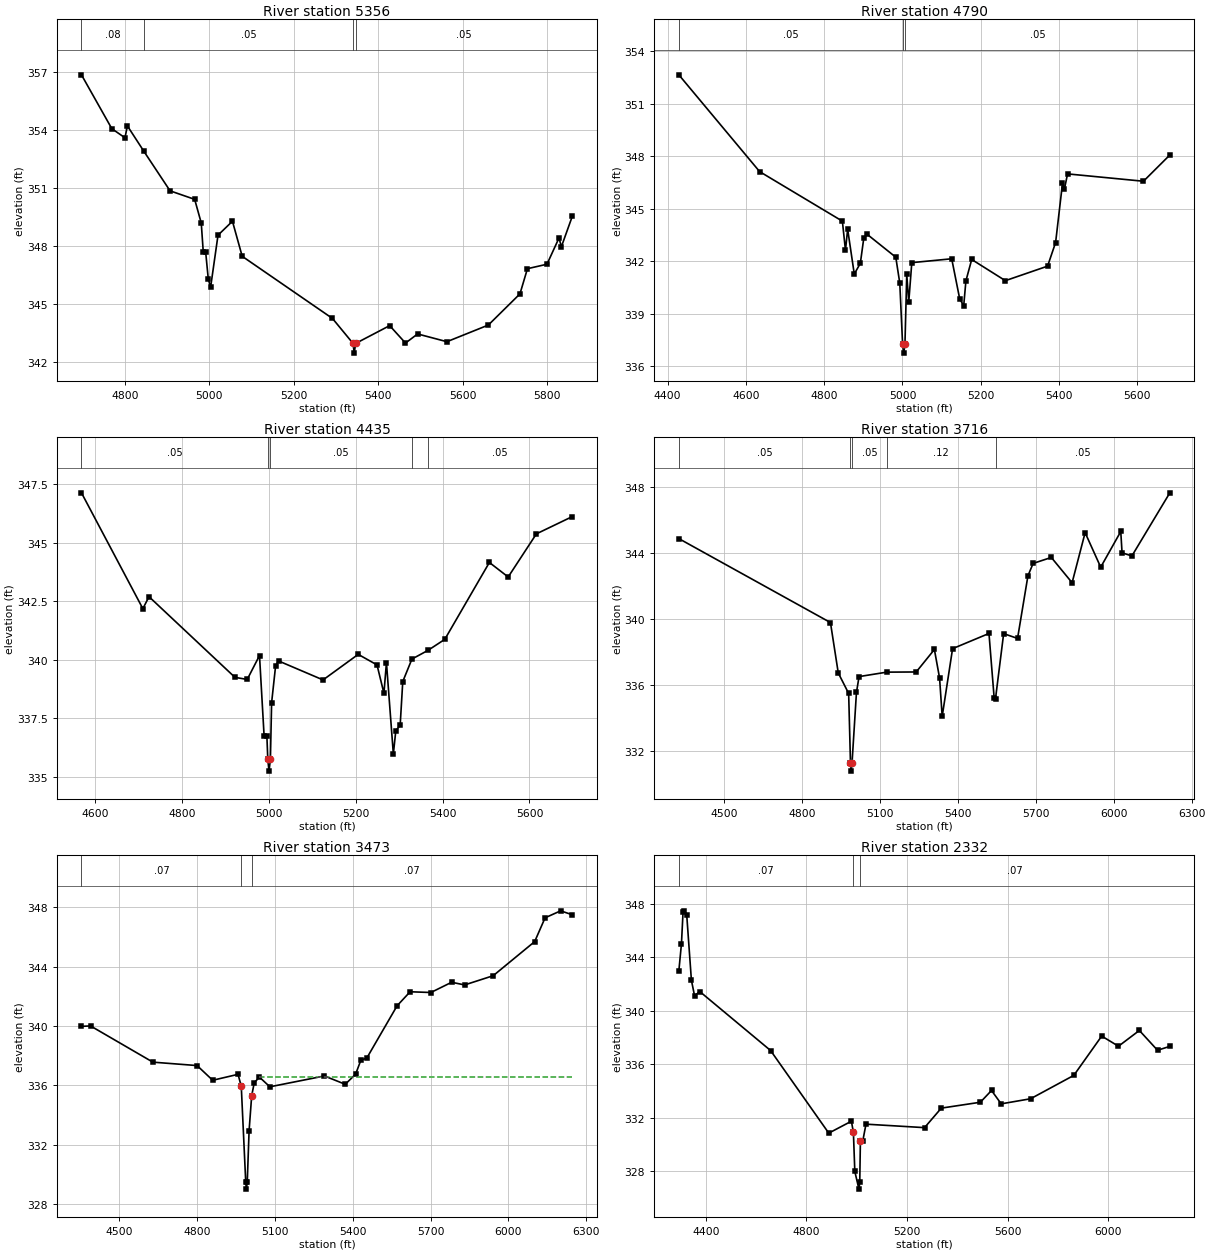
Type RM Length L Ch R = 1 ,5356    ,566,566,566
BEGIN DESCRIPTION:
UNT039 IN GIBB 10.0
END DESCRIPTION:
XS GIS Cut Line= 3
       3684092.1     10218091.64      3684342.11     10218241.64
      3685137.14     10218599.21
#Sta/Elev= 30
  4697.2  356.84  4769.1  354.06  4800.2  353.59  4806.1   354.2  4844.5  352.91
  4907.1  350.85  4965.4  350.41    4981  349.19  4985.8  347.68  4991.5  347.68
  4997.6  346.31  5003.1  345.86  5020.7  348.56  5054.9  349.28    5078  347.47
  5291.9  344.26  5340.7  342.97  5343.4  342.47  5346.7  342.97  5427.4  343.89
  5464.9  342.99  5493.6  343.46    5563  343.06  5661.2  343.92  5736.1  345.53
  5753.8  346.83  5800.1  347.06  5828.7  348.42  5834.2  347.96  5860.5  349.56
#Mann= 4 ,-1 , 0
  4697.2     .08       0  4844.5     .05       0  5340.7     .03       0
  5346.7     .05       0
Bank Sta=5340.7,5346.7
XS Rating Curve= 0 ,0
Exp/Cntr=0.3,0.1

Type RM Length L Ch R = 1 ,4790    ,355,355,355
BEGIN DESCRIPTION:
UNT039 IN GIBB 9.0
END DESCRIPTION:
XS GIS Cut Line= 3
      3683936.88     10218448.15      3684353.32     10218652.28
      3685128.08     10218811.31
#Sta/Elev= 30
  4428.5  352.65    4635  347.12  4846.4  344.29  4854.3  342.63  4859.9  343.83
  4876.8  341.27  4892.3  341.88  4901.3  343.35  4910.2  343.53  4982.9  342.23
  4993.1  340.75  5000.3  337.25  5003.1  336.75  5006.3  337.25  5010.9  341.25
    5016  339.66  5023.8  341.92  5125.8  342.14  5146.3  339.84  5156.5  339.47
  5162.1  340.88  5176.9   342.1  5262.9  340.89  5370.8  341.72  5391.3  343.07
  5408.9  346.45    5414  346.15  5421.9  346.99  5615.8  346.57  5683.2  348.07
#Mann= 3 ,-1 , 0
  4428.5     .05       0  5000.3     .03       0  5006.3     .05       0
Bank Sta=5000.3,5006.3
XS Rating Curve= 0 ,0
Exp/Cntr=0.3,0.1

Type RM Length L Ch R = 1 ,4435    ,719,719,719
BEGIN DESCRIPTION:
UNT039 IN GIBB 8.0
END DESCRIPTION:
XS GIS Cut Line= 3
      3684042.11     10218691.65      3684342.11     10218991.64
      3684958.05      10219338.2
#Sta/Elev= 30
  4568.1  347.12  4709.5  342.18  4723.7  342.69  4921.6  339.25  4949.9  339.16
  4978.2  340.18  4988.8  336.75  4995.2  336.75  4997.3  335.75  5000.1  335.25
  5003.3  335.75  5006.1  338.17  5015.3  339.74    5022  339.95  5124.6  339.14
  5205.6  340.23  5248.9  339.78  5264.8  338.57  5270.6  339.88  5286.5  335.98
  5292.2  336.98  5302.2   337.2  5308.2  339.07  5329.3  340.03  5366.2   340.4
    5405  340.87  5507.7  344.15    5551  343.53    5616  345.37  5699.1  346.11
#Mann= 5 ,-1 , 0
  4568.1     .05       0  4997.3     .03       0  5003.3     .05       0
  5329.3     .12       0  5366.2     .05       0
Bank Sta=4997.3,5003.3
XS Rating Curve= 0 ,0
Exp/Cntr=0.3,0.1

Type RM Length L Ch R = 1 ,3716    ,243,243,243
BEGIN DESCRIPTION:
UNT039 IN GIBB 7.0
END DESCRIPTION:
XS GIS Cut Line= 3
      3683198.53     10219354.34      3684002.22     10219366.72
      3685088.16     10219390.78
#Sta/Elev= 30
    4326  344.85  4909.6  339.77  4939.7  336.72  4979.7  335.48  4986.7  331.28
  4989.4  330.78  4992.7  331.28  5009.7  335.54  5019.7   336.5  5126.5  336.77
  5239.7  336.78  5309.7  338.14  5329.7  336.41  5339.7  334.09  5379.7  338.19
  5519.8  339.11  5539.8   335.2    5545  335.17  5576.3   339.1  5629.8  338.81
  5669.8   342.6  5689.8  343.35  5759.8  343.71  5839.8  342.18  5889.9  345.21
  5949.9  343.12  6027.1  345.28  6032.1  343.99  6069.9   343.8    6216  347.62
#Mann= 5 ,-1 , 0
    4326     .05       0  4986.7     .03       0  4992.7     .05       0
  5126.5     .12       0    5545     .05       0
Bank Sta=4986.7,4992.7
XS Rating Curve= 0 ,0
Exp/Cntr=0.3,0.1

Type RM Length L Ch R = 1 ,3473    ,1141,1141,1141
BEGIN DESCRIPTION:
UNT039 IN GIBB 5.0
END DESCRIPTION:
XS GIS Cut Line= 4
      3683167.29     10219557.47       3683729.8     10219588.72
      3684156.88     10219567.88      3685057.56     10219557.47
#Sta/Elev= 30
  4354.9  339.97  4389.8     340  4630.1  337.56  4800.4  337.33  4860.5  336.34
  4958.2  336.74  4970.6  335.93  4987.7  329.51  4990.4  329.01  4993.7  329.51
  5000.7  332.94  5010.7   335.3  5020.7  336.18  5040.7  336.55  5080.8   335.9
    5291  336.63  5371.1  336.07  5411.1  336.75  5431.1  337.68  5454.7  337.85
  5571.1  341.36  5621.1   342.3  5701.1  342.25  5781.1  342.94  5831.1  342.76
  5941.1  343.38  6101.1  345.68  6141.1  347.28  6201.1  347.75  6246.6  347.48
#Mann= 3 , 0 , 0
  4354.9     .07       0  4970.6     .05       0  5010.7     .07       0
#XS Ineff= 2 , 0
                          5040.4          336.57
Permanent Ineff=
       F       F
Bank Sta=4970.6,5010.7
XS Rating Curve= 0 ,0
Exp/Cntr=0.3,0.1

Type RM Length L Ch R = 1 ,2332    ,685,685,685
BEGIN DESCRIPTION:
UNT039 IN GIBB 4.0
END DESCRIPTION:
XS GIS Cut Line= 3
       3682942.1     10219491.64       3683086.3     10219981.91
      3684368.79     10220639.96
#Sta/Elev= 30
  4292.6  342.98    4303  345.01  4309.3  347.38  4314.5  347.48  4323.9  347.19
  4342.6  342.28  4355.1  341.13    4376  341.44  4657.4  337.03  4888.8  330.85
  4978.8  331.74  4986.8   330.9  4992.4  327.98  5008.8  326.66    5012  327.16
  5014.6  330.25  5023.7  330.23  5036.8  331.52  5269.7  331.26  5336.3  332.72
  5491.6  333.16    5536  334.04  5574.5  333.04  5691.3  333.42  5863.3  335.17
  5974.2  338.11  6040.8  337.35  6123.9  338.53  6196.1  337.05  6245.1  337.34
#Mann= 3 , 0 , 0
  4292.6     .07       0  4986.8     .05       0  5014.6     .07       0
Bank Sta=4986.8,5014.6
XS Rating Curve= 0 ,0
Exp/Cntr=0.3,0.1

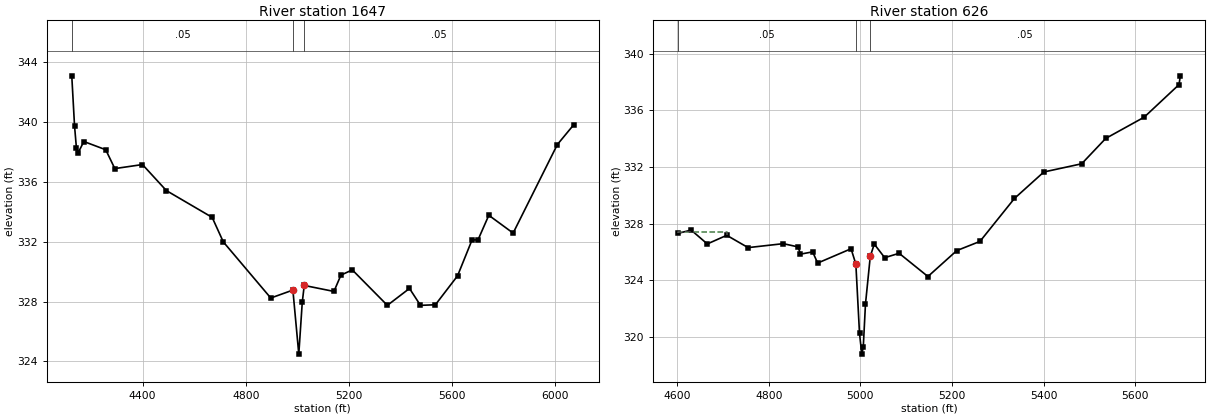
Type RM Length L Ch R = 1 ,1647    ,1021,1021,1021
BEGIN DESCRIPTION:
UNT039 IN GIBB 3.0
END DESCRIPTION:
XS GIS Cut Line= 3
      3682365.15     10219693.32      3682839.64     10220279.32
      3683542.13     10221241.68
#Sta/Elev= 30
  4125.7  343.09  4136.4  339.75  4143.8  338.25  4150.2  337.94  4172.5   338.7
  4257.3  338.15  4292.5  336.89  4399.6  337.16  4492.3  335.42  4669.7  333.63
  4712.9  331.99  4896.8  328.24  4982.5  328.77  5005.4  324.49  5018.8  327.95
  5026.5  329.08  5141.6  328.68  5168.6  329.77  5212.7  330.12  5348.6  327.75
  5434.3  328.88  5476.9  327.75  5534.7  327.79  5620.5  329.72  5676.9  332.13
  5699.7  332.12  5741.7  333.77  5835.9  332.58  6007.4   338.5  6071.2  339.83
#Mann= 3 , 0 , 0
  4125.7     .05       0  4982.5     .03       0  5026.5     .05       0
Bank Sta=4982.5,5026.5
XS Rating Curve= 0 ,0
Exp/Cntr=0.3,0.1

Type RM Length L Ch R = 1 ,626     ,0,0,0
BEGIN DESCRIPTION:
UNT039 IN GIBB 1.0
END DESCRIPTION:
XS GIS Cut Line= 3
        3682378.       10220836.      3682479.46     10220942.55
      3683377.33     10221228.24
#Sta/Elev= 30
  4602.2  327.31  4630.4  327.54  4665.7  326.56  4708.1  327.17  4754.8   326.3
  4831.7  326.58  4863.9  326.35  4869.2  325.84  4895.7     326  4906.7  325.21
  4979.6  326.22  4990.1  325.14  4998.1  320.24  5003.1  318.78  5006.3  319.28
  5011.1  322.31  5021.6  325.68  5030.3  326.55  5053.1  325.59  5084.6   325.9
  5147.5  324.26  5210.5  326.09  5261.2  326.74  5336.4  329.77  5400.6  331.64
  5483.3  332.22  5535.8  334.01  5619.8  335.51  5695.9  337.81  5698.7  338.43
#Mann= 3 , 0 , 0
  4602.2     .05       0  4990.1     .03       0  5021.6     .05       0
#XS Ineff= 2 , 0
         4708.68   327.4
Permanent Ineff=
       F       F
Bank Sta=4990.1,5021.6
XS Rating Curve= 0 ,0
Exp/Cntr=0.3,0.1

Chan Stop Cuts=-1
Use User Specified Reach Order=0
Composite Channel Slope=5