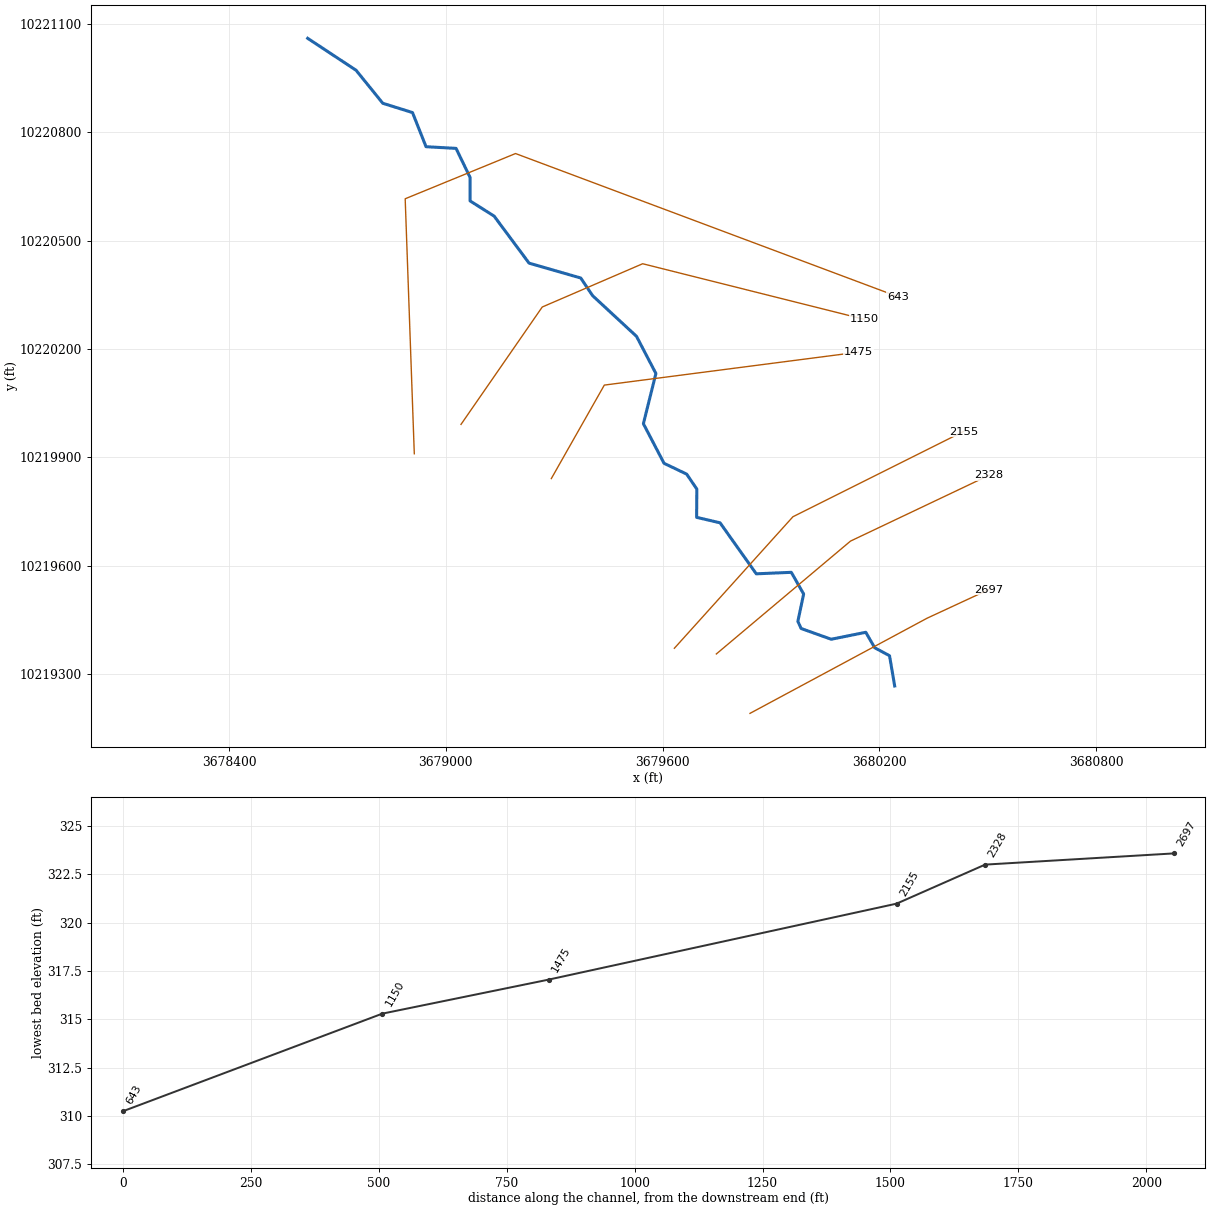
--- UNT040 IN GIBB.prj (project) ---

Proj Title=UNT040 IN GIBB Base Level Engineering
Current Plan=p01
Default Exp/Contr=0.3,0.1
English Units
Geom File=g01
Flow File=f01
Plan File=p01
BEGIN DESCRIPTION:
UNT040 IN GIBB
END DESCRIPTION:

--- UNT040 IN GIBB.p01 (plan) ---

Plan Title=Multiple Run
Short Identifier=Multiple
Geom File=g01
Flow File=f01
Subcritical Flow
K Sum by GR= 0
Std Step Tol= 0.01
Critical Tol= 0.01
Num of Std Step Trials= 20
Max Error Tol= 0.3
Flow Tol Ratio= 0.001
Split Flow NTrial= 30
Split Flow Tol= 0.02
Split Flow Ratio= 0.02
Log Output Level= 0
Friction Slope Method= 1
Unsteady Friction Slope Method= 2
Unsteady Bridges Friction Slope Method= 1
Parabolic Critical Depth
Global Vel Dist=  1 , 1 , 1
Global Log Level= 0
CheckData=True
Encroach Param= -1, 0, 0, 0
BEGIN DESCRIPTION:
Multiple Run
END DESCRIPTION:

--- UNT040 IN GIBB.f01 (steady flow) ---

Flow Title=Multiple
Number of Profiles=7
Profile Names=10-year,25-year,50-year,1pct_min,100-year,1pct_plu,500-year
River Rch & RM= UNT040 IN GIBB,Reach-1,2697
     385     502     594     517     699     945     965
Boundary for River Rch & Prof#=UNT040 IN GIBB,Reach-1,1
Up Type=0
Dn Type=3
Dn Slope=0.005
Boundary for River Rch & Prof#=UNT040 IN GIBB,Reach-1,2
Up Type=0
Dn Type=3
Dn Slope=0.005
Boundary for River Rch & Prof#=UNT040 IN GIBB,Reach-1,3
Up Type=0
Dn Type=3
Dn Slope=0.005
Boundary for River Rch & Prof#=UNT040 IN GIBB,Reach-1,4
Up Type=0
Dn Type=3
Dn Slope=0.005
Boundary for River Rch & Prof#=UNT040 IN GIBB,Reach-1,5
Up Type=0
Dn Type=3
Dn Slope=0.005
Boundary for River Rch & Prof#=UNT040 IN GIBB,Reach-1,6
Up Type=0
Dn Type=3
Dn Slope=0.005
Boundary for River Rch & Prof#=UNT040 IN GIBB,Reach-1,7
Up Type=0
Dn Type=3
Dn Slope=0.005

--- UNT040 IN GIBB.g01 (geometry) ---

Geom Title=Existing Conditions

River Reach=UNT040 IN GIBB,Reach-1
Reach XY= 30
      3680242.64     10219267.51      3680228.39     10219351.22
      3680187.24     10219373.42      3680162.68     10219416.10
      3680066.93     10219396.85      3679983.66     10219426.61
      3679974.61     10219446.39      3679990.64     10219522.05
      3679956.43     10219582.10      3679859.48     10219577.99
      3679759.23     10219719.20      3679694.38     10219734.29
      3679694.89     10219812.57      3679666.80     10219853.99
      3679604.17     10219883.90      3679546.99     10219993.49
      3679581.64     10220132.49      3679527.94     10220235.40
      3679406.40     10220347.97      3679373.56     10220396.87
      3679230.52     10220438.03      3679133.72     10220568.26
      3679067.34     10220610.21      3679067.16     10220675.53
      3679028.33     10220755.76      3678945.27     10220760.33
      3678907.79     10220854.89      3678825.60     10220880.59
      3678751.58     10220972.00      3678617.66     10221060.37

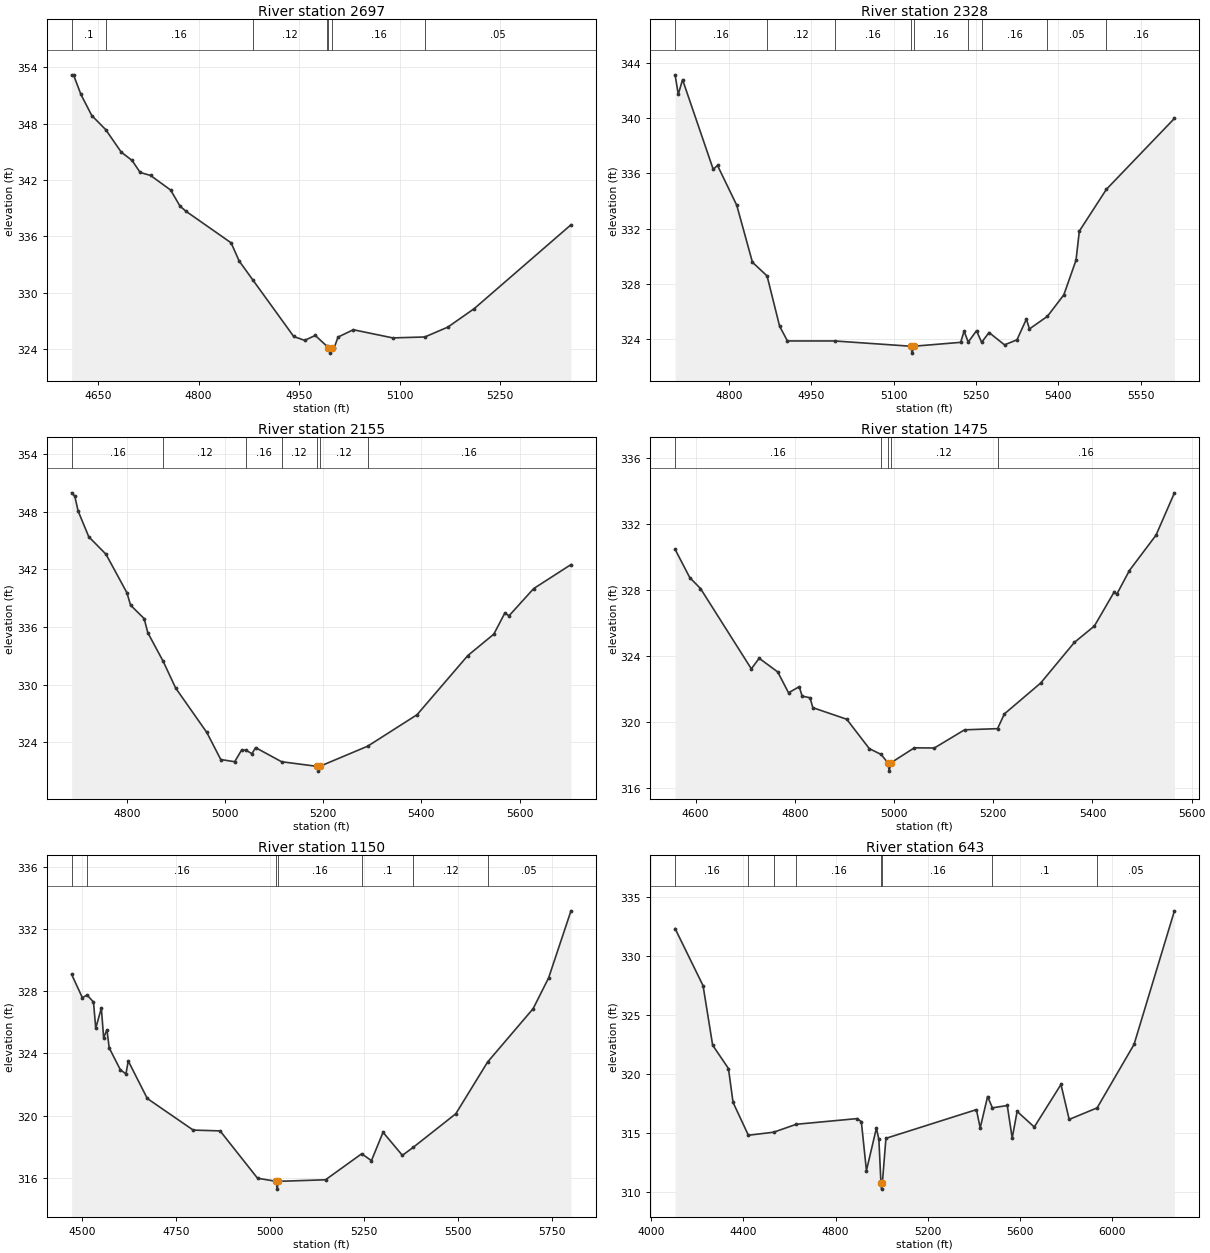
Type RM Length L Ch R = 1,2697,369,369,369
BEGIN DESCRIPTION:
UNT040 IN GIBB 5.0
END DESCRIPTION:
XS GIS Cut Line= 3
      3679842.10     10219191.64      3680332.23     10219455.04
      3680502.94     10219534.21
#Sta/Elev= 30
  4610.8  353.20  4613.6  353.20  4624.6  351.12  4640.8  348.87  4661.7  347.36
  4684.7  344.98  4700.9  344.09  4713.0  342.81  4728.5  342.49  4758.4  340.94
  4772.3  339.24  4781.1  338.69  4848.6  335.32  4860.6  333.39  4881.2  331.35
  4942.0  325.35  4958.2  324.94  4974.1  325.46  4991.0  324.35  4993.4  324.08
  4996.1  323.58  4999.4  324.08  5002.0  324.10  5008.1  325.29  5030.8  326.07
  5089.7  325.20  5137.5  325.30  5171.8  326.35  5211.2  328.32  5355.4  337.24
#Mann=7,-1,0
  4610.8     0.1       0  4661.7    0.16       0  4881.2    0.12       0
  4991.0    0.16       0  4993.4    0.07       0  4999.4    0.16       0
  5137.5    0.05       0
Bank Sta=4993.4,4999.4
Exp/Cntr=0.3,0.1

Type RM Length L Ch R = 1,2328,173,173,173
BEGIN DESCRIPTION:
UNT040 IN GIBB 5.1
END DESCRIPTION:
XS GIS Cut Line= 3
      3679748.91     10219356.09      3680120.29     10219668.53
      3680504.14     10219850.89
#Sta/Elev= 30
  4701.5  343.12  4707.3  341.71  4715.1  342.77  4771.0  336.29  4778.8  336.57
  4813.9  333.69  4842.5  329.57  4869.2  328.58  4892.0  324.95  4906.3  323.88
  4992.3  323.88  5130.8  323.50  5133.6  323.00  5136.8  323.50  5222.1  323.78
  5228.3  324.59  5235.9  323.80  5251.0  324.62  5260.3  323.78  5273.8  324.49
  5302.0  323.60  5324.7  323.96  5341.9  325.46  5347.5  324.75  5380.2  325.66
  5410.1  327.21  5432.4  329.72  5438.4  331.82  5487.7  334.84  5611.8  339.97
#Mann=9,-1,0
  4701.5    0.16       0  4869.2    0.12       0  4992.3    0.16       0
  5130.8    0.07       0  5136.8    0.16       0  5235.9    0.05       0
  5260.3    0.16       0  5380.2    0.05       0  5487.7    0.16       0
Bank Sta=5130.8,5136.8
Exp/Cntr=0.3,0.1

Type RM Length L Ch R = 1,2155,680,680,680
BEGIN DESCRIPTION:
UNT040 IN GIBB 4.0
END DESCRIPTION:
XS GIS Cut Line= 3
      3679632.75     10219371.88      3679960.93     10219735.95
      3680432.69     10219971.83
#Sta/Elev= 30
  4687.3  349.99  4693.8  349.63  4700.5  348.10  4722.2  345.41  4757.3  343.59
  4799.9  339.58  4807.4  338.28  4835.1  336.88  4842.5  335.41  4874.0  332.41
  4899.3  329.64  4962.8  325.01  4991.2  322.19  5019.6  321.96  5033.8  323.19
  5042.5  323.16  5054.7  322.80  5062.2  323.43  5115.1  321.96  5186.9  321.48
  5189.7  320.98  5192.9  321.48  5290.6  323.58  5391.2  326.86  5494.7  333.03
  5547.7  335.26  5570.1  337.46  5578.6  337.17  5628.9  340.01  5704.9  342.51
#Mann=7,-1,0
  4687.3    0.16       0  4874.0    0.12       0  5042.5    0.16       0
  5115.1    0.12       0  5186.9    0.07       0  5192.9    0.12       0
  5290.6    0.16       0
Bank Sta=5186.9,5192.9
Exp/Cntr=0.3,0.1

Type RM Length L Ch R = 1,1475,325,325,325
BEGIN DESCRIPTION:
UNT040 IN GIBB 3.0
END DESCRIPTION:
XS GIS Cut Line= 3
      3679292.09     10219841.61      3679438.84     10220100.44
      3680142.12     10220191.64
#Sta/Elev= 30
  4558.6  330.47  4588.2  328.76  4609.8  328.10  4712.3  323.24  4728.1  323.88
  4765.6  323.05  4787.3  321.79  4808.9  322.16  4814.7  321.59  4830.6  321.49
  4836.3  320.89  4904.6  320.19  4950.2  318.41  4974.0  318.06  4987.5  317.55
  4990.3  317.05  4993.5  317.55  5040.9  318.46  5081.3  318.45  5142.2  319.55
  5208.7  319.62  5222.4  320.51  5295.6  322.38  5363.6  324.84  5403.9  325.83
  5444.0  327.90  5449.0  327.75  5474.5  329.19  5528.2  331.33  5565.3  333.89
#Mann=5,-1,0
  4558.6    0.16       0  4974.0    0.12       0  4987.5    0.07       0
  4993.5    0.12       0  5208.7    0.16       0
Bank Sta=4987.5,4993.5
Exp/Cntr=0.3,0.1

Type RM Length L Ch R = 1,1150,507,507,507
BEGIN DESCRIPTION:
UNT040 IN GIBB 2.0
END DESCRIPTION:
XS GIS Cut Line= 4
      3679042.08     10219991.61      3679266.96     10220316.58
      3679544.98     10220436.39      3680157.38     10220282.78
#Sta/Elev= 30
  4471.4  329.08  4499.8  327.59  4512.8  327.75  4529.6  327.30  4535.6  325.62
  4550.5  326.92  4556.6  325.01  4565.4  325.52  4571.4  324.36  4601.2  322.95
  4616.0  322.69  4622.1  323.52  4672.8  321.11  4795.1  319.08  4866.6  319.03
  4966.3  315.99  5015.8  315.79  5018.5  315.29  5021.8  315.79  5147.3  315.89
  5243.5  317.56  5269.5  317.12  5300.4  318.94  5351.9  317.46  5380.6  317.97
  5494.1  320.13  5578.7  323.45  5700.0  326.88  5741.1  328.85  5800.7  333.16
#Mann=7,-1,0
  4471.4    0.05       0  4512.8    0.16       0  5015.8    0.07       0
  5021.8    0.16       0  5243.5     0.1       0  5380.6    0.12       0
  5578.7    0.05       0
Bank Sta=5015.8,5021.8
Exp/Cntr=0.3,0.1

Type RM Length L Ch R = 1,643,0,0,0
BEGIN DESCRIPTION:
UNT040 IN GIBB 1.0
END DESCRIPTION:
XS GIS Cut Line= 4
      3678912.80     10219910.29      3678887.55     10220616.20
      3679193.08     10220741.45      3680251.37     10220345.22
#Sta/Elev= 30
  4103.7  332.30  4225.1  327.46  4266.6  322.43  4335.2  320.45  4355.2  317.58
  4421.7  314.80  4531.4  315.06  4629.6  315.73  4893.2  316.21  4911.8  315.95
  4933.9  311.81  4977.1  315.40  4987.9  314.45  4996.9  310.74  4999.7  310.24
  5002.9  310.74  5018.5  314.54  5411.1  316.97  5427.5  315.42  5459.6  318.08
  5480.5  317.12  5545.0  317.32  5566.3  314.56  5587.7  316.82  5662.2  315.50
  5778.0  319.10  5813.6  316.14  5934.8  317.12  6095.0  322.49  6270.3  333.80
#Mann=8,-1,0
  4103.7    0.16       0  4421.7     0.1       0  4531.4    0.05       0
  4629.6    0.16       0  4996.9    0.07       0  5002.9    0.16       0
  5480.5     0.1       0  5934.8    0.05       0
Bank Sta=4996.9,5002.9
Exp/Cntr=0.3,0.1

Chan Stop Cuts=-1