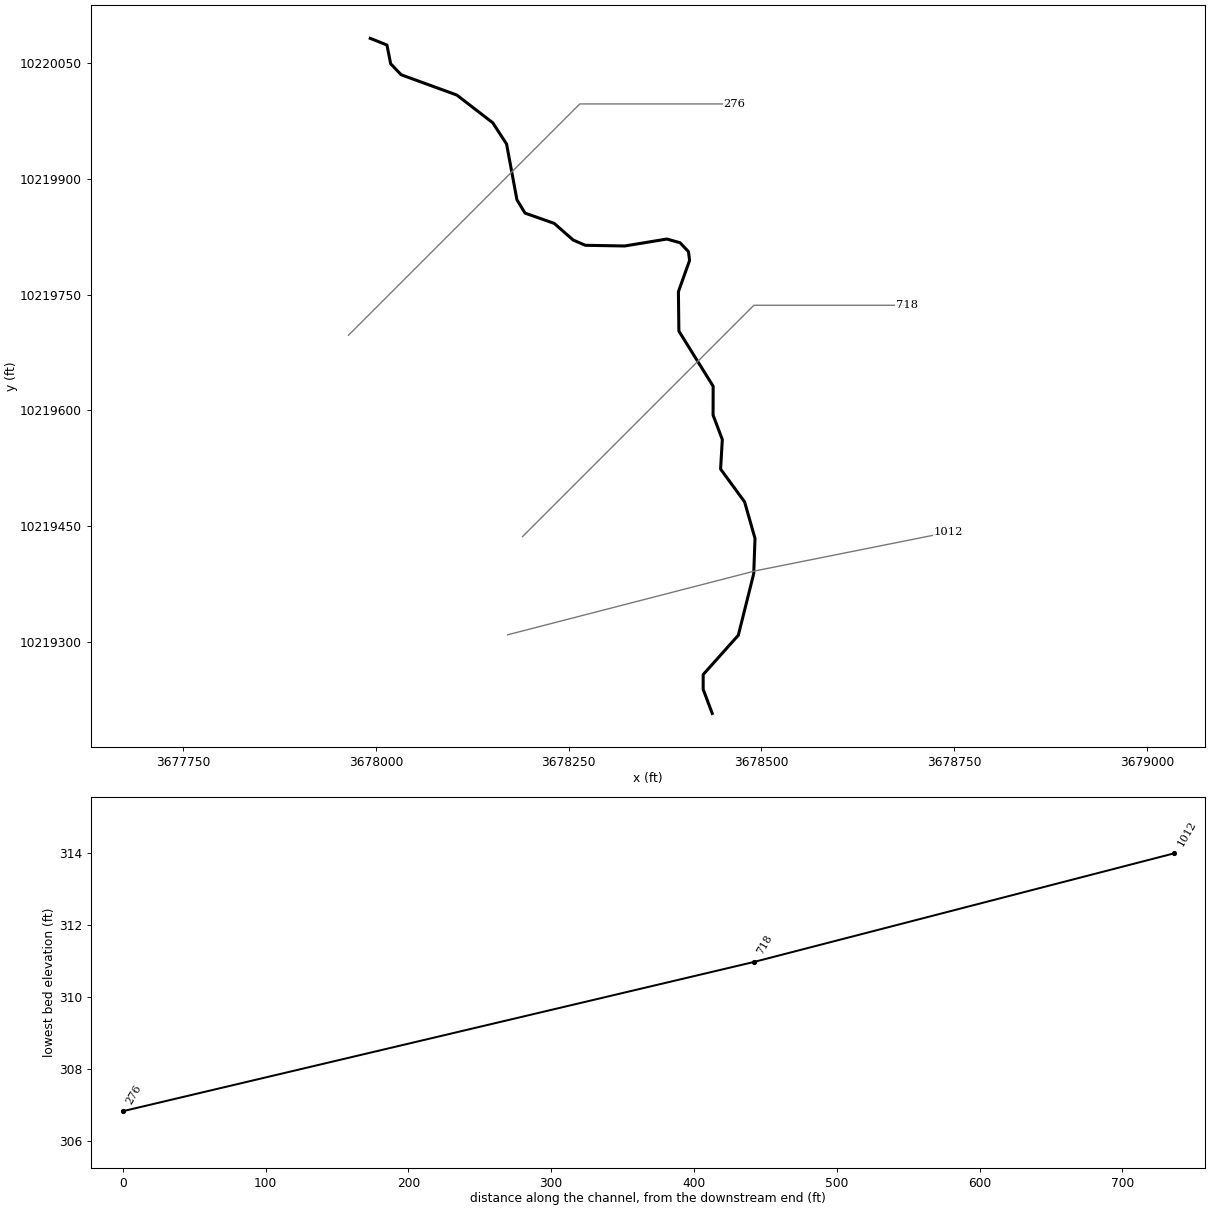
--- UNT041 IN GIBB.prj (project) ---

Proj Title=UNT041 IN GIBB Base Level Engineering
Current Plan=p01
Default Exp/Contr=0.3,0.1
English Units
Geom File=g01
Flow File=f01
Plan File=p01
BEGIN DESCRIPTION:
UNT041 IN GIBB
END DESCRIPTION:

--- UNT041 IN GIBB.p01 (plan) ---

Plan Title=Multiple Run
Short Identifier=Multiple
Geom File=g01
Flow File=f01
Subcritical Flow
K Sum by GR= 0
Std Step Tol= 0.01
Critical Tol= 0.01
Num of Std Step Trials= 20
Max Error Tol= 0.3
Flow Tol Ratio= 0.001
Split Flow NTrial= 30
Split Flow Tol= 0.02
Split Flow Ratio= 0.02
Log Output Level= 0
Friction Slope Method= 1
Unsteady Friction Slope Method= 2
Unsteady Bridges Friction Slope Method= 1
Parabolic Critical Depth
Global Vel Dist=  1 , 1 , 1
Global Log Level= 0
CheckData=True
Encroach Param= -1, 0, 0, 0
BEGIN DESCRIPTION:
Multiple Run
END DESCRIPTION:

--- UNT041 IN GIBB.f01 (steady flow) ---

Flow Title=Multiple
Number of Profiles=7
Profile Names=10-year,25-year,50-year,1pct_min,100-year,1pct_plu,500-year
River Rch & RM= UNT041 IN GIBB,Reach-1,1012
     394     514     609     530     717     970     992
Boundary for River Rch & Prof#=UNT041 IN GIBB,Reach-1,1
Up Type=0
Dn Type=3
Dn Slope=0.005
Boundary for River Rch & Prof#=UNT041 IN GIBB,Reach-1,2
Up Type=0
Dn Type=3
Dn Slope=0.005
Boundary for River Rch & Prof#=UNT041 IN GIBB,Reach-1,3
Up Type=0
Dn Type=3
Dn Slope=0.005
Boundary for River Rch & Prof#=UNT041 IN GIBB,Reach-1,4
Up Type=0
Dn Type=3
Dn Slope=0.005
Boundary for River Rch & Prof#=UNT041 IN GIBB,Reach-1,5
Up Type=0
Dn Type=3
Dn Slope=0.005
Boundary for River Rch & Prof#=UNT041 IN GIBB,Reach-1,6
Up Type=0
Dn Type=3
Dn Slope=0.005
Boundary for River Rch & Prof#=UNT041 IN GIBB,Reach-1,7
Up Type=0
Dn Type=3
Dn Slope=0.005

--- UNT041 IN GIBB.g01 (geometry) ---

Geom Title=Existing Conditions

River Reach=UNT041 IN GIBB,Reach-1
Reach XY= 30
      3678436.20     10219206.82      3678424.47     10219237.96
      3678424.46     10219257.13      3678470.06     10219308.16
      3678490.03     10219388.02      3678491.71     10219433.71
      3678478.19     10219481.12      3678447.06     10219523.68
      3678449.30     10219561.99      3678437.32     10219593.64
      3678437.42     10219631.08      3678392.98     10219702.58
      3678392.34     10219753.66      3678406.85     10219794.26
      3678405.37     10219805.68      3678394.48     10219817.19
      3678377.35     10219821.99      3678322.71     10219812.98
      3678271.64     10219813.87      3678255.92     10219820.67
      3678231.25     10219842.31      3678193.42     10219855.63
      3678182.94     10219872.91      3678169.50     10219945.24
      3678151.53     10219972.82      3678104.94     10220008.76
      3678032.76     10220035.06      3678019.17     10220049.34
      3678014.36     10220073.60      3677992.72     10220082.28

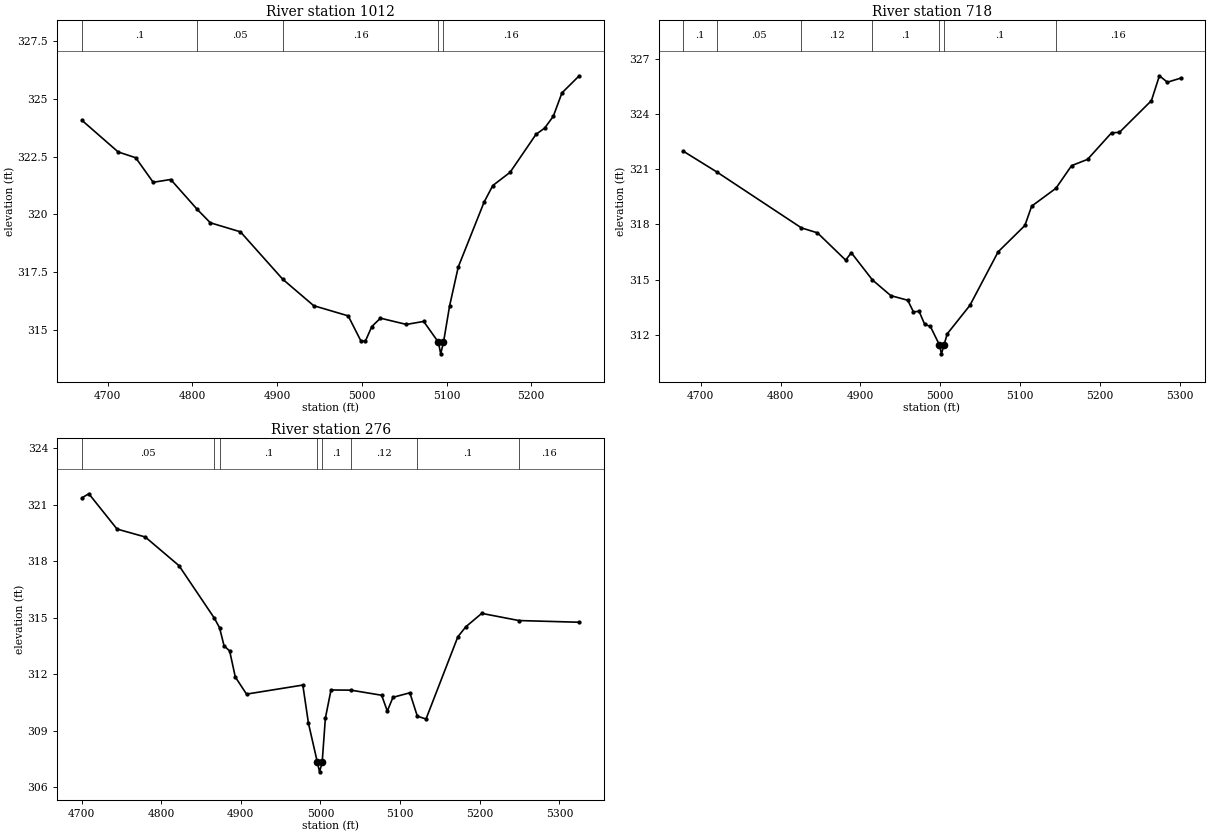
Type RM Length L Ch R = 1,1012,294,294,294
BEGIN DESCRIPTION:
UNT041 IN GIBB 2.0
END DESCRIPTION:
XS GIS Cut Line= 3
      3678170.82     10219308.72      3678492.11     10219391.64
      3678742.14     10219441.65
#Sta/Elev= 30
  4669.8  324.06  4712.4  322.70  4733.1  322.45  4753.7  321.39  4774.4  321.51
  4805.7  320.22  4821.2  319.64  4856.7  319.25  4906.7  317.20  4943.2  316.06
  4983.9  315.62  4999.0  314.53  5004.2  314.53  5011.8  315.16  5022.0  315.52
  5052.6  315.25  5073.0  315.38  5090.4  314.48  5093.1  313.98  5096.4  314.48
  5103.6  316.05  5113.8  317.73  5144.4  320.54  5154.6  321.25  5175.0  321.82
  5205.6  323.46  5215.8  323.73  5226.0  324.24  5236.2  325.25  5256.6  325.99
#Mann=5,-1,0
  4669.8     0.1       0  4805.7    0.05       0  4906.7    0.16       0
  5090.4    0.07       0  5096.4    0.16       0
Bank Sta=5090.4,5096.4
Exp/Cntr=0.3,0.1

Type RM Length L Ch R = 1,718,442,442,442
BEGIN DESCRIPTION:
UNT041 IN GIBB 1.1
END DESCRIPTION:
XS GIS Cut Line= 3
      3678190.22     10219436.10      3678490.22     10219736.10
      3678688.65     10219736.10
#Sta/Elev= 30
  4678.3  321.97  4720.0  320.85  4826.1  317.81  4846.2  317.54  4881.5  316.06
  4888.6  316.46  4915.1  314.98  4938.1  314.13  4959.3  313.88  4966.4  313.25
  4973.5  313.28  4980.5  312.57  4987.6  312.46  4998.8  311.47  5001.5  310.97
  5004.8  311.47  5008.8  312.06  5037.1  313.60  5072.5  316.51  5106.0  317.94
  5114.5  318.99  5144.9  319.96  5164.5  321.19  5184.5  321.53  5214.5  322.97
  5224.5  323.00  5264.5  324.72  5274.5  326.07  5284.5  325.72  5301.0  325.94
#Mann=7,-1,0
  4678.3     0.1       0  4720.0    0.05       0  4826.1    0.12       0
  4915.1     0.1       0  4998.8    0.07       0  5004.8     0.1       0
  5144.9    0.16       0
Bank Sta=4998.8,5004.8
Exp/Cntr=0.3,0.1

Type RM Length L Ch R = 1,276,0,0,0
BEGIN DESCRIPTION:
UNT041 IN GIBB 1.0
END DESCRIPTION:
XS GIS Cut Line= 3
      3677964.45     10219697.21      3678264.45     10219997.20
      3678464.49     10219997.20
#Sta/Elev= 30
  4700.6  321.36  4709.1  321.57  4744.5  319.70  4779.9  319.28  4822.3  317.76
  4866.8  314.97  4873.2  314.47  4878.9  313.51  4885.9  313.24  4893.0  311.86
  4907.1  310.95  4977.8  311.43  4984.9  309.40  4996.1  307.33  4998.8  306.83
  5002.1  307.33  5006.1  309.67  5013.2  311.17  5038.3  311.16  5076.8  310.89
  5083.9  310.05  5091.0  310.78  5112.2  311.02  5121.6  309.78  5132.5  309.63
  5172.5  313.99  5182.5  314.52  5202.5  315.23  5249.2  314.85  5324.9  314.76
#Mann=8,-1,0
  4700.6    0.05       0  4866.8    0.12       0  4873.2     0.1       0
  4996.1    0.07       0  5002.1     0.1       0  5038.3    0.12       0
  5121.6     0.1       0  5249.2    0.16       0
Bank Sta=4996.1,5002.1
Exp/Cntr=0.3,0.1

Chan Stop Cuts=-1