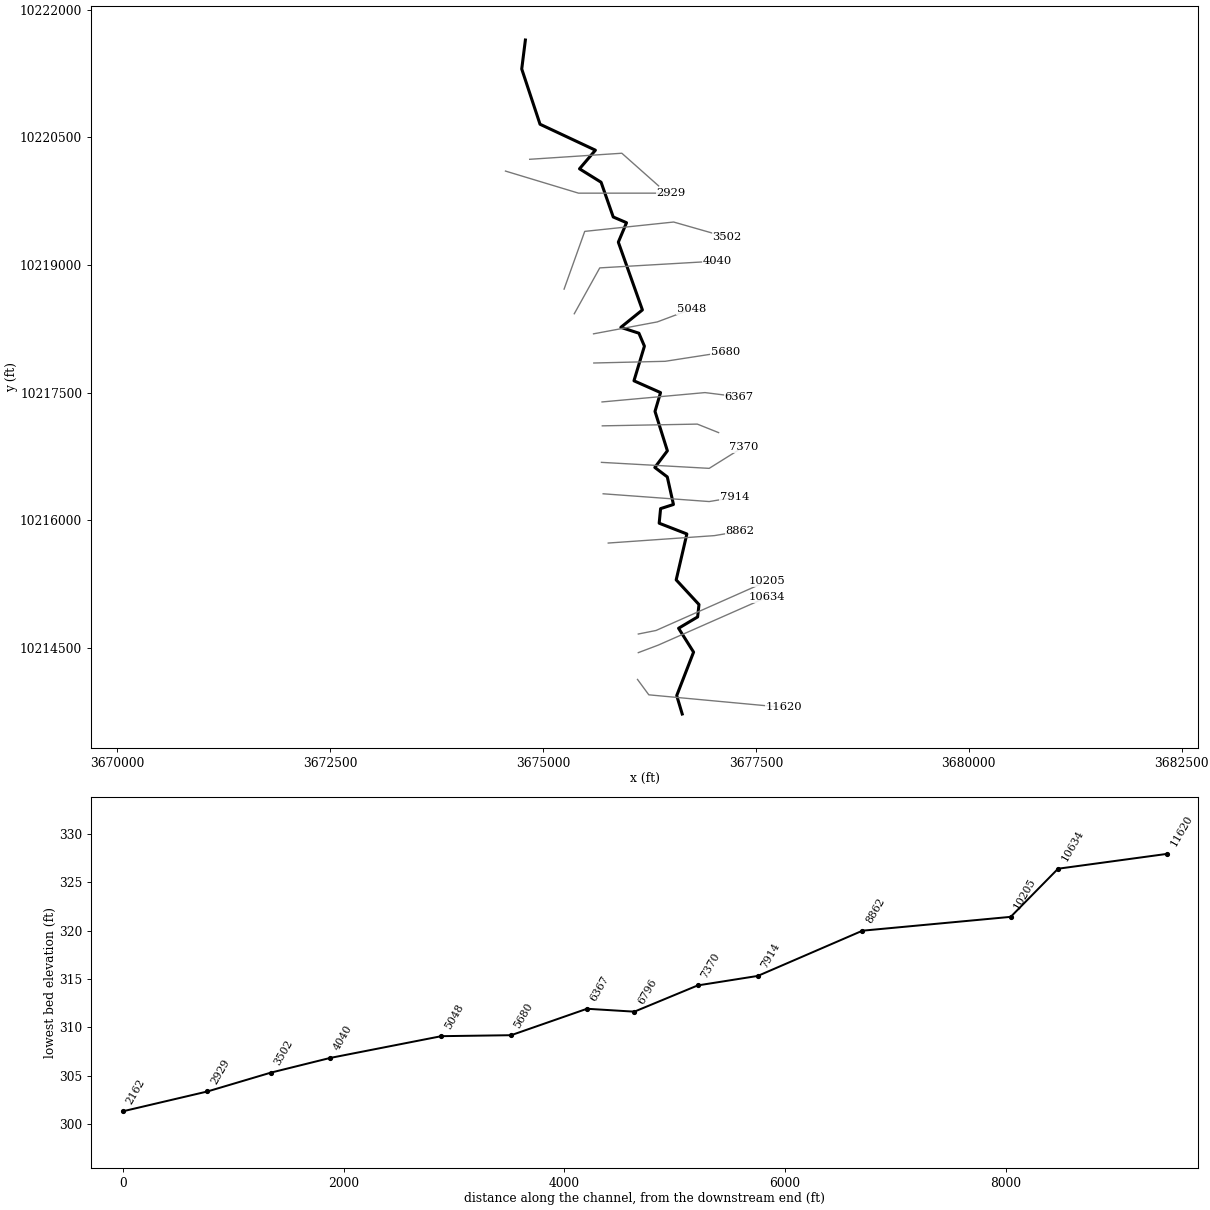
--- UNT042 IN GIBB.prj (project) ---

Proj Title=UNT042 IN GIBB Base Level Engineering
Current Plan=p01
Default Exp/Contr=0.3,0.1
English Units
Geom File=g01
Flow File=f01
Plan File=p01
Y Axis Title=Elevation
X Axis Title(PF)=Main Channel Distance
X Axis Title(XS)=Station
BEGIN DESCRIPTION:
UNT042 IN GIBB
END DESCRIPTION:
DSS Export Rating Curves= 0
DSS Export Rating Curve Sorted= 0
DSS Export Volume Flow Curves= 0
DXF OffsetX= 0
DXF OffsetY= 0
DXF ScaleX= 1
DXF ScaleY= 10

--- UNT042 IN GIBB.p01 (plan) ---

Plan Title=Multiple Run
Short Identifier=Multiple
Geom File=g01
Flow File=f01
Subcritical Flow
K Sum by GR= 0
Std Step Tol= 0.01
Critical Tol= 0.01
Num of Std Step Trials= 20
Max Error Tol= 0.3
Flow Tol Ratio= 0.001
Split Flow NTrial= 30
Split Flow Tol= 0.02
Split Flow Ratio= 0.02
Log Output Level= 0
Friction Slope Method= 1
Unsteady Friction Slope Method= 2
Unsteady Bridges Friction Slope Method= 1
Parabolic Critical Depth
Global Vel Dist=  1 , 1 , 1
Global Log Level= 0
CheckData=True
Encroach Param= -1, 0, 0, 0
BEGIN DESCRIPTION:
Multiple Run
END DESCRIPTION:

--- UNT042 IN GIBB.f01 (steady flow) ---

Flow Title=Multiple
Number of Profiles=7
Profile Names=10-year,25-year,50-year,1pct_min,100-year,1pct_plu,500-year
River Rch & RM= UNT042 IN GIBB,Reach-1,11620
     787    1062    1286    1140    1542    2085    2215
River Rch & RM= UNT042 IN GIBB,Reach-1,10205
     944    1281    1558    1385    1873    2533    2707
Boundary for River Rch & Prof#=UNT042 IN GIBB,Reach-1,1
Up Type=0
Dn Type=3
Dn Slope=0.005
Boundary for River Rch & Prof#=UNT042 IN GIBB,Reach-1,2
Up Type=0
Dn Type=3
Dn Slope=0.005
Boundary for River Rch & Prof#=UNT042 IN GIBB,Reach-1,3
Up Type=0
Dn Type=3
Dn Slope=0.005
Boundary for River Rch & Prof#=UNT042 IN GIBB,Reach-1,4
Up Type=0
Dn Type=3
Dn Slope=0.005
Boundary for River Rch & Prof#=UNT042 IN GIBB,Reach-1,5
Up Type=0
Dn Type=3
Dn Slope=0.005
Boundary for River Rch & Prof#=UNT042 IN GIBB,Reach-1,6
Up Type=0
Dn Type=3
Dn Slope=0.005
Boundary for River Rch & Prof#=UNT042 IN GIBB,Reach-1,7
Up Type=0
Dn Type=3
Dn Slope=0.005

--- UNT042 IN GIBB.g01 (geometry) ---

Geom Title=Existing Conditions
Program Version=4.10

River Reach=UNT042 IN GIBB  ,Reach-1
Reach XY= 30
      3676633.75      10213726.4      3676569.18      10213942.7
      3676767.26     10214453.26      3676591.04     10214733.43
      3676814.71     10214866.69      3676830.69     10215012.07
      3676562.91     10215301.85      3676688.35     10215841.11
      3676363.18     10215967.34      3676379.71     10216138.73
      3676530.82      10216187.2      3676458.34     10216511.28
      3676312.09     10216622.17      3676459.52     10216817.71
      3676314.14     10217280.65      3676379.27      10217501.5
        3676067.     10217639.95       3676189.8      10218046.9
      3676125.13       10218199.      3675912.88     10218267.75
      3676166.15     10218472.57      3675883.29      10219268.4
      3675979.84     10219496.84      3675823.65     10219563.93
      3675680.91     10219972.21      3675427.41     10220129.97
      3675614.09     10220348.49      3674963.79     10220653.38
      3674748.79     10221302.37      3674791.71     10221642.51

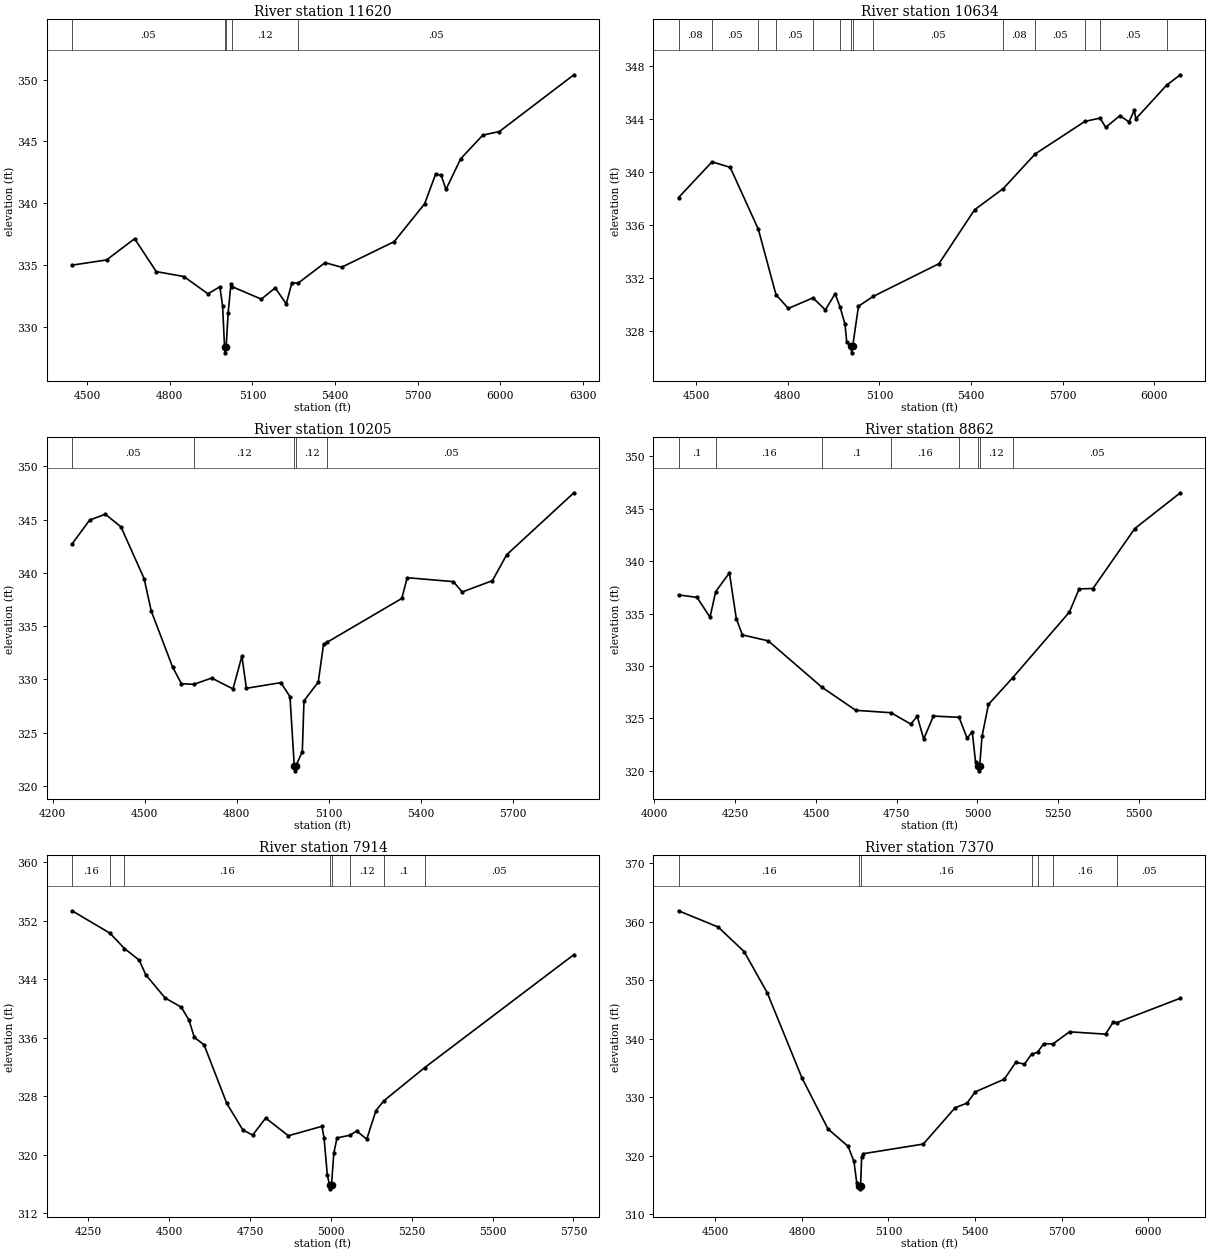
Type RM Length L Ch R = 1 ,11620   ,986,986,986
BEGIN DESCRIPTION:
UNT042 IN GIBB 19.0
END DESCRIPTION:
XS GIS Cut Line= 3
      3676108.65     10214132.42       3676241.4     10213951.73
      3677831.33     10213803.87
#Sta/Elev= 30
  4445.6     335  4570.7  335.42  4672.7  337.14  4750.9  334.48  4851.3  334.08
  4938.7  332.68  4981.9  333.25  4991.9  331.69  4998.9  328.41  5001.7  327.91
  5004.9  328.41    5012  331.13    5022  333.46  5027.5  333.25  5132.5  332.25
  5182.7  333.16  5222.9  331.87    5243  333.55  5266.9  333.56  5363.5   335.2
  5423.8  334.83  5614.6   336.9    5725  339.96  5765.2  342.37  5785.3  342.25
  5802.5  341.12  5855.6  343.59    5936  345.51  5996.2   345.8  6266.6  350.39
#Mann= 5 ,-1 , 0
  4445.6     .05       0  4998.9     .03       0  5004.9     .05       0
  5027.5     .12       0  5266.9     .05       0
Bank Sta=4998.9,5004.9
XS Rating Curve= 0 ,0
Exp/Cntr=0.3,0.1

Type RM Length L Ch R = 1 ,10634   ,429,429,429
BEGIN DESCRIPTION:
UNT042 IN GIBB 17.0
END DESCRIPTION:
XS GIS Cut Line= 3
      3676118.12     10214447.17      3676352.45     10214535.69
        3677626.     10215097.09
#Sta/Elev= 30
  4442.3   338.1    4552   340.8  4611.4  340.38  4703.6   335.7  4761.3  330.77
  4801.7  329.73  4882.2  330.53  4922.8  329.62  4954.7  330.84  4970.8  329.86
  4987.3  328.52  4992.8  327.18  5006.3  326.88  5009.1  326.38  5012.3  326.88
  5031.2   329.9  5079.5  330.64  5294.6  333.11  5411.2  337.18  5505.1  338.78
  5609.9   341.4  5772.3  343.85    5822   344.1  5840.5   343.4  5887.1  344.29
  5916.4  343.81  5933.8  344.68  5939.2  344.05  6039.5  346.58  6084.6  347.37
#Mann= 14 ,-1 , 0
  4442.3     .08       0    4552     .05       0  4703.6     .08       0
  4761.3     .05       0  4882.2     .12       0  4970.8     .08       0
  5006.3     .07       0  5012.3     .08       0  5079.5     .05       0
  5505.1     .08       0  5609.9     .05       0  5772.3     .08       0
    5822     .05       0  6039.5     .08       0
Bank Sta=5006.3,5012.3
XS Rating Curve= 0 ,0
Exp/Cntr=0.3,0.1

Type RM Length L Ch R = 1 ,10205   ,1343,1343,1343
BEGIN DESCRIPTION:
UNT042 IN GIBB 15.0
END DESCRIPTION:
XS GIS Cut Line= 3
      3676118.07      10214665.9      3676326.41     10214707.57
       3677628.7     10215284.92
#Sta/Elev= 30
    4263  342.71  4320.5  344.95  4371.5   345.5  4422.5  344.31    4498  339.46
  4521.3  336.41  4591.1  331.14  4619.8  329.59  4660.2  329.53  4718.4  330.12
    4788   329.1    4817  332.17  4831.7  329.16  4944.3  329.69  4973.9  328.37
  4987.8  321.91  4990.6  321.41  4993.8  321.91  5014.1  323.22  5019.6  327.98
  5066.1  329.74  5083.3  333.27  5095.6  333.49  5338.6  337.59  5356.4  339.54
    5507  339.17  5535.7   338.2  5634.3  339.26  5680.8  341.69    5900  347.51
#Mann= 5 ,-1 , 0
    4263     .05       0  4660.2     .12       0  4987.8     .07       0
  4993.8     .12       0  5095.6     .05       0
Bank Sta=4987.8,4993.8
XS Rating Curve= 0 ,0
Exp/Cntr=0.3,0.1

Type RM Length L Ch R = 1 ,8862    ,948,948,948
BEGIN DESCRIPTION:
UNT042 IN GIBB 14.0
END DESCRIPTION:
XS GIS Cut Line= 3
      3675764.94     10215734.44      3677011.29     10215821.57
      3677311.26     10215871.56
#Sta/Elev= 30
  4074.8  336.78  4132.1  336.54  4172.2  334.65    4190   337.1  4232.3  338.88
  4253.6  334.52  4272.4  332.96  4352.6  332.39  4518.8  327.96  4623.3  325.76
  4732.4  325.53  4793.7  324.45  4813.8  325.18  4833.8  323.02  4863.9  325.21
  4943.3  325.09    4968  323.11  4984.2  323.69  4994.2  320.87  5001.2  320.48
    5004  319.98  5007.2  320.48  5014.3  323.26  5034.3  326.32  5109.9  328.89
  5284.9  335.14    5315  337.35  5357.8  337.39  5487.2  343.11  5628.3  346.53
#Mann= 8 ,-1 , 0
  4074.8      .1       0    4190     .16       0  4518.8      .1       0
  4732.4     .16       0  4943.3     .12       0  5001.2     .07       0
  5007.2     .12       0  5109.9     .05       0
Bank Sta=5001.2,5007.2
XS Rating Curve= 0 ,0
Exp/Cntr=0.3,0.1

Type RM Length L Ch R = 1 ,7914    ,544,544,544
BEGIN DESCRIPTION:
UNT042 IN GIBB 12.0
END DESCRIPTION:
XS GIS Cut Line= 3
      3675705.09     10216312.97      3676950.93     10216221.69
      3677249.04     10216271.38
#Sta/Elev= 30
  4200.1  353.34  4317.1  350.28  4362.2  348.18  4407.7  346.58  4428.1  344.58
  4487.9  341.41    4538  340.15  4561.7  338.37  4578.1  336.03  4608.2  335.01
  4678.4     327  4728.5  323.33  4758.6  322.67  4798.7  324.99  4868.9  322.57
  4972.6  323.86  4979.2  322.26  4989.2  317.23  4996.2  315.81    4999  315.31
  5002.2  315.81  5009.3   320.2  5019.3  322.28  5060.5  322.65  5079.5  323.24
  5111.2   322.1  5139.6  326.01  5163.7  327.34    5290  331.88  5751.5  347.34
#Mann= 8 ,-1 , 0
  4200.1     .16       0  4317.1      .1       0  4362.2     .16       0
  4996.2     .07       0  5002.2     .16       0  5060.5     .12       0
  5163.7      .1       0    5290     .05       0
Bank Sta=4996.2,5002.2
XS Rating Curve= 0 ,0
Exp/Cntr=0.3,0.1

Type RM Length L Ch R = 1 ,7370    ,574,574,574
BEGIN DESCRIPTION:
UNT042 IN GIBB 11.0
END DESCRIPTION:
XS GIS Cut Line= 3
      3675685.19     10216682.02      3676950.55     10216611.59
      3677350.54     10216861.58
#Sta/Elev= 30
  4372.4  361.84  4509.5  359.07  4599.7  354.87  4679.8  347.83    4800   333.3
  4890.1  324.58  4960.2  321.58  4980.3  319.02  4990.3  315.25  4997.3  314.83
    5000  314.33  5003.3  314.83  5007.1  319.82  5012.2  320.33  5220.6  321.98
  5330.8  328.18  5372.4  328.99  5400.9   330.9  5501.1  333.06  5541.1  335.94
  5571.2  335.65  5595.7  337.32  5616.9  337.68    5638  339.14  5669.6  339.08
  5727.4  341.16  5852.4  340.76  5879.5  342.88  5890.9  342.72  6111.4   346.9
#Mann= 7 ,-1 , 0
  4372.4     .16       0  4997.3     .07       0  5003.3     .16       0
  5595.7      .1       0  5616.9     .05       0  5669.6     .16       0
  5890.9     .05       0
Bank Sta=4997.3,5003.3
XS Rating Curve= 0 ,0
Exp/Cntr=0.3,0.1

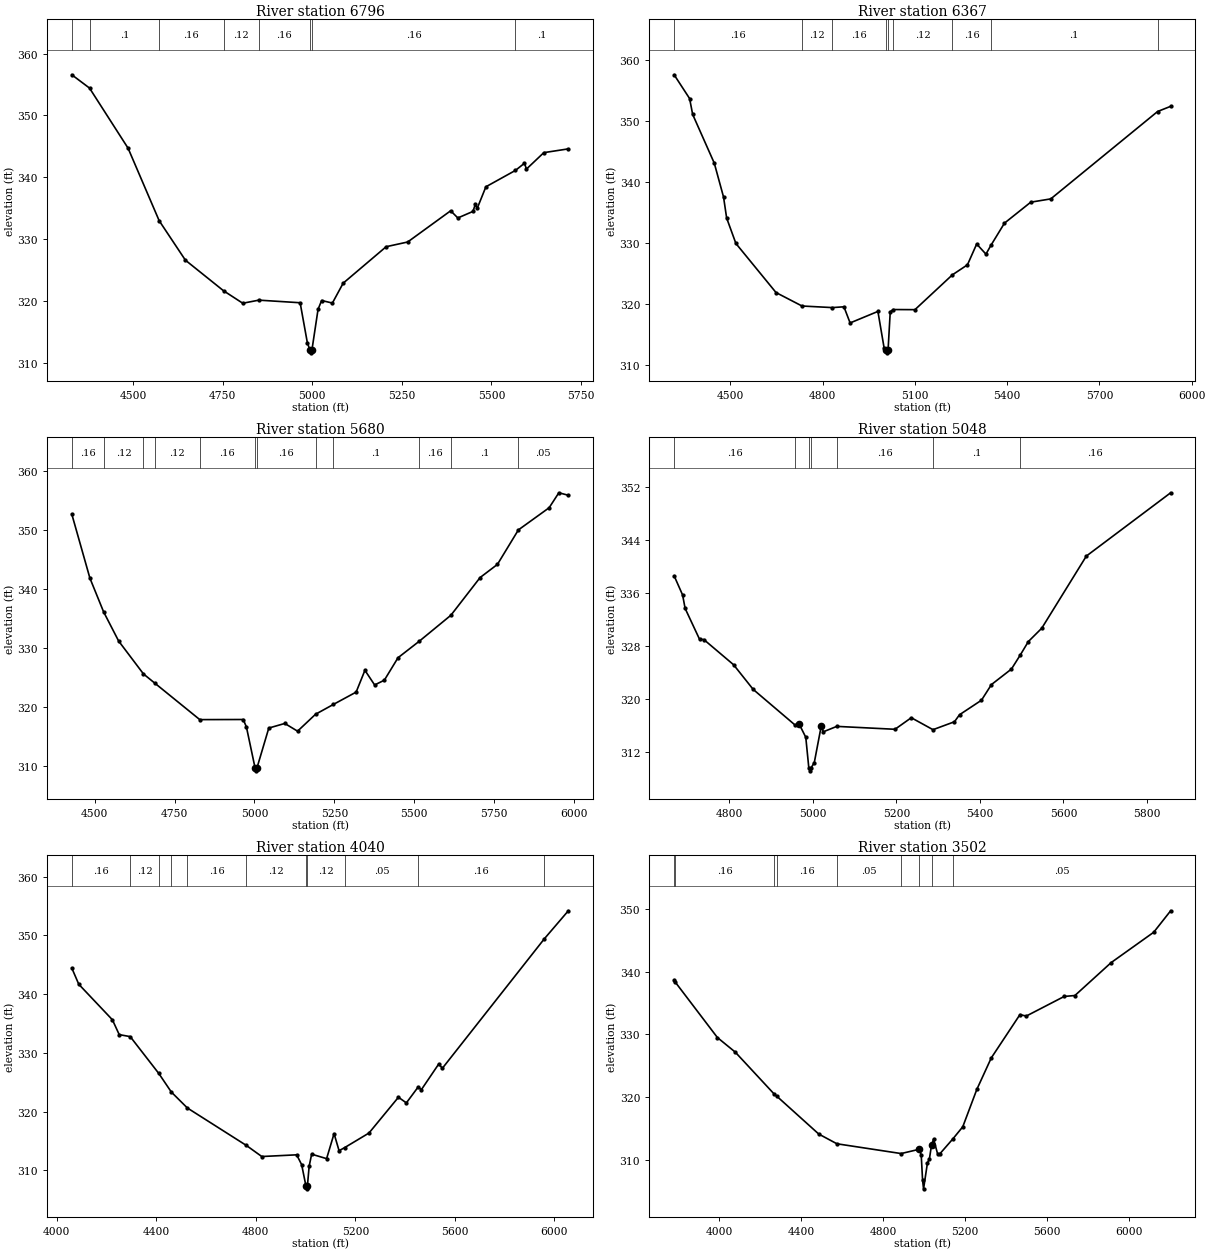
Type RM Length L Ch R = 1 ,6796    ,429,429,429
BEGIN DESCRIPTION:
UNT042 IN GIBB 10.0
END DESCRIPTION:
XS GIS Cut Line= 3
      3675695.16     10217110.92      3676811.16     10217131.41
      3677061.12     10217031.43
#Sta/Elev= 30
  4329.2  356.58  4378.6  354.43  4486.2  344.71    4573  332.98  4646.2   326.6
  4752.5  321.66  4806.2  319.64  4851.1  320.14  4966.3  319.72  4986.3  313.29
  4993.3  312.12    4996  311.62  4999.3  312.12  5016.3  318.66  5026.3  320.08
  5056.3  319.67  5086.3  322.88  5206.3  328.78  5266.3  329.54  5386.3  334.59
  5406.3  333.43  5448.6  334.49    5455  335.63  5460.4  334.99  5484.6  338.47
  5567.1  341.12  5592.3  342.28  5597.7  341.33  5646.2  343.99  5714.6   344.6
#Mann= 8 ,-1 , 0
  4329.2     .16       0  4378.6      .1       0    4573     .16       0
  4752.5     .12       0  4851.1     .16       0  4993.3     .07       0
  4999.3     .16       0  5567.1      .1       0
Bank Sta=4993.3,4999.3
XS Rating Curve= 0 ,0
Exp/Cntr=0.3,0.1

Type RM Length L Ch R = 1 ,6367    ,687,687,687
BEGIN DESCRIPTION:
UNT042 IN GIBB 9.0
END DESCRIPTION:
XS GIS Cut Line= 3
      3675692.06     10217391.64       3676900.8     10217501.49
      3677298.98     10217451.72
#Sta/Elev= 30
  4316.7  357.58    4367  353.68    4377  351.07  4447.3  343.07  4477.4  337.51
  4487.5  334.06  4517.6  329.88  4648.1  321.82  4732.6  319.61  4831.4  319.35
    4869  319.48  4889.1  316.83  4979.5  318.72  4999.6  312.75  5006.6  312.42
  5009.3  311.92  5012.6  312.42  5019.6  318.65    5029  319.03    5100  319.01
  5221.8  324.73  5270.7  326.37  5300.8  329.79  5330.9  328.13  5347.2  329.58
  5391.2  333.22  5476.7  336.66  5541.8   337.2  5889.3  351.55  5931.7   352.4
#Mann= 9 ,-1 , 0
  4316.7     .16       0  4732.6     .12       0  4831.4     .16       0
  5006.6     .07       0  5012.6     .16       0    5029     .12       0
  5221.8     .16       0  5347.2      .1       0  5889.3     .05       0
Bank Sta=5006.6,5012.6
XS Rating Curve= 0 ,0
Exp/Cntr=0.3,0.1

Type RM Length L Ch R = 1 ,5680    ,632,632,632
BEGIN DESCRIPTION:
UNT042 IN GIBB 8.0
END DESCRIPTION:
XS GIS Cut Line= 3
      3675595.44     10217849.03      3676433.28     10217868.98
      3677141.46      10217978.7
#Sta/Elev= 30
    4428  352.74  4484.7  341.88  4527.6  336.16  4574.7  331.21  4652.4  325.63
  4687.6  324.08  4828.7  317.88  4964.8   317.9  4974.8  316.62  5001.8  309.69
  5004.6  309.19  5007.8  309.69  5044.8  316.45  5094.9  317.23  5134.9  315.92
  5191.2  318.79  5246.8  320.45  5318.3  322.55  5345.8  326.25  5376.2  323.76
  5406.6  324.57  5449.4  328.38  5515.7  331.17    5615  335.59  5706.5  341.99
  5760.7  344.22  5826.3  350.07  5922.6  353.83    5953  356.37  5982.7  355.95
#Mann= 12 ,-1 , 0
    4428     .16       0  4527.6     .12       0  4652.4     .16       0
  4687.6     .12       0  4828.7     .16       0  5001.8     .07       0
  5007.8     .16       0  5191.2     .12       0  5246.8      .1       0
  5515.7     .16       0    5615      .1       0  5826.3     .05       0
Bank Sta=5001.8,5007.8
XS Rating Curve= 0 ,0
Exp/Cntr=0.3,0.1

Type RM Length L Ch R = 1 ,5048    ,1008,1008,1008
BEGIN DESCRIPTION:
UNT042 IN GIBB 6.0
END DESCRIPTION:
XS GIS Cut Line= 3
      3675592.14     10218191.65      3676341.21     10218331.67
      3676741.17     10218481.65
#Sta/Elev= 30
  4667.7  338.61    4688  335.71    4694  333.68  4728.7  328.99  4738.9  328.96
  4810.1  325.15    4857  321.42  4957.6  316.01  4967.4  316.14    4983  314.17
  4990.2  309.59    4993  309.09  4996.2  309.59  5003.4  310.34    5020  315.86
  5025.1     315  5057.3  315.82  5196.7  315.38  5235.7  317.13  5287.7  315.32
  5339.1  316.52  5351.2  317.58  5403.8  319.78  5427.7  322.15  5475.6   324.5
  5496.5   326.6  5516.1  328.66  5548.2  330.68    5655   341.6  5856.9  351.18
#Mann= 7 ,-1 , 0
  4667.7     .16       0  4957.6     .12       0  4990.2     .07       0
  4996.2     .12       0  5057.3     .16       0  5287.7      .1       0
  5496.5     .16       0
Bank Sta=4967.4,5020
XS Rating Curve= 0 ,0
Exp/Cntr=0.3,0.1

Type RM Length L Ch R = 1 ,4040    ,538,538,538
BEGIN DESCRIPTION:
UNT042 IN GIBB 4.0
END DESCRIPTION:
XS GIS Cut Line= 3
      3675366.02     10218427.57      3675665.24     10218966.18
      3677041.69     10219045.97
#Sta/Elev= 30
  4060.8  344.42  4088.8  341.66  4223.8  335.62  4251.3  333.09  4295.5  332.75
  4410.3  326.48  4460.8  323.31  4525.2   320.6    4762  314.23  4824.1  312.34
  4964.3  312.63  4984.3  310.95  5001.4  307.34  5004.1  306.84  5007.4  307.34
  5014.4  310.69  5024.4  312.74  5084.5  311.98  5114.5  316.24  5134.6  313.33
  5156.7  313.85  5254.8  316.34  5373.1  322.43    5405  321.47  5452.6  324.19
  5465.1  323.71  5535.2   328.1  5549.6  327.36  5959.3   349.4  6055.7  354.17
#Mann= 11 ,-1 , 0
  4060.8     .16       0  4295.5     .12       0  4410.3     .16       0
  4460.8     .12       0  4525.2     .16       0    4762     .12       0
  5001.4     .07       0  5007.4     .12       0  5156.7     .05       0
  5452.6     .16       0  5959.3     .05       0
Bank Sta=5001.4,5007.4
XS Rating Curve= 0 ,0
Exp/Cntr=0.3,0.1

Type RM Length L Ch R = 1 ,3502    ,573,573,573
BEGIN DESCRIPTION:
UNT042 IN GIBB 3.0
END DESCRIPTION:
XS GIS Cut Line= 4
       3675246.3     10218716.79      3675488.73     10219394.92
      3676533.02      10219504.8      3677161.45     10219325.25
#Sta/Elev= 30
  3778.8  338.66  3784.3  338.31  3990.1  329.46  4077.1  327.14  4268.5   320.4
  4278.9  320.13  4484.9  314.06  4573.5  312.51  4886.8  310.95    4975  311.63
    4985  310.73  4991.6   306.7  4996.4  305.32  5015.2  309.42  5025.2  310.15
  5035.3   312.3  5045.3  313.26  5065.5  310.84  5075.5  310.89  5139.7   313.3
  5187.8  315.22  5256.5  321.19  5326.9  326.21  5466.9  333.12  5497.8  332.89
    5683  336.02  5735.3  336.17  5912.1  341.42  6119.8  346.26  6202.6  349.69
#Mann= 9 ,-1 , 0
  3778.8      .1       0  3784.3     .16       0  4268.5     .05       0
  4278.9     .16       0  4573.5     .05       0  4886.8     .12       0
    4975     .07       0  5035.3     .12       0  5139.7     .05       0
Bank Sta=4975,5035.3
XS Rating Curve= 0 ,0
Exp/Cntr=0.3,0.1

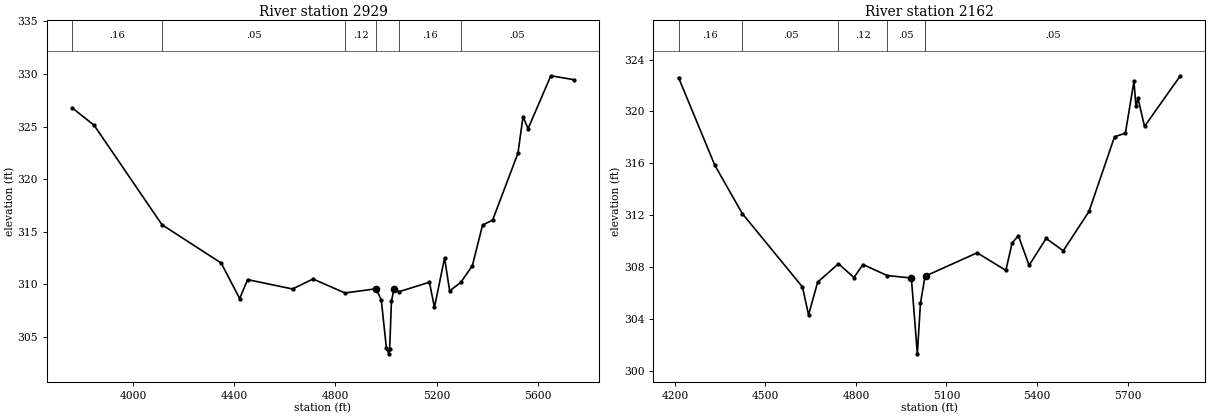
Type RM Length L Ch R = 1 ,2929    ,767,767,767
BEGIN DESCRIPTION:
UNT042 IN GIBB 2.0
END DESCRIPTION:
XS GIS Cut Line= 3
      3674558.03     10220103.28      3675415.88     10219843.93
      3676503.09     10219843.93
#Sta/Elev= 30
  3759.3  326.79  3846.6  325.12  4114.7  315.66  4348.6  312.02  4421.7  308.64
  4453.1  310.44  4630.7  309.55  4711.7   310.5    4838  309.17  4961.7  309.57
  4981.7  308.47  5001.7  303.93  5011.5  303.38  5014.7  303.88  5021.7   308.4
  5031.7  309.52  5051.7  309.29  5171.7  310.19  5191.7  307.81  5231.7   312.5
  5251.7  309.37  5295.8  310.17  5341.7  311.78  5381.7  315.62  5421.7  316.11
  5521.7  322.46  5541.7  325.93  5561.7   324.8  5651.7  329.83  5742.7  329.46
#Mann= 6 ,-1 , 0
  3759.3     .16       0  4114.7     .05       0    4838     .12       0
  4961.7     .07       0  5051.7     .16       0  5295.8     .05       0
Bank Sta=4961.7,5031.7
XS Rating Curve= 0 ,0
Exp/Cntr=0.3,0.1

Type RM Length L Ch R = 1 ,2162    ,0,0,0
BEGIN DESCRIPTION:
UNT042 IN GIBB 1.0
END DESCRIPTION:
XS GIS Cut Line= 3
      3674842.14     10220241.64      3675924.58     10220312.73
      3676356.94     10219928.93
#Sta/Elev= 30
    4212  322.61  4332.2  315.86  4423.2  312.14  4622.8  306.48  4642.9  304.33
    4673  306.85  4742.1  308.27  4793.2  307.21  4823.3  308.21  4903.6  307.36
  4983.6  307.17  5003.4  301.33  5013.7  305.22  5028.2  307.22  5033.7  307.36
  5201.5  309.11  5296.8  307.76  5317.3  309.86  5338.2  310.43  5373.7  308.15
  5430.2  310.22    5487  309.27  5572.3   312.3  5656.8  318.05  5692.8  318.33
  5721.2  322.32  5727.9  320.41  5734.7     321  5756.3  318.85  5874.9  322.75
#Mann= 6 ,-1 , 0
    4212     .16       0  4423.2     .05       0  4742.1     .12       0
  4903.6     .05       0  5028.2     .12       0  5028.2     .05       0
Bank Sta=4983.6,5033.7
XS Rating Curve= 0 ,0
Exp/Cntr=0.3,0.1

Chan Stop Cuts=-1
Use User Specified Reach Order=0
Composite Channel Slope=5