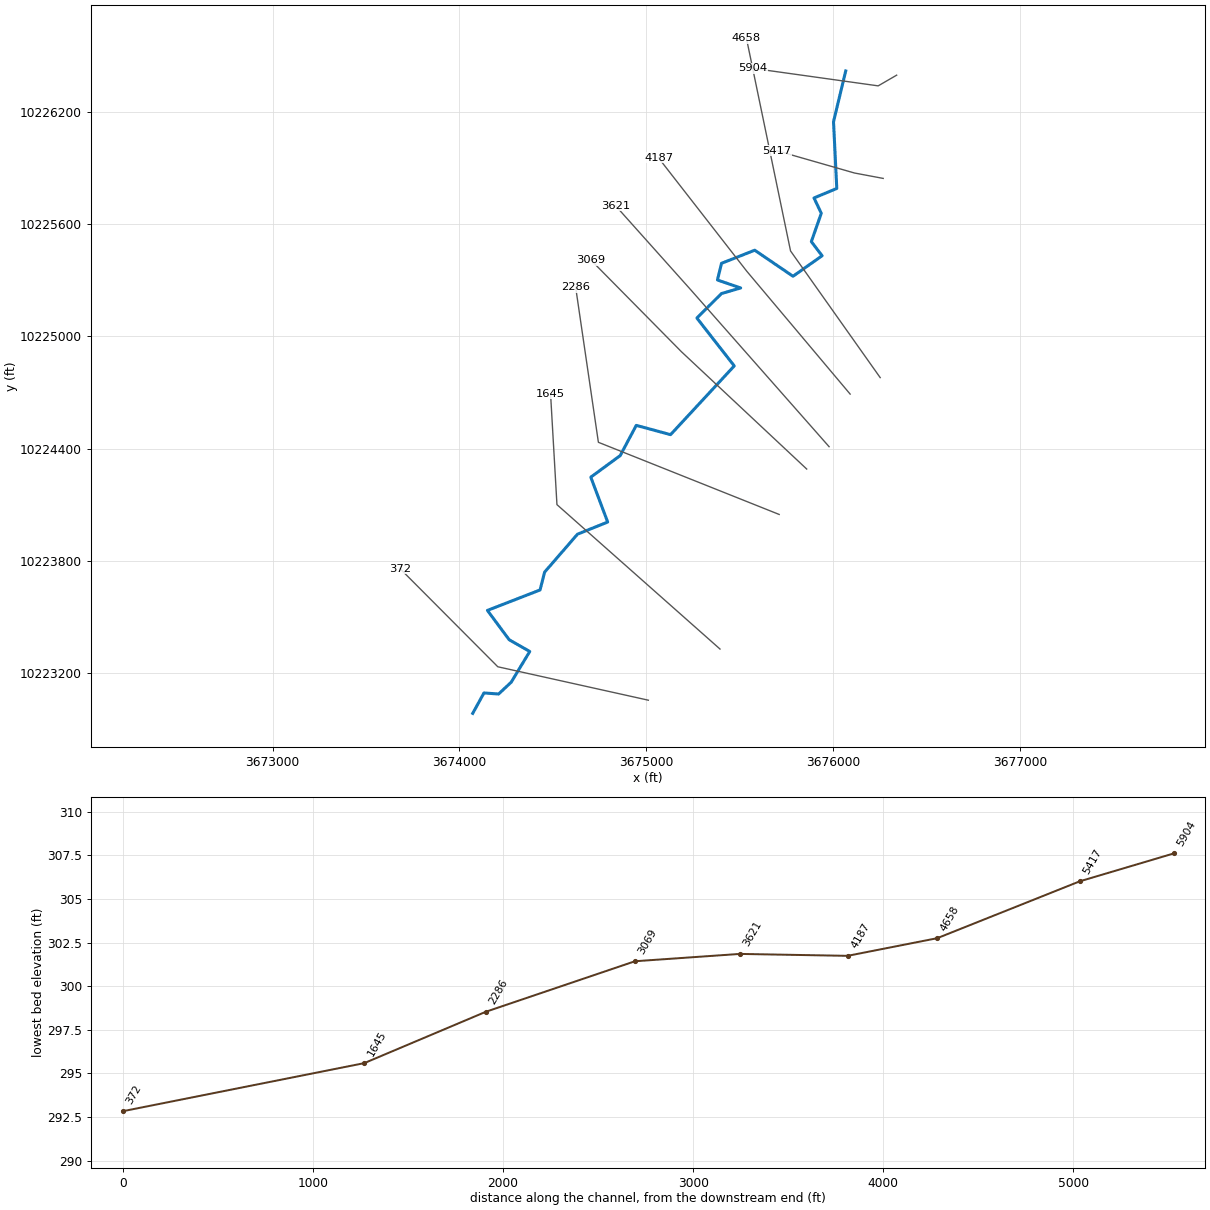
--- UNT043 IN GIBB.prj (project) ---

Proj Title=UNT043 IN GIBB Base Level Engineering
Current Plan=p01
Default Exp/Contr=0.3,0.1
English Units
Geom File=g01
Flow File=f01
Plan File=p01
Y Axis Title=Elevation
X Axis Title(PF)=Main Channel Distance
X Axis Title(XS)=Station
BEGIN DESCRIPTION:
UNT043 IN GIBB
END DESCRIPTION:
DSS Export Rating Curves= 0
DSS Export Rating Curve Sorted= 0
DSS Export Volume Flow Curves= 0
DXF OffsetX= 0
DXF OffsetY= 0
DXF ScaleX= 1
DXF ScaleY= 10

--- UNT043 IN GIBB.p01 (plan) ---

Plan Title=Multiple Run
Short Identifier=Multiple
Geom File=g01
Flow File=f01
Subcritical Flow
K Sum by GR= 0
Std Step Tol= 0.01
Critical Tol= 0.01
Num of Std Step Trials= 20
Max Error Tol= 0.3
Flow Tol Ratio= 0.001
Split Flow NTrial= 30
Split Flow Tol= 0.02
Split Flow Ratio= 0.02
Log Output Level= 0
Friction Slope Method= 1
Unsteady Friction Slope Method= 2
Unsteady Bridges Friction Slope Method= 1
Parabolic Critical Depth
Global Vel Dist=  1 , 1 , 1
Global Log Level= 0
CheckData=True
Encroach Param= -1, 0, 0, 0
BEGIN DESCRIPTION:
Multiple Run
END DESCRIPTION:

--- UNT043 IN GIBB.f01 (steady flow) ---

Flow Title=Multiple
Number of Profiles=7
Profile Names=10-year,25-year,50-year,1pct_min,100-year,1pct_plu,500-year
River Rch & RM= UNT043 IN GIBB,Reach-1,5904
     621     827     994     875    1183    1600    1676
River Rch & RM= UNT043 IN GIBB,Reach-1,4658
    1072    1476    1812    1627    2200    2975    3244
River Rch & RM= UNT043 IN GIBB,Reach-1,2286
    1044    1431    1751    1568    2120    2867    3107
Boundary for River Rch & Prof#=UNT043 IN GIBB,Reach-1,1
Up Type=0
Dn Type=3
Dn Slope=0.005
Boundary for River Rch & Prof#=UNT043 IN GIBB,Reach-1,2
Up Type=0
Dn Type=3
Dn Slope=0.005
Boundary for River Rch & Prof#=UNT043 IN GIBB,Reach-1,3
Up Type=0
Dn Type=3
Dn Slope=0.005
Boundary for River Rch & Prof#=UNT043 IN GIBB,Reach-1,4
Up Type=0
Dn Type=3
Dn Slope=0.005
Boundary for River Rch & Prof#=UNT043 IN GIBB,Reach-1,5
Up Type=0
Dn Type=3
Dn Slope=0.005
Boundary for River Rch & Prof#=UNT043 IN GIBB,Reach-1,6
Up Type=0
Dn Type=3
Dn Slope=0.005
Boundary for River Rch & Prof#=UNT043 IN GIBB,Reach-1,7
Up Type=0
Dn Type=3
Dn Slope=0.005

--- UNT043 IN GIBB.g01 (geometry) ---

Geom Title=Existing Conditions
Program Version=4.10

River Reach=UNT043 IN GIBB  ,Reach-1
Reach XY= 30
      3676068.39     10226421.49      3676003.08     10226149.53
      3676020.56     10225792.44      3675898.63     10225741.53
      3675937.63     10225659.54      3675884.37      10225507.8
      3675941.98     10225432.19      3675786.13     10225322.38
      3675581.39     10225461.86      3675403.59     10225391.76
      3675381.72     10225302.37      3675506.14     10225259.82
      3675403.52     10225229.95      3675271.63     10225098.84
      3675471.71     10224842.51      3675130.79     10224474.48
      3674947.21     10224524.26      3674861.18     10224362.43
      3674703.73     10224246.87      3674794.24     10224006.69
       3674632.5     10223941.67      3674456.51     10223738.59
      3674432.21     10223643.11      3674150.38     10223533.66
      3674266.88     10223376.63      3674376.92     10223313.84
      3674277.87     10223149.51      3674210.18     10223086.19
      3674131.88     10223091.92      3674071.71     10222982.51

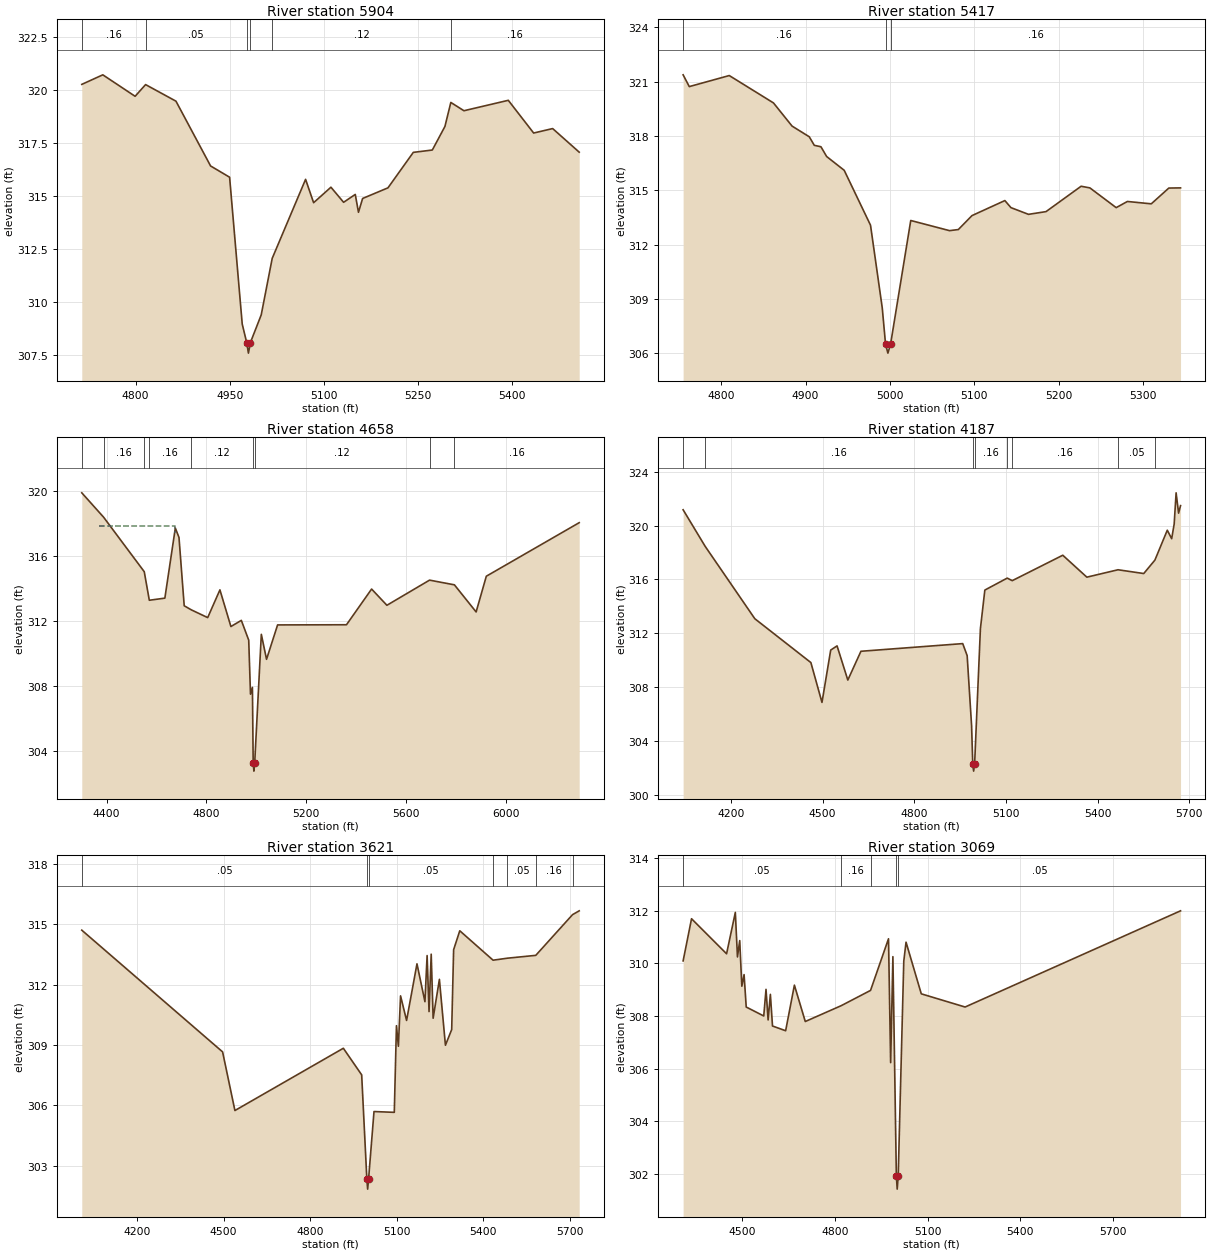
Type RM Length L Ch R = 1 ,5904    ,495,495,495
BEGIN DESCRIPTION:
UNT043 IN GIBB 9.0
END DESCRIPTION:
XS GIS Cut Line= 3
       3676341.1     10226398.95      3676242.11     10226341.64
      3675570.22     10226435.57
#Sta/Elev= 30
  4714.2  320.26  4747.7  320.71  4799.2   319.7  4815.9  320.25  4864.3  319.47
  4919.5  316.42  4949.8  315.89  4969.9  308.98    4977  308.11  4979.8  307.61
    4983  308.11  5000.2  309.41  5017.7  312.07  5070.9  315.79  5083.7  314.69
  5111.3  315.42  5131.5  314.71  5150.1  315.08  5155.2  314.24  5161.8  314.89
  5202.2  315.39  5242.6  317.06  5272.9  317.17    5293  318.28  5302.4  319.41
  5323.3  319.02    5394  319.51  5434.4  317.97  5464.7  318.18    5507  317.07
#Mann= 6 ,-1 , 0
  4714.2     .16       0  4815.9     .05       0    4977     .04       0
    4983     .05       0  5017.7     .12       0  5302.4     .16       0
Bank Sta=4977,4983
XS Rating Curve= 0 ,0
Exp/Cntr=0.3,0.1

Type RM Length L Ch R = 1 ,5417    ,750,750,750
BEGIN DESCRIPTION:
UNT043 IN GIBB 8.0
END DESCRIPTION:
XS GIS Cut Line= 3
      3676269.09     10225846.19      3676115.36     10225875.15
      3675698.79     10225994.63
#Sta/Elev= 30
  4754.8  321.37  4762.1  320.72  4809.5  321.33  4861.9  319.82    4884  318.54
  4904.4  317.95  4910.3  317.48  4918.2   317.4    4925  316.86  4945.8   316.1
    4977  313.07  4990.9  308.51  4994.8  306.51  4997.6  306.01  5000.8  306.51
  5024.7  313.33  5070.7  312.77  5081.1  312.83  5097.3   313.6  5136.3  314.43
  5143.5  314.04  5164.3  313.67  5185.1  313.82  5226.7  315.22  5237.1  315.13
  5268.3  314.04  5281.6  314.38  5309.9  314.25  5330.7  315.12  5344.6  315.13
#Mann= 3 ,-1 , 0
  4754.8     .16       0  4994.8     .07       0  5000.8     .16       0
Bank Sta=4994.8,5000.8
XS Rating Curve= 0 ,0
Exp/Cntr=0.3,0.1

Type RM Length L Ch R = 1 ,4658    ,471,471,471
BEGIN DESCRIPTION:
UNT043 IN GIBB 6.0
END DESCRIPTION:
XS GIS Cut Line= 3
      3676252.94     10224779.82      3675773.06     10225457.91
      3675536.98     10226596.06
#Sta/Elev= 30
  4300.5   319.9  4387.8   318.4  4550.8  315.04  4571.1  313.28  4633.4  313.41
  4675.3  317.73    4690  317.15  4710.9  312.94  4739.2  312.69    4805  312.21
    4854  313.92    4898  311.66  4939.8  312.04  4969.4  310.82  4976.5  307.49
  4984.2  307.91  4987.3  303.25  4990.1  302.75  4993.3  303.25  5019.9  311.18
  5040.8  309.64  5085.1  311.76  5361.1  311.77  5461.8  313.97  5523.1  312.97
    5694  314.52  5793.6  314.23  5880.6  312.56  5921.4  314.76  6293.6  318.06
#Mann= 9 ,-1 , 0
  4300.5     .05       0  4387.8     .16       0  4550.8     .12       0
  4571.1     .16       0  4739.2     .12       0  4987.3     .07       0
  4993.3     .12       0    5694     .05       0  5793.6     .16       0
#XS Ineff= 1 ,-1
  4369.7 4672.18  317.83
Permanent Ineff=
       F
Bank Sta=4987.3,4993.3
XS Rating Curve= 0 ,0
Exp/Cntr=0.3,0.1

Type RM Length L Ch R = 1 ,4187    ,566,566,566
BEGIN DESCRIPTION:
UNT043 IN GIBB 5.0
END DESCRIPTION:
XS GIS Cut Line= 3
      3676092.08     10224691.67      3675538.68     10225349.41
      3675066.49     10225955.89
#Sta/Elev= 30
  4043.5  321.17  4115.4  318.46  4278.2  313.07  4461.7  309.81    4498  306.85
  4526.6  310.74  4547.4  311.05  4582.6  308.51  4625.5  310.65  4958.7  311.22
  4973.2  310.33  4987.7  305.13  4991.6  302.24  4994.4  301.74  4997.6  302.24
  5016.6  312.33  5031.1   315.2  5104.4  316.09  5120.8   315.9  5286.2  317.79
    5365  316.16    5467  316.71  5551.3  316.43  5587.8  317.43  5628.3  319.65
  5642.7  319.02  5650.9  320.12  5657.2  322.43  5665.3  320.92  5671.7  321.48
#Mann= 8 ,-1 , 0
  4043.5     .05       0  4115.4     .16       0  4991.6     .07       0
  4997.6     .16       0  5104.4     .12       0  5120.8     .16       0
    5467     .05       0  5587.8     .16       0
Bank Sta=4991.6,4997.6
XS Rating Curve= 0 ,0
Exp/Cntr=0.3,0.1

Type RM Length L Ch R = 1 ,3621    ,552,552,552
BEGIN DESCRIPTION:
UNT043 IN GIBB 4.0
END DESCRIPTION:
XS GIS Cut Line= 3
      3675979.34     10224410.14       3675239.2     10225249.58
      3674836.34     10225700.09
#Sta/Elev= 30
  4008.6   314.7  4496.5  308.66  4539.2  305.75  4914.9  308.84  4978.4  307.52
  4996.3  302.35  4999.1  301.85  5002.3  302.35  5021.1   305.7  5091.4  305.66
  5098.9  309.96  5105.6  308.94  5113.1  311.44    5134  310.22    5170  313.03
  5197.6  311.15  5205.1  313.44  5211.8  310.66  5219.3  313.51    5226  310.33
  5247.7  312.26  5268.6  308.99  5290.3  309.77    5297  313.73  5318.3  314.67
  5433.7  313.21  5483.5  313.31  5581.6  313.45    5709  315.47  5732.1  315.66
#Mann= 7 ,-1 , 0
  4008.6     .05       0  4996.3     .03       0  5002.3     .05       0
  5433.7     .16       0  5483.5     .05       0  5581.6     .16       0
    5709     .05       0
Bank Sta=4996.3,5002.3
XS Rating Curve= 0 ,0
Exp/Cntr=0.3,0.1

Type RM Length L Ch R = 1 ,3069    ,783,783,783
BEGIN DESCRIPTION:
UNT043 IN GIBB 3.0
END DESCRIPTION:
XS GIS Cut Line= 3
      3675859.52      10224290.5      3675189.23     10224918.17
       3674704.3     10225409.19
#Sta/Elev= 30
  4309.8  310.09    4337  311.69  4450.3  310.36  4478.6  311.93  4485.5  310.24
  4492.8  310.86  4499.6  309.13  4506.9  309.57  4513.8  308.34  4570.5     308
  4577.8  309.01  4584.6  307.85  4591.9  308.82  4598.8  307.62  4641.3  307.44
  4669.6  309.17  4704.8  307.79  4820.8  308.39  4915.8  308.97  4973.9  310.93
  4980.8  306.23  4988.1  310.25  4999.3  301.93    5002  301.43  5005.3  301.93
  5023.3  310.08  5030.6   310.8  5079.9  308.84  5221.6  308.34  5918.2  311.99
#Mann= 5 ,-1 , 0
  4309.8     .05       0  4820.8     .16       0  4915.8     .05       0
  4999.3     .03       0  5005.3     .05       0
Bank Sta=4999.3,5005.3
XS Rating Curve= 0 ,0
Exp/Cntr=0.3,0.1

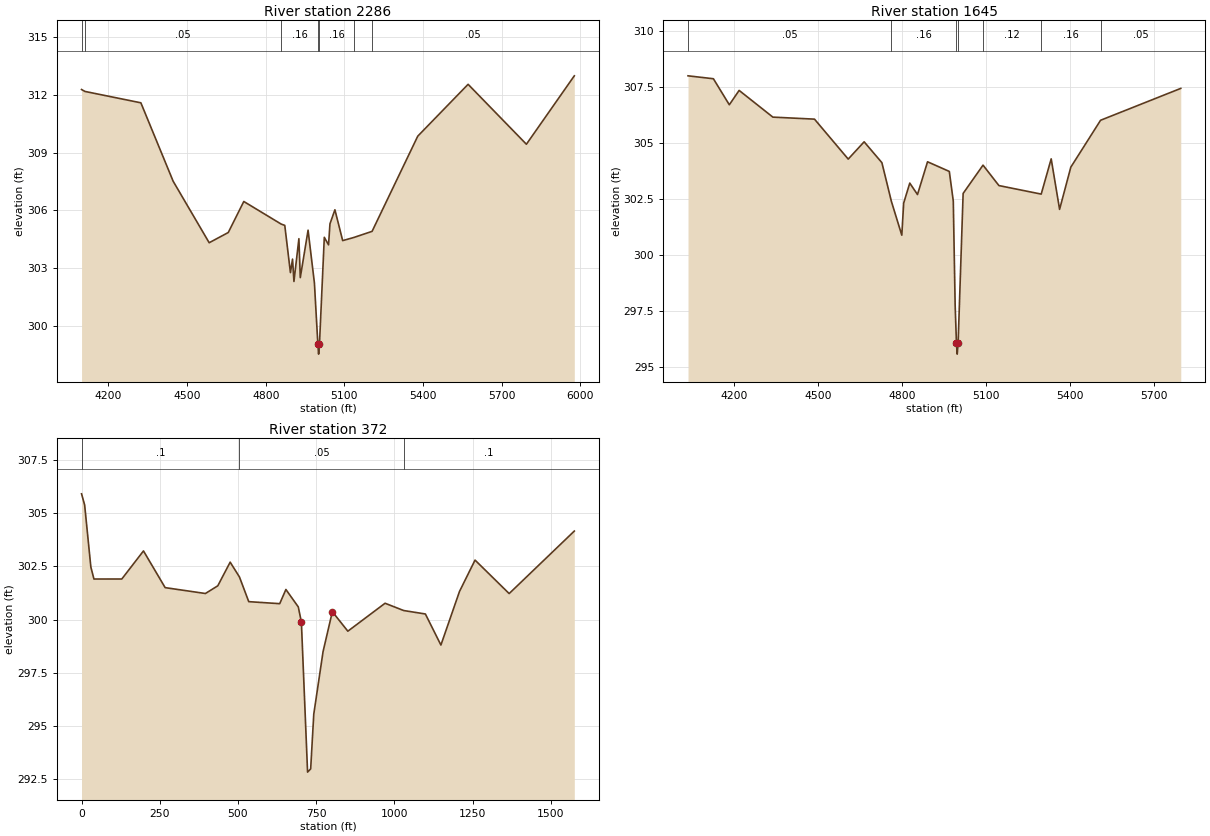
Type RM Length L Ch R = 1 ,2286    ,641,641,641
BEGIN DESCRIPTION:
UNT043 IN GIBB 2.0
END DESCRIPTION:
XS GIS Cut Line= 3
      3675712.27     10224047.33      3674744.41     10224433.61
      3674622.89     10225262.56
#Sta/Elev= 30
  4097.5  312.27  4110.5  312.17  4323.8  311.58    4447  307.51  4584.4  304.32
  4657.2  304.85  4716.5  306.46  4858.8  305.29  4872.8  305.22  4894.4  302.77
  4902.4  303.47  4907.8  302.31  4926.7  304.53    4932  302.51  4961.7  304.97
  4985.9  302.23  4999.1  299.04  5001.9  298.54  5005.1  299.04  5023.6   304.6
  5039.8  304.21  5045.2   305.3  5064.1  306.03  5093.7  304.43  5135.7  304.59
  5205.9  304.91  5380.2  309.85  5572.2  312.54  5794.6  309.43  5977.4  312.98
#Mann= 7 ,-1 , 0
  4097.5     .08       0  4110.5     .05       0  4858.8     .16       0
  4999.1     .07       0  5005.1     .16       0  5135.7      .1       0
  5205.9     .05       0
Bank Sta=4999.1,5005.1
XS Rating Curve= 0 ,0
Exp/Cntr=0.3,0.1

Type RM Length L Ch R = 1 ,1645    ,1270,1270,1270
BEGIN DESCRIPTION:
UNT043 IN GIBB 1.0
END DESCRIPTION:
XS GIS Cut Line= 3
      3675395.43     10223326.86      3674522.59     10224099.97
      3674488.34     10224693.98
#Sta/Elev= 30
  4034.3  307.99    4125  307.86  4181.9   306.7    4217  307.34  4337.5  306.15
  4486.3  306.06  4606.8  304.28  4663.7  305.05  4727.2  304.12    4761   302.4
  4798.3  300.89    4805  302.32  4826.8  303.21  4854.4   302.7  4890.3  304.16
  4968.1  303.73  4982.3  302.41    4989  297.75  4993.6  296.09  4996.3  295.59
  4999.6  296.09  5017.5  302.75  5088.6  304.01  5145.4   303.1  5296.5  302.72
  5332.2  304.29  5362.2  302.04  5402.3  303.92  5508.7  306.01  5795.3  307.43
#Mann= 7 ,-1 , 0
  4034.3     .05       0    4761     .16       0  4993.6     .07       0
  4999.6     .16       0  5088.6     .12       0  5296.5     .16       0
  5508.7     .05       0
Bank Sta=4993.6,4999.6
XS Rating Curve= 0 ,0
Exp/Cntr=0.3,0.1

Type RM Length L Ch R = 1 ,372     ,,,
XS GIS Cut Line= 3
        3675012.       10223053.        3674206.       10223232.
        3673682.       10223758.
#Sta/Elev= 30
       0305.90829.899687305.383129.69906302.473939.59875301.9059128.6959301.9063
197.9937303.2257267.2915301.5014395.9875301.2256435.5862301.5866475.1849302.6981
 504.884302.0013534.5831300.8429  633.58300.7476653.3793301.4143 692.978300.5962
702.8777299.8804722.6771292.8344732.5768292.9863742.4765 295.556772.1755298.4954
801.8746 300.371 851.412299.4551970.4423300.76751029.958300.42541099.392300.2636
1148.988 298.8041208.503301.32411258.099302.7953 1367.21301.22231575.513304.1582
#Mann= 3 ,-1 , 0
       0      .1       0 504.884     .05       01029.958      .1       0
Bank Sta=702.8777,801.8746
XS Rating Curve= 0 ,0
Exp/Cntr=0.3,0.1

Chan Stop Cuts=-1
Use User Specified Reach Order=0
Composite Channel Slope=5