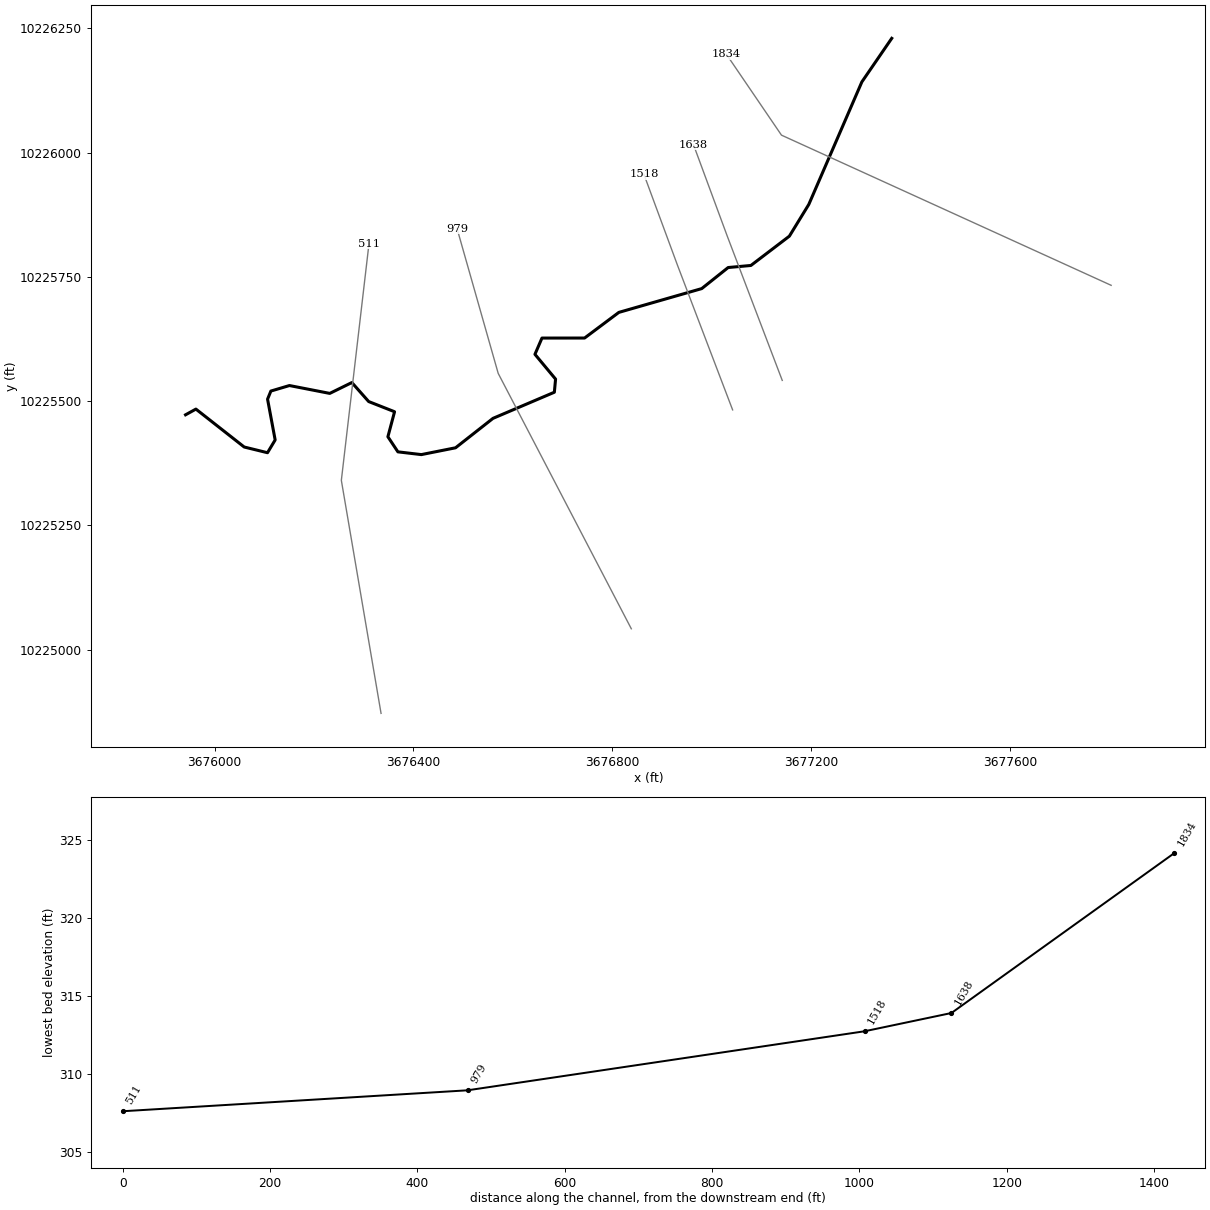
--- UNT044 IN GIBB.prj (project) ---

Proj Title=UNT044 IN GIBB Base Level Engineering
Current Plan=p01
Default Exp/Contr=0.3,0.1
English Units
Geom File=g01
Flow File=f01
Plan File=p01
Y Axis Title=Elevation
X Axis Title(PF)=Main Channel Distance
X Axis Title(XS)=Station
BEGIN DESCRIPTION:
UNT044 IN GIBB
END DESCRIPTION:
DSS Export Rating Curves= 0
DSS Export Rating Curve Sorted= 0
DSS Export Volume Flow Curves= 0
DXF OffsetX= 0
DXF OffsetY= 0
DXF ScaleX= 1
DXF ScaleY= 10

--- UNT044 IN GIBB.p01 (plan) ---

Plan Title=Multiple Run
Short Identifier=Multiple
Geom File=g01
Flow File=f01
Subcritical Flow
K Sum by GR= 0
Std Step Tol= 0.01
Critical Tol= 0.01
Num of Std Step Trials= 20
Max Error Tol= 0.3
Flow Tol Ratio= 0.001
Split Flow NTrial= 30
Split Flow Tol= 0.02
Split Flow Ratio= 0.02
Log Output Level= 0
Friction Slope Method= 1
Unsteady Friction Slope Method= 2
Unsteady Bridges Friction Slope Method= 1
Parabolic Critical Depth
Global Vel Dist=  1 , 1 , 1
Global Log Level= 0
CheckData=True
Encroach Param= -1, 0, 0, 0
BEGIN DESCRIPTION:
Multiple Run
END DESCRIPTION:

--- UNT044 IN GIBB.f01 (steady flow) ---

Flow Title=Multiple
Program Version=4.10
Number of Profiles= 7
Profile Names=10-year,25-year,50-year,1pct_min,100-year,1pct_plu,500-year
River Rch & RM=UNT044 IN GIBB,Reach-1         ,1834
     417     544     645     561     758    1025    1047
Boundary for River Rch & Prof#=UNT044 IN GIBB,Reach-1         , 1
Up Type= 0
Dn Type= 3
Dn Slope=0.005
Boundary for River Rch & Prof#=UNT044 IN GIBB,Reach-1         , 2
Up Type= 0
Dn Type= 3
Dn Slope=0.005
Boundary for River Rch & Prof#=UNT044 IN GIBB,Reach-1         , 3
Up Type= 0
Dn Type= 3
Dn Slope=0.005
Boundary for River Rch & Prof#=UNT044 IN GIBB,Reach-1         , 4
Up Type= 0
Dn Type= 3
Dn Slope=0.005
Boundary for River Rch & Prof#=UNT044 IN GIBB,Reach-1         , 5
Up Type= 0
Dn Type= 3
Dn Slope=0.005
Boundary for River Rch & Prof#=UNT044 IN GIBB,Reach-1         , 6
Up Type= 0
Dn Type= 3
Dn Slope=0.005
Boundary for River Rch & Prof#=UNT044 IN GIBB,Reach-1         , 7
Up Type= 0
Dn Type= 3
Dn Slope=0.005
DSS Import GetInterval= 0
DSS Import GetPeak= 0
DSS Import FillOption= 0

--- UNT044 IN GIBB.g01 (geometry) ---

Geom Title=Existing Conditions
Program Version=4.10

River Reach=UNT044 IN GIBB  ,Reach-1
Reach XY= 30
      3677362.36     10226229.85      3677302.26     10226142.22
      3677195.49     10225895.69      3677156.42     10225831.89
      3677079.02     10225772.92      3677033.26     10225768.77
       3676980.1     10225726.39      3676813.35     10225678.53
      3676744.44     10225626.94      3676658.71     10225626.88
      3676644.59     10225594.18      3676686.07     10225544.33
      3676683.64     10225517.91      3676560.22     10225465.36
      3676484.87     10225406.15      3676416.05     10225392.44
      3676368.91     10225397.98      3676348.75     10225428.35
      3676362.16     10225478.68      3676310.12     10225499.15
      3676276.26     10225537.39       3676231.8     10225515.56
       3676150.7     10225531.37      3676113.35     10225520.28
      3676106.69     10225503.96      3676121.97     10225421.92
      3676106.55     10225396.22       3676059.7      10225407.7
      3675962.54     10225483.99      3675941.71     10225472.51

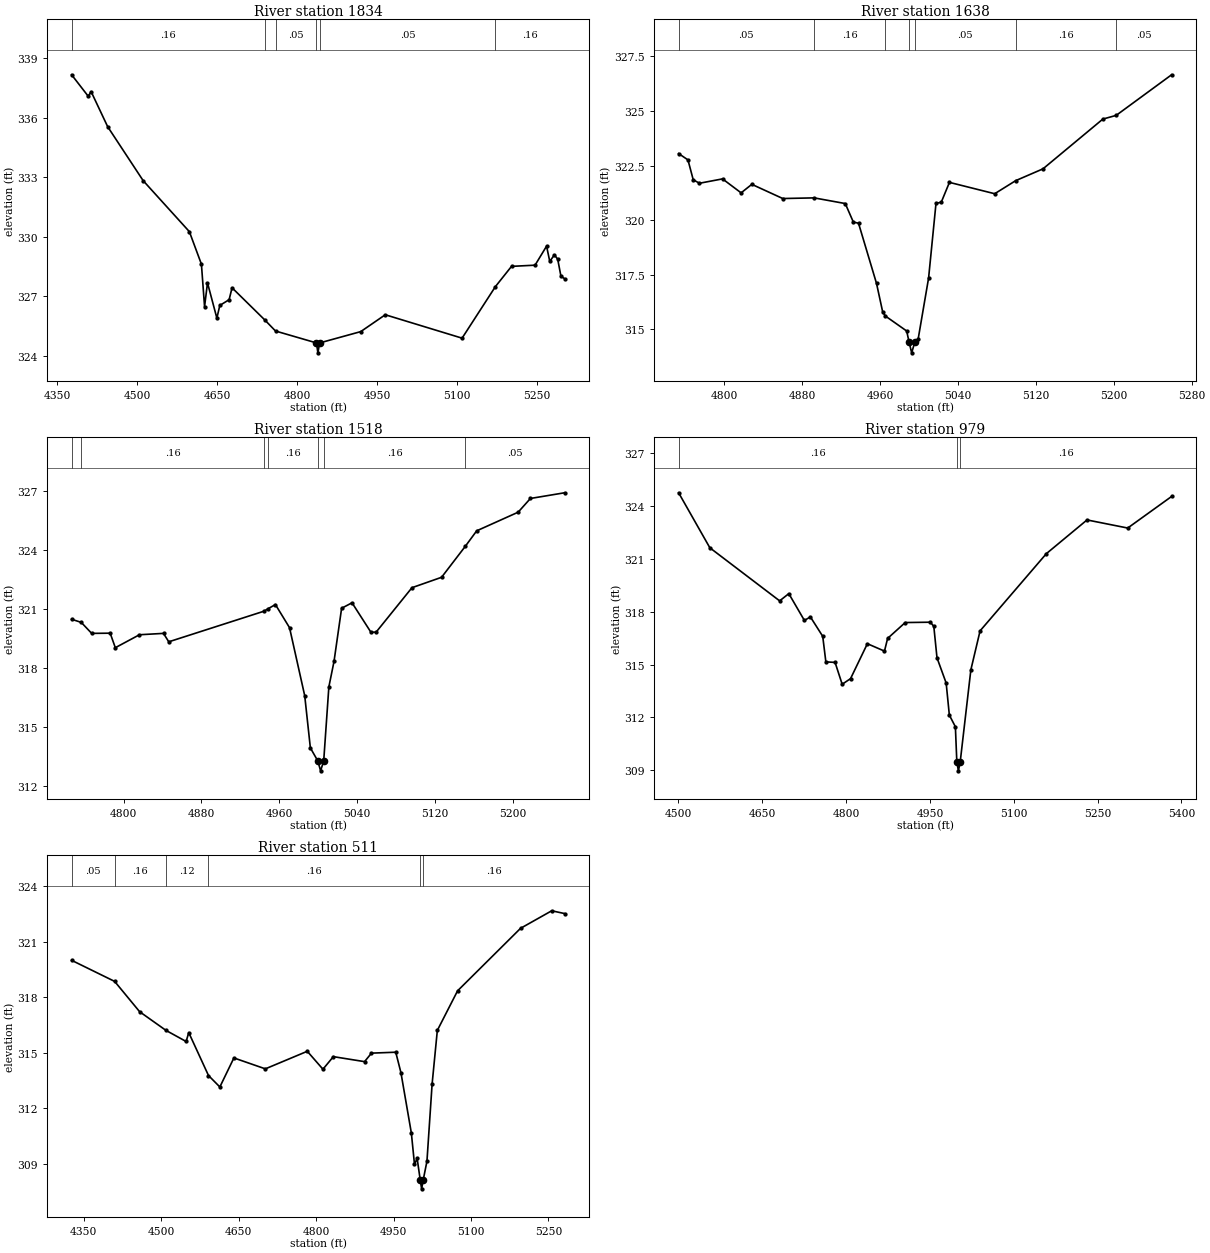
Type RM Length L Ch R = 1 ,1834    ,302,302,302
BEGIN DESCRIPTION:
UNT044 IN GIBB 4.0
END DESCRIPTION:
XS GIS Cut Line= 3
      3677803.75     10225732.99      3677140.54     10226035.09
      3677029.99     10226197.45
#Sta/Elev= 30
  4376.7  338.16  4407.8  337.08  4413.3  337.31  4444.4  335.54    4511  332.82
  4597.7  330.25  4620.3  328.61  4626.2  326.47  4631.7  327.67  4649.3  325.89
  4654.8  326.53  4672.3  326.82  4677.8  327.42  4738.8  325.81  4759.4  325.24
  4836.2  324.64  4838.9  324.14  4842.2  324.64  4919.3  325.21  4965.4  326.06
  5109.5  324.88  5172.1  327.48  5202.3   328.5  5246.5  328.56  5268.1  329.52
  5274.1  328.75  5282.8  329.08    5289  328.86  5295.1     328  5301.9  327.88
#Mann= 6 ,-1 , 0
  4376.7     .16       0  4738.8     .07       0  4759.4     .05       0
  4836.2    .033       0  4842.2     .05       0  5172.1     .16       0
Bank Sta=4836.2,4842.2
XS Rating Curve= 0 ,0
Exp/Cntr=0.3,0.1

Type RM Length L Ch R = 1 ,1638    ,118,118,118
BEGIN DESCRIPTION:
UNT044 IN GIBB 3.0
END DESCRIPTION:
XS GIS Cut Line= 3
      3677142.09     10225541.69      3677031.45     10225831.99
      3676963.64      10226015.6
#Sta/Elev= 30
  4752.9  323.05  4762.5  322.76  4767.9  321.85  4774.3  321.69    4798  321.89
  4817.1  321.25  4828.1  321.64  4859.9  320.99  4892.1  321.02  4924.1  320.76
  4932.4  319.91  4937.7  319.86  4956.2   317.1  4962.5   315.8  4965.2  315.61
  4987.2  314.92  4989.6  314.42  4992.3  313.92  4995.6  314.42    4999  314.56
  5009.7  317.35  5017.3  320.77  5022.7  320.82  5031.1  321.73  5077.6  321.21
  5099.2  321.81  5127.2  322.35  5188.7  324.63  5202.4   324.8  5259.3  326.66
#Mann= 7 ,-1 , 0
  4752.9     .05       0  4892.1     .16       0  4965.2     .05       0
  4989.6     .04       0  4995.6     .05       0  5099.2     .16       0
  5202.4     .05       0
Bank Sta=4989.6,4995.6
XS Rating Curve= 0 ,0
Exp/Cntr=0.3,0.1

Type RM Length L Ch R = 1 ,1518    ,539,539,539
BEGIN DESCRIPTION:
UNT044 IN GIBB 3.1
END DESCRIPTION:
XS GIS Cut Line= 3
      3677042.24     10225482.39      3676931.57     10225772.77
      3676863.75     10225956.39
#Sta/Elev= 30
  4746.7  320.48  4756.6  320.32  4767.3  319.76  4786.3  319.77  4791.6  319.03
  4816.4  319.69  4841.1  319.76  4846.5  319.33  4944.3  320.89  4948.3  321.01
  4956.1  321.23  4970.6  320.05  4986.2  316.58    4992  313.92  4999.7  313.25
  5002.5  312.75  5005.7  313.25    5011  317.03  5016.3  318.33  5024.1  321.04
  5034.8  321.32  5054.2  319.82  5059.5  319.82  5096.4  322.09  5126.8  322.62
  5151.2   324.2  5162.9  324.99  5205.5  325.94  5218.1  326.64  5253.2  326.93
#Mann= 7 ,-1 , 0
  4746.7     .05       0  4756.6     .16       0  4944.3     .05       0
  4948.3     .16       0  4999.7     .07       0  5005.7     .16       0
  5151.2     .05       0
Bank Sta=4999.7,5005.7
XS Rating Curve= 0 ,0
Exp/Cntr=0.3,0.1

Type RM Length L Ch R = 1 ,979     ,468,468,468
BEGIN DESCRIPTION:
UNT044 IN GIBB 2.0
END DESCRIPTION:
XS GIS Cut Line= 3
      3676838.44     10225042.07      3676570.64     10225555.88
      3676487.89     10225847.14
#Sta/Elev= 30
  4500.3  324.74  4556.2  321.62  4681.1  318.61  4697.5  319.02  4725.4   317.5
  4736.1   317.7  4758.2   316.6  4763.8  315.15  4780.3  315.12    4793  313.88
    4808   314.2  4838.1  316.18  4868.7  315.76  4874.3  316.48  4905.8  317.38
  4950.9   317.4    4957  317.16  4962.7  315.38  4979.1  313.95  4984.8  312.13
  4995.6  311.47  4998.2  309.47    5001  308.97  5004.2  309.47  5023.3   314.7
  5039.8  316.91  5158.5  321.29  5231.2   323.2    5304  322.74  5382.5  324.53
#Mann= 3 ,-1 , 0
  4500.3     .16       0  4998.2     .07       0  5004.2     .16       0
Bank Sta=4998.2,5004.2
XS Rating Curve= 0 ,0
Exp/Cntr=0.3,0.1

Type RM Length L Ch R = 1 ,511     ,0,0,0
BEGIN DESCRIPTION:
UNT044 IN GIBB 1.0
END DESCRIPTION:
XS GIS Cut Line= 3
      3676334.99     10224871.86      3676255.12     10225340.64
      3676310.68     10225816.37
#Sta/Elev= 30
  4326.7  319.99    4410  318.85  4458.4  317.21  4509.4   316.2  4548.4   315.6
  4553.5  316.08  4591.7  313.76  4613.7  313.14  4640.9  314.71  4701.8  314.12
    4783  315.07  4813.3   314.1  4833.5  314.78  4893.9  314.51  4907.3  314.97
  4954.3  315.02  4964.3  313.92  4984.5  310.65  4990.6  308.95  4995.7  309.28
  5001.6  308.13  5004.4  307.63  5007.6  308.13  5014.7  309.12  5024.7   313.3
  5034.8   316.2    5074  318.34  5195.9  321.72  5256.3  322.67  5281.2  322.52
#Mann= 6 ,-1 , 0
  4326.7     .05       0    4410     .16       0  4509.4     .12       0
  4591.7     .16       0  5001.6     .07       0  5007.6     .16       0
Bank Sta=5001.6,5007.6
XS Rating Curve= 0 ,0
Exp/Cntr=0.3,0.1
Stream Node=UNT044 IN GIBB  ,Reach-1         , 0 , 0 ,Upstream end
Stream Node=UNT044 IN GIBB  ,Reach-1         , 0 , 1 ,Downstream end

Chan Stop Cuts=-1
Use User Specified Reach Order=0
Composite Channel Slope=5