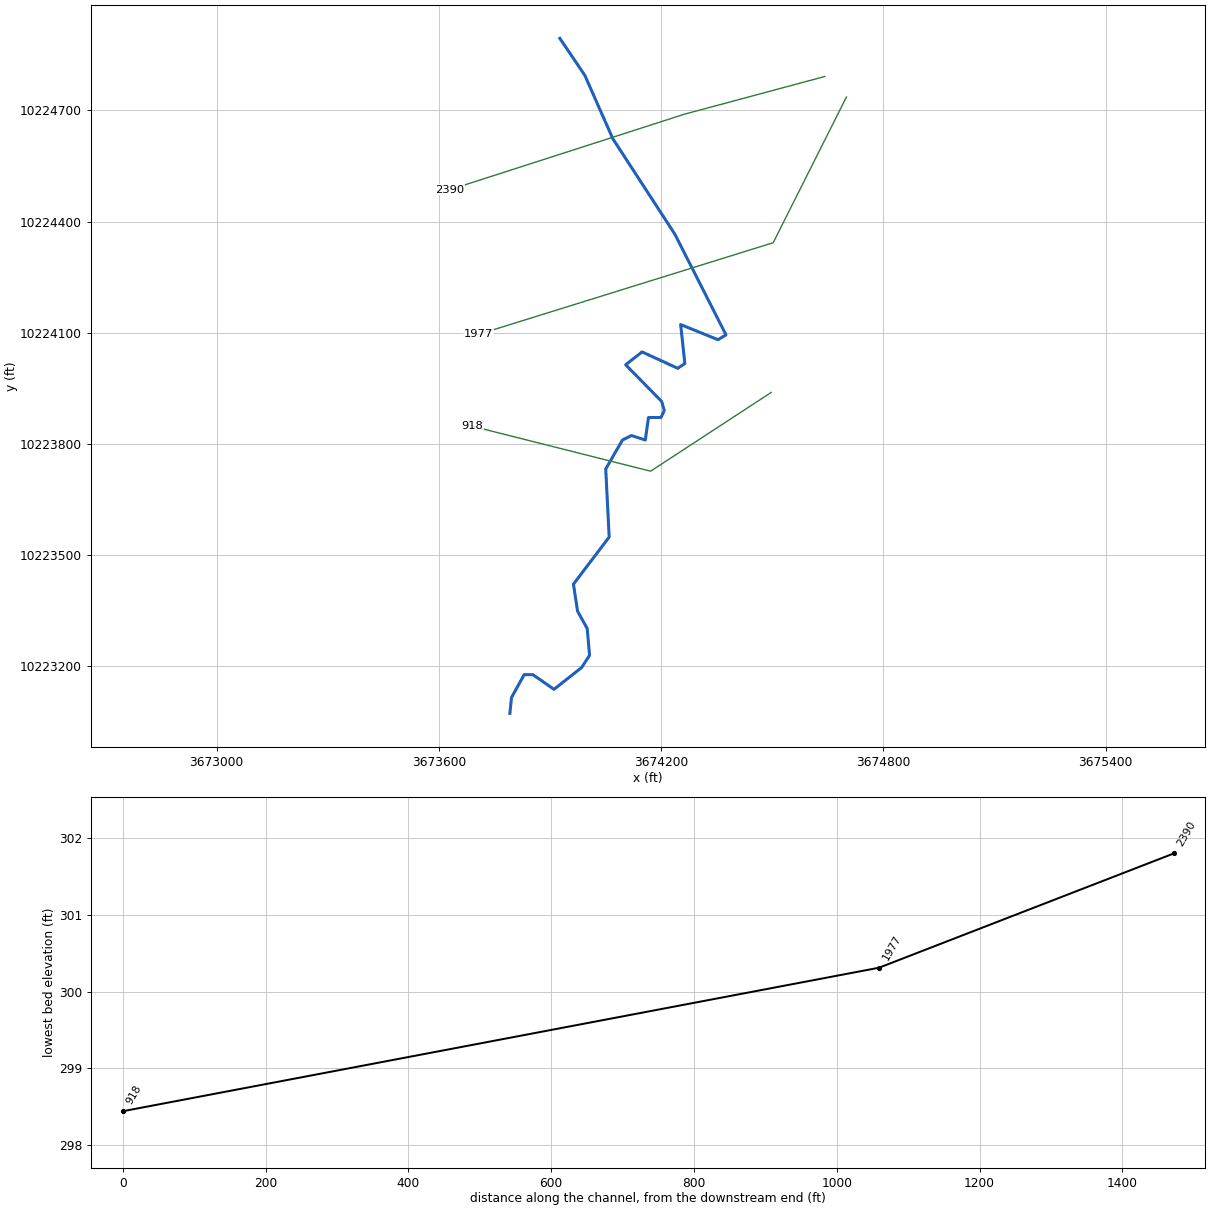
--- UNT045 IN GIBB.prj (project) ---

Proj Title=UNT045 IN GIBB Base Level Engineering
Current Plan=p01
Default Exp/Contr=0.3,0.1
English Units
Geom File=g01
Flow File=f01
Plan File=p01
Y Axis Title=Elevation
X Axis Title(PF)=Main Channel Distance
X Axis Title(XS)=Station
BEGIN DESCRIPTION:
UNT045 IN GIBB
END DESCRIPTION:
DSS Export Rating Curves= 0
DSS Export Rating Curve Sorted= 0
DSS Export Volume Flow Curves= 0
DXF OffsetX= 0
DXF OffsetY= 0
DXF ScaleX= 1
DXF ScaleY= 10

--- UNT045 IN GIBB.p01 (plan) ---

Plan Title=Multiple Run
Short Identifier=Multiple
Geom File=g01
Flow File=f01
Subcritical Flow
K Sum by GR= 0
Std Step Tol= 0.01
Critical Tol= 0.01
Num of Std Step Trials= 20
Max Error Tol= 0.3
Flow Tol Ratio= 0.001
Split Flow NTrial= 30
Split Flow Tol= 0.02
Split Flow Ratio= 0.02
Log Output Level= 0
Friction Slope Method= 1
Unsteady Friction Slope Method= 2
Unsteady Bridges Friction Slope Method= 1
Parabolic Critical Depth
Global Vel Dist=  1 , 1 , 1
Global Log Level= 0
CheckData=True
Encroach Param= -1, 0, 0, 0
BEGIN DESCRIPTION:
Multiple Run
END DESCRIPTION:

--- UNT045 IN GIBB.f01 (steady flow) ---

Flow Title=Multiple
Number of Profiles=7
Profile Names=10-year,25-year,50-year,1pct_min,100-year,1pct_plu,500-year
River Rch & RM= UNT045 IN GIBB,Reach-1,2390
     296     376     437     374     505     683     673
Boundary for River Rch & Prof#=UNT045 IN GIBB,Reach-1,1
Up Type=0
Dn Type=3
Dn Slope=0.005
Boundary for River Rch & Prof#=UNT045 IN GIBB,Reach-1,2
Up Type=0
Dn Type=3
Dn Slope=0.005
Boundary for River Rch & Prof#=UNT045 IN GIBB,Reach-1,3
Up Type=0
Dn Type=3
Dn Slope=0.005
Boundary for River Rch & Prof#=UNT045 IN GIBB,Reach-1,4
Up Type=0
Dn Type=3
Dn Slope=0.005
Boundary for River Rch & Prof#=UNT045 IN GIBB,Reach-1,5
Up Type=0
Dn Type=3
Dn Slope=0.005
Boundary for River Rch & Prof#=UNT045 IN GIBB,Reach-1,6
Up Type=0
Dn Type=3
Dn Slope=0.005
Boundary for River Rch & Prof#=UNT045 IN GIBB,Reach-1,7
Up Type=0
Dn Type=3
Dn Slope=0.005

--- UNT045 IN GIBB.g01 (geometry) ---

Geom Title=Existing Conditions
Program Version=4.10

River Reach=UNT045 IN GIBB  ,Reach-1
Reach XY= 30
      3673926.46     10224894.51      3673993.93     10224794.67
      3674069.45     10224623.66      3674236.98     10224365.85
        3674375.     10224094.15       3674353.3     10224081.13
      3674252.61     10224121.93      3674263.89     10224016.89
      3674244.79     10224003.87      3674148.44     10224048.14
      3674104.17     10224013.42      3674201.39     10223914.46
      3674208.34     10223890.15      3674199.65     10223871.06
       3674165.8     10223871.06      3674157.12     10223810.29
      3674119.79     10223822.45      3674095.49     10223810.29
      3674050.35     10223732.17      3674059.68     10223548.39
      3673963.22     10223421.24      3673974.36     10223348.26
      3674000.31     10223301.79      3674006.72     10223229.18
      3673985.23     10223196.13      3673910.69     10223137.41
       3673853.8     10223176.96      3673830.25     10223176.98
      3673795.97     10223115.29      3673791.71     10223072.51

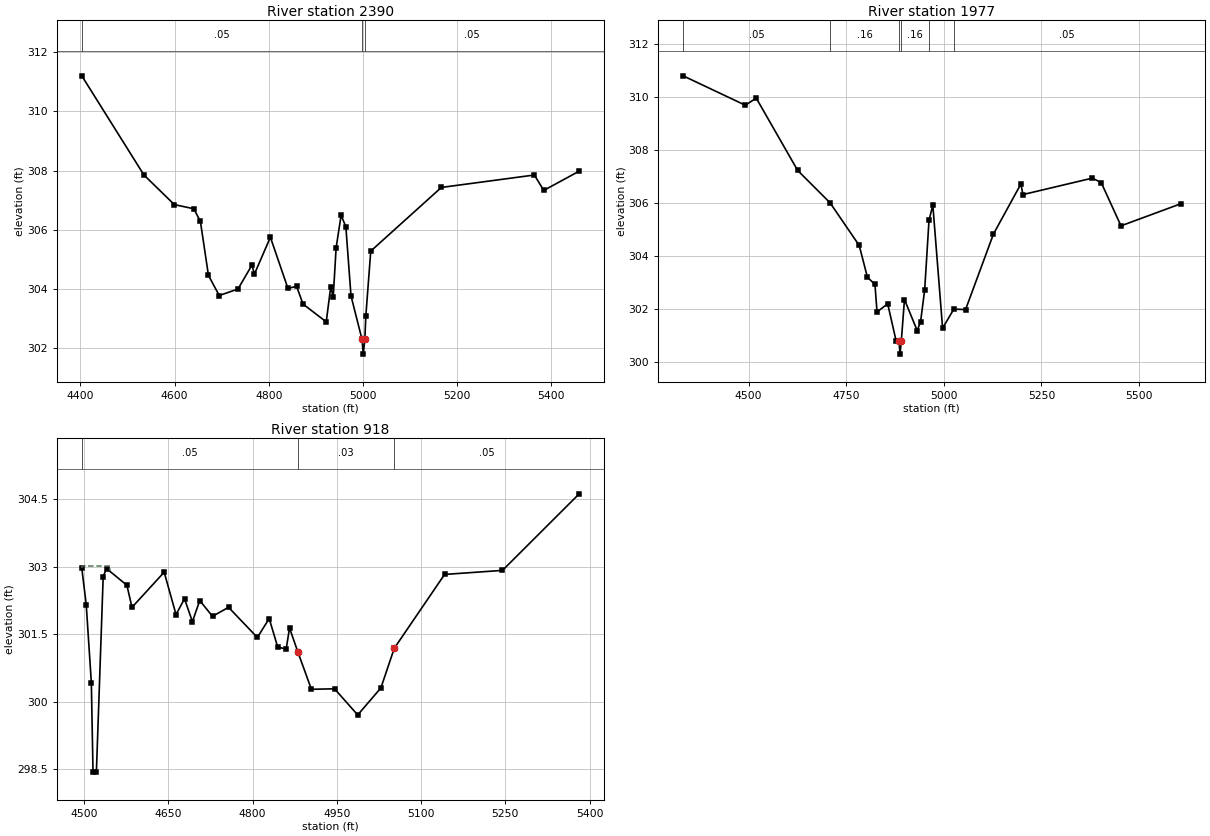
Type RM Length L Ch R = 1 ,2390    ,413,413,413
BEGIN DESCRIPTION:
UNT045 IN GIBB 1.0
END DESCRIPTION:
XS GIS Cut Line= 3
      3674642.09     10224791.64      3674262.64     10224689.68
       3673630.4     10224486.16
#Sta/Elev= 30
  4402.8   311.2  4534.9  307.85  4599.5  306.85  4640.9  306.71  4654.9  306.28
    4672  304.46  4694.9  303.78  4734.8     304  4764.5  304.81  4769.6   304.5
  4803.6  305.75  4840.9  304.02  4859.3  304.09    4873  303.49  4922.3  302.89
  4931.9  304.08  4937.1  303.72  4943.3  305.39  4953.9  306.49    4964   306.1
  4974.9  303.77  4998.3   302.3    5001   301.8  5004.3   302.3  5006.5   303.1
  5016.9  305.28  5166.9  307.43  5364.6  307.85  5384.6  307.33  5459.9  307.98
#Mann= 3 ,-1 , 0
  4402.8     .05       0  4998.3     .03       0  5004.3     .05       0
Bank Sta=4998.3,5004.3
XS Rating Curve= 0 ,0
Exp/Cntr=0.3,0.1

Type RM Length L Ch R = 1 ,1977    ,1059,1059,1059
BEGIN DESCRIPTION:
UNT045 IN GIBB 1.1
END DESCRIPTION:
XS GIS Cut Line= 3
      3674700.08     10224736.16      3674502.38     10224342.88
      3673706.47     10224095.32
#Sta/Elev= 30
  4332.6  310.81  4491.9   309.7  4519.8  309.97  4625.9  307.24  4708.8  306.02
  4783.5  304.41  4804.5  303.21  4823.8  302.94  4829.1   301.9  4856.4  302.21
  4877.8  300.82  4885.3  300.81    4888  300.31  4891.3  300.81  4899.4  302.37
  4931.9   301.2  4940.6  301.53  4951.1  302.73  4962.2  305.36    4972  305.93
    4997  301.29  5025.8  302.01  5055.8  301.99  5127.2  304.84  5197.5  306.73
  5202.7  306.33  5380.5  306.95  5403.2  306.78  5453.8  305.15  5606.3  305.98
#Mann= 6 ,-1 , 0
  4332.6     .05       0  4708.8     .16       0  4885.3     .07       0
  4891.3     .16       0  4962.2     .12       0  5025.8     .05       0
Bank Sta=4885.3,4891.3
XS Rating Curve= 0 ,0
Exp/Cntr=0.3,0.1

Type RM Length L Ch R = 1 ,918     ,0,0,0
BEGIN DESCRIPTION:
UNT045 IN GIBB 1.2
END DESCRIPTION:
XS GIS Cut Line= 3
        3674497.      10223938.8       3674171.5     10223726.14
       3673689.7     10223847.68
#Sta/Elev= 30
  4495.9  302.97  4503.8  302.16  4512.9  300.43  4515.9  298.44  4521.9  298.44
    4534  302.78    4540  302.96  4576.2  302.59  4585.3   302.1  4642.6  302.88
  4663.7  301.94  4678.8  302.29  4692.9  301.78  4705.9  302.25  4728.7   301.9
  4757.2   302.1  4808.5  301.43  4829.6  301.85  4844.7  301.22  4859.8  301.17
  4865.8  301.64  4880.9   301.1  4904.7  300.28    4946  300.29  4987.2  299.71
  5028.5  300.31  5052.3  301.19  5141.9  302.83    5245  302.92  5381.6  304.62
#Mann= 3 , 0 , 0
  4495.9     .05       0  4880.9     .03       0  5052.3     .05       0
#XS Ineff= 2 , 0
         4545.85  303.01
Permanent Ineff=
       F       F
Bank Sta=4880.9,5052.3
XS Rating Curve= 0 ,0
Exp/Cntr=0.3,0.1

Chan Stop Cuts=-1
Use User Specified Reach Order=0
Composite Channel Slope=5