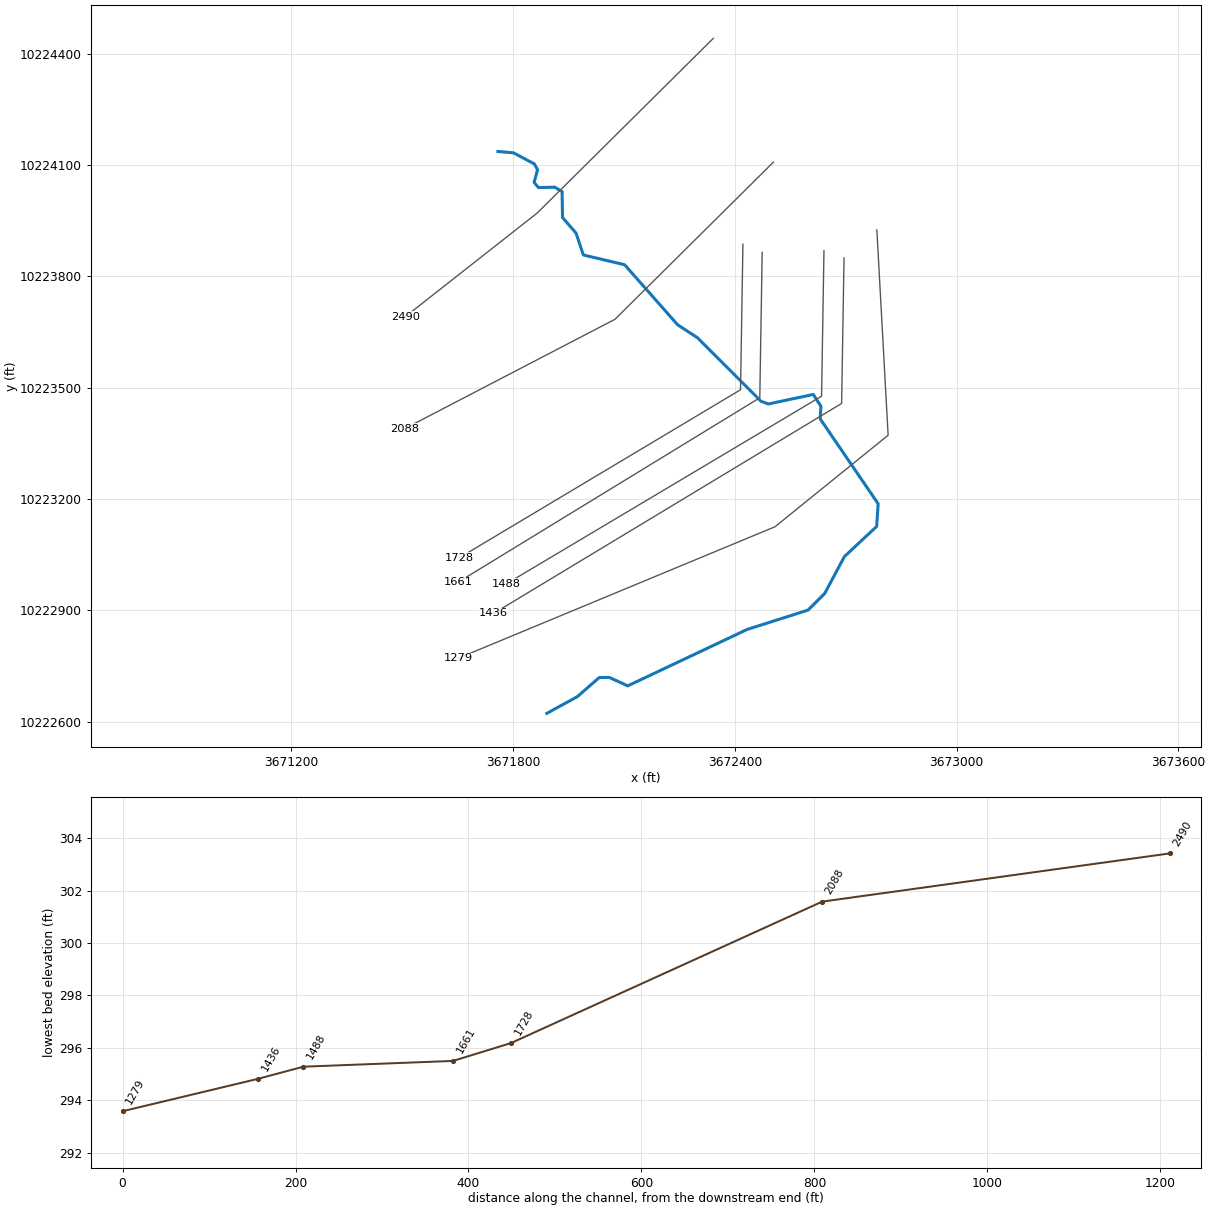
--- UNT046 IN GIBB.prj (project) ---

Proj Title=UNT046 IN GIBB Base Level Engineering
Current Plan=p01
Default Exp/Contr=0.3,0.1
English Units
Geom File=g01
Flow File=f01
Plan File=p01
Y Axis Title=Elevation
X Axis Title(PF)=Main Channel Distance
X Axis Title(XS)=Station
BEGIN DESCRIPTION:
UNT046 IN GIBB
END DESCRIPTION:
DSS Export Rating Curves= 0
DSS Export Rating Curve Sorted= 0
DSS Export Volume Flow Curves= 0
DXF OffsetX= 0
DXF OffsetY= 0
DXF ScaleX= 1
DXF ScaleY= 10

--- UNT046 IN GIBB.p01 (plan) ---

Plan Title=Multiple Run
Short Identifier=Multiple
Geom File=g01
Flow File=f01
Subcritical Flow
K Sum by GR= 0
Std Step Tol= 0.01
Critical Tol= 0.01
Num of Std Step Trials= 20
Max Error Tol= 0.3
Flow Tol Ratio= 0.001
Split Flow NTrial= 30
Split Flow Tol= 0.02
Split Flow Ratio= 0.02
Log Output Level= 0
Friction Slope Method= 1
Unsteady Friction Slope Method= 2
Unsteady Bridges Friction Slope Method= 1
Parabolic Critical Depth
Global Vel Dist=  1 , 1 , 1
Global Log Level= 0
CheckData=True
Encroach Param= -1, 0, 0, 0
BEGIN DESCRIPTION:
Multiple Run
END DESCRIPTION:

--- UNT046 IN GIBB.f01 (steady flow) ---

Flow Title=Multiple
Number of Profiles=7
Profile Names=10-year,25-year,50-year,1pct_min,100-year,1pct_plu,500-year
River Rch & RM= UNT046 IN GIBB,Reach-1,2490
     294     375     438     376     509     688     684
Boundary for River Rch & Prof#=UNT046 IN GIBB,Reach-1,1
Up Type=0
Dn Type=3
Dn Slope=0.005
Boundary for River Rch & Prof#=UNT046 IN GIBB,Reach-1,2
Up Type=0
Dn Type=3
Dn Slope=0.005
Boundary for River Rch & Prof#=UNT046 IN GIBB,Reach-1,3
Up Type=0
Dn Type=3
Dn Slope=0.005
Boundary for River Rch & Prof#=UNT046 IN GIBB,Reach-1,4
Up Type=0
Dn Type=3
Dn Slope=0.005
Boundary for River Rch & Prof#=UNT046 IN GIBB,Reach-1,5
Up Type=0
Dn Type=3
Dn Slope=0.005
Boundary for River Rch & Prof#=UNT046 IN GIBB,Reach-1,6
Up Type=0
Dn Type=3
Dn Slope=0.005
Boundary for River Rch & Prof#=UNT046 IN GIBB,Reach-1,7
Up Type=0
Dn Type=3
Dn Slope=0.005

--- UNT046 IN GIBB.g01 (geometry) ---

Geom Title=Existing Conditions
Program Version=4.10

River Reach=UNT046 IN GIBB  ,Reach-1
Reach XY= 30
      3671759.53     10224136.81      3671801.66       10224133.
      3671858.15     10224103.08      3671866.61     10224087.36
      3671857.25      10224053.4      3671869.08     10224039.32
      3671912.84     10224040.48        3671933.     10224028.69
      3671934.15     10223958.71      3671970.72     10223916.64
      3671990.43     10223857.86      3672102.16     10223831.49
      3672245.59     10223669.61      3672299.13     10223634.76
      3672471.32     10223463.46      3672490.96     10223456.27
       3672612.4     10223481.95      3672632.93     10223450.44
      3672631.28      10223415.9      3672787.89     10223187.37
      3672783.92     10223126.28      3672696.64     10223045.06
      3672643.44      10222945.8      3672598.36     10222900.83
      3672433.33     10222848.59      3672110.68     10222696.69
      3672060.33     10222719.47      3672033.38     10222719.04
      3671974.55      10222667.8      3671891.71     10222622.51

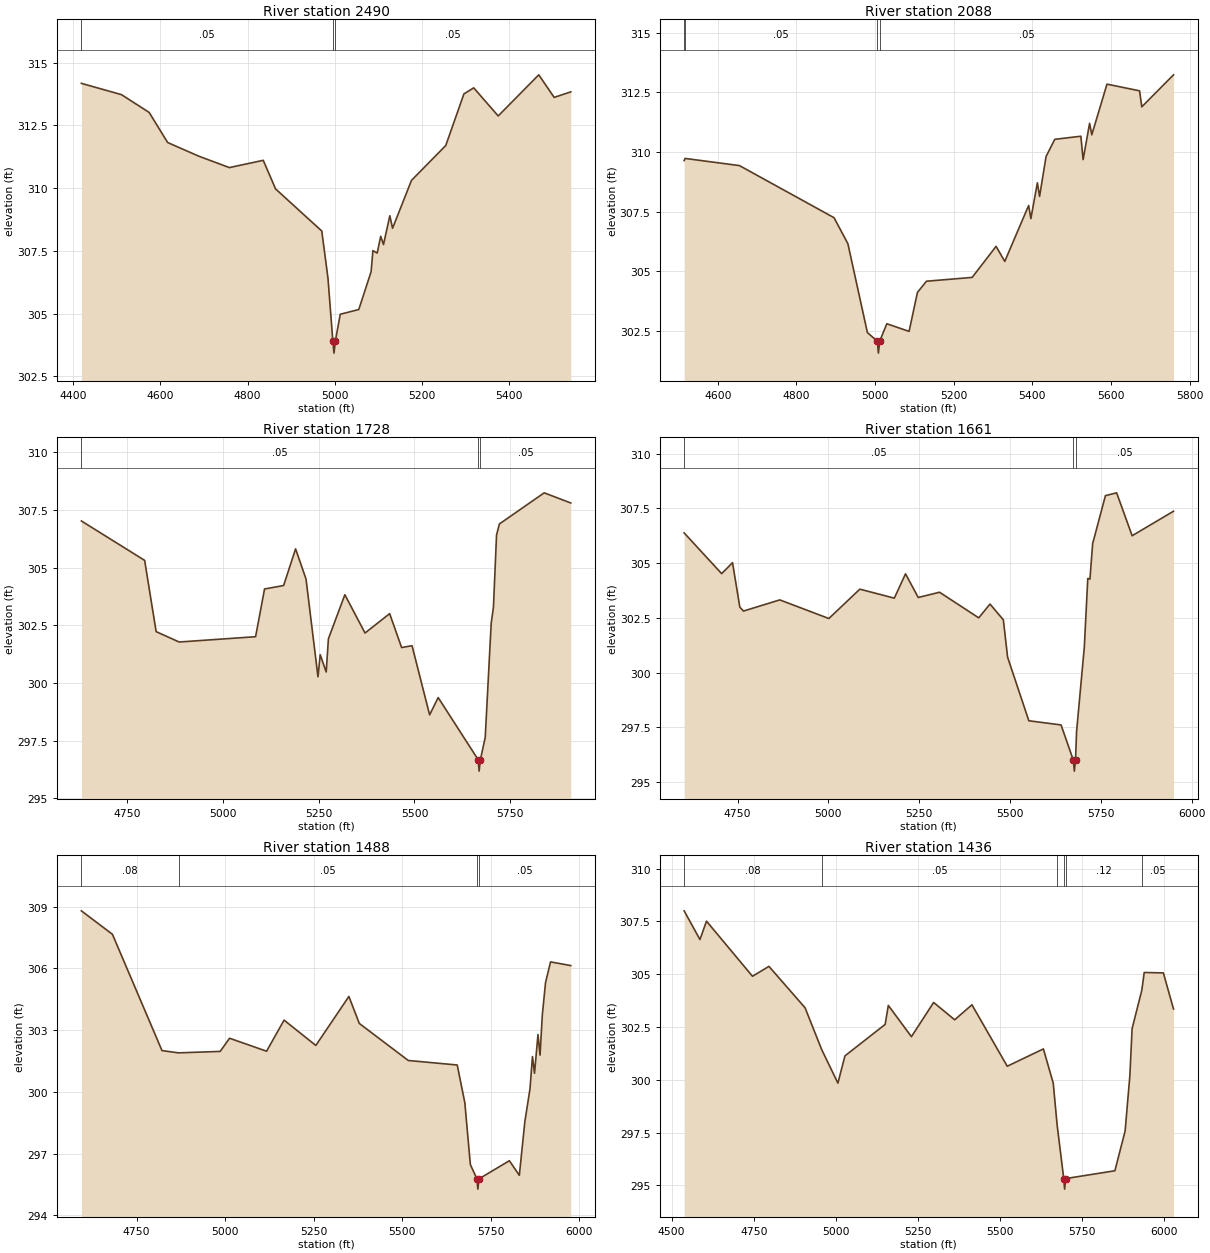
Type RM Length L Ch R = 1 ,2490    ,402,402,402
BEGIN DESCRIPTION:
UNT046 IN GIBB 7.0
END DESCRIPTION:
XS GIS Cut Line= 3
      3672342.09     10224441.63      3671865.52     10223970.75
      3671509.03     10223691.66
#Sta/Elev= 30
  4418.9  314.18  4510.8  313.73  4574.4  313.02  4616.8  311.82  4687.6  311.28
  4758.3  310.82  4836.1  311.11  4864.4  309.97  4970.4  308.29  4984.6  306.41
  4995.7  303.92  4998.4  303.42  5001.7  303.92  5012.8  304.97  5055.3  305.16
  5083.6  306.67  5087.7  307.51  5097.5  307.41  5105.6  308.08    5112  307.75
  5126.5   308.9  5132.8   308.4  5176.2  310.31  5254.8   311.7  5296.5  313.76
    5319     314  5375.1  312.88  5468.2  314.52  5503.5  313.62  5541.6  313.84
#Mann= 3 ,-1 , 0
  4418.9     .05       0  4995.7     .03       0  5001.7     .05       0
Bank Sta=4995.7,5001.7
XS Rating Curve= 0 ,0
Exp/Cntr=0.3,0.1

Type RM Length L Ch R = 1 ,2088    ,360,360,360
BEGIN DESCRIPTION:
UNT046 IN GIBB 6.0
END DESCRIPTION:
XS GIS Cut Line= 3
      3672504.64       10224108.      3672075.98     10223684.46
      3671506.14      10223389.2
#Sta/Elev= 30
  4514.5  309.64    4517  309.73  4655.2  309.43  4895.6  307.25  4930.9  306.16
  4980.5  302.44  5005.7  302.08  5008.5  301.58  5011.7  302.08  5029.9  302.81
  5086.5  302.49  5107.7  304.12  5130.6  304.59  5246.9  304.75  5307.7  306.05
  5329.8  305.42  5390.5  307.76  5396.2  307.21  5412.7  308.71  5418.3  308.14
  5434.8  309.81  5456.9  310.53  5523.3  310.66    5529  309.68  5545.5   311.2
  5551.1  310.72  5589.7  312.84  5672.6  312.56  5678.2  311.89  5758.9  313.23
#Mann= 4 ,-1 , 0
  4514.5     .08       0    4517     .05       0  5005.7     .03       0
  5011.7     .05       0
Bank Sta=5005.7,5011.7
XS Rating Curve= 0 ,0
Exp/Cntr=0.3,0.1

Type RM Length L Ch R = 1 ,1728    ,67,67,67
BEGIN DESCRIPTION:
UNT046 IN GIBB 5.0
END DESCRIPTION:
XS GIS Cut Line= 3
      3672422.14     10223886.62      3672415.68     10223494.62
      3671655.78     10223042.26
#Sta/Elev= 30
  4631.3  307.03  4796.3  305.32  4826.3  302.23  4886.3  301.78  5085.7  302.01
    5109  304.08  5158.8  304.23    5190  305.82  5217.2  304.51  5248.4  300.27
  5254.2  301.23  5269.8  300.48  5275.6  301.92  5318.5  303.83  5371.1  302.17
  5435.3  303.01  5466.5  301.54  5493.7  301.62  5539.6  298.62  5561.9  299.37
    5666  296.68  5668.7  296.18    5672  296.68  5684.6  297.64  5700.2   302.6
    5706  303.28  5714.1  306.42  5721.6   306.9  5838.4  308.25  5907.7  307.81
#Mann= 3 ,-1 , 0
  4631.3     .05       0    5666     .03       0    5672     .05       0
Bank Sta=5666,5672
XS Rating Curve= 0 ,0
Exp/Cntr=0.3,0.1

Type RM Length L Ch R = 1 ,1661    ,173,173,173
BEGIN DESCRIPTION:
UNT046 IN GIBB 4.0
END DESCRIPTION:
XS GIS Cut Line= 3
      3672474.22     10223864.87      3672467.76     10223472.92
      3671651.95     10222976.08
#Sta/Elev= 30
  4602.9  306.38  4706.1  304.52  4736.1  305.02  4756.2  302.99  4766.2  302.81
  4866.2  303.32  5001.3  302.47  5086.6  303.81  5181.5   303.4  5212.3  304.51
  5247.4  303.43    5306  303.67  5413.9   302.5  5444.9  303.13  5481.6  302.41
  5493.4   300.7  5551.8   297.8  5640.5  297.61  5674.3     296  5677.1   295.5
  5680.3     296  5683.2   297.3  5704.5  301.16  5714.1   304.3    5720  304.27
  5727.5  305.89  5762.6  308.08  5793.5  308.21  5836.2  306.25  5950.1  307.37
#Mann= 3 ,-1 , 0
  4602.9     .05       0  5674.3     .03       0  5680.3     .05       0
Bank Sta=5674.3,5680.3
XS Rating Curve= 0 ,0
Exp/Cntr=0.3,0.1

Type RM Length L Ch R = 1 ,1488    ,52,52,52
BEGIN DESCRIPTION:
UNT046 IN GIBB 3.0
END DESCRIPTION:
XS GIS Cut Line= 3
      3672641.33     10223869.28      3672634.86     10223477.26
      3671782.98     10222972.05
#Sta/Elev= 30
  4593.9   308.8  4681.6  307.66  4821.6  302.01  4868.3   301.9    4986  301.97
  5012.5  302.61  5117.1  301.98  5166.5  303.49  5256.2  302.26  5349.6  304.64
    5379  303.33  5517.3  301.53  5655.7  301.31  5677.1  299.48  5692.8  296.47
  5711.2  295.78  5713.9  295.28  5717.2  295.78    5803  296.66  5831.1  295.95
  5846.7  298.56  5861.2  300.15  5868.2  301.72    5874  300.91  5883.8  302.79
  5889.6  301.79    5896  303.73  5905.2  305.32  5919.3  306.32  5976.4  306.14
#Mann= 4 ,-1 , 0
  4593.9     .08       0  4868.3     .05       0  5711.2     .03       0
  5717.2     .05       0
Bank Sta=5711.2,5717.2
XS Rating Curve= 0 ,0
Exp/Cntr=0.3,0.1

Type RM Length L Ch R = 1 ,1436    ,157,157,157
BEGIN DESCRIPTION:
UNT046 IN GIBB 2.0
END DESCRIPTION:
XS GIS Cut Line= 3
      3672695.58     10223849.71      3672689.12     10223457.73
      3671748.24     10222892.18
#Sta/Elev= 30
    4538     308  4586.1  306.64  4606.1  307.51  4746.1   304.9  4796.1  305.37
  4906.1  303.41  4956.7  301.43  5006.1  299.84  5027.5  301.13  5149.9  302.62
  5159.6  303.52  5229.9  302.04  5297.5  303.66  5361.6  302.84  5414.1  303.55
  5521.6  300.64  5631.7  301.46  5661.6  299.84  5673.6  297.84  5693.6  295.32
  5696.3  294.82  5699.6  295.32  5849.3  295.69  5880.4  297.57  5894.9  300.19
  5901.7  302.42  5931.3  304.24  5938.6  305.08  5996.9  305.06  6027.8  303.35
#Mann= 6 ,-1 , 0
    4538     .08       0  4956.7     .05       0  5673.6     .12       0
  5693.6     .03       0  5699.6     .12       0  5931.3     .05       0
Bank Sta=5693.6,5699.6
XS Rating Curve= 0 ,0
Exp/Cntr=0.3,0.1

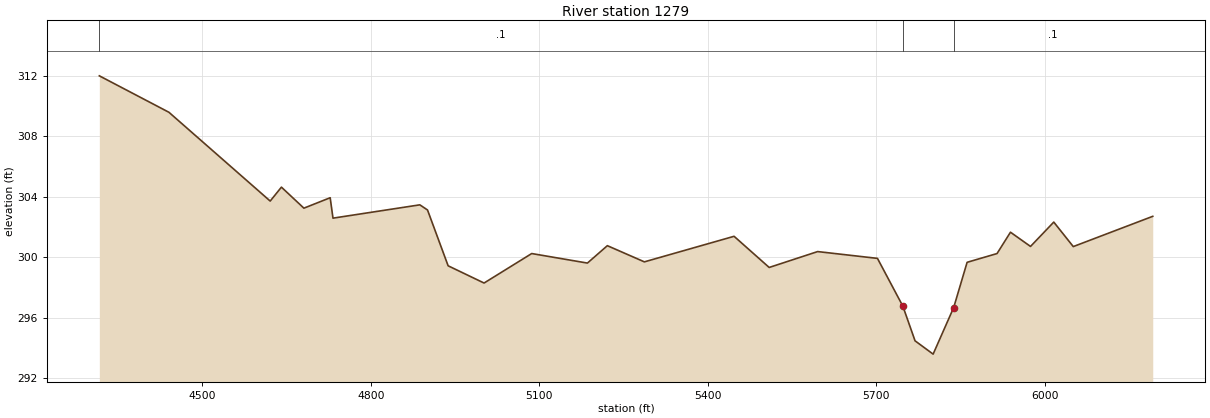
Type RM Length L Ch R = 1 ,1279    ,0,0,0
BEGIN DESCRIPTION:
UNT046 IN GIBB 1.0
END DESCRIPTION:
XS GIS Cut Line= 4
       3672784.4     10223925.34      3672814.89     10223372.04
      3672508.97     10223125.47        3671651.     10222770.65
#Sta/Elev= 30
  4316.7  311.98  4440.6  309.57  4620.9   303.7  4640.9  304.62  4680.9  303.23
  4727.7  303.92  4732.7  302.57  4887.3  303.45    4901  303.11  4937.7  299.42
  5001.7  298.28  5086.5  300.23  5185.7   299.6  5221.2  300.75  5287.1  299.68
  5446.8  301.37  5509.3  299.31  5595.6  300.36  5702.1  299.91  5747.3  296.75
    5769  294.46  5801.2  293.58  5837.8  296.66  5861.7  299.65    5915  300.23
  5938.9  301.64  5974.6   300.7    6016  302.31  6050.7  300.69  6192.2  302.69
#Mann= 3 , 0 , 0
  4316.7      .1       0  5747.3     .07       0  5837.8      .1       0
#XS Ineff= 2 , 0
         5447.87  301.25
Permanent Ineff=
       F       F
Bank Sta=5747.3,5837.8
XS Rating Curve= 0 ,0
Exp/Cntr=0.3,0.1

Chan Stop Cuts=-1
Use User Specified Reach Order=0
Composite Channel Slope=5