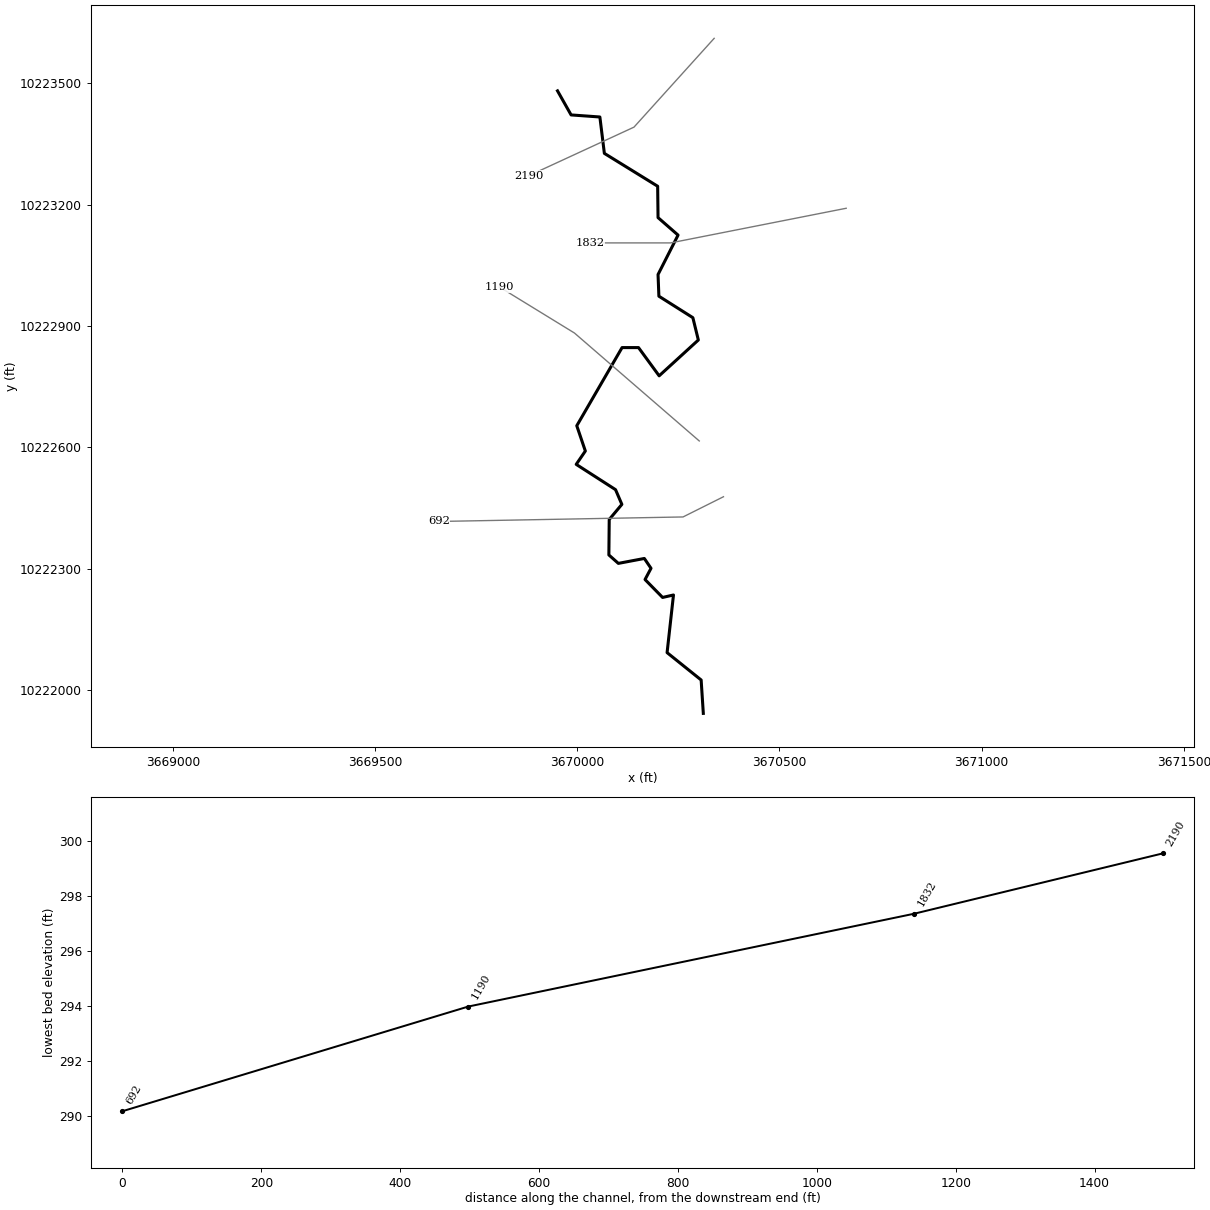
--- UNT047 IN GIBB.prj (project) ---

Proj Title=UNT047 IN GIBB Base Level Engineering
Current Plan=p01
Default Exp/Contr=0.3,0.1
English Units
Geom File=g01
Flow File=f01
Plan File=p01
BEGIN DESCRIPTION:
UNT047 IN GIBB
END DESCRIPTION:

--- UNT047 IN GIBB.p01 (plan) ---

Plan Title=Multiple Run
Short Identifier=Multiple
Geom File=g01
Flow File=f01
Subcritical Flow
K Sum by GR= 0
Std Step Tol= 0.01
Critical Tol= 0.01
Num of Std Step Trials= 20
Max Error Tol= 0.3
Flow Tol Ratio= 0.001
Split Flow NTrial= 30
Split Flow Tol= 0.02
Split Flow Ratio= 0.02
Log Output Level= 0
Friction Slope Method= 1
Unsteady Friction Slope Method= 2
Unsteady Bridges Friction Slope Method= 1
Parabolic Critical Depth
Global Vel Dist=  1 , 1 , 1
Global Log Level= 0
CheckData=True
Encroach Param= -1, 0, 0, 0
BEGIN DESCRIPTION:
Multiple Run
END DESCRIPTION:

--- UNT047 IN GIBB.f01 (steady flow) ---

Flow Title=Multiple
Number of Profiles=7
Profile Names=10-year,25-year,50-year,1pct_min,100-year,1pct_plu,500-year
River Rch & RM= UNT047 IN GIBB,Reach-1,2190
     175     215     246     206     279     378     359
Boundary for River Rch & Prof#=UNT047 IN GIBB,Reach-1,1
Up Type=0
Dn Type=3
Dn Slope=0.005
Boundary for River Rch & Prof#=UNT047 IN GIBB,Reach-1,2
Up Type=0
Dn Type=3
Dn Slope=0.005
Boundary for River Rch & Prof#=UNT047 IN GIBB,Reach-1,3
Up Type=0
Dn Type=3
Dn Slope=0.005
Boundary for River Rch & Prof#=UNT047 IN GIBB,Reach-1,4
Up Type=0
Dn Type=3
Dn Slope=0.005
Boundary for River Rch & Prof#=UNT047 IN GIBB,Reach-1,5
Up Type=0
Dn Type=3
Dn Slope=0.005
Boundary for River Rch & Prof#=UNT047 IN GIBB,Reach-1,6
Up Type=0
Dn Type=3
Dn Slope=0.005
Boundary for River Rch & Prof#=UNT047 IN GIBB,Reach-1,7
Up Type=0
Dn Type=3
Dn Slope=0.005

--- UNT047 IN GIBB.g01 (geometry) ---

Geom Title=Existing Conditions

River Reach=UNT047 IN GIBB,Reach-1
Reach XY= 30
      3669951.26     10223481.52      3669984.82     10223422.04
      3670055.97     10223416.92      3670067.08     10223326.99
      3670198.84     10223245.69      3670199.78     10223168.15
      3670249.26     10223124.92      3670199.78     10223027.52
      3670201.87     10222973.88      3670285.86     10222920.79
      3670299.40     10222865.58      3670202.53     10222777.04
      3670151.49     10222846.83      3670110.86     10222846.83
      3669998.88     10222653.60      3670020.06     10222591.10
      3669997.49     10222558.11      3670094.71     10222495.61
      3670110.34     10222459.16      3670079.09     10222421.83
      3670078.22     10222334.16      3670101.66     10222313.32
      3670165.89     10222325.48      3670182.39     10222301.17
      3670167.63     10222273.39      3670211.03     10222229.12
      3670237.94     10222235.20      3670222.15     10222092.71
      3670306.35     10222025.03      3670311.71     10221942.51

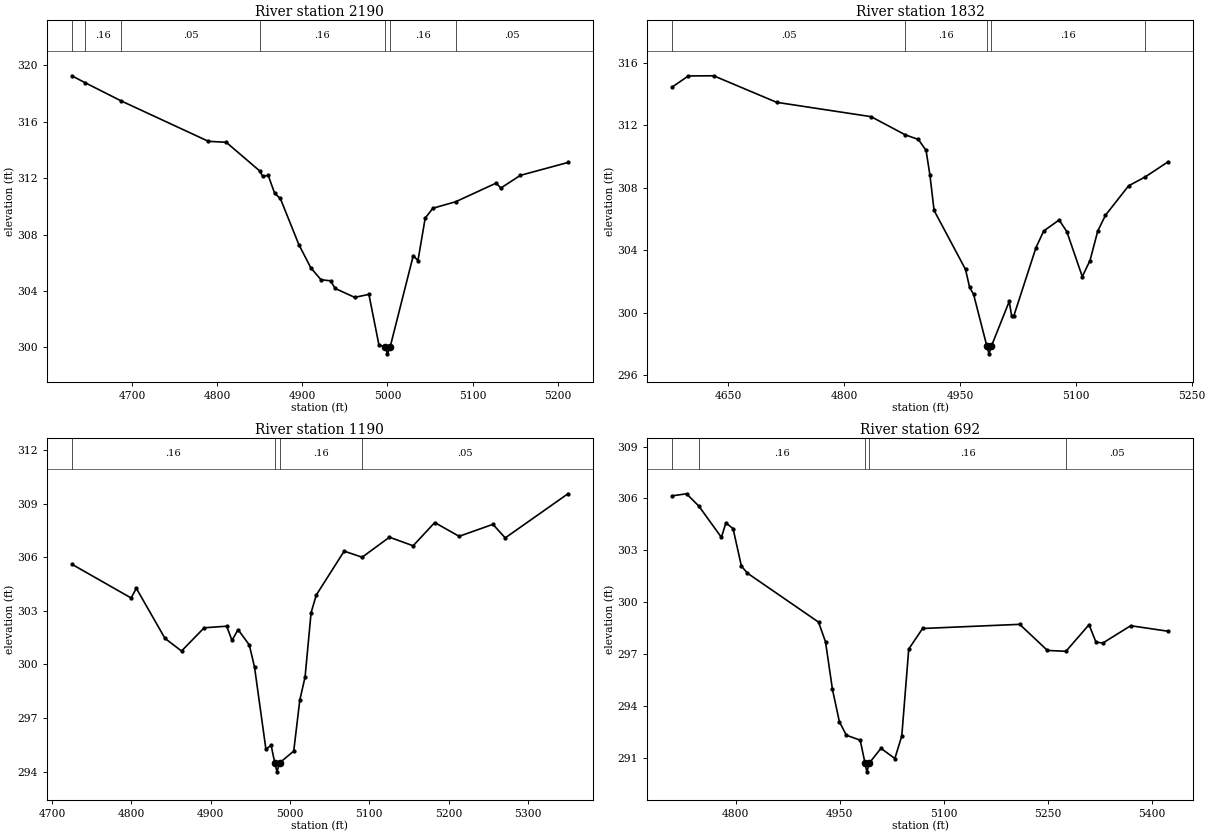
Type RM Length L Ch R = 1,2190,358,358,358
BEGIN DESCRIPTION:
UNT047 IN GIBB 4.0
END DESCRIPTION:
XS GIS Cut Line= 3
      3670338.54     10223611.38      3670140.32     10223391.85
      3669879.91     10223271.61
#Sta/Elev= 30
  4629.4  319.24  4644.7  318.76  4687.4  317.46  4789.8  314.60  4810.8  314.53
  4850.1  312.50  4853.4  312.13  4860.1  312.18  4867.6  310.92  4874.3  310.55
  4896.0  307.29  4910.1  305.64  4922.0  304.80  4933.2  304.72  4938.7  304.18
  4961.6  303.55  4978.3  303.76  4990.1  300.17  4997.3  300.05  5000.1  299.55
  5003.3  300.05  5030.4  306.51  5035.9  306.15  5044.4  309.16  5053.4  309.86
  5080.2  310.32  5127.7  311.64  5133.2  311.29  5156.2  312.19  5212.0  313.10
#Mann=7,-1,0
  4629.4    0.05       0  4644.7    0.16       0  4687.4    0.05       0
  4850.1    0.16       0  4997.3    0.07       0  5003.3    0.16       0
  5080.2    0.05       0
Bank Sta=4997.3,5003.3
Exp/Cntr=0.3,0.1

Type RM Length L Ch R = 1,1832,642,642,642
BEGIN DESCRIPTION:
UNT047 IN GIBB 3.0
END DESCRIPTION:
XS GIS Cut Line= 3
      3670664.94     10223191.27      3670230.89     10223105.64
      3670030.91     10223105.64
#Sta/Elev= 30
  4577.1  314.45  4598.2  315.17  4631.0  315.18  4712.5  313.48  4834.8  312.56
  4879.3  311.39  4896.0  311.10  4906.0  310.40  4911.1  308.79  4916.4  306.55
  4957.1  302.77  4962.4  301.62  4967.5  301.18  4984.7  297.86  4987.5  297.36
  4990.7  297.86  5013.7  300.72  5016.9  299.77  5019.5  299.77  5048.3  304.16
  5058.3  305.23  5078.3  305.94  5088.3  305.19  5108.3  302.31  5118.3  303.34
  5128.3  305.23  5138.3  306.24  5168.3  308.13  5189.5  308.69  5219.5  309.67
#Mann=5,-1,0
  4577.1    0.05       0  4879.3    0.16       0  4984.7    0.07       0
  4990.7    0.16       0  5189.5    0.05       0
Bank Sta=4984.7,4990.7
Exp/Cntr=0.3,0.1

Type RM Length L Ch R = 1,1190,498,498,498
BEGIN DESCRIPTION:
UNT047 IN GIBB 2.0
END DESCRIPTION:
XS GIS Cut Line= 3
      3670301.67     10222616.00      3669993.21     10222882.78
      3669807.50     10222996.72
#Sta/Elev= 30
  4724.9  305.61  4799.7  303.72  4806.3  304.26  4842.4  301.46  4863.3  300.75
  4891.8  302.05  4920.3  302.14  4926.9  301.34  4934.6  301.95  4948.8  301.09
  4955.4  299.84  4969.7  295.26  4976.3  295.47  4980.9  294.49  4983.7  293.99
  4986.9  294.49  5004.8  295.15  5012.5  298.02  5019.1  299.29  5026.7  302.90
  5033.3  303.89  5068.4  306.34  5091.1  306.00  5125.5  307.12  5155.4  306.64
  5182.6  307.94  5213.4  307.17  5256.0  307.84  5271.5  307.08  5350.6  309.55
#Mann=4,-1,0
  4724.9    0.16       0  4980.9    0.07       0  4986.9    0.16       0
  5091.1    0.05       0
Bank Sta=4980.9,4986.9
Exp/Cntr=0.3,0.1

Type RM Length L Ch R = 1,692,0,0,0
BEGIN DESCRIPTION:
UNT047 IN GIBB 1.0
END DESCRIPTION:
XS GIS Cut Line= 3
      3670361.54     10222478.10      3670261.58     10222428.12
      3669658.04     10222416.97
#Sta/Elev= 30
  4708.3  306.15  4729.2  306.27  4746.9  305.56  4779.5  303.75  4785.9  304.58
  4796.3  304.26  4808.3  302.09  4817.0  301.68  4919.5  298.85  4929.6  297.71
  4939.6  294.96  4949.6  293.09  4959.6  292.31  4979.6  292.02  4986.6  290.69
  4989.3  290.19  4992.6  290.69  5009.6  291.55  5029.6  290.96  5039.6  292.27
  5049.6  297.29  5069.6  298.48  5209.6  298.72  5249.6  297.21  5276.3  297.16
  5309.6  298.70  5319.6  297.69  5329.6  297.64  5369.6  298.64  5423.7  298.32
#Mann=5,-1,0
  4708.3    0.05       0  4746.9    0.16       0  4986.6    0.07       0
  4992.6    0.16       0  5276.3    0.05       0
Bank Sta=4986.6,4992.6
Exp/Cntr=0.3,0.1

Chan Stop Cuts=-1