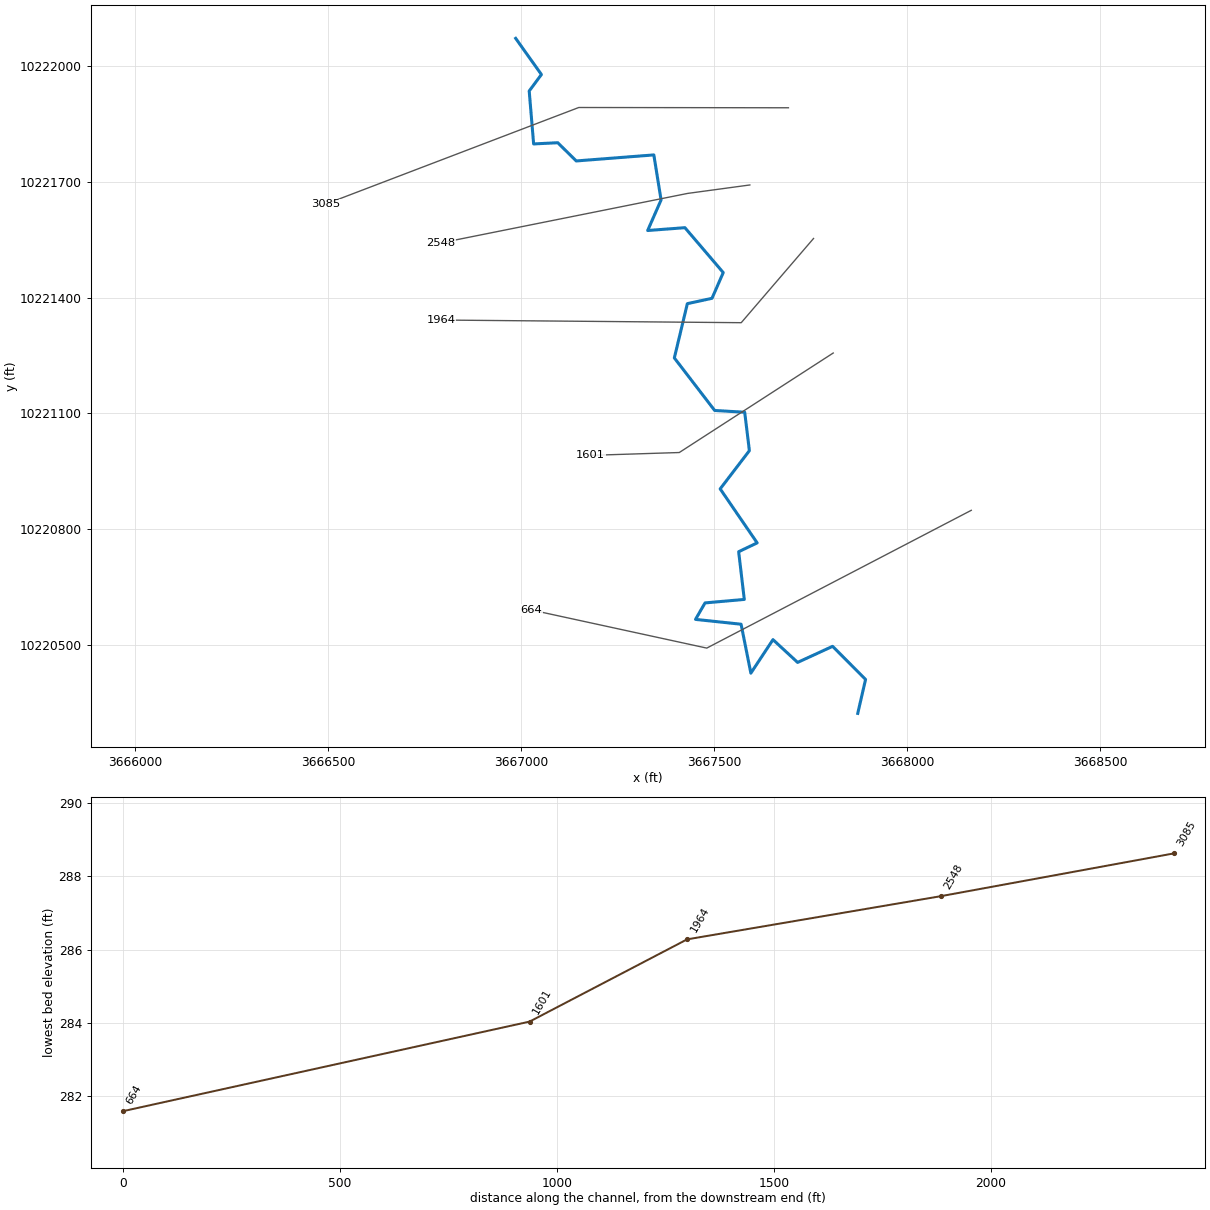
--- UNT048 IN GIBB.prj (project) ---

Proj Title=UNT048 IN GIBB Base Level Engineering
Current Plan=p01
Default Exp/Contr=0.3,0.1
English Units
Geom File=g01
Flow File=f01
Plan File=p01
BEGIN DESCRIPTION:
UNT048 IN GIBB
END DESCRIPTION:

--- UNT048 IN GIBB.p01 (plan) ---

Plan Title=Multiple Run
Short Identifier=Multiple
Geom File=g01
Flow File=f01
Subcritical Flow
K Sum by GR= 0
Std Step Tol= 0.01
Critical Tol= 0.01
Num of Std Step Trials= 20
Max Error Tol= 0.3
Flow Tol Ratio= 0.001
Split Flow NTrial= 30
Split Flow Tol= 0.02
Split Flow Ratio= 0.02
Log Output Level= 0
Friction Slope Method= 1
Unsteady Friction Slope Method= 2
Unsteady Bridges Friction Slope Method= 1
Parabolic Critical Depth
Global Vel Dist=  1 , 1 , 1
Global Log Level= 0
CheckData=True
Encroach Param= -1, 0, 0, 0
BEGIN DESCRIPTION:
Multiple Run
END DESCRIPTION:

--- UNT048 IN GIBB.f01 (steady flow) ---

Flow Title=Multiple
Number of Profiles=7
Profile Names=10-year,25-year,50-year,1pct_min,100-year,1pct_plu,500-year
River Rch & RM= UNT048 IN GIBB,Reach-1,3085
     548     730     877     773    1045    1414    1483
Boundary for River Rch & Prof#=UNT048 IN GIBB,Reach-1,1
Up Type=0
Dn Type=3
Dn Slope=0.005
Boundary for River Rch & Prof#=UNT048 IN GIBB,Reach-1,2
Up Type=0
Dn Type=3
Dn Slope=0.005
Boundary for River Rch & Prof#=UNT048 IN GIBB,Reach-1,3
Up Type=0
Dn Type=3
Dn Slope=0.005
Boundary for River Rch & Prof#=UNT048 IN GIBB,Reach-1,4
Up Type=0
Dn Type=3
Dn Slope=0.005
Boundary for River Rch & Prof#=UNT048 IN GIBB,Reach-1,5
Up Type=0
Dn Type=3
Dn Slope=0.005
Boundary for River Rch & Prof#=UNT048 IN GIBB,Reach-1,6
Up Type=0
Dn Type=3
Dn Slope=0.005
Boundary for River Rch & Prof#=UNT048 IN GIBB,Reach-1,7
Up Type=0
Dn Type=3
Dn Slope=0.005

--- UNT048 IN GIBB.g01 (geometry) ---

Geom Title=Existing Conditions

River Reach=UNT048 IN GIBB,Reach-1
Reach XY= 30
      3666985.38     10222071.56      3667052.04     10221977.81
      3667020.44     10221935.11      3667031.90     10221797.95
      3667094.40     10221801.08      3667142.32     10221753.86
      3667343.36     10221769.48      3667362.11     10221652.81
      3667327.39     10221573.65      3667423.92     10221580.94
      3667523.22     10221464.62      3667494.06     10221397.95
      3667430.17     10221384.06      3667396.49     10221243.44
      3667501.00     10221107.33      3667578.78     10221102.81
      3667590.93     10221003.16      3667515.24     10220904.20
      3667611.07     10220764.27      3667563.15     10220741.35
      3667577.74     10220617.74      3667476.00     10220608.72
      3667451.35     10220566.01      3667569.40     10220553.51
      3667594.75     10220426.77      3667652.04     10220513.58
      3667715.93     10220454.55      3667806.56     10220496.22
      3667891.97     10220410.45      3667871.71     10220322.51

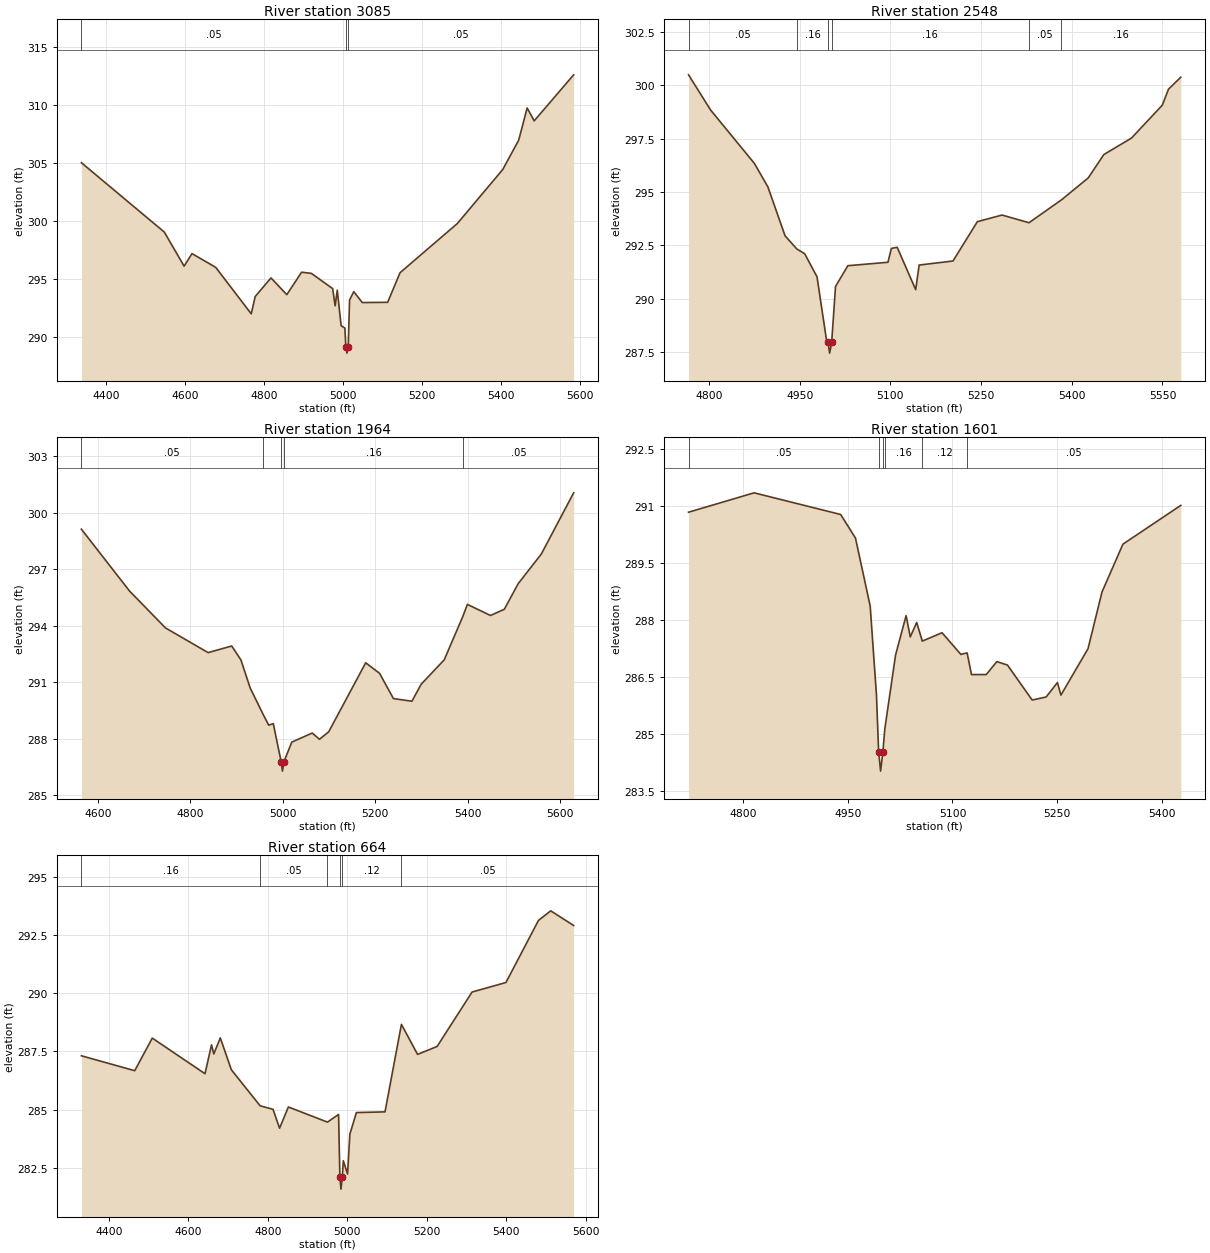
Type RM Length L Ch R = 1,3085,537,537,537
BEGIN DESCRIPTION:
UNT048 IN GIBB 5.0
END DESCRIPTION:
XS GIS Cut Line= 3
      3667692.10     10221891.64      3667148.87     10221892.35
      3666492.12     10221641.65
#Sta/Elev= 30
  4337.5  305.01  4547.5  299.04  4597.5  296.11  4617.5  297.19  4677.5  296.01
  4767.5  292.01  4777.5  293.50  4817.5  295.10  4857.5  293.66  4895.0  295.59
  4919.8  295.49  4973.6  294.18  4979.9  292.70  4985.3  294.05  4995.0  290.99
  5004.6  290.79  5007.0  289.13  5009.7  288.63  5013.0  289.13  5016.4  293.20
  5027.1  293.92  5048.5  292.98  5112.8  293.00  5144.3  295.55  5289.3  299.78
  5404.3  304.43  5444.6  306.95  5466.0  309.72  5483.8  308.61  5583.7  312.57
#Mann=3,-1,0
  4337.5    0.05       0  5007.0    0.03       0  5013.0    0.05       0
Bank Sta=5007,5013
Exp/Cntr=0.3,0.1

Type RM Length L Ch R = 1,2548,584,584,584
BEGIN DESCRIPTION:
UNT048 IN GIBB 4.0
END DESCRIPTION:
XS GIS Cut Line= 3
      3667592.14     10221691.65      3667430.96     10221669.76
      3666792.14     10221541.65
#Sta/Elev= 30
  4766.1  300.48  4802.4  298.84  4874.9  296.34  4897.3  295.24  4925.7  292.95
  4945.3  292.33  4958.2  292.11  4978.6  291.03  4994.7  287.99  4996.8  287.96
  4999.5  287.46  5002.8  287.96  5009.2  290.58  5029.6  291.55  5095.9  291.71
  5101.6  292.36  5111.2  292.41  5141.8  290.43  5147.5  291.58  5203.5  291.77
  5243.8  293.61  5284.6  293.92  5329.2  293.56  5382.9  294.63  5427.3  295.66
  5453.0  296.75  5498.7  297.52  5549.7  299.06  5560.0  299.81  5580.3  300.37
#Mann=6,-1,0
  4766.1    0.05       0  4945.3    0.16       0  4996.8    0.07       0
  5002.8    0.16       0  5329.2    0.05       0  5382.9    0.16       0
Bank Sta=4996.8,5002.8
Exp/Cntr=0.3,0.1

Type RM Length L Ch R = 1,1964,363,363,363
BEGIN DESCRIPTION:
UNT048 IN GIBB 3.0
END DESCRIPTION:
XS GIS Cut Line= 3
      3667757.15     10221552.99      3667569.80     10221334.78
      3666792.13     10221341.64
#Sta/Elev= 30
  4564.0  299.12  4668.1  295.84  4746.0  293.88  4838.2  292.57  4889.3  292.92
  4909.3  292.18  4929.3  290.69  4957.1  289.30  4969.3  288.72  4979.3  288.80
  4996.3  286.78  4999.1  286.28  5002.3  286.78  5019.3  287.82  5063.6  288.30
  5079.3  287.97  5099.3  288.37  5179.3  292.03  5209.3  291.47  5239.3  290.13
  5279.3  289.99  5299.3  290.89  5349.3  292.19  5390.0  294.52  5399.3  295.13
  5449.3  294.54  5479.3  294.87  5509.3  296.23  5559.3  297.80  5629.3  301.05
#Mann=5,-1,0
  4564.0    0.05       0  4957.1    0.16       0  4996.3    0.07       0
  5002.3    0.16       0  5390.0    0.05       0
Bank Sta=4996.3,5002.3
Exp/Cntr=0.3,0.1

Type RM Length L Ch R = 1,1601,937,937,937
BEGIN DESCRIPTION:
UNT048 IN GIBB 2.0
END DESCRIPTION:
XS GIS Cut Line= 3
      3667808.17     10221256.23      3667409.28     10220998.38
      3667179.27     10220991.06
#Sta/Elev= 30
  4722.0  290.84  4815.9  291.35  4939.9  290.78  4961.1  290.16  4982.2  288.37
  4991.2  286.02  4994.3  284.53  4997.1  284.03  5000.3  284.53  5003.2  285.15
  5018.5  287.08  5033.6  288.12  5039.6  287.56  5048.8  287.94  5056.8  287.45
  5085.1  287.67  5112.1  287.10  5121.0  287.14  5127.3  286.57  5148.4  286.57
  5163.6  286.91  5178.8  286.82  5214.2  285.90  5234.2  285.98  5250.4  286.36
  5255.4  286.03  5294.2  287.25  5314.2  288.74  5344.2  290.00  5427.1  291.02
#Mann=6,-1,0
  4722.0    0.05       0  4994.3    0.03       0  5000.3    0.05       0
  5003.2    0.16       0  5056.8    0.12       0  5121.0    0.05       0
Bank Sta=4994.3,5000.3
Exp/Cntr=0.3,0.1

Type RM Length L Ch R = 1,664,0,0,0
BEGIN DESCRIPTION:
UNT048 IN GIBB 1.0
END DESCRIPTION:
XS GIS Cut Line= 3
      3668165.86     10220848.67      3667480.50     10220491.66
      3667025.69     10220590.53
#Sta/Elev= 30
  4331.1  287.31  4465.2  286.67  4509.4  288.07  4642.0  286.54  4658.4  287.78
  4664.1  287.39  4680.5  288.08  4708.3  286.71  4780.7  285.16  4813.1  285.01
  4829.6  284.20  4851.7  285.11  4950.1  284.46  4978.0  284.79  4981.3  282.08
  4984.0  281.58  4987.3  282.08  4989.9  282.80  5000.6  282.23  5006.4  283.94
  5022.8  284.87  5094.8  284.90  5136.1  288.66  5176.7  287.37  5225.8  287.71
  5313.8  290.05  5399.0  290.46  5480.9  293.13  5511.6  293.54  5569.3  292.91
#Mann=6,-1,0
  4331.1    0.16       0  4780.7    0.05       0  4950.1    0.12       0
  4981.3    0.07       0  4987.3    0.12       0  5136.1    0.05       0
Bank Sta=4981.3,4987.3
Exp/Cntr=0.3,0.1

Chan Stop Cuts=-1