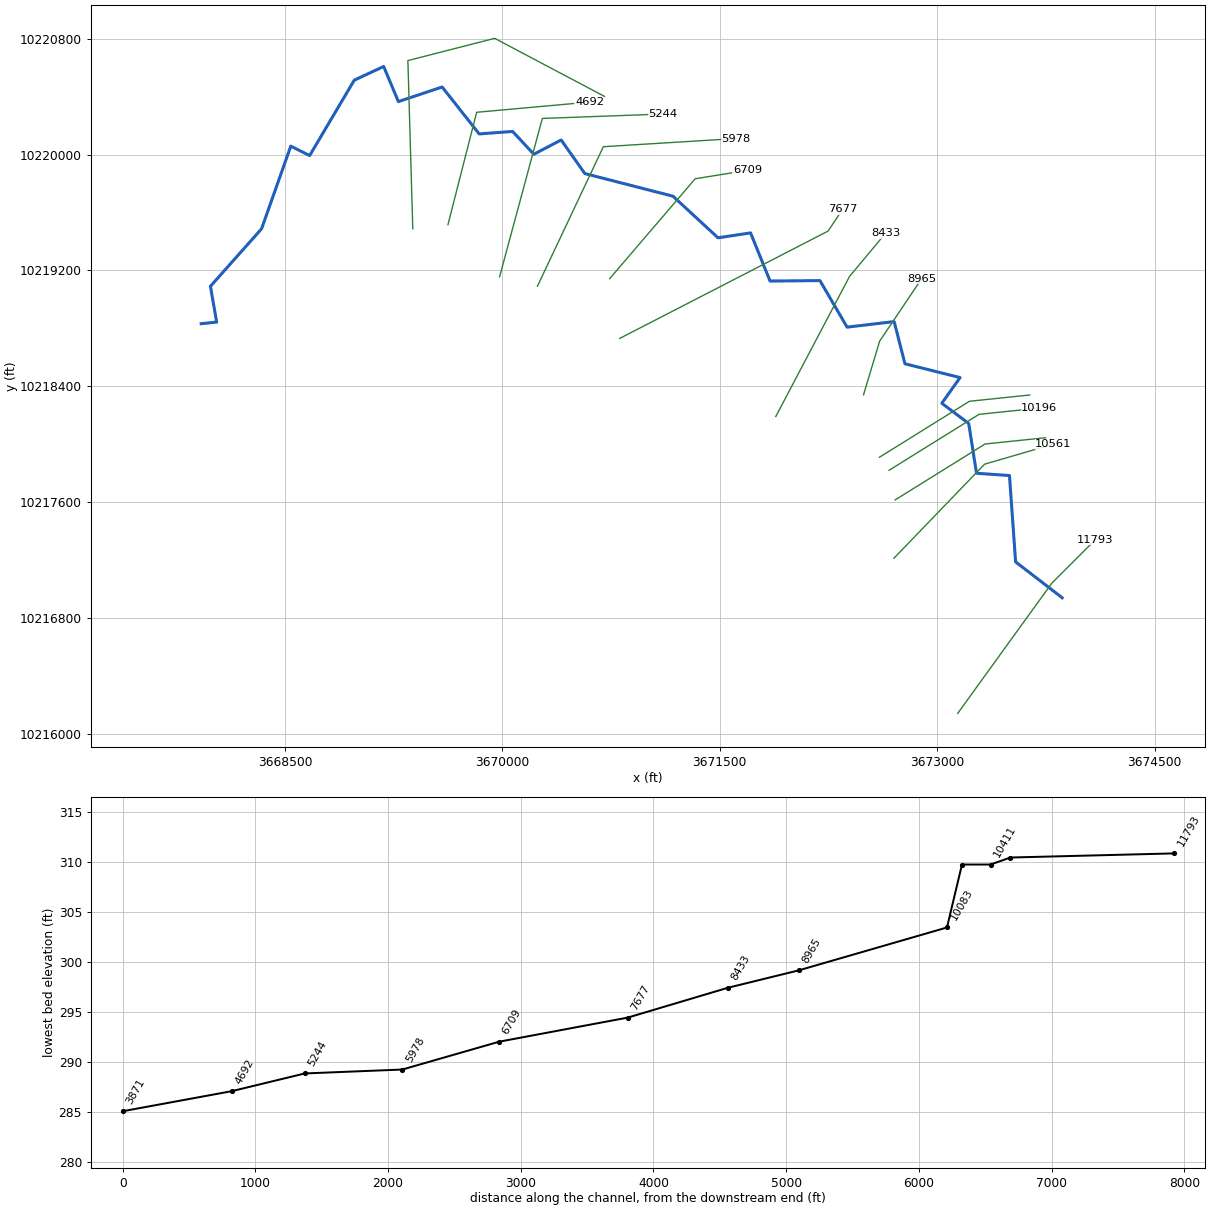
--- UNT049 IN GIBB.prj (project) ---

Proj Title=UNT049 IN GIBB Base Level Engineering
Current Plan=p01
Default Exp/Contr=0.3,0.1
English Units
Geom File=g01
Flow File=f01
Plan File=p01
BEGIN DESCRIPTION:
UNT049 IN GIBB
END DESCRIPTION:

--- UNT049 IN GIBB.p01 (plan) ---

Plan Title=Multiple Run
Short Identifier=Multiple
Geom File=g01
Flow File=f01
Subcritical Flow
K Sum by GR= 0
Std Step Tol= 0.01
Critical Tol= 0.01
Num of Std Step Trials= 20
Max Error Tol= 0.3
Flow Tol Ratio= 0.001
Split Flow NTrial= 30
Split Flow Tol= 0.02
Split Flow Ratio= 0.02
Log Output Level= 0
Friction Slope Method= 1
Unsteady Friction Slope Method= 2
Unsteady Bridges Friction Slope Method= 1
Parabolic Critical Depth
Global Vel Dist=  1 , 1 , 1
Global Log Level= 0
CheckData=True
Encroach Param= -1, 0, 0, 0
BEGIN DESCRIPTION:
Multiple Run
END DESCRIPTION:

--- UNT049 IN GIBB.f01 (steady flow) ---

Flow Title=Multiple
Number of Profiles=7
Profile Names=10-year,25-year,50-year,1pct_min,100-year,1pct_plu,500-year
River Rch & RM= UNT049 IN GIBB,Reach-1,11793
     658     881    1062     938    1268    1715    1806
River Rch & RM= UNT049 IN GIBB,Reach-1,6709
    1149    1583    1943    1744    2359    3190    3477
Boundary for River Rch & Prof#=UNT049 IN GIBB,Reach-1,1
Up Type=0
Dn Type=3
Dn Slope=0.005
Boundary for River Rch & Prof#=UNT049 IN GIBB,Reach-1,2
Up Type=0
Dn Type=3
Dn Slope=0.005
Boundary for River Rch & Prof#=UNT049 IN GIBB,Reach-1,3
Up Type=0
Dn Type=3
Dn Slope=0.005
Boundary for River Rch & Prof#=UNT049 IN GIBB,Reach-1,4
Up Type=0
Dn Type=3
Dn Slope=0.005
Boundary for River Rch & Prof#=UNT049 IN GIBB,Reach-1,5
Up Type=0
Dn Type=3
Dn Slope=0.005
Boundary for River Rch & Prof#=UNT049 IN GIBB,Reach-1,6
Up Type=0
Dn Type=3
Dn Slope=0.005
Boundary for River Rch & Prof#=UNT049 IN GIBB,Reach-1,7
Up Type=0
Dn Type=3
Dn Slope=0.005

--- UNT049 IN GIBB.g01 (geometry) ---

Geom Title=Existing Conditions

River Reach=UNT049 IN GIBB,Reach-1
Reach XY= 30
      3673863.34     10216939.71      3673541.58     10217187.56
      3673499.23     10217783.92      3673271.80     10217799.71
      3673217.98     10218143.46      3673032.43     10218282.99
      3673158.45     10218460.41      3672777.98     10218555.62
      3672703.39     10218847.00      3672378.69     10218808.64
      3672191.37     10219129.95      3671847.20     10219126.98
      3671712.65     10219459.45      3671487.83     10219425.65
      3671177.12     10219712.81      3670569.05     10219869.14
      3670405.67     10220100.95      3670217.04     10220002.63
      3670070.85     10220159.97      3669839.91     10220142.95
      3669584.43     10220466.87      3669282.30     10220366.22
      3669180.91     10220608.65      3668977.84     10220513.90
      3668670.04     10219993.14      3668540.01     10220058.88
      3668338.35     10219487.74      3667985.47     10219090.69
      3668028.53     10218843.50      3667921.71     10218832.51

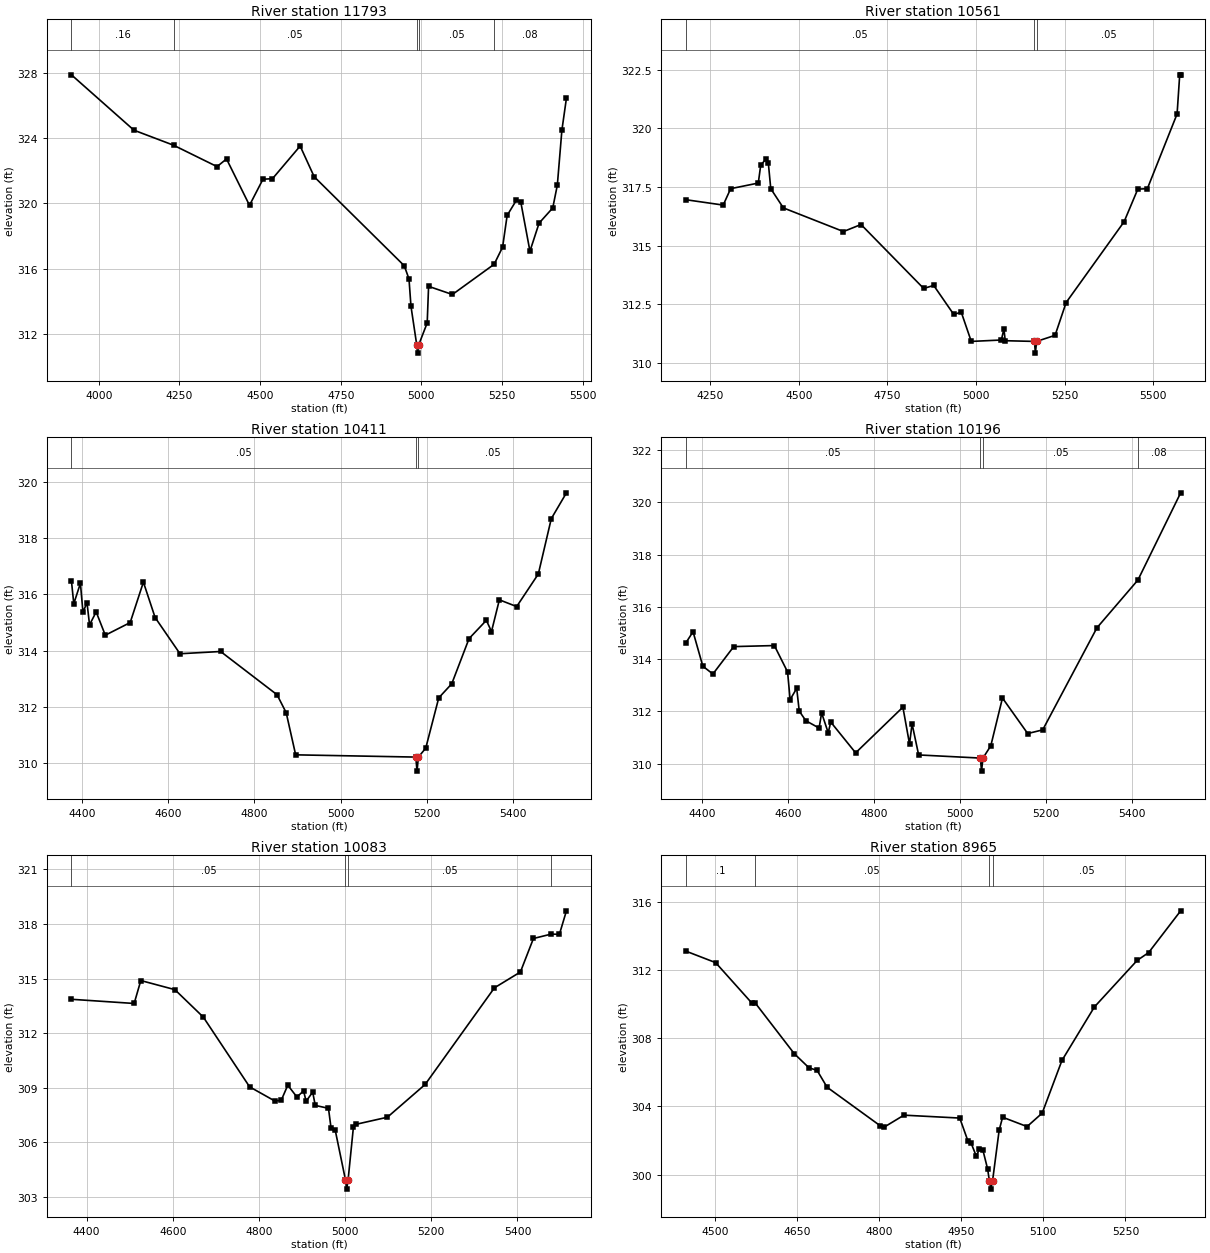
Type RM Length L Ch R = 1,11793,1232,1232,1232
BEGIN DESCRIPTION:
UNT049 IN GIBB 15.0
END DESCRIPTION:
XS GIS Cut Line= 3
      3673142.10     10216141.64      3673792.11     10217041.64
      3674092.07     10217341.61
#Sta/Elev= 30
  3915.2  327.86  4109.0  324.47  4231.8  323.55  4366.6  322.24  4396.0  322.71
  4467.2  319.87  4509.0  321.47  4538.4  321.50  4624.2  323.50  4667.7  321.62
  4946.9  316.17  4961.6  315.36  4967.7  313.69  4985.6  311.32  4988.4  310.82
  4991.6  311.32  5018.0  312.67  5022.3  314.91  5096.1  314.41  5225.5  316.26
  5251.7  317.31  5265.8  319.25  5294.1  320.17  5308.2  320.06  5336.5  317.06
  5364.8  318.78  5407.2  319.71  5421.4  321.11  5435.5  324.47  5449.6  326.43
#Mann=5,-1,0
  3915.2    0.16       0  4231.8    0.05       0  4985.6    0.03       0
  4991.6    0.05       0  5225.5    0.08       0
Bank Sta=4985.6,4991.6
Exp/Cntr=0.3,0.1

Type RM Length L Ch R = 1,10561,150,150,150
BEGIN DESCRIPTION:
UNT049 IN GIBB 13.0
END DESCRIPTION:
XS GIS Cut Line= 3
      3672701.51     10217212.51      3673327.36     10217862.21
      3673802.35     10218000.76
#Sta/Elev= 30
  4180.8  316.96  4286.8  316.73  4307.8  317.43  4385.8  317.67  4392.7  318.44
  4406.9  318.68  4414.1  318.53  4421.0  317.43  4456.5  316.61  4626.1  315.60
  4675.7  315.90  4852.5  313.17  4880.8  313.30  4937.4  312.06  4958.5  312.16
  4986.8  310.91  5071.7  310.97  5078.9  311.44  5082.7  310.94  5165.1  310.91
  5167.8  310.41  5171.1  310.91  5223.3  311.17  5254.5  312.57  5418.1  316.02
  5456.7  317.41  5483.7  317.43  5567.6  320.62  5575.0  322.29  5577.7  322.29
#Mann=3,-1,0
  4180.8    0.05       0  5165.1    0.03       0  5171.1    0.05       0
Bank Sta=5165.1,5171.1
Exp/Cntr=0.3,0.1

Type RM Length L Ch R = 1,10411,215,215,215
BEGIN DESCRIPTION:
UNT049 IN GIBB 11.2
END DESCRIPTION:
XS GIS Cut Line= 3
      3672709.85     10217615.33      3673330.50     10218001.62
      3673747.10     10218045.01
#Sta/Elev= 30
  4374.9  316.49  4380.4  315.67  4395.8  316.40  4401.7  315.37  4411.1  315.71
  4417.0  314.92  4432.4  315.38  4453.6  314.55  4511.4  315.00  4542.1  316.44
  4569.3  315.18  4627.1  313.89  4721.5  313.97  4852.6  312.43  4873.8  311.79
  4895.8  310.29  5174.9  310.21  5177.7  309.71  5180.9  310.21  5198.0  310.53
  5228.2  312.32  5258.4  312.82  5298.6  314.43  5338.8  315.08  5350.7  314.68
  5369.0  315.81  5409.2  315.57  5459.5  316.73  5489.6  318.70  5524.8  319.62
#Mann=3,-1,0
  4374.9    0.05       0  5174.9    0.03       0  5180.9    0.05       0
Bank Sta=5174.9,5180.9
Exp/Cntr=0.3,0.1

Type RM Length L Ch R = 1,10196,113,113,113
BEGIN DESCRIPTION:
UNT049 IN GIBB 11.1
END DESCRIPTION:
XS GIS Cut Line= 3
      3672668.19     10217820.20      3673288.84     10218206.48
      3673705.55     10218249.89
#Sta/Elev= 30
  4362.5  314.61  4379.7  315.05  4402.4  313.73  4425.8  313.43  4474.2  314.48
  4568.6  314.52  4599.3  313.51  4605.2  312.45  4620.5  312.88  4626.4  312.01
  4641.8  311.64  4672.5  311.36  4678.4  311.94  4693.7  311.18  4699.6  311.59
  4757.4  310.41  4867.2  312.16  4882.6  310.75  4888.5  311.52  4903.8  310.33
  5047.2  310.21  5049.9  309.71  5053.2  310.21  5071.4  310.68  5098.5  312.51
  5157.1  311.15  5192.0  311.29  5318.0  315.20  5413.2  317.03  5512.5  320.37
#Mann=4,-1,0
  4362.5    0.05       0  5047.2    0.03       0  5053.2    0.05       0
  5413.2    0.08       0
Bank Sta=5047.2,5053.2
Exp/Cntr=0.3,0.1

Type RM Length L Ch R = 1,10083,1118,1118,1118
BEGIN DESCRIPTION:
UNT049 IN GIBB 11.0
END DESCRIPTION:
XS GIS Cut Line= 3
      3672602.22     10217910.48      3673222.86     10218296.76
      3673638.29     10218340.03
#Sta/Elev= 30
  4365.0  313.86  4510.6  313.63  4526.0  314.89  4605.0  314.39  4671.1  312.88
  4778.5  309.05  4836.4  308.28  4851.7  308.30  4867.1  309.14  4888.3  308.49
  4903.7  308.83  4909.6  308.26  4924.9  308.76  4930.8  308.03  4961.5  307.87
  4967.4  306.80  4976.9  306.70  5001.0  303.93  5003.7  303.43  5007.0  303.93
  5019.3  306.82  5025.2  306.99  5098.2  307.38  5185.8  309.18  5346.6  314.49
  5406.9  315.36  5437.1  317.20  5478.2  317.44  5497.4  317.43  5513.7  318.72
#Mann=4,-1,0
  4365.0    0.05       0  5001.0    0.03       0  5007.0    0.05       0
  5478.2    0.08       0
Bank Sta=5001,5007
Exp/Cntr=0.3,0.1

Type RM Length L Ch R = 1,8965,532,532,532
BEGIN DESCRIPTION:
UNT049 IN GIBB 9.0
END DESCRIPTION:
XS GIS Cut Line= 3
      3672492.10     10218341.64      3672602.92     10218711.04
      3672892.13     10219141.68
#Sta/Elev= 30
  4446.5  313.12  4501.3  312.44  4567.4  310.07  4573.7  310.07  4644.9  307.10
  4671.8  306.27  4686.6  306.12  4704.9  305.13  4801.5  302.88  4809.3  302.79
  4845.3  303.49  4947.3  303.32  4962.3  301.97  4968.3  301.83  4977.3  301.10
  4983.3  301.48  4989.5  301.45  4998.3  300.32  5001.3  299.65  5004.1  299.15
  5007.3  299.65  5019.3  302.61  5025.6  303.37  5070.3  302.82  5097.9  303.61
  5134.0  306.70  5193.3  309.84  5271.4  312.57  5292.4  313.03  5350.9  315.48
#Mann=4,-1,0
  4446.5     0.1       0  4573.7    0.05       0  5001.3    0.03       0
  5007.3    0.05       0
Bank Sta=5001.3,5007.3
Exp/Cntr=0.3,0.1

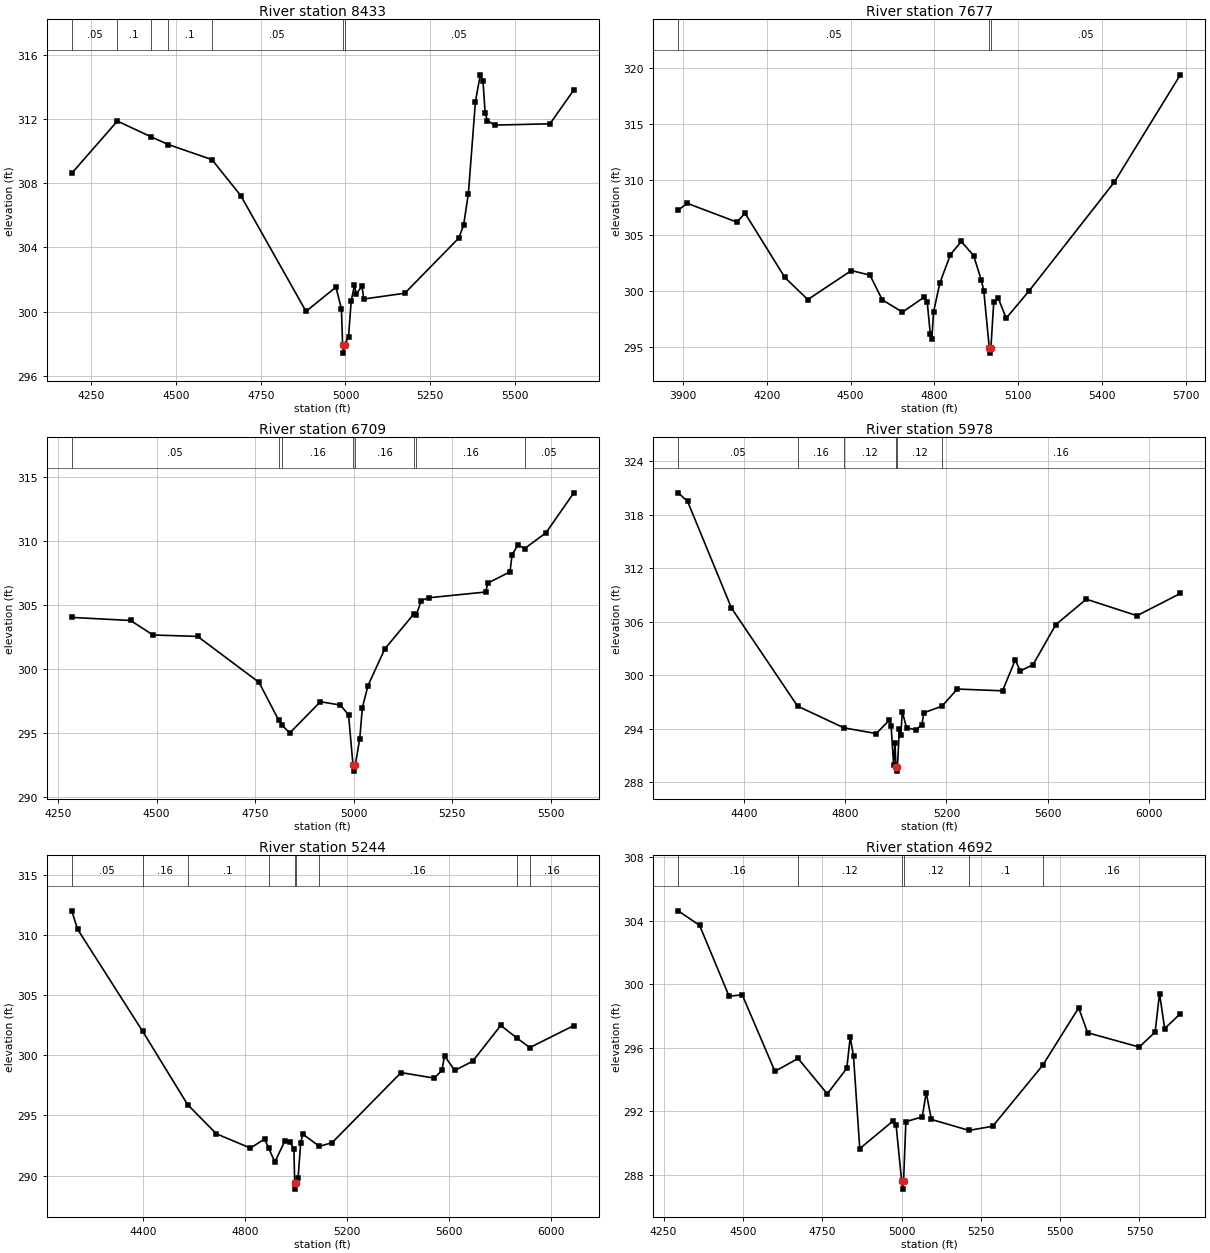
Type RM Length L Ch R = 1,8433,756,756,756
BEGIN DESCRIPTION:
UNT049 IN GIBB 7.0
END DESCRIPTION:
XS GIS Cut Line= 3
      3671886.70     10218191.59      3672395.75     10219159.00
      3672644.74     10219457.79
#Sta/Elev= 30
  4192.0  308.62  4326.6  311.87  4426.2  310.89  4476.8  310.41  4605.7  309.47
  4690.8  307.23  4883.5  300.02  4971.8  301.53  4988.1  300.17  4991.4  297.92
  4994.1  297.42  4997.4  297.92  5008.9  298.44  5017.0  300.69  5026.5  301.64
  5032.1  301.10  5048.5  301.59  5054.2  300.79  5175.1  301.15  5334.2  304.58
  5348.5  305.37  5362.8  307.36  5383.6  313.08  5397.9  314.75  5405.8  314.37
  5412.3  312.38  5418.8  311.89  5440.9  311.62  5603.6  311.70  5674.1  313.81
#Mann=7,-1,0
  4192.0    0.05       0  4326.6     0.1       0  4426.2    0.05       0
  4476.8     0.1       0  4605.7    0.05       0  4991.4    0.03       0
  4997.4    0.05       0
Bank Sta=4991.4,4997.4
Exp/Cntr=0.3,0.1

Type RM Length L Ch R = 1,7677,968,968,968
BEGIN DESCRIPTION:
UNT049 IN GIBB 6.0
END DESCRIPTION:
XS GIS Cut Line= 3
      3670809.66     10218730.78      3672247.66     10219472.02
      3672347.39     10219621.62
#Sta/Elev= 30
  3883.2  307.29  3916.0  307.88  4093.3  306.20  4122.2  307.00  4264.9  301.23
  4347.2  299.25  4503.1  301.85  4569.6  301.44  4613.9  299.22  4686.0  298.12
  4763.4  299.46  4774.7  299.01  4785.6  296.17  4791.2  295.74  4797.2  298.11
  4819.7  300.72  4857.7  303.28  4896.4  304.46  4940.7  303.20  4968.5  300.98
  4977.2  300.02  4996.7  294.94  4999.5  294.44  5002.7  294.94  5012.9  299.06
  5029.4  299.35  5057.2  297.57  5140.2  300.05  5444.9  309.80  5680.8  319.42
#Mann=3,-1,0
  3883.2    0.05       0  4996.7    0.03       0  5002.7    0.05       0
Bank Sta=4996.7,5002.7
Exp/Cntr=0.3,0.1

Type RM Length L Ch R = 1,6709,731,731,731
BEGIN DESCRIPTION:
UNT049 IN GIBB 5.0
END DESCRIPTION:
XS GIS Cut Line= 3
      3670740.21     10219143.10      3671330.50     10219833.21
      3671692.08     10219891.64
#Sta/Elev= 30
  4284.5  304.02  4433.7  303.78  4490.8  302.65  4603.9  302.54  4759.8  298.96
  4810.0  295.99  4819.2  295.60  4837.7  295.01  4915.6  297.45  4966.2  297.19
  4987.0  296.43  4998.3  292.54  5001.0  292.04  5004.3  292.54  5015.5  294.58
  5022.1  296.99  5036.4  298.71  5079.2  301.57  5152.3  304.27  5159.1  304.22
  5171.4  305.33  5190.0  305.55  5335.3  306.00  5340.3  306.69  5396.8  307.57
  5402.1  308.90  5417.1  309.67  5434.1  309.39  5488.0  310.61  5558.9  313.73
#Mann=8,-1,0
  4284.5    0.05       0  4810.0    0.12       0  4819.2    0.16       0
  4998.3    0.07       0  5004.3    0.16       0  5152.3    0.12       0
  5159.1    0.16       0  5434.1    0.05       0
Bank Sta=4998.3,5004.3
Exp/Cntr=0.3,0.1

Type RM Length L Ch R = 1,5978,734,734,734
BEGIN DESCRIPTION:
UNT049 IN GIBB 3.0
END DESCRIPTION:
XS GIS Cut Line= 3
      3670242.09     10219091.62      3670696.82     10220054.57
      3671612.67     10220110.99
#Sta/Elev= 30
  4141.0  320.45  4177.9  319.49  4351.1  307.54  4612.1  296.55  4795.2  294.11
  4923.1  293.47  4974.2  294.97  4981.5  294.37  4991.4  290.00  4997.0  292.37
  5000.6  289.76  5003.4  289.26  5006.6  289.76  5014.2  293.99  5019.7  293.27
  5025.7  295.92  5042.5  294.11  5081.0  293.89  5103.2  294.48  5110.8  295.80
  5182.4  296.54  5243.0  298.46  5421.6  298.26  5471.7  301.72  5491.7  300.49
  5541.8  301.18  5632.0  305.68  5752.2  308.53  5952.6  306.68  6123.5  309.17
#Mann=6,-1,0
  4141.0    0.05       0  4612.1    0.16       0  4795.2    0.12       0
  5000.6    0.07       0  5006.6    0.12       0  5182.4    0.16       0
Bank Sta=5000.6,5006.6
Exp/Cntr=0.3,0.1

Type RM Length L Ch R = 1,5244,552,552,552
BEGIN DESCRIPTION:
UNT049 IN GIBB 2.0
END DESCRIPTION:
XS GIS Cut Line= 3
      3669980.69     10219156.17      3670275.82     10220249.88
      3671108.13     10220280.23
#Sta/Elev= 30
  4122.3  312.01  4145.2  310.47  4399.3  302.01  4575.8  295.90  4688.4  293.47
  4821.9  292.28  4877.6  293.05  4893.2  292.27  4917.5  291.13  4957.4  292.91
  4977.3  292.76  4992.1  292.22  4995.0  289.37  4997.8  288.87  5001.0  289.37
  5008.4  289.80  5018.7  292.74  5026.8  293.44  5091.9  292.43  5141.4  292.73
  5411.5  298.56  5541.6  298.10  5571.6  298.75  5581.6  299.95  5621.7  298.74
  5691.7  299.50  5801.8  302.48  5864.7  301.44  5915.7  300.64  6088.0  302.47
#Mann=9,-1,0
  4122.3    0.05       0  4399.3    0.16       0  4575.8     0.1       0
  4893.2    0.12       0  4995.0    0.07       0  5001.0    0.12       0
  5091.9    0.16       0  5864.7     0.1       0  5915.7    0.16       0
Bank Sta=4995,5001
Exp/Cntr=0.3,0.1

Type RM Length L Ch R = 1,4692,821,821,821
BEGIN DESCRIPTION:
Mapping XS 70ced834
END DESCRIPTION:
XS GIS Cut Line= 3
      3669624.64     10219516.29      3669822.56     10220292.32
      3670601.22     10220362.64
#Sta/Elev= 30
  4296.1  304.63  4363.5  303.71  4456.4  299.25  4497.7  299.34  4600.9  294.52
  4673.9  295.33  4766.0  293.10  4827.4  294.71  4838.3  296.68  4848.6  295.47
  4868.3  289.65  4972.4  291.38  4982.7  291.16  5000.4  287.60  5003.1  287.10
  5006.4  287.60  5013.7  291.35  5065.3  291.65  5077.8  293.18  5094.0  291.49
  5212.6  290.80  5287.3  291.06  5445.0  294.90  5558.4  298.52  5586.6  296.95
  5749.2  296.05  5799.4  296.99  5813.3  299.42  5829.5  297.21  5878.8  298.15
#Mann=6,-1,0
  4296.1    0.16       0  4673.9    0.12       0  5000.4    0.07       0
  5006.4    0.12       0  5212.6     0.1       0  5445.0    0.16       0
Bank Sta=5000.4,5006.4
Exp/Cntr=0.3,0.1

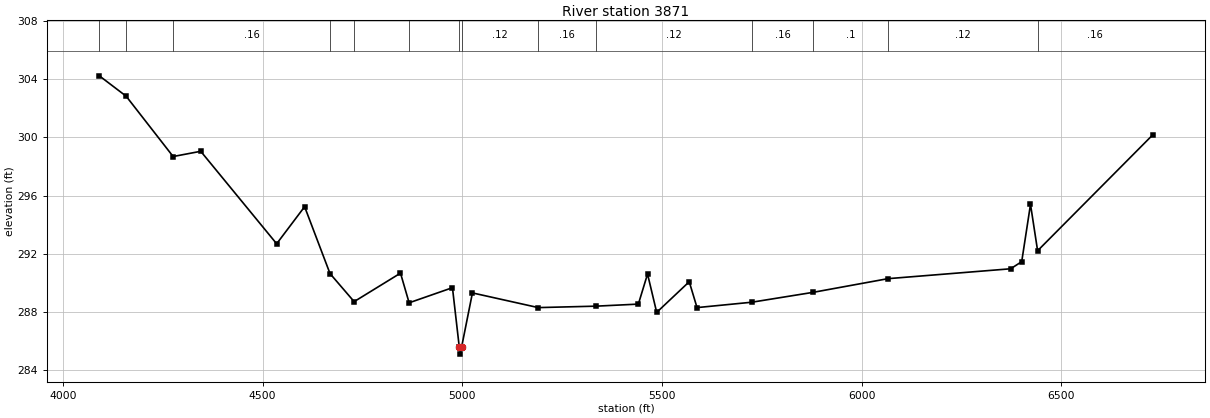
Type RM Length L Ch R = 1,3871,0,0,0
BEGIN DESCRIPTION:
UNT049 IN GIBB 1.0
END DESCRIPTION:
XS GIS Cut Line= 4
      3669381.82     10219487.85      3669347.97     10220649.30
      3669946.93     10220802.94      3670704.76     10220401.89
#Sta/Elev= 30
  4091.1  304.24  4158.2  302.84  4275.9  298.69  4345.0  299.05  4535.1  292.69
  4605.1  295.24  4668.7  290.64  4729.1  288.71  4845.2  290.67  4866.8  288.63
  4975.3  289.67  4992.3  285.60  4995.0  285.10  4998.3  285.60  5025.3  289.31
  5190.2  288.30  5335.9  288.40  5440.8  288.54  5463.8  290.61  5486.7  287.97
  5568.2  290.08  5587.7  288.30  5724.8  288.67  5878.5  289.35  6065.8  290.29
  6373.0  290.97  6400.7  291.46  6422.7  295.40  6440.5  292.21  6728.8  300.18
#Mann=14,-1,0
  4091.1    0.16       0  4158.2    0.05       0  4275.9    0.16       0
  4668.7    0.12       0  4729.1    0.16       0  4866.8    0.12       0
  4992.3    0.07       0  4998.3    0.12       0  5190.2    0.16       0
  5335.9    0.12       0  5724.8    0.16       0  5878.5     0.1       0
  6065.8    0.12       0  6440.5    0.16       0
Bank Sta=4992.3,4998.3
Exp/Cntr=0.3,0.1

Chan Stop Cuts=-1