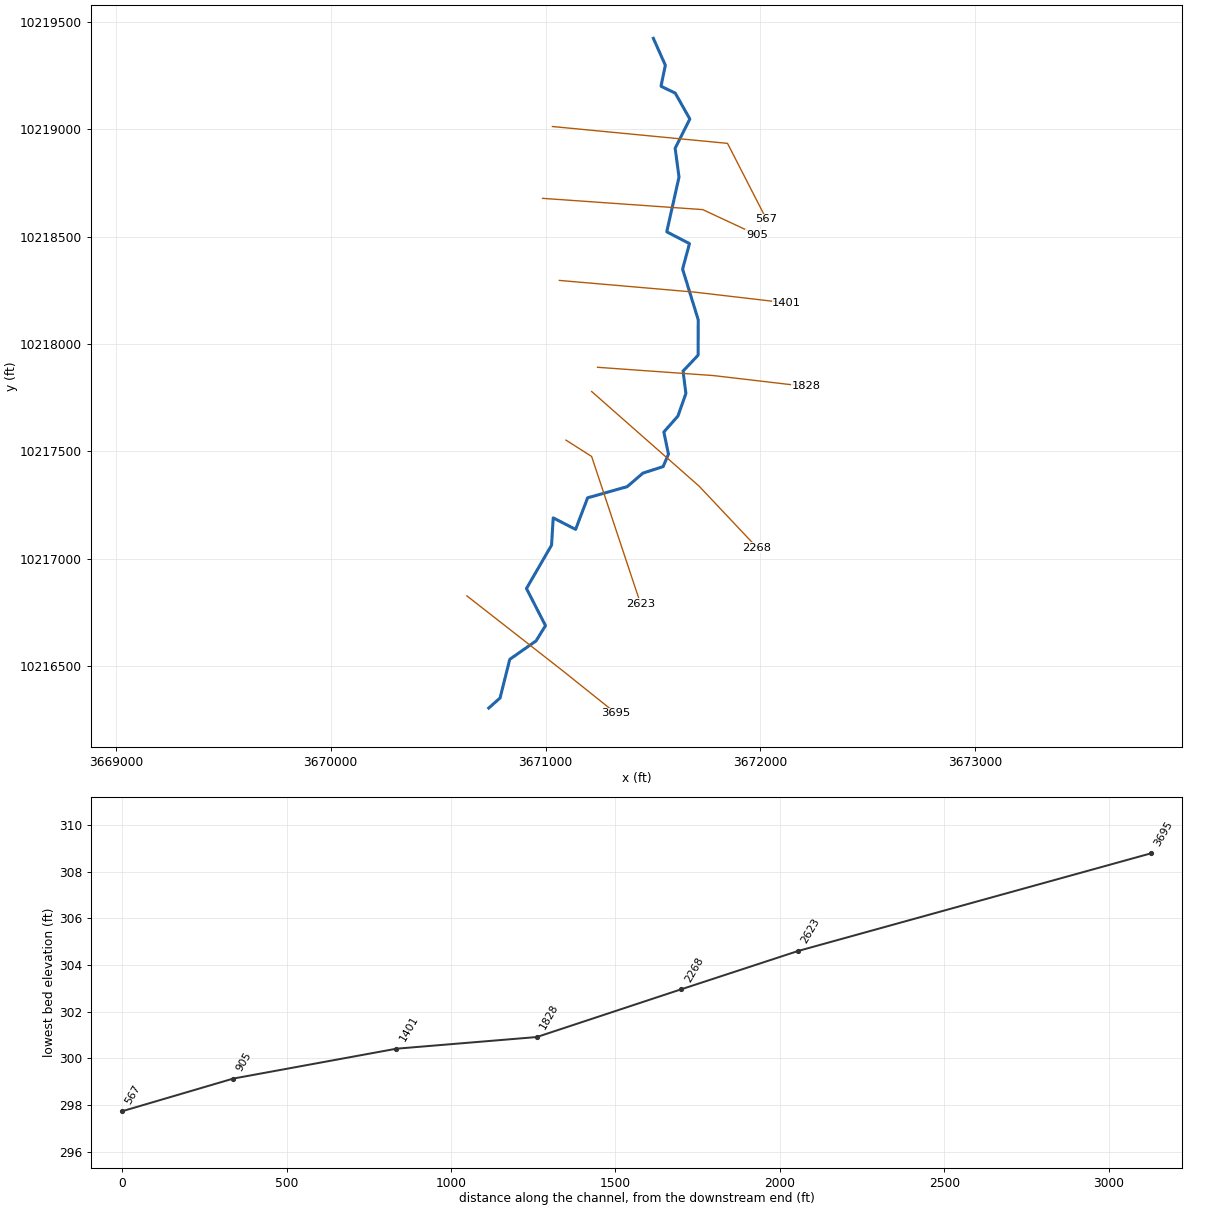
--- UNT050 IN GIBB.prj (project) ---

Proj Title=UNT050 IN GIBB Base Level Engineering
Current Plan=p01
Default Exp/Contr=0.3,0.1
English Units
Geom File=g01
Flow File=f01
Plan File=p01
BEGIN DESCRIPTION:
UNT050 IN GIBB
END DESCRIPTION:

--- UNT050 IN GIBB.p01 (plan) ---

Plan Title=Multiple Run
Short Identifier=Multiple
Geom File=g01
Flow File=f01
Subcritical Flow
K Sum by GR= 0
Std Step Tol= 0.01
Critical Tol= 0.01
Num of Std Step Trials= 20
Max Error Tol= 0.3
Flow Tol Ratio= 0.001
Split Flow NTrial= 30
Split Flow Tol= 0.02
Split Flow Ratio= 0.02
Log Output Level= 0
Friction Slope Method= 1
Unsteady Friction Slope Method= 2
Unsteady Bridges Friction Slope Method= 1
Parabolic Critical Depth
Global Vel Dist=  1 , 1 , 1
Global Log Level= 0
CheckData=True
Encroach Param= -1, 0, 0, 0
BEGIN DESCRIPTION:
Multiple Run
END DESCRIPTION:

--- UNT050 IN GIBB.f01 (steady flow) ---

Flow Title=Multiple
Number of Profiles=7
Profile Names=10-year,25-year,50-year,1pct_min,100-year,1pct_plu,500-year
River Rch & RM= UNT050 IN GIBB,Reach-1,3695
     488     640     761     664     897    1214    1246
Boundary for River Rch & Prof#=UNT050 IN GIBB,Reach-1,1
Up Type=0
Dn Type=3
Dn Slope=0.005
Boundary for River Rch & Prof#=UNT050 IN GIBB,Reach-1,2
Up Type=0
Dn Type=3
Dn Slope=0.005
Boundary for River Rch & Prof#=UNT050 IN GIBB,Reach-1,3
Up Type=0
Dn Type=3
Dn Slope=0.005
Boundary for River Rch & Prof#=UNT050 IN GIBB,Reach-1,4
Up Type=0
Dn Type=3
Dn Slope=0.005
Boundary for River Rch & Prof#=UNT050 IN GIBB,Reach-1,5
Up Type=0
Dn Type=3
Dn Slope=0.005
Boundary for River Rch & Prof#=UNT050 IN GIBB,Reach-1,6
Up Type=0
Dn Type=3
Dn Slope=0.005
Boundary for River Rch & Prof#=UNT050 IN GIBB,Reach-1,7
Up Type=0
Dn Type=3
Dn Slope=0.005

--- UNT050 IN GIBB.g01 (geometry) ---

Geom Title=Existing Conditions

River Reach=UNT050 IN GIBB,Reach-1
Reach XY= 30
      3670735.67     10216305.99      3670788.36     10216352.79
      3670833.54     10216532.78      3670955.65     10216618.19
      3670999.80     10216689.41      3670911.27     10216862.29
      3671027.99     10217064.07      3671035.75     10217191.02
      3671139.92     10217137.28      3671195.81     10217284.28
      3671380.16     10217336.24      3671453.10     10217399.19
      3671547.20     10217429.60      3671572.05     10217487.40
      3671550.51     10217590.50      3671616.06     10217664.60
      3671653.11     10217769.66      3671639.97     10217874.12
      3671710.04     10217947.99      3671710.67     10218112.36
      3671637.75     10218348.69      3671669.88     10218467.23
      3671564.07     10218522.19      3671621.14     10218776.90
      3671603.17     10218910.85      3671671.52     10219047.15
      3671603.55     10219167.57      3671537.24     10219199.69
      3671557.55     10219297.27      3671501.71     10219422.51

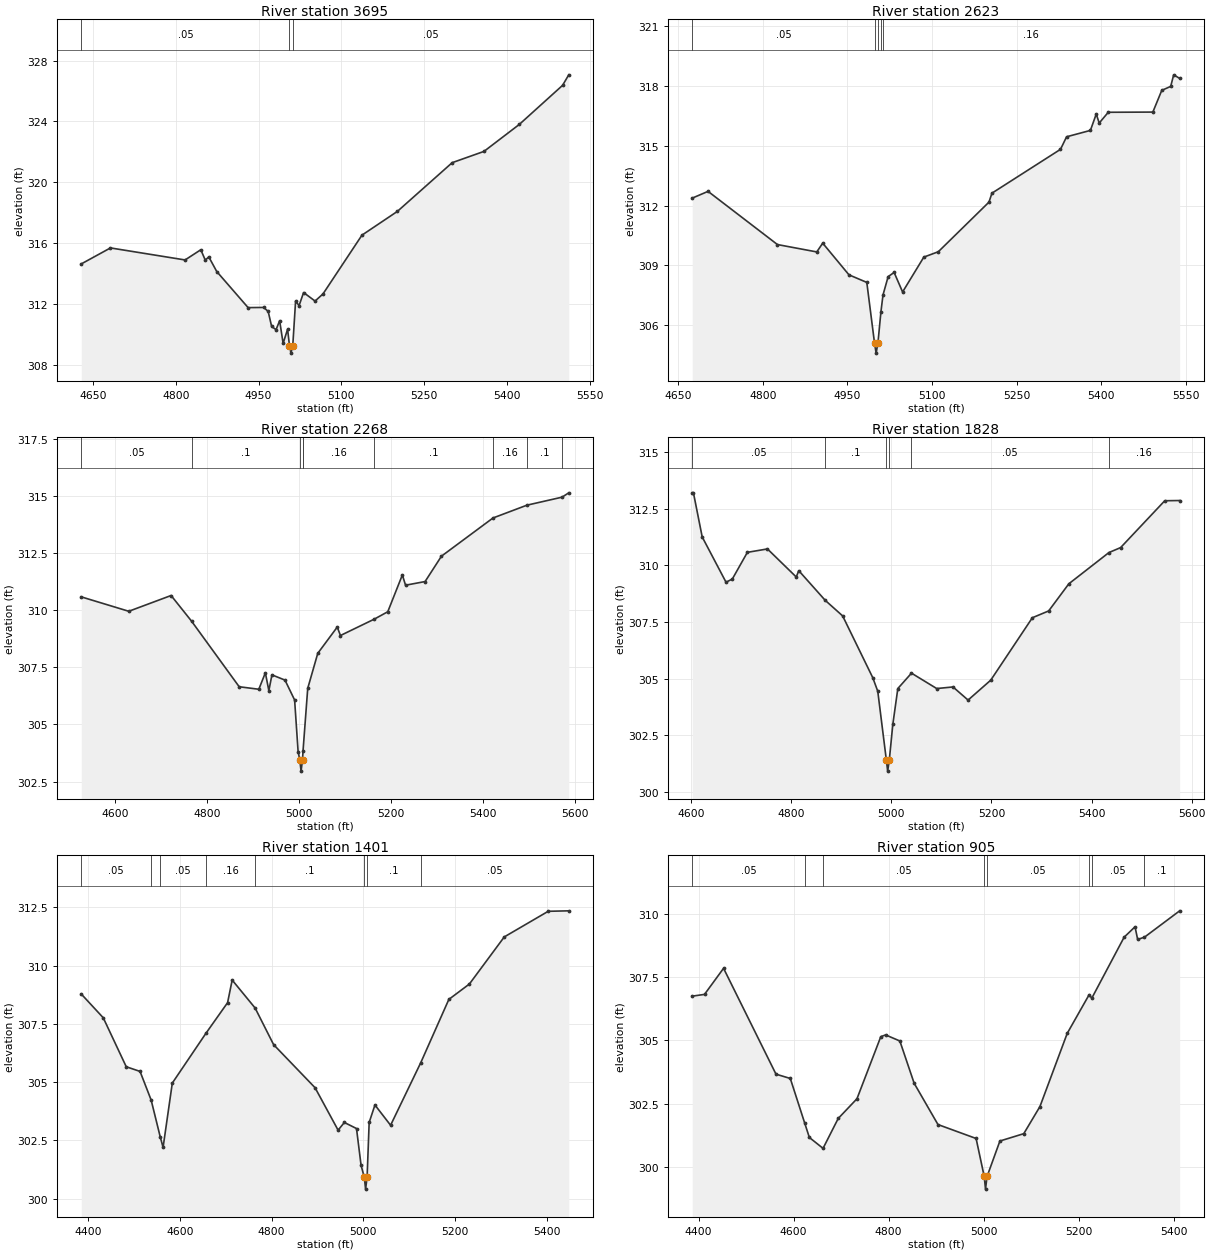
Type RM Length L Ch R = 1,3695,1072,1072,1072
BEGIN DESCRIPTION:
UNT050 IN GIBB 8.0
END DESCRIPTION:
XS GIS Cut Line= 3
      3670633.91     10216828.02      3671078.51     10216480.62
      3671327.82     10216281.17
#Sta/Elev= 30
  4628.7  314.64  4681.6  315.69  4816.8  314.90  4845.3  315.57  4853.4  314.89
  4859.8  315.10  4874.2  314.14  4931.0  311.77  4959.2  311.78  4967.4  311.52
  4973.7  310.53  4981.7  310.32  4988.2  310.91  4994.5  309.42  5002.6  310.35
  5006.0  309.28  5008.7  308.78  5012.0  309.28  5017.1  312.20  5023.4  311.90
  5031.6  312.76  5052.4  312.20  5066.8  312.67  5137.4  316.53  5201.6  318.09
  5300.9  321.29  5358.5  322.03  5422.5  323.80  5501.0  326.37  5512.2  327.06
#Mann=3,-1,0
  4628.7    0.05       0  5006.0    0.03       0  5012.0    0.05       0
Bank Sta=5006,5012
Exp/Cntr=0.3,0.1

Type RM Length L Ch R = 1,2623,355,355,355
BEGIN DESCRIPTION:
UNT050 IN GIBB 6.0
END DESCRIPTION:
XS GIS Cut Line= 3
      3671095.10     10217552.80      3671214.51     10217476.66
      3671442.12     10216791.60
#Sta/Elev= 30
  4675.1  312.38  4703.2  312.72  4826.1  310.05  4895.8  309.68  4906.3  310.12
  4952.8  308.53  4984.4  308.15  4998.1  305.10  5000.9  304.60  5004.1  305.10
  5009.4  306.67  5013.1  307.52  5022.2  308.44  5032.8  308.65  5047.8  307.67
  5085.4  309.42  5111.1  309.69  5200.8  312.18  5206.1  312.63  5327.5  314.83
  5338.3  315.46  5380.5  315.78  5390.8  316.60  5396.1  316.15  5412.1  316.69
  5491.1  316.70  5506.9  317.79  5522.7  317.99  5528.0  318.57  5538.6  318.39
#Mann=5,-1,0
  4675.1    0.05       0  4998.1   0.035       0  5004.1    0.05       0
  5009.4     0.1       0  5013.1    0.16       0
Bank Sta=4998.1,5004.1
Exp/Cntr=0.3,0.1

Type RM Length L Ch R = 1,2268,440,440,440
BEGIN DESCRIPTION:
UNT050 IN GIBB 5.0
END DESCRIPTION:
XS GIS Cut Line= 3
      3671214.52     10217779.07      3671714.49     10217338.74
      3671984.30     10217052.48
#Sta/Elev= 30
  4527.2  310.58  4630.4  309.95  4722.4  310.64  4766.8  309.52  4870.4  306.65
  4913.1  306.54  4927.3  307.26  4934.9  306.48  4941.6  307.17  4970.0  306.94
  4990.9  306.07  4998.5  303.81  5002.1  303.46  5004.9  302.96  5008.1  303.46
  5009.1  303.82  5019.4  306.58  5041.2  308.11  5083.6  309.26  5090.5  308.89
  5164.4  309.61  5193.4  309.93  5225.1  311.54  5232.0  311.09  5274.5  311.25
  5310.1  312.36  5422.1  314.03  5495.9  314.59  5572.2  314.94  5586.8  315.13
#Mann=9,-1,0
  4527.2    0.05       0  4766.8     0.1       0  5002.1    0.07       0
  5008.1     0.1       0  5009.1    0.16       0  5164.4     0.1       0
  5422.1    0.16       0  5495.9     0.1       0  5572.2    0.05       0
Bank Sta=5002.1,5008.1
Exp/Cntr=0.3,0.1

Type RM Length L Ch R = 1,1828,427,427,427
BEGIN DESCRIPTION:
UNT050 IN GIBB 4.0
END DESCRIPTION:
XS GIS Cut Line= 3
      3671242.13     10217891.64      3671782.59     10217853.03
      3672212.10     10217802.64
#Sta/Elev= 30
  4601.8  313.21  4604.3  313.21  4621.8  311.26  4669.4  309.26  4682.0  309.40
  4712.1  310.58  4752.2  310.73  4809.8  309.49  4814.8  309.77  4867.6  308.46
  4902.5  307.77  4962.7  305.04  4972.7  304.44  4989.8  301.41  4992.5  300.91
  4995.8  301.41  5002.8  302.98  5012.8  304.56  5040.1  305.24  5090.5  304.56
  5123.1  304.63  5153.2  304.05  5198.5  304.93  5281.7  307.69  5314.3  307.99
  5354.6  309.19  5434.7  310.57  5458.1  310.79  5546.3  312.86  5576.1  312.87
#Mann=6,-1,0
  4601.8    0.05       0  4867.6     0.1       0  4989.8    0.07       0
  4995.8     0.1       0  5040.1    0.05       0  5434.7    0.16       0
Bank Sta=4989.8,4995.8
Exp/Cntr=0.3,0.1

Type RM Length L Ch R = 1,1401,496,496,496
BEGIN DESCRIPTION:
UNT050 IN GIBB 3.0
END DESCRIPTION:
XS GIS Cut Line= 3
      3671064.43     10218295.93      3671692.11     10218241.64
      3672121.77     10218191.46
#Sta/Elev= 30
  4385.2  308.78  4433.1  307.76  4483.2  305.66  4513.3  305.46  4537.5  304.23
  4557.3  302.65  4563.5  302.20  4583.6  304.96  4656.7  307.09  4704.1  308.41
  4714.1  309.38  4764.1  308.18  4804.4  306.61  4894.8  304.76  4945.0  302.94
  4958.6  303.27  4985.1  303.01  4995.1  301.43  5002.2  300.91  5004.9  300.41
  5008.2  300.91  5012.7  303.27  5025.3  304.02  5059.4  303.15  5125.3  305.84
  5186.4  308.55  5231.2  309.21  5307.2  311.23  5403.0  312.33  5447.8  312.35
#Mann=8,-1,0
  4385.2    0.05       0  4537.5    0.12       0  4557.3    0.05       0
  4656.7    0.16       0  4764.1     0.1       0  5002.2    0.07       0
  5008.2     0.1       0  5125.3    0.05       0
Bank Sta=5002.2,5008.2
Exp/Cntr=0.3,0.1

Type RM Length L Ch R = 1,905,338,338,338
BEGIN DESCRIPTION:
UNT050 IN GIBB 2.0
END DESCRIPTION:
XS GIS Cut Line= 3
      3670986.25     10218677.88      3671731.47     10218625.49
      3671983.90     10218507.75
#Sta/Elev= 30
  4386.7  306.75  4412.6  306.82  4452.7  307.85  4563.0  303.67  4593.1  303.50
  4623.2  301.75  4633.2  301.17  4662.0  300.74  4693.9  301.92  4733.4  302.70
  4783.5  305.15  4793.6  305.22  4823.6  304.98  4853.7  303.31  4903.8  301.68
  4984.0  301.13  5001.1  299.63  5003.8  299.13  5007.1  299.63  5034.1  301.03
  5084.3  301.32  5118.3  302.39  5175.7  305.28  5221.9  306.81  5227.4  306.67
  5295.5  309.08  5318.4  309.49  5323.9  308.99  5338.3  309.08  5412.3  310.12
#Mann=8,-1,0
  4386.7    0.05       0  4623.2    0.12       0  4662.0    0.05       0
  5001.1    0.04       0  5007.1    0.05       0  5221.9     0.1       0
  5227.4    0.05       0  5338.3     0.1       0
Bank Sta=5001.1,5007.1
Exp/Cntr=0.3,0.1

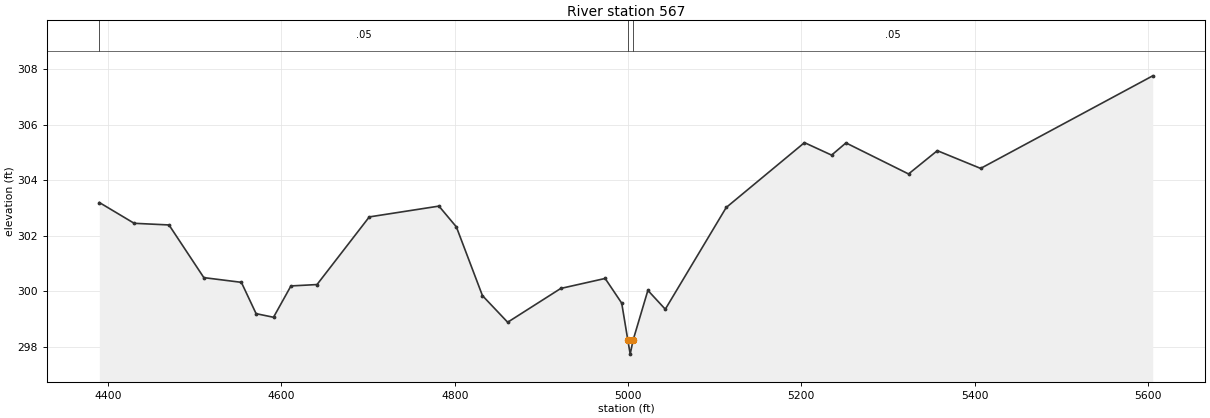
Type RM Length L Ch R = 1,567,0,0,0
BEGIN DESCRIPTION:
UNT050 IN GIBB 1.0
END DESCRIPTION:
XS GIS Cut Line= 3
      3671032.04     10219012.15      3671846.83     10218933.75
      3672027.99     10218580.44
#Sta/Elev= 30
  4389.9  303.20  4430.1  302.45  4470.3  302.39  4510.5  300.49  4553.8  300.32
  4570.8  299.19  4590.9  299.06  4611.0  300.19  4641.1  300.24  4701.4  302.68
  4781.8  303.07  4801.9  302.32  4832.0  299.84  4861.1  298.88  4922.4  300.10
  4973.6  300.46  4992.7  299.57  4999.8  298.23  5002.5  297.73  5005.8  298.23
  5022.9  300.03  5043.0  299.35  5113.3  303.02  5203.6  305.36  5234.9  304.91
  5251.5  305.35  5323.7  304.23  5356.9  305.07  5406.9  304.43  5605.5  307.77
#Mann=3,-1,0
  4389.9    0.05       0  4999.8    0.03       0  5005.8    0.05       0
Bank Sta=4999.8,5005.8
Exp/Cntr=0.3,0.1

Chan Stop Cuts=-1