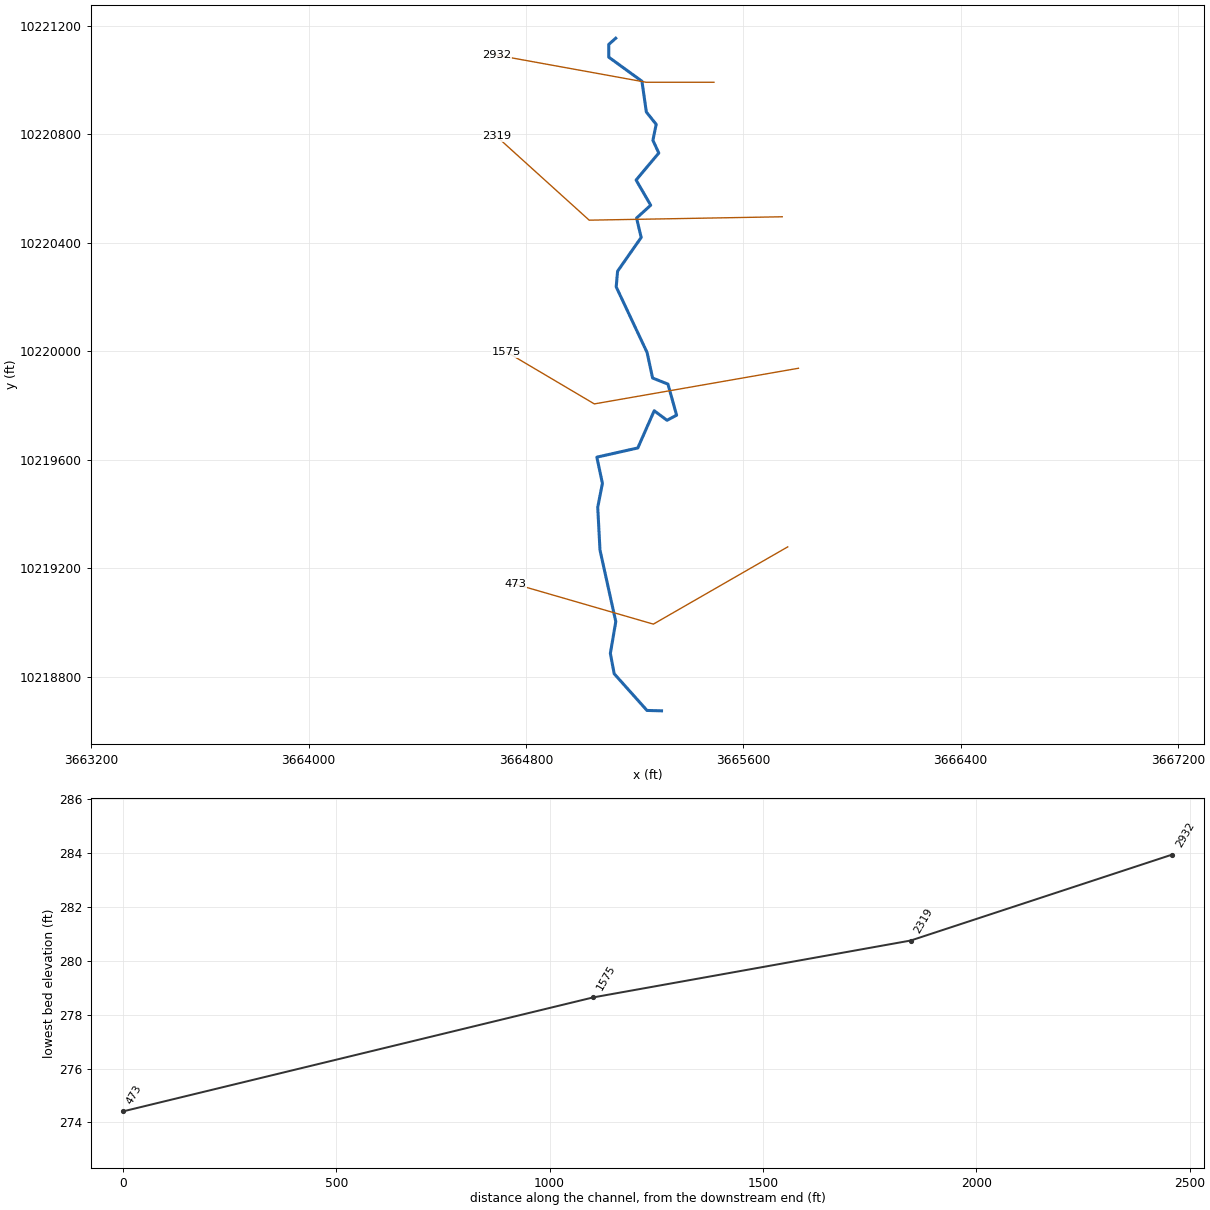
--- UNT051 IN GIBB.prj (project) ---

Proj Title=UNT051 IN GIBB Base Level Engineering
Current Plan=p01
Default Exp/Contr=0.3,0.1
English Units
Geom File=g01
Flow File=f01
Plan File=p01
BEGIN DESCRIPTION:
UNT051 IN GIBB
END DESCRIPTION:

--- UNT051 IN GIBB.p01 (plan) ---

Plan Title=Multiple Run
Short Identifier=Multiple
Geom File=g01
Flow File=f01
Subcritical Flow
K Sum by GR= 0
Std Step Tol= 0.01
Critical Tol= 0.01
Num of Std Step Trials= 20
Max Error Tol= 0.3
Flow Tol Ratio= 0.001
Split Flow NTrial= 30
Split Flow Tol= 0.02
Split Flow Ratio= 0.02
Log Output Level= 0
Friction Slope Method= 1
Unsteady Friction Slope Method= 2
Unsteady Bridges Friction Slope Method= 1
Parabolic Critical Depth
Global Vel Dist=  1 , 1 , 1
Global Log Level= 0
CheckData=True
Encroach Param= -1, 0, 0, 0
BEGIN DESCRIPTION:
Multiple Run
END DESCRIPTION:

--- UNT051 IN GIBB.f01 (steady flow) ---

Flow Title=Multiple
Number of Profiles=7
Profile Names=10-year,25-year,50-year,1pct_min,100-year,1pct_plu,500-year
River Rch & RM= UNT051 IN GIBB,Reach-1,2932
     738    1003    1220    1089    1472    1991    2141
Boundary for River Rch & Prof#=UNT051 IN GIBB,Reach-1,1
Up Type=0
Dn Type=3
Dn Slope=0.005
Boundary for River Rch & Prof#=UNT051 IN GIBB,Reach-1,2
Up Type=0
Dn Type=3
Dn Slope=0.005
Boundary for River Rch & Prof#=UNT051 IN GIBB,Reach-1,3
Up Type=0
Dn Type=3
Dn Slope=0.005
Boundary for River Rch & Prof#=UNT051 IN GIBB,Reach-1,4
Up Type=0
Dn Type=3
Dn Slope=0.005
Boundary for River Rch & Prof#=UNT051 IN GIBB,Reach-1,5
Up Type=0
Dn Type=3
Dn Slope=0.005
Boundary for River Rch & Prof#=UNT051 IN GIBB,Reach-1,6
Up Type=0
Dn Type=3
Dn Slope=0.005
Boundary for River Rch & Prof#=UNT051 IN GIBB,Reach-1,7
Up Type=0
Dn Type=3
Dn Slope=0.005

--- UNT051 IN GIBB.g01 (geometry) ---

Geom Title=Existing Conditions

River Reach=UNT051 IN GIBB,Reach-1
Reach XY= 30
      3665130.29     10221154.05      3665104.72     10221131.10
      3665104.72     10221084.19      3665226.88     10220995.32
      3665243.10     10220881.93      3665279.34     10220836.37
      3665267.25     10220777.47      3665288.91     10220730.71
      3665205.39     10220630.96      3665259.11     10220538.27
      3665207.13     10220490.73      3665224.08     10220419.23
      3665137.22     10220294.79      3665132.16     10220236.96
      3665245.86     10219994.97      3665266.11     10219900.91
      3665322.61     10219878.40      3665354.55     10219763.81
      3665319.14     10219745.06      3665272.11     10219780.23
      3665211.63     10219642.99      3665060.91     10219609.00
      3665081.37     10219512.42      3665064.13     10219424.31
      3665072.45     10219266.51      3665130.61     10219002.53
      3665110.63     10218885.34      3665124.69     10218810.34
      3665245.53     10218674.93      3665298.96     10218673.56

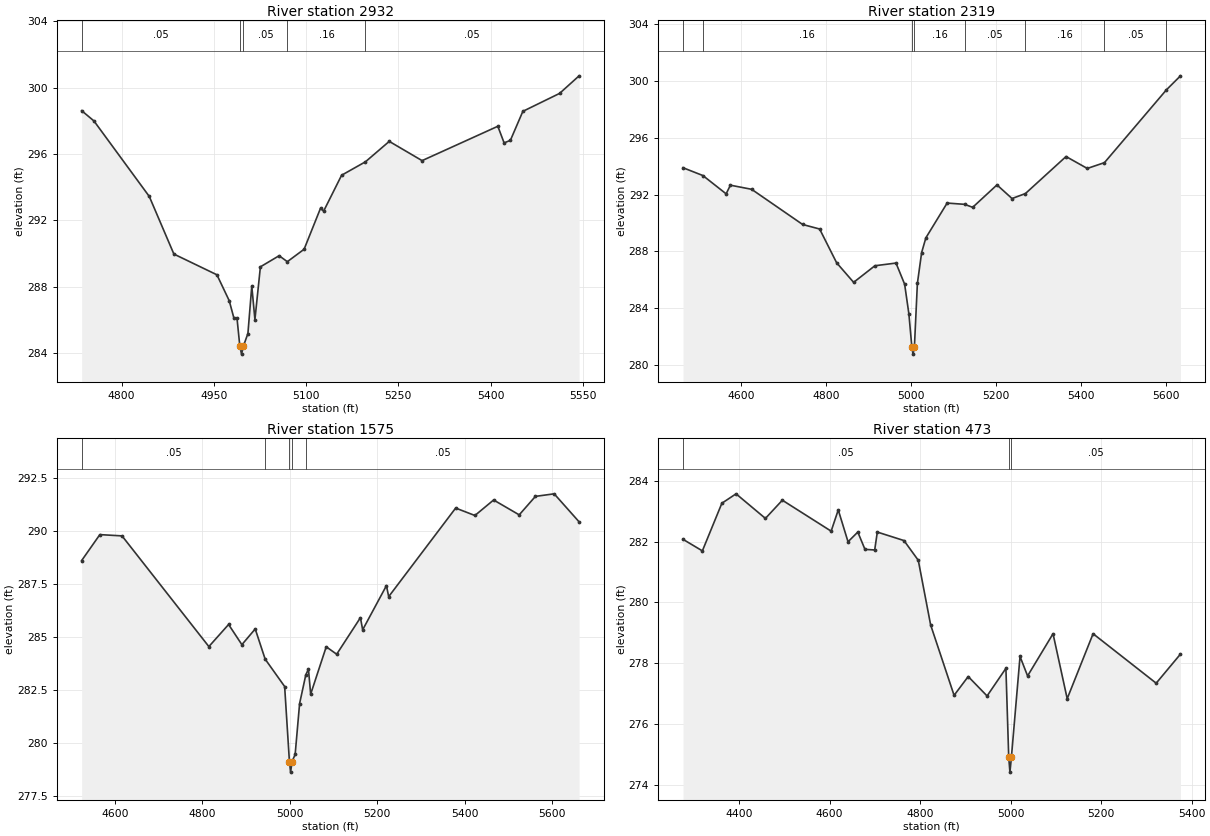
Type RM Length L Ch R = 1,2932,613,613,613
BEGIN DESCRIPTION:
UNT051 IN GIBB 4.0
END DESCRIPTION:
XS GIS Cut Line= 3
      3665492.14     10220991.64      3665242.11     10220991.64
      3664692.06     10221091.65
#Sta/Elev= 30
  4735.0  298.61  4755.0  297.99  4845.0  293.44  4885.0  289.97  4955.0  288.72
  4975.0  287.16  4982.5  286.13  4987.6  286.13  4992.2  284.44  4995.0  283.94
  4998.2  284.44  5005.4  285.18  5011.7  288.04  5016.8  286.02  5025.7  289.20
  5056.2  289.87  5069.5  289.51  5096.8  290.26  5123.5  292.73  5128.6  292.56
  5157.8  294.72  5196.6  295.53  5235.3  296.76  5288.7  295.60  5411.9  297.67
  5422.1  296.67  5432.3  296.82  5452.6  298.57  5512.3  299.65  5544.1  300.71
#Mann=5,-1,0
  4735.0    0.05       0  4992.2    0.03       0  4998.2    0.05       0
  5069.5    0.16       0  5196.6    0.05       0
Bank Sta=4992.2,4998.2
Exp/Cntr=0.3,0.1

Type RM Length L Ch R = 1,2319,744,744,744
BEGIN DESCRIPTION:
UNT051 IN GIBB 3.0
END DESCRIPTION:
XS GIS Cut Line= 3
      3665743.45     10220495.55      3665032.69     10220483.03
      3664692.09     10220791.65
#Sta/Elev= 30
  4462.8  293.89  4509.5  293.34  4564.2  292.05  4574.2  292.66  4624.2  292.37
  4744.2  289.89  4784.2  289.57  4824.2  287.19  4864.2  285.81  4914.2  286.98
  4963.9  287.17  4984.2  285.68  4994.2  283.59  5001.2  281.25  5004.0  280.75
  5007.2  281.25  5014.2  285.73  5024.2  287.91  5034.2  288.95  5084.2  291.40
  5125.4  291.31  5144.3  291.10  5201.5  292.68  5236.9  291.72  5268.4  292.07
  5364.0  294.68  5414.0  293.84  5454.4  294.25  5600.1  299.38  5633.3  300.37
#Mann=8,-1,0
  4462.8    0.05       0  4509.5    0.16       0  5001.2    0.07       0
  5007.2    0.16       0  5125.4    0.05       0  5268.4    0.16       0
  5454.4    0.05       0  5600.1    0.16       0
Bank Sta=5001.2,5007.2
Exp/Cntr=0.3,0.1

Type RM Length L Ch R = 1,1575,1102,1102,1102
BEGIN DESCRIPTION:
UNT051 IN GIBB 2.0
END DESCRIPTION:
XS GIS Cut Line= 3
      3665803.04     10219936.91      3665051.64     10219805.41
      3664729.17     10219996.39
#Sta/Elev= 30
  4524.2  288.60  4565.8  289.82  4616.5  289.76  4815.1  284.55  4860.2  285.59
  4890.6  284.64  4921.1  285.38  4943.8  283.96  4988.4  282.67  4999.3  279.14
  5002.0  278.64  5005.3  279.14  5012.4  279.47  5022.6  281.87  5036.8  283.22
  5042.8  283.49  5047.9  282.31  5083.5  284.54  5107.4  284.19  5161.7  285.91
  5166.8  285.34  5221.2  287.42  5226.3  286.90  5379.5  291.07  5423.5  290.72
  5466.3  291.45  5524.8  290.75  5561.9  291.62  5604.8  291.74  5661.8  290.42
#Mann=5,-1,0
  4524.2    0.05       0  4943.8    0.16       0  4999.3    0.07       0
  5005.3    0.16       0  5036.8    0.05       0
Bank Sta=4999.3,5005.3
Exp/Cntr=0.3,0.1

Type RM Length L Ch R = 1,473,0,0,0
BEGIN DESCRIPTION:
UNT051 IN GIBB 1.0
END DESCRIPTION:
XS GIS Cut Line= 3
      3665763.60     10219278.20      3665268.94     10218993.30
      3664761.69     10219140.46
#Sta/Elev= 30
  4276.4  282.08  4319.1  281.70  4362.2  283.27  4393.5  283.58  4458.4  282.77
  4495.8  283.37  4603.6  282.35  4619.3  283.05  4640.9  282.00  4662.5  282.32
  4678.3  281.75  4699.8  281.73  4705.6  282.32  4764.5  282.04  4796.1  281.39
  4823.4  279.26  4875.2  276.94  4906.4  277.56  4948.1  276.92  4989.7  277.83
  4995.9  274.91  4998.6  274.41  5001.9  274.91  5020.9  278.22  5037.6  277.58
  5093.8  278.97  5125.1  276.83  5182.3  278.97  5321.7  277.34  5375.4  278.30
#Mann=3,-1,0
  4276.4    0.05       0  4995.9    0.03       0  5001.9    0.05       0
Bank Sta=4995.9,5001.9
Exp/Cntr=0.3,0.1

Chan Stop Cuts=-1