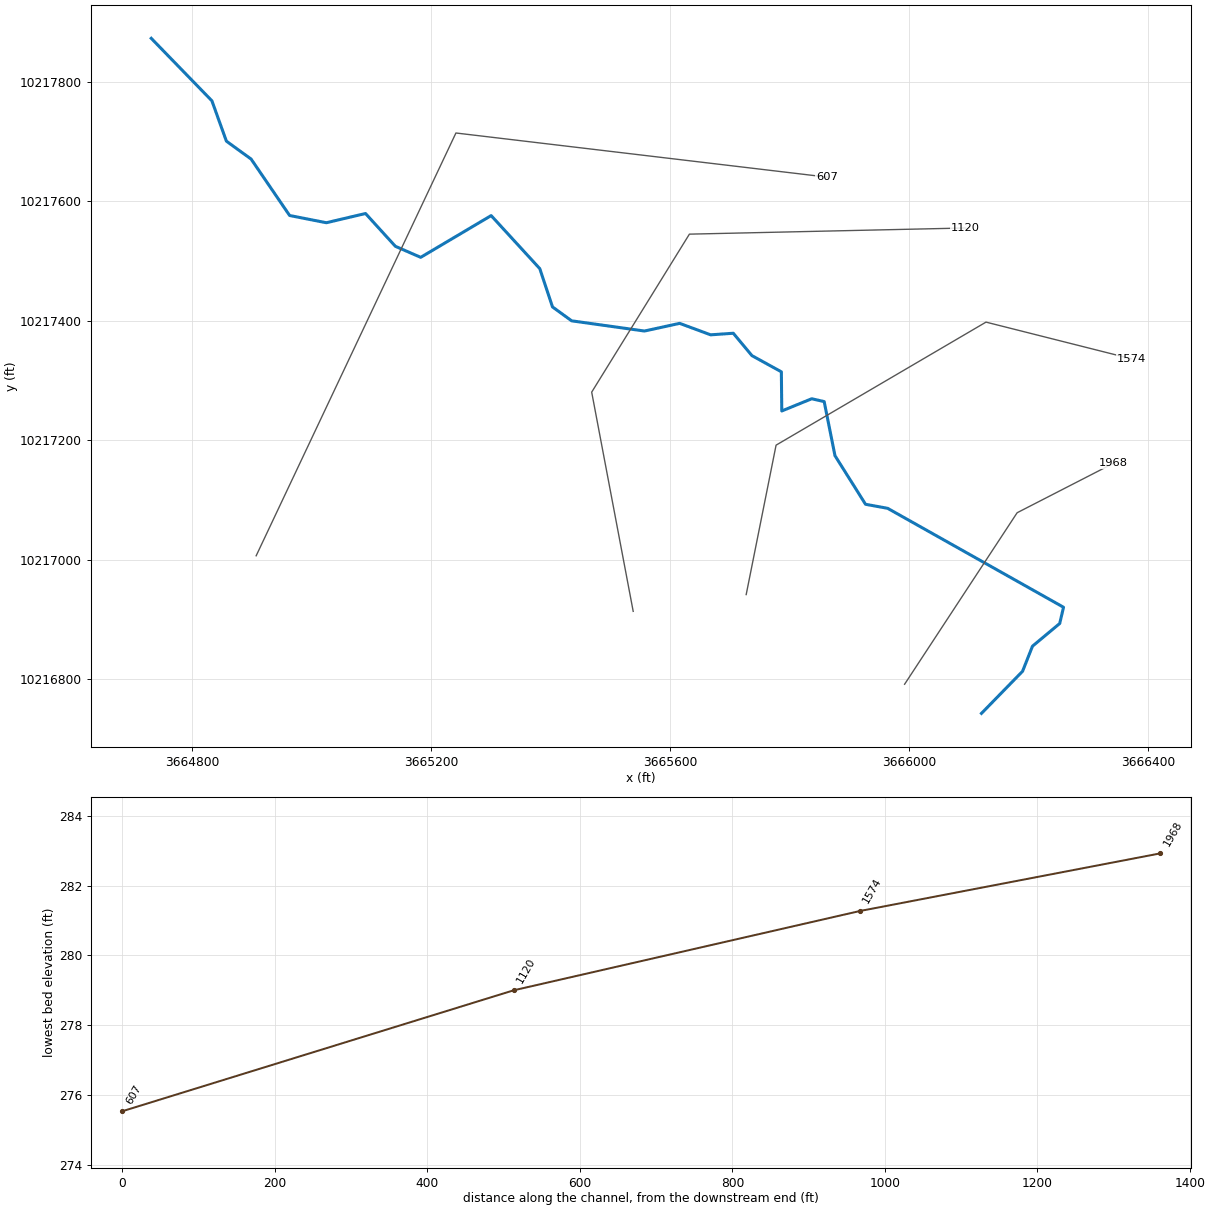
--- UNT052 IN GIBB.prj (project) ---

Proj Title=UNT052 IN GIBB Base Level Engineering
Current Plan=p01
Default Exp/Contr=0.3,0.1
English Units
Geom File=g01
Flow File=f01
Plan File=p01
BEGIN DESCRIPTION:
UNT052 IN GIBB
END DESCRIPTION:

--- UNT052 IN GIBB.p01 (plan) ---

Plan Title=Multiple Run
Short Identifier=Multiple
Geom File=g01
Flow File=f01
Subcritical Flow
K Sum by GR= 0
Std Step Tol= 0.01
Critical Tol= 0.01
Num of Std Step Trials= 20
Max Error Tol= 0.3
Flow Tol Ratio= 0.001
Split Flow NTrial= 30
Split Flow Tol= 0.02
Split Flow Ratio= 0.02
Log Output Level= 0
Friction Slope Method= 1
Unsteady Friction Slope Method= 2
Unsteady Bridges Friction Slope Method= 1
Parabolic Critical Depth
Global Vel Dist=  1 , 1 , 1
Global Log Level= 0
CheckData=True
Encroach Param= -1, 0, 0, 0
BEGIN DESCRIPTION:
Multiple Run
END DESCRIPTION:

--- UNT052 IN GIBB.f01 (steady flow) ---

Flow Title=Multiple
Number of Profiles=7
Profile Names=10-year,25-year,50-year,1pct_min,100-year,1pct_plu,500-year
River Rch & RM= UNT052 IN GIBB,Reach-1,1968
     468     619     741     652     881    1192    1243
Boundary for River Rch & Prof#=UNT052 IN GIBB,Reach-1,1
Up Type=0
Dn Type=3
Dn Slope=0.005
Boundary for River Rch & Prof#=UNT052 IN GIBB,Reach-1,2
Up Type=0
Dn Type=3
Dn Slope=0.005
Boundary for River Rch & Prof#=UNT052 IN GIBB,Reach-1,3
Up Type=0
Dn Type=3
Dn Slope=0.005
Boundary for River Rch & Prof#=UNT052 IN GIBB,Reach-1,4
Up Type=0
Dn Type=3
Dn Slope=0.005
Boundary for River Rch & Prof#=UNT052 IN GIBB,Reach-1,5
Up Type=0
Dn Type=3
Dn Slope=0.005
Boundary for River Rch & Prof#=UNT052 IN GIBB,Reach-1,6
Up Type=0
Dn Type=3
Dn Slope=0.005
Boundary for River Rch & Prof#=UNT052 IN GIBB,Reach-1,7
Up Type=0
Dn Type=3
Dn Slope=0.005

--- UNT052 IN GIBB.g01 (geometry) ---

Geom Title=Existing Conditions

River Reach=UNT052 IN GIBB,Reach-1
Reach XY= 30
      3666120.74     10216742.90      3666189.49     10216813.37
      3666206.08     10216855.33      3666251.63     10216893.29
      3666258.02     10216920.49      3665963.76     10217086.04
      3665926.76     10217092.80      3665875.62     10217174.15
      3665857.55     10217264.67      3665836.72     10217269.38
      3665786.64     10217248.96      3665785.92     10217314.44
      3665736.67     10217341.58      3665705.48     10217379.01
      3665667.63     10217376.36      3665615.77     10217395.55
      3665556.85     10217382.72      3665435.05     10217399.79
      3665402.98     10217423.10      3665381.79     10217487.07
      3665300.38     10217575.88      3665182.53     10217506.03
      3665140.16     10217524.48      3665090.19     10217579.38
      3665024.62     10217563.95      3664963.21     10217576.03
      3664898.78     10217670.48      3664857.44     10217700.42
      3664833.18     10217767.94      3664731.71     10217872.51

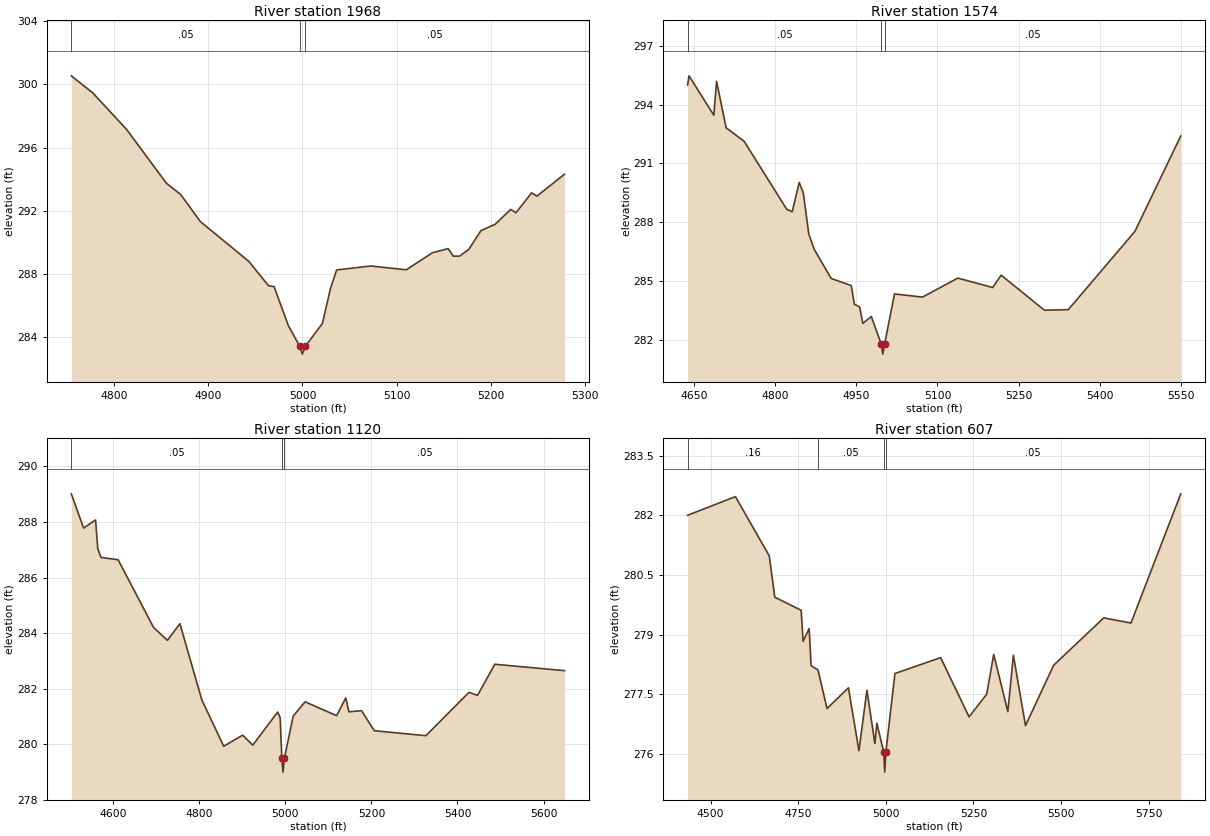
Type RM Length L Ch R = 1,1968,394,394,394
BEGIN DESCRIPTION:
UNT052 IN GIBB 4.0
END DESCRIPTION:
XS GIS Cut Line= 3
      3665992.11     10216791.64      3666180.39     10217078.62
      3666341.02     10217161.11
#Sta/Elev= 30
  4754.5  300.54  4777.1  299.47  4813.3  297.14  4855.5  293.74  4870.6  293.03
  4891.6  291.31  4942.9  288.80  4964.0  287.25  4969.9  287.19  4985.0  284.73
  4997.1  283.42  4999.9  282.92  5003.1  283.42  5021.2  284.86  5029.6  287.04
  5036.3  288.25  5072.5  288.50  5110.3  288.26  5138.1  289.34  5154.7  289.60
  5160.3  289.12  5167.1  289.13  5176.8  289.56  5189.6  290.74  5204.7  291.14
  5221.2  292.08  5226.8  291.87  5243.4  293.13  5249.0  292.92  5278.3  294.31
#Mann=3,-1,0
  4754.5    0.05       0  4997.1    0.03       0  5003.1    0.05       0
Bank Sta=4997.1,5003.1
Exp/Cntr=0.3,0.1

Type RM Length L Ch R = 1,1574,454,454,454
BEGIN DESCRIPTION:
UNT052 IN GIBB 3.0
END DESCRIPTION:
XS GIS Cut Line= 4
      3665727.08     10216941.69      3665777.09     10217191.73
      3666128.31     10217397.63      3666371.28     10217336.32
#Sta/Elev= 30
  4637.6  295.00  4640.2  295.47  4686.1  293.46  4691.2  295.19  4708.9  292.82
  4742.2  292.13  4821.1  288.66  4831.3  288.54  4844.1  290.03  4851.7  289.50
  4861.9  287.39  4872.1  286.61  4903.3  285.13  4940.4  284.77  4946.2  283.82
  4956.1  283.67  4961.9  282.84  4977.6  283.19  4996.1  281.77  4998.8  281.27
  5002.1  281.77  5020.5  284.34  5072.3  284.18  5137.8  285.15  5202.2  284.67
  5217.9  285.30  5298.0  283.51  5342.2  283.54  5465.4  287.53  5550.3  292.40
#Mann=3,-1,0
  4637.6    0.05       0  4996.1    0.03       0  5002.1    0.05       0
Bank Sta=4996.1,5002.1
Exp/Cntr=0.3,0.1

Type RM Length L Ch R = 1,1120,513,513,513
BEGIN DESCRIPTION:
UNT052 IN GIBB 2.0
END DESCRIPTION:
XS GIS Cut Line= 4
      3665538.04     10216913.64      3665468.59     10217280.45
      3665632.07     10217544.84      3666094.08     10217555.16
#Sta/Elev= 30
  4502.4  289.01  4530.9  287.78  4558.8  288.07  4563.9  287.03  4571.6  286.72
  4611.1  286.64  4693.7  284.20  4725.9  283.74  4754.8  284.34  4805.7  281.60
  4856.6  279.93  4900.6  280.33  4924.1  279.97  4982.0  281.16  4987.9  280.96
  4991.7  279.50  4994.4  279.00  4997.7  279.50  5018.2  281.02  5045.8  281.53
  5119.1  281.03  5140.4  281.67  5147.5  281.17  5177.0  281.21  5206.6  280.49
  5326.6  280.31  5426.7  281.87  5446.7  281.76  5486.7  282.88  5648.7  282.65
#Mann=3,-1,0
  4502.4    0.05       0  4991.7    0.03       0  4997.7    0.05       0
Bank Sta=4991.7,4997.7
Exp/Cntr=0.3,0.1

Type RM Length L Ch R = 1,607,0,0,0
BEGIN DESCRIPTION:
UNT052 IN GIBB 1.0
END DESCRIPTION:
XS GIS Cut Line= 3
      3664907.24     10217006.63      3665241.45     10217714.11
      3665862.12     10217640.32
#Sta/Elev= 30
  4434.2  282.00  4570.6  282.47  4667.2  280.98  4683.1  279.94  4758.3  279.61
  4763.8  278.83  4781.1  279.15  4786.6  278.22  4806.3  278.11  4832.1  277.14
  4893.2  277.66  4923.2  276.08  4946.0  277.60  4968.7  276.26  4974.3  276.77
  4994.0  276.04  4996.8  275.54  5000.0  276.04  5025.9  278.02  5156.4  278.42
  5237.5  276.93  5287.8  277.50  5307.9  278.50  5348.2  277.06  5364.0  278.48
  5398.6  276.71  5479.1  278.23  5622.0  279.42  5699.6  279.29  5841.7  282.54
#Mann=4,-1,0
  4434.2    0.16       0  4806.3    0.05       0  4994.0    0.03       0
  5000.0    0.05       0
Bank Sta=4994,5000
Exp/Cntr=0.3,0.1

Chan Stop Cuts=-1