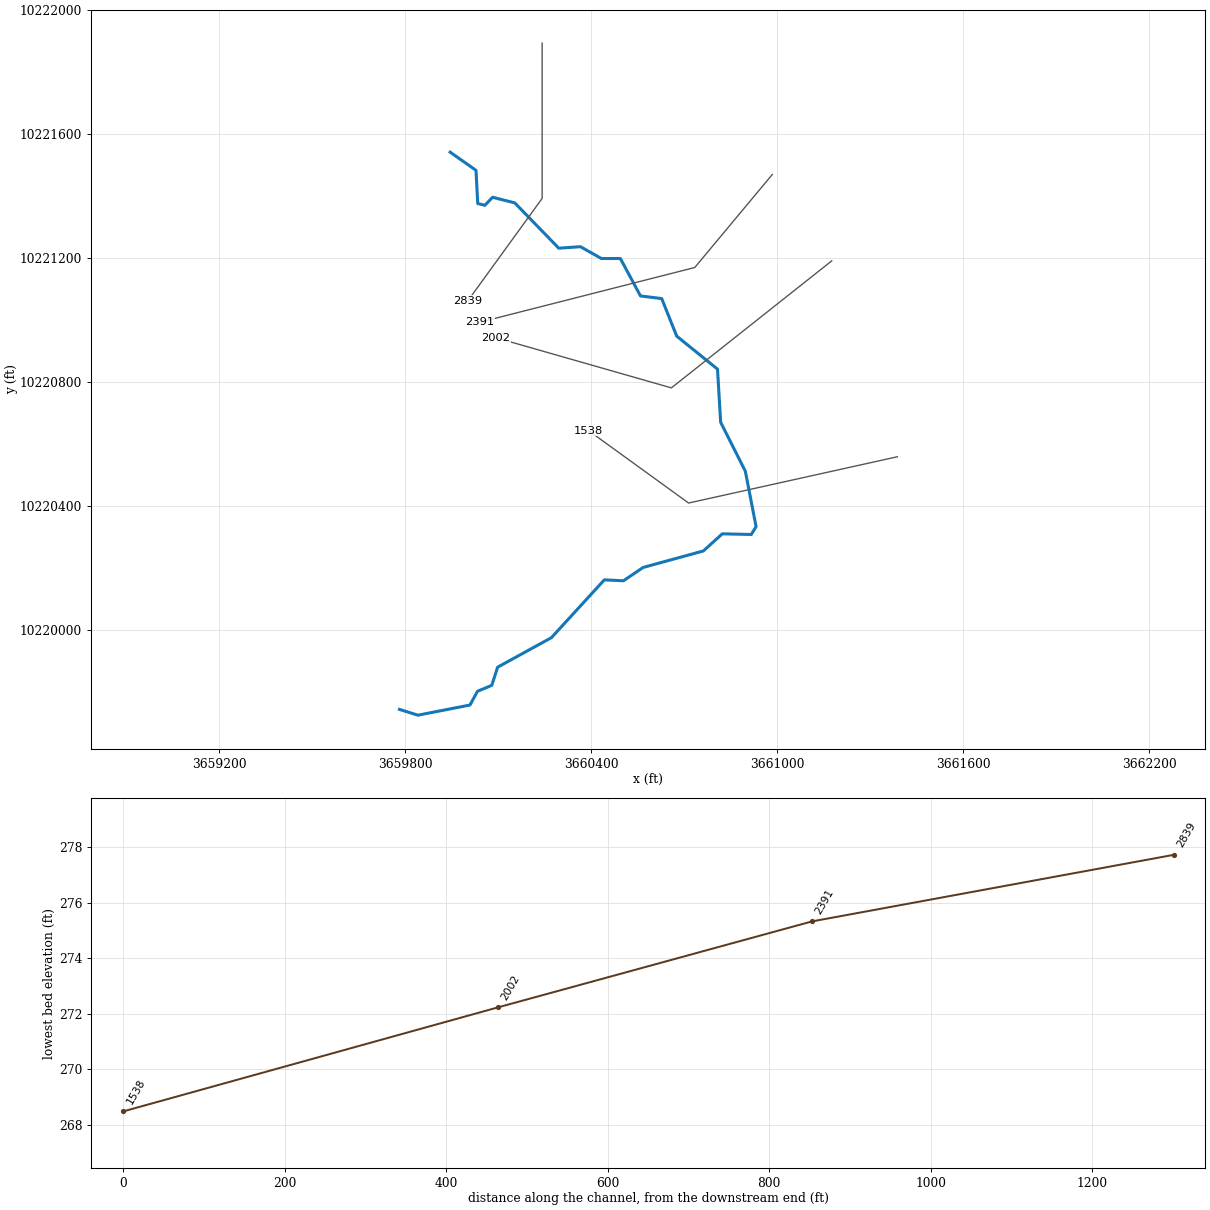
--- UNT053 IN GIBB.prj (project) ---

Proj Title=UNT053 IN GIBB Base Level Engineering
Current Plan=p01
Default Exp/Contr=0.3,0.1
English Units
Geom File=g01
Flow File=f01
Plan File=p01
Y Axis Title=Elevation
X Axis Title(PF)=Main Channel Distance
X Axis Title(XS)=Station
BEGIN DESCRIPTION:
UNT053 IN GIBB
END DESCRIPTION:
DSS Export Rating Curves= 0
DSS Export Rating Curve Sorted= 0
DSS Export Volume Flow Curves= 0
DXF OffsetX= 0
DXF OffsetY= 0
DXF ScaleX= 1
DXF ScaleY= 10

--- UNT053 IN GIBB.p01 (plan) ---

Plan Title=Multiple Run
Short Identifier=Multiple
Geom File=g01
Flow File=f01
Subcritical Flow
K Sum by GR= 0
Std Step Tol= 0.01
Critical Tol= 0.01
Num of Std Step Trials= 20
Max Error Tol= 0.3
Flow Tol Ratio= 0.001
Split Flow NTrial= 30
Split Flow Tol= 0.02
Split Flow Ratio= 0.02
Log Output Level= 0
Friction Slope Method= 1
Unsteady Friction Slope Method= 2
Unsteady Bridges Friction Slope Method= 1
Parabolic Critical Depth
Global Vel Dist=  1 , 1 , 1
Global Log Level= 0
CheckData=True
Encroach Param= -1, 0, 0, 0
BEGIN DESCRIPTION:
Multiple Run
END DESCRIPTION:

--- UNT053 IN GIBB.f01 (steady flow) ---

Flow Title=Multiple
Number of Profiles=7
Profile Names=10-year,25-year,50-year,1pct_min,100-year,1pct_plu,500-year
River Rch & RM= UNT053 IN GIBB,Reach-1,2839
     661     894    1086     968    1309    1771    1900
Boundary for River Rch & Prof#=UNT053 IN GIBB,Reach-1,1
Up Type=0
Dn Type=3
Dn Slope=0.005
Boundary for River Rch & Prof#=UNT053 IN GIBB,Reach-1,2
Up Type=0
Dn Type=3
Dn Slope=0.005
Boundary for River Rch & Prof#=UNT053 IN GIBB,Reach-1,3
Up Type=0
Dn Type=3
Dn Slope=0.005
Boundary for River Rch & Prof#=UNT053 IN GIBB,Reach-1,4
Up Type=0
Dn Type=3
Dn Slope=0.005
Boundary for River Rch & Prof#=UNT053 IN GIBB,Reach-1,5
Up Type=0
Dn Type=3
Dn Slope=0.005
Boundary for River Rch & Prof#=UNT053 IN GIBB,Reach-1,6
Up Type=0
Dn Type=3
Dn Slope=0.005
Boundary for River Rch & Prof#=UNT053 IN GIBB,Reach-1,7
Up Type=0
Dn Type=3
Dn Slope=0.005

--- UNT053 IN GIBB.g01 (geometry) ---

Geom Title=Existing Conditions
Program Version=4.10

River Reach=UNT053 IN GIBB  ,Reach-1
Reach XY= 30
      3659945.35     10221540.11      3660028.74     10221481.37
      3660034.27     10221374.39      3660057.22     10221368.65
      3660082.32     10221394.57      3660153.78     10221376.43
      3660295.69     10221230.29      3660365.54     10221235.13
      3660433.19     10221196.97      3660494.42     10221196.96
      3660559.35      10221076.2      3660627.74     10221067.74
      3660676.26     10220946.54      3660807.77     10220840.16
      3660817.95     10220668.69      3660897.54     10220510.86
       3660932.2     10220332.06      3660916.79     10220306.76
      3660823.24     10220308.88      3660762.16     10220253.64
       3660567.6     10220200.25      3660504.46     10220157.42
      3660442.64     10220160.31      3660271.92     10219973.81
       3660098.5     10219878.63      3660079.57     10219820.12
      3660033.47     10219800.87      3660009.26     10219756.58
      3659841.35     10219723.81      3659781.71     10219742.51

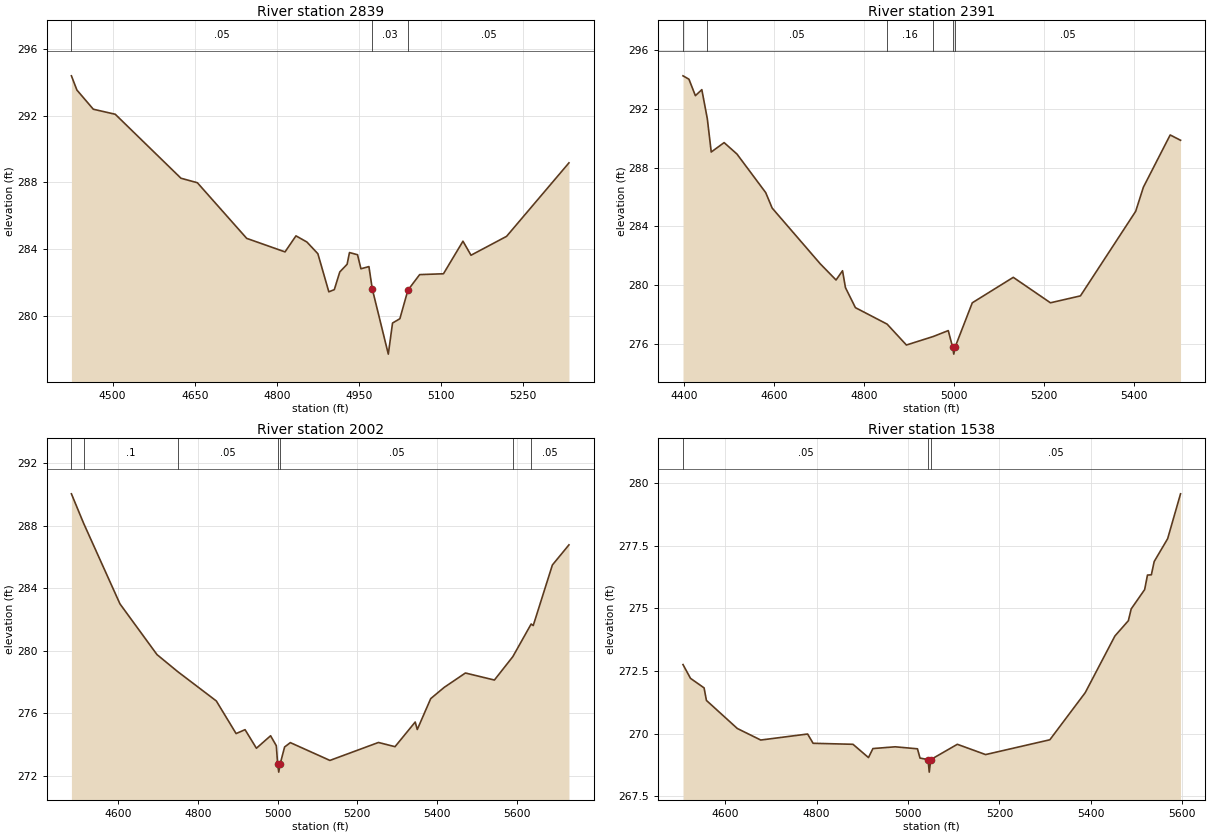
Type RM Length L Ch R = 1 ,2839    ,448,448,448
BEGIN DESCRIPTION:
UNT053 IN GIBB 4.0
END DESCRIPTION:
XS GIS Cut Line= 3
      3660242.11     10221891.67      3660242.11     10221390.83
      3660002.74     10221060.97
#Sta/Elev= 30
  4424.9  294.38  4434.9  293.53  4464.9  292.38  4504.9  292.08  4624.9  288.25
  4654.9  287.98  4744.9  284.65  4814.9  283.84  4834.9   284.8  4854.9  284.43
  4874.9  283.73  4894.9  281.45  4904.9  281.58  4914.9  282.64  4928.3   283.1
  4932.6   283.8  4947.3  283.67  4953.5  282.83  4968.1  282.96  4974.3  281.61
  5003.5  277.72  5011.2  279.58  5024.6  279.84  5039.3  281.55  5060.7  282.48
  5104.2  282.53  5139.8  284.48  5154.5  283.64  5219.4  284.77  5333.3  289.17
#Mann= 3 , 0 , 0
  4424.9     .05       0  4974.3     .03       0  5039.3     .05       0
Bank Sta=4974.3,5039.3
XS Rating Curve= 0 ,0
Exp/Cntr=0.3,0.1

Type RM Length L Ch R = 1 ,2391    ,389,389,389
BEGIN DESCRIPTION:
UNT053 IN GIBB 3.0
END DESCRIPTION:
XS GIS Cut Line= 3
      3660984.49     10221468.06      3660734.47     10221168.03
      3660042.13     10220991.65
#Sta/Elev= 30
  4398.2  294.24  4411.4  294.01  4425.7  292.89    4440   293.3  4452.2  291.32
  4460.9  289.06  4489.5   289.7  4518.1  288.92  4581.9   286.3  4596.2  285.25
    4703  281.46  4738.1  280.36  4752.5  280.99    4759  279.84  4781.1  278.48
  4851.5  277.36  4894.4  275.94  4954.2  276.52  4987.3  276.92  4996.8  275.82
  4999.6  275.32  5002.8  275.82  5040.7  278.81  5131.7  280.54  5214.3  278.81
  5280.9  279.28  5403.6  285.03  5420.7  286.67  5480.2  290.22  5503.2  289.86
#Mann= 6 ,-1 , 0
  4398.2     .16       0  4452.2     .05       0  4851.5     .16       0
  4954.2     .05       0  4996.8     .03       0  5002.8     .05       0
Bank Sta=4996.8,5002.8
XS Rating Curve= 0 ,0
Exp/Cntr=0.3,0.1

Type RM Length L Ch R = 1 ,2002    ,464,464,464
BEGIN DESCRIPTION:
UNT053 IN GIBB 2.0
END DESCRIPTION:
XS GIS Cut Line= 3
      3661176.35     10221189.44      3660658.98     10220779.68
      3660092.14     10220941.63
#Sta/Elev= 30
  4481.9  290.05  4512.6  288.16  4603.8     283  4696.8  279.75  4748.8  278.66
  4845.8  276.78  4895.5  274.69    4918  274.94  4946.5  273.75  4982.1  274.55
  4996.5  273.91  4999.9  272.72  5002.6  272.22  5005.9  272.72  5017.3  273.83
  5031.7  274.11  5131.1  272.97    5253  274.12  5294.6  273.85  5345.3  275.43
  5350.5  274.95  5384.3  276.93  5418.1  277.65  5471.4  278.57  5544.2  278.12
  5590.5  279.62  5636.5  281.71  5641.7  281.61  5689.8  285.49  5731.4  286.78
#Mann= 7 ,-1 , 0
  4481.9     .16       0  4512.6      .1       0  4748.8     .05       0
  4999.9     .03       0  5005.9     .05       0  5590.5     .16       0
  5636.5     .05       0
Bank Sta=4999.9,5005.9
XS Rating Curve= 0 ,0
Exp/Cntr=0.3,0.1

Type RM Length L Ch R = 1 ,1538    ,0,0,0
BEGIN DESCRIPTION:
UNT053 IN GIBB 1.0
END DESCRIPTION:
XS GIS Cut Line= 3
      3661388.11     10220557.49      3660714.54     10220408.19
       3660392.1     10220641.65
#Sta/Elev= 30
  4507.9  272.76  4524.3  272.21    4554  271.83  4559.1  271.33  4626.7  270.21
  4677.9  269.75  4780.4  269.99  4792.4  269.62  4879.6  269.58  4913.5  269.05
  4923.2  269.41  4971.9  269.48  5020.6   269.4  5026.2  269.03  5043.7  268.97
  5046.4  268.47  5049.7  268.97  5107.8  269.58  5169.6  269.17  5310.1  269.76
  5387.5  271.64  5452.4   273.9  5481.8  274.51    5488  274.98  5517.4  275.75
  5523.6  276.33  5532.1  276.34  5538.3  276.87  5567.7  277.78  5595.9  279.57
#Mann= 3 ,-1 , 0
  4507.9     .05       0  5043.7     .03       0  5049.7     .05       0
Bank Sta=5043.7,5049.7
XS Rating Curve= 0 ,0
Exp/Cntr=0.3,0.1

Chan Stop Cuts=-1
Use User Specified Reach Order=0
Composite Channel Slope=5