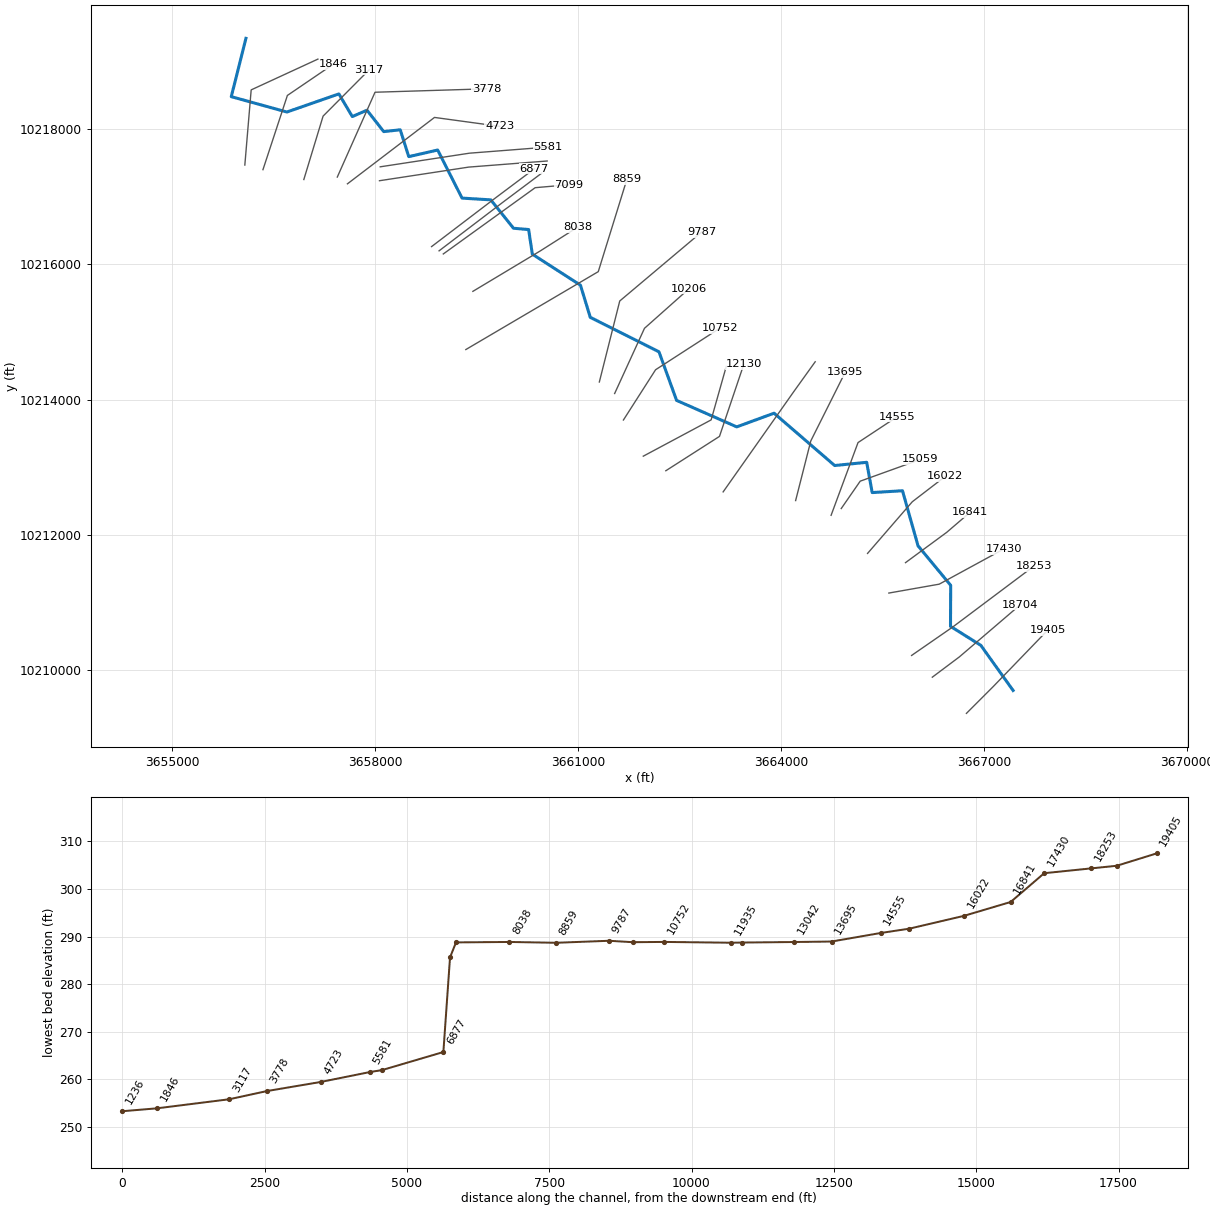
--- UNT054 IN GIBB.prj (project) ---

Proj Title=UNT054 IN GIBB Base Level Engineering
Current Plan=p01
Default Exp/Contr=0.3,0.1
English Units
Geom File=g01
Flow File=f01
Plan File=p01
BEGIN DESCRIPTION:
UNT054 IN GIBB
END DESCRIPTION:

--- UNT054 IN GIBB.p01 (plan) ---

Plan Title=Multiple Run
Short Identifier=Multiple
Geom File=g01
Flow File=f01
Subcritical Flow
K Sum by GR= 0
Std Step Tol= 0.01
Critical Tol= 0.01
Num of Std Step Trials= 20
Max Error Tol= 0.3
Flow Tol Ratio= 0.001
Split Flow NTrial= 30
Split Flow Tol= 0.02
Split Flow Ratio= 0.02
Log Output Level= 0
Friction Slope Method= 1
Unsteady Friction Slope Method= 2
Unsteady Bridges Friction Slope Method= 1
Parabolic Critical Depth
Global Vel Dist=  1 , 1 , 1
Global Log Level= 0
CheckData=True
Encroach Param= -1, 0, 0, 0
BEGIN DESCRIPTION:
Multiple Run
END DESCRIPTION:

--- UNT054 IN GIBB.f01 (steady flow) ---

Flow Title=Multiple
Number of Profiles=7
Profile Names=10-year,25-year,50-year,1pct_min,100-year,1pct_plu,500-year
River Rch & RM= UNT054 IN GIBB,Reach-1,19405
    1232    1710    2111    1905    2576    3483    3837
River Rch & RM= UNT054 IN GIBB,Reach-1,13695
    1388    1935    2396    2168    2932    3965    4390
River Rch & RM= UNT054 IN GIBB,Reach-1,11935
    1384    1923    2375    2143    2898    3919    4316
River Rch & RM= UNT054 IN GIBB,Reach-1,8859
    1891    2666    3325    3026    4093    5535    6206
Boundary for River Rch & Prof#=UNT054 IN GIBB,Reach-1,1
Up Type=0
Dn Type=3
Dn Slope=0.005
Boundary for River Rch & Prof#=UNT054 IN GIBB,Reach-1,2
Up Type=0
Dn Type=3
Dn Slope=0.005
Boundary for River Rch & Prof#=UNT054 IN GIBB,Reach-1,3
Up Type=0
Dn Type=3
Dn Slope=0.005
Boundary for River Rch & Prof#=UNT054 IN GIBB,Reach-1,4
Up Type=0
Dn Type=3
Dn Slope=0.005
Boundary for River Rch & Prof#=UNT054 IN GIBB,Reach-1,5
Up Type=0
Dn Type=3
Dn Slope=0.005
Boundary for River Rch & Prof#=UNT054 IN GIBB,Reach-1,6
Up Type=0
Dn Type=3
Dn Slope=0.005
Boundary for River Rch & Prof#=UNT054 IN GIBB,Reach-1,7
Up Type=0
Dn Type=3
Dn Slope=0.005

--- UNT054 IN GIBB.g01 (geometry) ---

Geom Title=Existing Conditions

River Reach=UNT054 IN GIBB,Reach-1
Reach XY= 30
      3667431.71     10209702.51      3666955.41     10210368.97
      3666507.09     10210649.93      3666509.78     10211256.77
      3666027.18     10211840.11      3665797.31     10212654.51
      3665349.22     10212627.41      3665268.14     10213074.68
      3664794.73     10213027.29      3663898.83     10213800.82
      3663346.86     10213598.77      3662458.00     10213989.91
      3662197.59     10214708.23      3661181.96     10215218.21
      3661036.56     10215693.47      3660324.76     10216152.33
      3660271.11     10216515.87      3660046.63     10216535.14
      3659711.52     10216954.63      3659286.17     10216980.67
      3658925.93     10217691.39      3658498.41     10217593.73
      3658372.54     10217990.87      3658128.40     10217963.74
      3657880.93     10218280.12      3657663.84     10218186.28
      3657465.53     10218520.97      3656696.77     10218253.18
      3655874.65     10218480.34      3656091.71     10219342.51

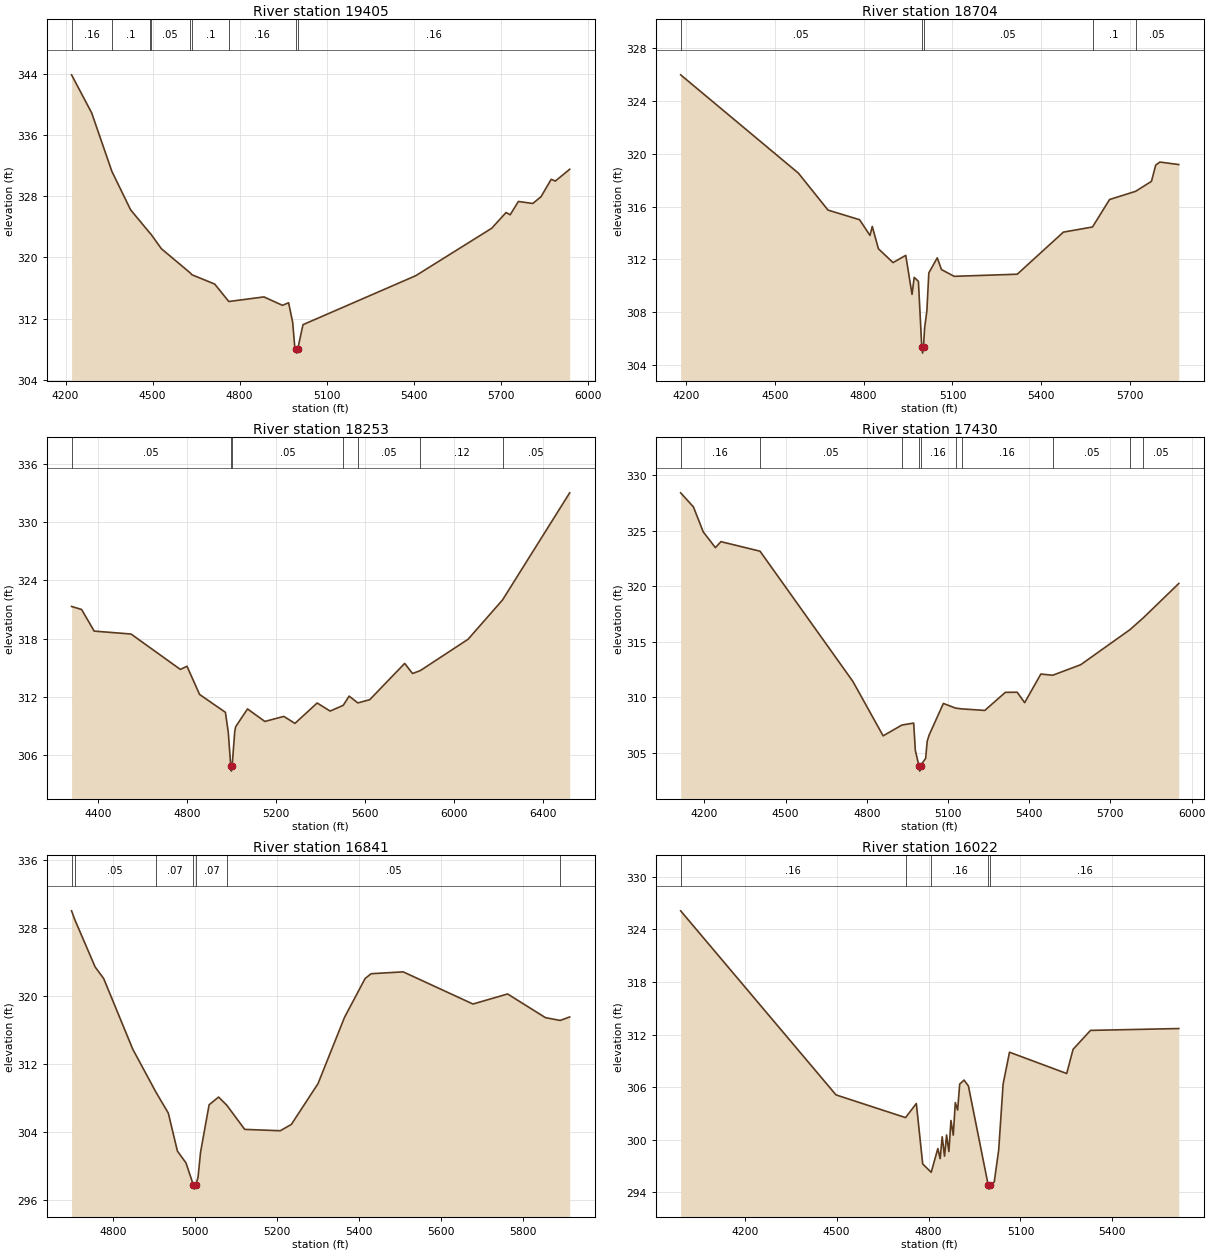
Type RM Length L Ch R = 1,19405,701,701,701
BEGIN DESCRIPTION:
UNT054 IN GIBB 36.0
END DESCRIPTION:
XS GIS Cut Line= 3
      3666742.56     10209363.36      3667142.54     10209763.34
      3667942.10     10210591.64
#Sta/Elev= 30
  4220.7  343.88  4289.9  338.91  4359.5  331.27  4424.2  326.23  4491.3  323.16
  4492.9  323.12  4530.3  321.14  4628.2  318.03  4635.9  317.73  4714.1  316.52
  4762.6  314.24  4883.8  314.84  4947.6  313.74  4968.7  314.08  4982.8  311.52
  4990.0  308.27  4994.0  307.99  4996.7  307.49  5000.0  307.99  5018.3  311.21
  5407.3  317.62  5668.9  323.82  5718.3  325.88  5732.5  325.58  5760.7  327.32
  5810.4  327.06  5838.7  327.94  5873.9  330.22  5888.1  329.99  5937.6  331.53
#Mann=9,-1,0
  4220.7    0.16       0  4359.5     0.1       0  4491.3    0.16       0
  4492.9    0.05       0  4628.2    0.16       0  4635.9     0.1       0
  4762.6    0.16       0  4994.0    0.07       0  5000.0    0.16       0
Bank Sta=4994,5000
Exp/Cntr=0.3,0.1

Type RM Length L Ch R = 1,18704,451,451,451
BEGIN DESCRIPTION:
UNT054 IN GIBB 34.0
END DESCRIPTION:
XS GIS Cut Line= 3
      3666238.42     10209898.49      3666638.40     10210198.48
      3667536.47     10210967.17
#Sta/Elev= 30
  4182.1  325.98  4579.7  318.53  4679.7  315.73  4786.3  315.00  4821.4  313.81
  4829.1  314.49  4849.9  312.80  4899.3  311.75  4942.2  312.30  4963.4  309.34
  4970.7  310.63  4985.0  310.33  4996.2  305.39  4999.0  304.89  5002.2  305.39
  5005.8  306.78  5013.5  308.09  5020.1  310.97  5048.6  312.11  5062.9  311.22
  5105.7  310.71  5318.7  310.87  5474.5  314.06  5572.9  314.45  5630.4  316.53
  5718.2  317.15  5772.0  317.91  5786.3  319.14  5800.5  319.37  5864.2  319.18
#Mann=5,-1,0
  4182.1    0.05       0  4996.2   0.035       0  5002.2    0.05       0
  5572.9     0.1       0  5718.2    0.05       0
Bank Sta=4996.2,5002.2
Exp/Cntr=0.3,0.1

Type RM Length L Ch R = 1,18253,823,823,823
BEGIN DESCRIPTION:
UNT054 IN GIBB 33.0
END DESCRIPTION:
XS GIS Cut Line= 3
      3665932.02     10210219.71      3666542.11     10210641.64
      3667742.13     10211541.66
#Sta/Elev= 30
  4278.9  321.31  4323.9  321.00  4380.7  318.77  4546.5  318.47  4768.6  314.82
  4798.3  315.15  4855.1  312.24  4971.3  310.40  4984.2  308.34  4995.4  304.84
  4998.1  304.34  5001.4  304.84  5013.2  308.41  5017.6  308.92  5070.7  310.75
  5148.8  309.46  5234.2  309.98  5284.2  309.26  5384.2  311.36  5442.5  310.53
  5501.5  311.12  5528.0  312.07  5567.3  311.37  5620.7  311.70  5778.0  315.44
  5813.4  314.40  5848.4  314.70  6063.4  317.93  6218.4  321.98  6520.7  333.02
#Mann=7,-1,0
  4278.9    0.05       0  4995.4   0.035       0  5001.4    0.05       0
  5501.5     0.1       0  5567.3    0.05       0  5848.4    0.12       0
  6218.4    0.05       0
Bank Sta=4995.4,5001.4
Exp/Cntr=0.3,0.1

Type RM Length L Ch R = 1,17430,589,589,589
BEGIN DESCRIPTION:
UNT054 IN GIBB 32.0
END DESCRIPTION:
XS GIS Cut Line= 3
      3665595.63     10211142.01      3666340.41     10211273.54
      3667292.12     10211791.65
#Sta/Elev= 30
  4112.7  328.41  4159.9  327.14  4196.1  324.89  4241.1  323.47  4261.4  324.01
  4405.9  323.15  4748.9  311.41  4860.6  306.51  4929.5  307.48  4973.4  307.66
  4979.6  305.18  4992.7  303.83  4995.5  303.33  4998.7  303.83  5017.6  304.48
  5023.3  306.02  5030.3  306.57  5083.1  309.43  5128.0  309.01  5150.8  308.94
  5236.0  308.80  5312.0  310.43  5355.7  310.44  5383.3  309.50  5443.1  312.08
  5486.8  311.97  5590.3  312.92  5772.4  316.08  5822.2  317.16  5952.6  320.24
#Mann=10,-1,0
  4112.7    0.16       0  4405.9    0.05       0  4929.5    0.16       0
  4992.7    0.07       0  4998.7    0.16       0  5128.0    0.05       0
  5150.8    0.16       0  5486.8    0.05       0  5772.4    0.16       0
  5822.2    0.05       0
Bank Sta=4992.7,4998.7
Exp/Cntr=0.3,0.1

Type RM Length L Ch R = 1,16841,819,819,819
BEGIN DESCRIPTION:
UNT054 IN GIBB 30.0
END DESCRIPTION:
XS GIS Cut Line= 3
      3665842.12     10211591.65      3666450.18     10212038.86
      3666798.90     10212337.77
#Sta/Elev= 30
  4699.6  329.98  4707.2  328.98  4757.1  323.38  4777.9  322.02  4848.9  313.71
  4904.6  308.73  4935.4  306.21  4957.6  301.75  4978.5  300.36  4996.3  297.78
  4999.1  297.28  5002.3  297.78  5007.8  298.66  5014.0  301.62  5034.8  307.19
  5057.9  308.10  5078.1  307.13  5121.6  304.30  5208.3  304.14  5235.4  304.89
  5300.2  309.67  5365.0  317.48  5415.1  322.03  5429.8  322.59  5507.8  322.81
  5677.9  319.03  5762.4  320.21  5854.6  317.43  5890.4  317.10  5913.7  317.51
#Mann=7,-1,0
  4699.6    0.16       0  4707.2    0.05       0  4904.6    0.07       0
  4996.3    0.07       0  5002.3    0.07       0  5078.1    0.05       0
  5890.4    0.16       0
Bank Sta=4996.3,5002.3
Exp/Cntr=0.3,0.1

Type RM Length L Ch R = 1,16022,963,963,963
BEGIN DESCRIPTION:
UNT054 IN GIBB 28.0
END DESCRIPTION:
XS GIS Cut Line= 3
      3665280.97     10211727.95      3665942.11     10212491.64
      3666430.70     10212866.93
#Sta/Elev= 30
  3990.7  326.12  4497.9  305.12  4724.9  302.53  4760.1  304.14  4780.9  297.24
  4808.6  296.29  4830.3  299.00  4837.9  297.85  4844.5  300.34  4852.2  298.13
  4858.8  300.55  4866.4  298.66  4873.1  302.20  4880.7  300.53  4887.3  304.24
  4894.9  303.39  4901.6  306.35  4915.8  306.81  4930.1  306.14  4994.5  294.87
  4997.3  294.37  5000.5  294.87  5014.4  295.18  5028.9  298.81  5043.4  306.36
  5064.2  309.99  5251.0  307.56  5271.8  310.32  5328.7  312.48  5616.9  312.69
#Mann=5,-1,0
  3990.7    0.16       0  4724.9    0.07       0  4808.6    0.16       0
  4994.5    0.07       0  5000.5    0.16       0
Bank Sta=4994.5,5000.5
Exp/Cntr=0.3,0.1

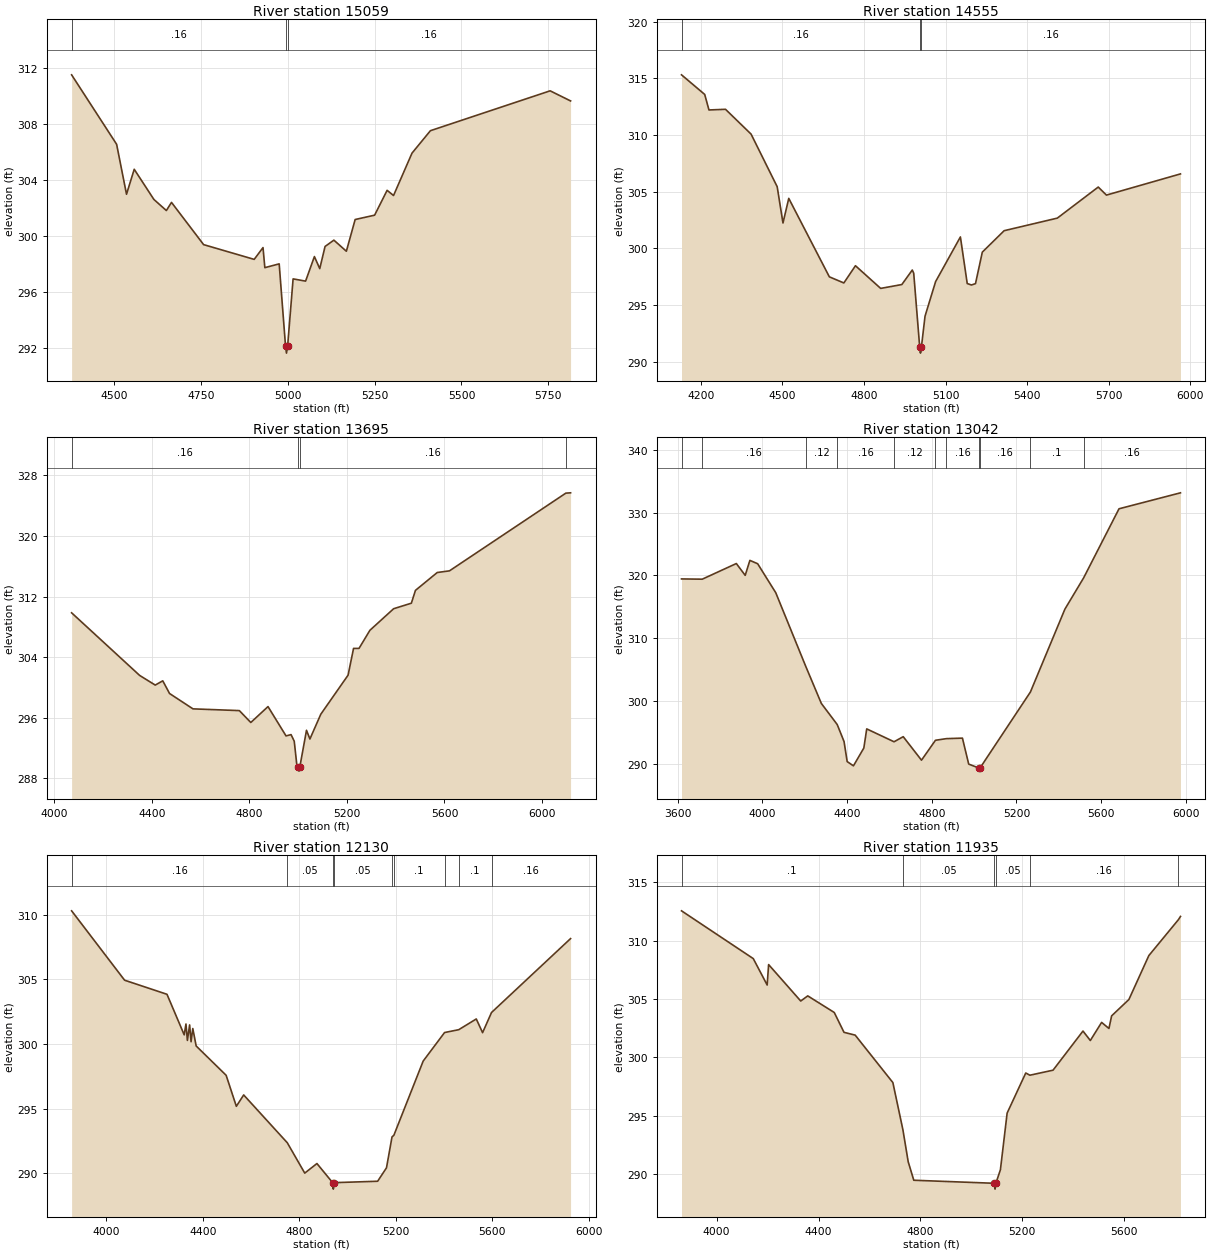
Type RM Length L Ch R = 1,15059,504,504,504
BEGIN DESCRIPTION:
UNT054 IN GIBB 26.0
END DESCRIPTION:
XS GIS Cut Line= 3
      3664892.10     10212391.63      3665172.35     10212796.12
      3666061.95     10213116.74
#Sta/Elev= 30
  4376.6  311.50  4506.3  306.55  4534.8  302.99  4557.0  304.77  4613.7  302.62
  4649.6  301.83  4664.4  302.41  4757.0  299.40  4902.7  298.35  4928.1  299.19
  4933.4  297.76  4974.7  298.03  4993.0  292.17  4995.7  291.67  4999.0  292.17
  5014.8  296.96  5050.8  296.80  5076.2  298.55  5091.6  297.69  5106.9  299.27
  5132.3  299.72  5168.3  298.93  5193.6  301.19  5249.7  301.50  5285.7  303.27
  5304.2  302.90  5357.4  305.92  5410.5  307.52  5755.5  310.36  5814.3  309.64
#Mann=3,-1,0
  4376.6    0.16       0  4993.0    0.07       0  4999.0    0.16       0
Bank Sta=4993,4999
Exp/Cntr=0.3,0.1

Type RM Length L Ch R = 1,14555,860,860,860
BEGIN DESCRIPTION:
UNT054 IN GIBB 25.0
END DESCRIPTION:
XS GIS Cut Line= 3
      3664742.11     10212291.66      3665139.90     10213366.40
      3665715.02     10213746.19
#Sta/Elev= 30
  4128.6  315.31  4213.9  313.58  4229.6  312.21  4290.4  312.27  4384.5  310.08
  4480.5  305.44  4501.8  302.24  4523.1  304.41  4672.4  297.49  4725.7  296.95
  4768.4  298.47  4861.1  296.47  4939.0  296.81  4977.4  298.09  4982.7  297.81
  5004.8  291.26  5007.5  290.76  5010.8  291.26  5024.3  294.02  5063.2  297.07
  5154.4  301.01  5179.5  296.90  5194.9  296.77  5209.9  296.89  5235.0  299.67
  5315.3  301.56  5510.9  302.67  5661.4  305.41  5691.5  304.70  5963.8  306.57
#Mann=3,-1,0
  4128.6    0.16       0  5004.8    0.07       0  5010.8    0.16       0
Bank Sta=5004.8,5010.8
Exp/Cntr=0.3,0.1

Type RM Length L Ch R = 1,13695,653,653,653
BEGIN DESCRIPTION:
UNT054 IN GIBB 23.0
END DESCRIPTION:
XS GIS Cut Line= 3
      3664217.60     10212509.22      3664442.11     10213391.64
      3664951.15     10214407.62
#Sta/Elev= 30
  4070.3  309.87  4349.2  301.61  4413.3  300.33  4444.3  300.89  4472.0  299.22
  4568.1  297.19  4758.4  296.96  4805.4  295.39  4876.0  297.49  4949.9  293.62
  4970.5  293.79  4983.6  292.92  4994.8  289.62  5000.2  289.47  5003.0  288.97
  5006.2  289.47  5033.9  294.36  5047.9  293.21  5092.7  296.49  5204.5  301.64
  5226.9  305.17  5249.3  305.17  5294.0  307.56  5391.4  310.41  5464.1  311.14
  5480.8  312.83  5570.2  315.19  5620.5  315.41  6097.9  325.67  6117.2  325.71
#Mann=4,-1,0
  4070.3    0.16       0  5000.2    0.07       0  5006.2    0.16       0
  6097.9     0.1       0
Bank Sta=5000.2,5006.2
Exp/Cntr=0.3,0.1

Type RM Length L Ch R = 1,13042,912,912,912
BEGIN DESCRIPTION:
UNT054 IN GIBB 22.0
END DESCRIPTION:
XS GIS Cut Line= 3
      3663146.05     10212637.70      3664189.76     10214119.07
      3664507.12     10214561.25
#Sta/Elev= 30
  3618.0  319.45  3716.0  319.41  3876.9  321.90  3918.8  320.02  3940.9  322.40
  3977.6  321.87  4063.2  317.25  4204.0  305.60  4278.4  299.64  4353.4  296.28
  4385.6  293.58  4400.4  290.39  4430.0  289.71  4479.1  292.55  4492.7  295.59
  4621.7  293.54  4665.1  294.35  4751.4  290.61  4817.3  293.78  4869.3  294.04
  4944.7  294.12  4974.3  289.99  5021.8  289.37  5024.6  288.87  5027.8  289.37
  5265.8  301.46  5428.6  314.64  5517.1  319.62  5684.2  330.61  5974.4  333.15
#Mann=11,-1,0
  3618.0     0.1       0  3716.0    0.16       0  4204.0    0.12       0
  4353.4    0.16       0  4621.7    0.12       0  4817.3    0.05       0
  4869.3    0.16       0  5021.8    0.07       0  5027.8    0.16       0
  5265.8     0.1       0  5517.1    0.16       0
Bank Sta=5021.8,5027.8
Exp/Cntr=0.3,0.1

Type RM Length L Ch R = 1,12130,195,195,195
BEGIN DESCRIPTION:
UNT054 IN GIBB 19.0
END DESCRIPTION:
XS GIS Cut Line= 3
      3662298.88     10212950.25      3663091.88     10213457.85
      3663452.51     10214526.08
#Sta/Elev= 30
  3856.2  310.30  4075.9  304.93  4251.7  303.84  4323.1  300.70  4330.4  301.54
  4336.3  300.27  4345.6  301.47  4351.5  300.17  4358.7  301.19  4372.7  299.84
  4497.0  297.57  4539.3  295.17  4569.7  296.05  4750.5  292.35  4822.9  290.00
  4873.5  290.74  4938.7  289.26  4941.4  288.76  4944.7  289.26  5125.2  289.37
  5161.9  290.41  5184.8  292.80  5192.5  292.93  5314.0  298.67  5402.7  300.88
  5461.5  301.10  5534.2  301.93  5560.4  300.87  5597.4  302.43  5925.2  308.15
#Mann=9,-1,0
  3856.2    0.16       0  4750.5    0.05       0  4938.7    0.03       0
  4944.7    0.05       0  5184.8    0.16       0  5192.5     0.1       0
  5402.7    0.05       0  5461.5     0.1       0  5597.4    0.16       0
Bank Sta=4938.7,4944.7
Exp/Cntr=0.3,0.1

Type RM Length L Ch R = 1,11935,1183,1183,1183
BEGIN DESCRIPTION:
UNT054 IN GIBB 18.0
END DESCRIPTION:
XS GIS Cut Line= 3
      3661965.48     10213165.49      3662968.76     10213701.96
      3663192.12     10214491.68
#Sta/Elev= 30
  3862.3  312.54  4144.0  308.45  4198.5  306.19  4204.2  307.94  4330.2  304.82
  4357.8  305.26  4461.8  303.84  4500.1  302.14  4544.0  301.90  4691.9  297.84
  4731.3  293.80  4752.0  291.07  4774.0  289.48  5090.2  289.22  5092.9  288.72
  5096.2  289.22  5114.0  290.38  5140.4  295.23  5213.5  298.66  5229.6  298.47
  5320.6  298.90  5438.1  302.25  5466.9  301.44  5511.2  302.99  5540.0  302.47
  5550.5  303.55  5618.3  304.95  5696.6  308.71  5812.9  311.79  5820.7  312.06
#Mann=6,-1,0
  3862.3     0.1       0  4731.3    0.05       0  5090.2    0.03       0
  5096.2    0.05       0  5229.6    0.16       0  5812.9    0.05       0
Bank Sta=5090.2,5096.2
Exp/Cntr=0.3,0.1

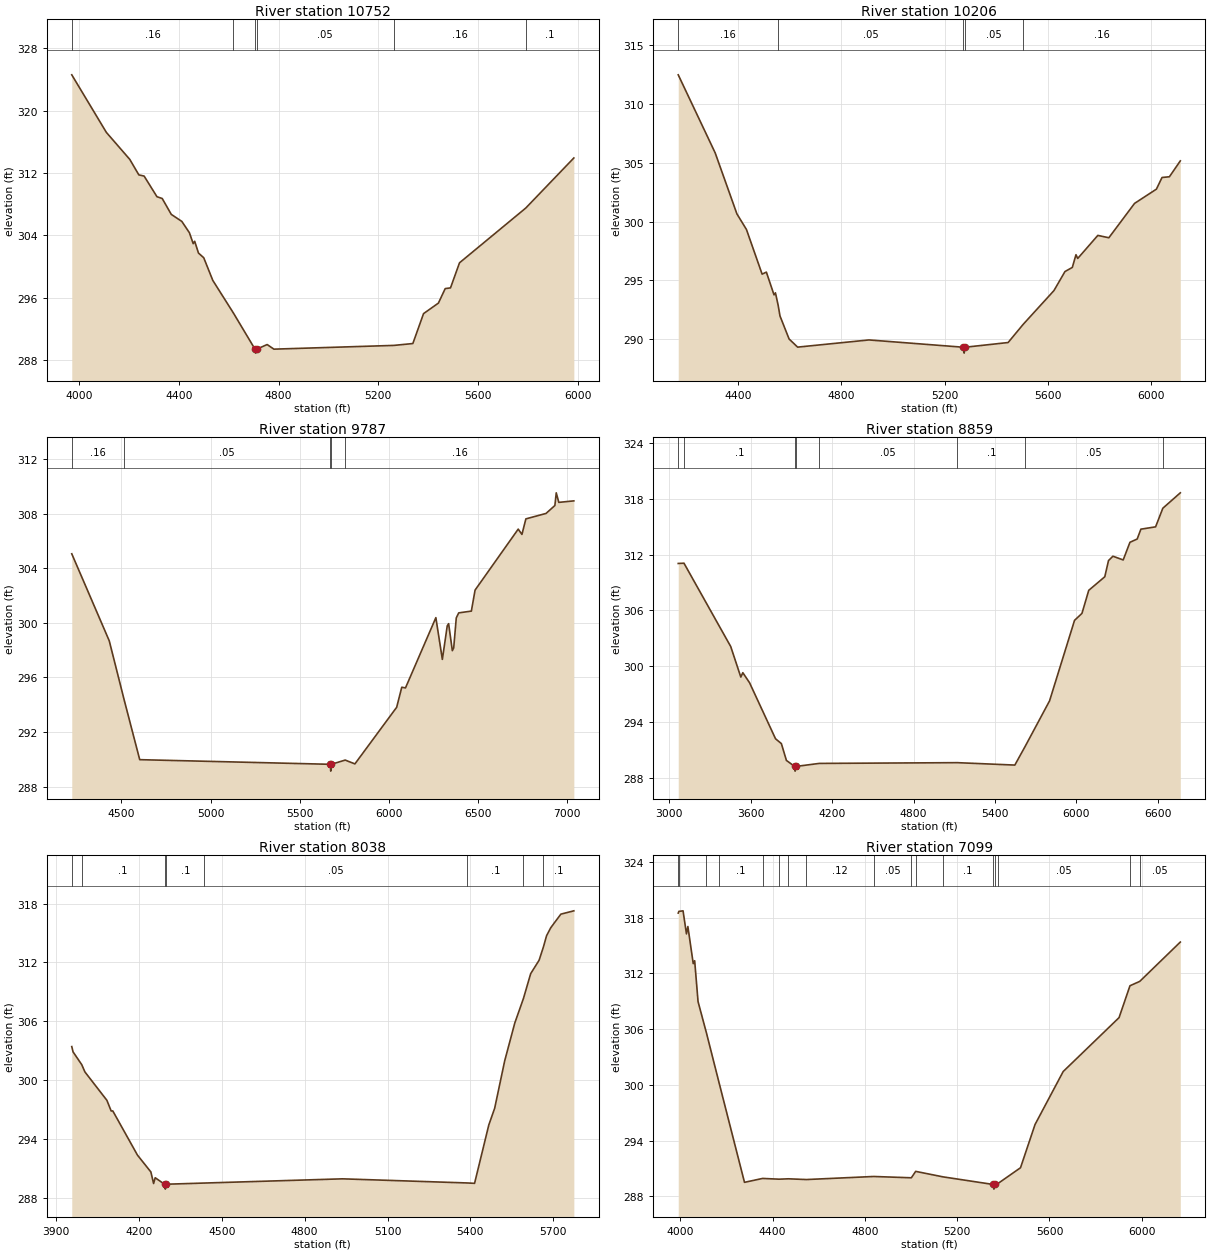
Type RM Length L Ch R = 1,10752,546,546,546
BEGIN DESCRIPTION:
UNT054 IN GIBB 16.0
END DESCRIPTION:
XS GIS Cut Line= 3
      3661671.79     10213700.27      3662147.32     10214443.18
      3663098.55     10215058.19
#Sta/Elev= 30
  3970.2  324.60  4109.1  317.21  4203.0  313.75  4239.4  311.76  4260.5  311.61
  4312.1  308.96  4333.2  308.73  4369.6  306.69  4411.9  305.79  4442.3  304.34
  4457.5  302.94  4463.5  303.24  4478.7  301.73  4499.8  301.13  4536.2  298.22
  4618.8  294.04  4705.7  289.39  4708.4  288.89  4711.7  289.39  4754.3  289.99
  4781.4  289.40  5262.6  289.88  5338.9  290.12  5381.9  293.96  5441.5  295.31
  5468.8  297.17  5490.0  297.26  5526.2  300.48  5792.2  307.51  5985.0  313.93
#Mann=6,-1,0
  3970.2    0.16       0  4618.8    0.05       0  4705.7    0.03       0
  4711.7    0.05       0  5262.6    0.16       0  5792.2     0.1       0
Bank Sta=4705.7,4711.7
Exp/Cntr=0.3,0.1

Type RM Length L Ch R = 1,10206,419,419,419
BEGIN DESCRIPTION:
UNT054 IN GIBB 15.0
END DESCRIPTION:
XS GIS Cut Line= 3
      3661542.12     10214091.67      3661982.98     10215055.45
      3662642.10     10215641.64
#Sta/Elev= 30
  4169.9  312.47  4312.8  305.84  4396.8  300.66  4433.8  299.33  4494.3  295.54
  4510.8  295.71  4540.4  293.78  4545.9  293.95  4556.6  292.87  4563.4  291.99
  4598.7  290.03  4631.7  289.34  4907.6  289.95  5273.0  289.33  5275.8  288.83
  5279.0  289.33  5445.8  289.73  5503.9  291.27  5623.0  294.14  5665.7  295.76
  5694.1  296.11  5708.3  297.19  5715.0  296.87  5792.8  298.83  5835.4  298.63
  5934.9  301.55  6019.4  302.76  6041.1  303.75  6069.6  303.81  6111.8  305.16
#Mann=5,-1,0
  4169.9    0.16       0  4556.6    0.05       0  5273.0    0.03       0
  5279.0    0.05       0  5503.9    0.16       0
Bank Sta=5273,5279
Exp/Cntr=0.3,0.1

Type RM Length L Ch R = 1,9787,928,928,928
BEGIN DESCRIPTION:
UNT054 IN GIBB 14.0
END DESCRIPTION:
XS GIS Cut Line= 3
      3661315.93     10214262.17      3661617.46     10215459.44
      3662825.82     10216477.33
#Sta/Elev= 30
  4222.0  305.06  4432.2  298.68  4515.4  294.37  4603.0  289.97  5671.0  289.63
  5673.8  289.13  5677.0  289.63  5754.8  289.94  5809.3  289.66  6043.4  293.81
  6072.0  295.28  6092.8  295.23  6263.1  300.38  6299.5  297.32  6326.9  299.78
  6334.6  299.94  6355.5  297.96  6363.2  298.17  6377.5  300.36  6391.1  300.73
  6462.1  300.86  6482.9  302.40  6724.8  306.87  6745.6  306.48  6767.7  307.62
  6880.8  308.02  6930.3  308.60  6938.0  309.53  6952.3  308.83  7036.6  308.94
#Mann=5,-1,0
  4222.0    0.16       0  4515.4    0.05       0  5671.0    0.03       0
  5677.0    0.05       0  5754.8    0.16       0
Bank Sta=5671,5677
Exp/Cntr=0.3,0.1

Type RM Length L Ch R = 1,8859,821,821,821
BEGIN DESCRIPTION:
UNT054 IN GIBB 12.0
END DESCRIPTION:
XS GIS Cut Line= 3
      3659342.06     10214741.62      3661300.18     10215893.55
      3661722.46     10217255.78
#Sta/Elev= 30
  3066.9  311.05  3109.2  311.08  3453.6  302.11  3527.8  298.83  3542.6  299.30
  3592.2  298.22  3783.6  292.19  3826.6  291.67  3863.7  289.86  3925.1  289.21
  3927.8  288.71  3931.1  289.21  4105.4  289.54  5122.7  289.62  5546.1  289.36
  5622.1  291.37  5801.9  296.27  5985.8  304.93  6040.5  305.68  6090.5  308.16
  6208.7  309.62  6236.0  311.36  6268.5  311.83  6344.3  311.43  6394.1  313.33
  6447.3  313.68  6474.6  314.74  6582.9  314.99  6636.0  316.99  6764.9  318.65
#Mann=8,-1,0
  3066.9    0.16       0  3109.2     0.1       0  3925.1   0.033       0
  3931.1     0.1       0  4105.4    0.05       0  5122.7     0.1       0
  5622.1    0.05       0  6636.0     0.1       0
Bank Sta=3925.1,3931.1
Exp/Cntr=0.3,0.1

Type RM Length L Ch R = 1,8038,939,939,939
BEGIN DESCRIPTION:
UNT054 IN GIBB 10.0
END DESCRIPTION:
XS GIS Cut Line= 3
      3659446.56     10215602.13      3660446.58     10216202.14
      3660996.55     10216552.12
#Sta/Elev= 30
  3956.6  303.42  3961.3  302.88  3992.7  301.58  4004.1  300.84  4083.8  297.94
  4099.3  296.85  4105.1  296.86  4194.5  292.35  4243.1  290.63  4252.9  289.45
  4258.7  290.04  4292.6  289.38  4295.4  288.88  4298.6  289.38  4436.7  289.50
  4937.0  289.93  5387.9  289.51  5415.2  289.47  5466.8  295.43  5488.0  297.13
  5524.4  301.98  5560.8  305.82  5592.3  308.34  5618.4  310.86  5648.9  312.23
  5664.7  313.60  5675.9  314.73  5691.2  315.55  5727.6  316.93  5774.7  317.27
#Mann=8,-1,0
  3956.6    0.05       0  3992.7     0.1       0  4292.6   0.033       0
  4298.6     0.1       0  4436.7    0.05       0  5387.9     0.1       0
  5592.3    0.05       0  5664.7     0.1       0
Bank Sta=4292.6,4298.6
Exp/Cntr=0.3,0.1

Type RM Length L Ch R = 1,7099,105,105,105
BEGIN DESCRIPTION:
UNT054 IN GIBB 8.0
END DESCRIPTION:
XS GIS Cut Line= 3
      3659009.27     10216155.04      3660367.33     10217134.63
      3660866.46     10217178.03
#Sta/Elev= 30
  3991.4  318.49  3994.3  318.67  4012.3  318.73  4027.0  316.25  4033.2  317.04
  4056.4  313.05  4062.6  313.36  4077.3  308.96  4113.7  305.59  4168.8  300.19
  4278.5  289.52  4357.0  289.94  4428.3  289.86  4468.8  289.90  4546.7  289.82
  4838.0  290.15  5001.5  290.01  5020.2  290.70  5138.6  290.11  5356.5  289.29
  5359.3  288.79  5362.5  289.29  5375.4  289.37  5474.5  291.09  5537.4  295.74
  5659.4  301.44  5901.5  307.24  5948.8  310.67  5991.2  311.14  6166.9  315.37
#Mann=17,-1,0
  3991.4    0.05       0  3994.3     0.1       0  4113.7    0.16       0
  4168.8     0.1       0  4357.0    0.05       0  4428.3     0.1       0
  4468.8    0.05       0  4546.7    0.12       0  4838.0    0.05       0
  5001.5    0.12       0  5020.2    0.05       0  5138.6     0.1       0
  5356.5   0.035       0  5362.5     0.1       0  5375.4    0.05       0
  5948.8     0.1       0  5991.2    0.05       0
Bank Sta=5356.5,5362.5
Exp/Cntr=0.3,0.1

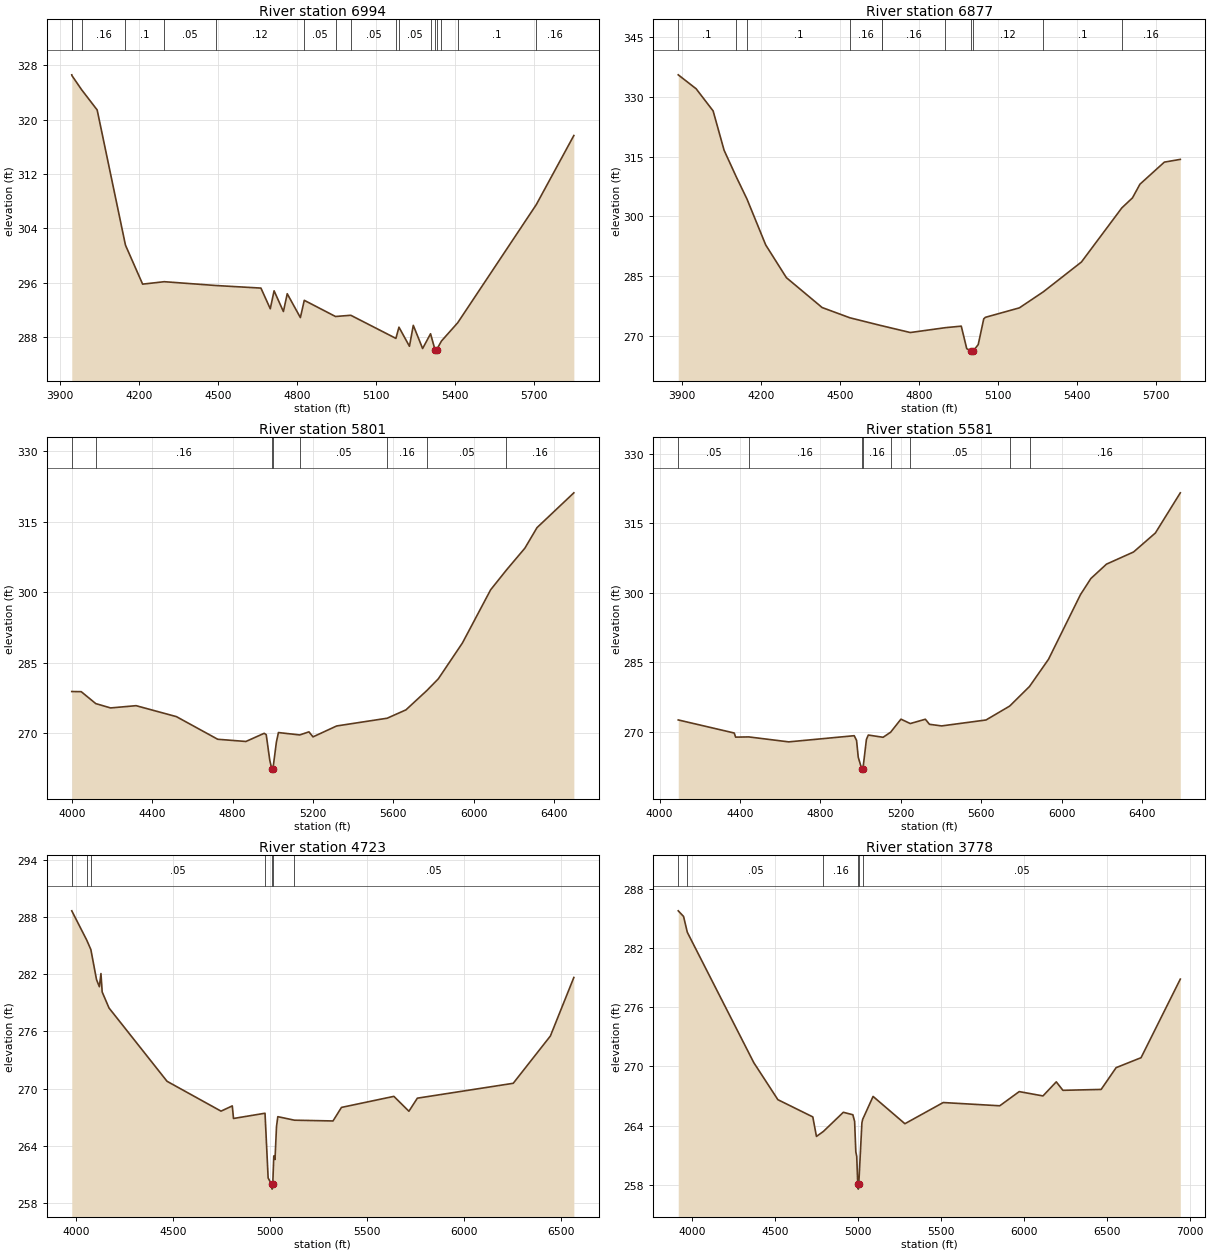
Type RM Length L Ch R = 1,6994,117,117,117
BEGIN DESCRIPTION:
UNT054 IN GIBB 7.1
END DESCRIPTION:
XS GIS Cut Line= 3
      3658946.76     10216201.04      3659903.02     10216929.40
      3660465.85     10217351.20
#Sta/Elev= 30
  3944.6  326.58  3945.2  326.47  3982.0  324.39  4041.0  321.41  4148.4  301.52
  4213.5  295.78  4295.6  296.14  4490.8  295.58  4662.5  295.20  4697.9  292.16
  4712.4  294.80  4747.8  291.75  4762.3  294.37  4812.2  290.86  4827.0  293.40
  4945.5  291.02  5003.5  291.20  5174.7  287.80  5186.3  289.45  5226.1  286.64
  5240.7  289.72  5276.1  286.31  5306.2  288.48  5323.1  286.13  5325.8  285.63
  5329.1  286.13  5347.6  287.41  5409.3  290.10  5707.3  307.47  5850.0  317.65
#Mann=17,-1,0
  3944.6    0.05       0  3945.2     0.1       0  3982.0    0.16       0
  4148.4     0.1       0  4295.6    0.05       0  4490.8    0.12       0
  4827.0    0.05       0  4945.5    0.12       0  5003.5    0.05       0
  5174.7    0.16       0  5186.3    0.05       0  5306.2     0.1       0
  5323.1    0.07       0  5329.1     0.1       0  5347.6    0.05       0
  5409.3     0.1       0  5707.3    0.16       0
Bank Sta=5323.1,5329.1
Exp/Cntr=0.3,0.1

Type RM Length L Ch R = 1,6877,1076,1076,1076
BEGIN DESCRIPTION:
UNT054 IN GIBB 7.0
END DESCRIPTION:
XS GIS Cut Line= 3
      3658835.63     10216263.52      3659791.91     10216991.90
      3660354.72     10217413.69
#Sta/Elev= 30
  3885.4  335.47  3953.3  331.98  4017.8  326.43  4059.4  316.58  4105.1  309.99
  4146.5  304.32  4217.4  292.85  4295.8  284.66  4431.5  277.17  4536.9  274.60
  4657.2  272.62  4657.5  272.62  4766.2  270.91  4898.5  272.12  4959.5  272.51
  4980.3  266.86  4998.2  266.25  5000.9  265.75  5004.2  266.25  5023.9  267.89
  5044.8  274.33  5051.1  274.72  5180.1  277.09  5271.2  281.12  5415.6  288.58
  5568.7  302.12  5609.3  304.65  5637.6  308.07  5730.2  313.60  5790.8  314.29
#Mann=11,-1,0
  3885.4     0.1       0  4105.1    0.16       0  4146.5     0.1       0
  4536.9    0.16       0  4657.2     0.1       0  4657.5    0.16       0
  4898.5    0.12       0  4998.2    0.07       0  5004.2    0.12       0
  5271.2     0.1       0  5568.7    0.16       0
Bank Sta=4998.2,5004.2
Exp/Cntr=0.3,0.1

Type RM Length L Ch R = 1,5801,220,220,220
BEGIN DESCRIPTION:
UNT054 IN GIBB 5.1
END DESCRIPTION:
XS GIS Cut Line= 3
      3658065.64     10217237.61      3659385.13     10217439.00
      3660544.85     10217529.28
#Sta/Elev= 30
  4000.2  278.90  4047.2  278.87  4119.7  276.33  4193.3  275.41  4320.2  275.89
  4520.8  273.56  4726.4  268.74  4866.6  268.27  4957.6  270.01  4967.7  269.72
  4985.4  264.27  4995.1  262.46  4997.8  261.96  5001.1  262.46  5018.3  268.14
  5028.4  270.17  5134.5  269.66  5180.2  270.32  5200.4  269.25  5318.0  271.57
  5569.5  273.22  5662.9  275.00  5767.0  279.12  5824.2  281.62  5943.8  289.23
  6084.2  300.55  6161.8  304.71  6254.7  309.42  6314.9  313.78  6498.2  321.19
#Mann=8,-1,0
  4000.2     0.1       0  4119.7    0.16       0  4995.1    0.07       0
  5001.1    0.16       0  5134.5    0.05       0  5569.5    0.16       0
  5767.0    0.05       0  6161.8    0.16       0
Bank Sta=4995.1,5001.1
Exp/Cntr=0.3,0.1

Type RM Length L Ch R = 1,5581,858,858,858
BEGIN DESCRIPTION:
UNT054 IN GIBB 5.0
END DESCRIPTION:
XS GIS Cut Line= 3
      3658076.66     10217443.29      3659396.07     10217644.68
      3660555.77     10217734.95
#Sta/Elev= 30
  4092.9  272.57  4371.5  269.75  4378.4  268.86  4443.6  268.91  4642.5  267.84
  4968.4  269.17  4980.1  268.16  4988.6  264.50  5005.8  262.03  5008.6  261.53
  5011.8  262.03  5029.1  268.36  5038.5  269.31  5112.1  268.83  5149.5  269.92
  5201.0  272.74  5247.3  271.79  5322.4  272.72  5342.7  271.63  5403.4  271.28
  5624.2  272.56  5741.9  275.56  5840.6  279.79  5935.2  285.66  6093.9  299.58
  6145.8  303.07  6223.5  306.17  6358.2  308.79  6466.8  312.89  6590.8  321.55
#Mann=8,-1,0
  4092.9    0.05       0  4443.6    0.16       0  5005.8    0.07       0
  5011.8    0.16       0  5149.5     0.1       0  5247.3    0.05       0
  5741.9     0.1       0  5840.6    0.16       0
Bank Sta=5005.8,5011.8
Exp/Cntr=0.3,0.1

Type RM Length L Ch R = 1,4723,945,945,945
BEGIN DESCRIPTION:
UNT054 IN GIBB 4.0
END DESCRIPTION:
XS GIS Cut Line= 3
      3657592.14     10217191.67      3658879.05     10218173.26
      3659842.06     10218041.65
#Sta/Elev= 30
  3975.7  288.65  4052.4  285.60  4074.2  284.59  4103.5  281.43  4118.1  280.69
  4126.3  282.07  4132.6  280.14  4167.9  278.46  4467.3  270.77  4745.8  267.64
  4803.9  268.19  4810.2  266.87  4972.8  267.42  4988.9  260.63  5006.7  259.96
  5009.5  259.46  5012.7  259.96  5018.0  262.94  5024.3  262.57  5032.1  266.03
  5038.8  267.06  5124.8  266.69  5323.6  266.61  5367.2  268.03  5637.7  269.19
  5715.2  267.63  5758.8  269.00  6253.4  270.56  6445.1  275.52  6566.2  281.66
#Mann=7,-1,0
  3975.7    0.05       0  4052.4     0.1       0  4074.2    0.05       0
  4972.8    0.16       0  5006.7    0.07       0  5012.7    0.16       0
  5124.8    0.05       0
Bank Sta=5006.7,5012.7
Exp/Cntr=0.3,0.1

Type RM Length L Ch R = 1,3778,661,661,661
BEGIN DESCRIPTION:
UNT054 IN GIBB 2.0
END DESCRIPTION:
XS GIS Cut Line= 3
      3657442.10     10217291.63      3657999.82     10218545.66
      3659648.28     10218596.40
#Sta/Elev= 30
  3918.4  285.80  3950.5  285.23  3973.1  283.62  4373.1  270.39  4518.1  266.63
  4728.3  264.88  4750.2  262.90  4791.6  263.40  4912.0  265.35  4969.4  265.10
  4980.0  264.42  4987.2  261.33  4992.7  260.87  4998.9  258.05  5001.7  257.55
  5004.9  258.05  5023.8  264.27  5028.4  264.63  5091.1  266.96  5282.6  264.19
  5513.2  266.34  5853.4  266.01  5970.6  267.45  6113.5  267.01  6193.6  268.44
  6233.6  267.58  6463.7  267.67  6553.7  269.88  6703.8  270.89  6940.1  278.87
#Mann=6,-1,0
  3918.4    0.16       0  3973.1    0.05       0  4791.6    0.16       0
  4998.9    0.07       0  5004.9    0.16       0  5028.4    0.05       0
Bank Sta=4998.9,5004.9
Exp/Cntr=0.3,0.1

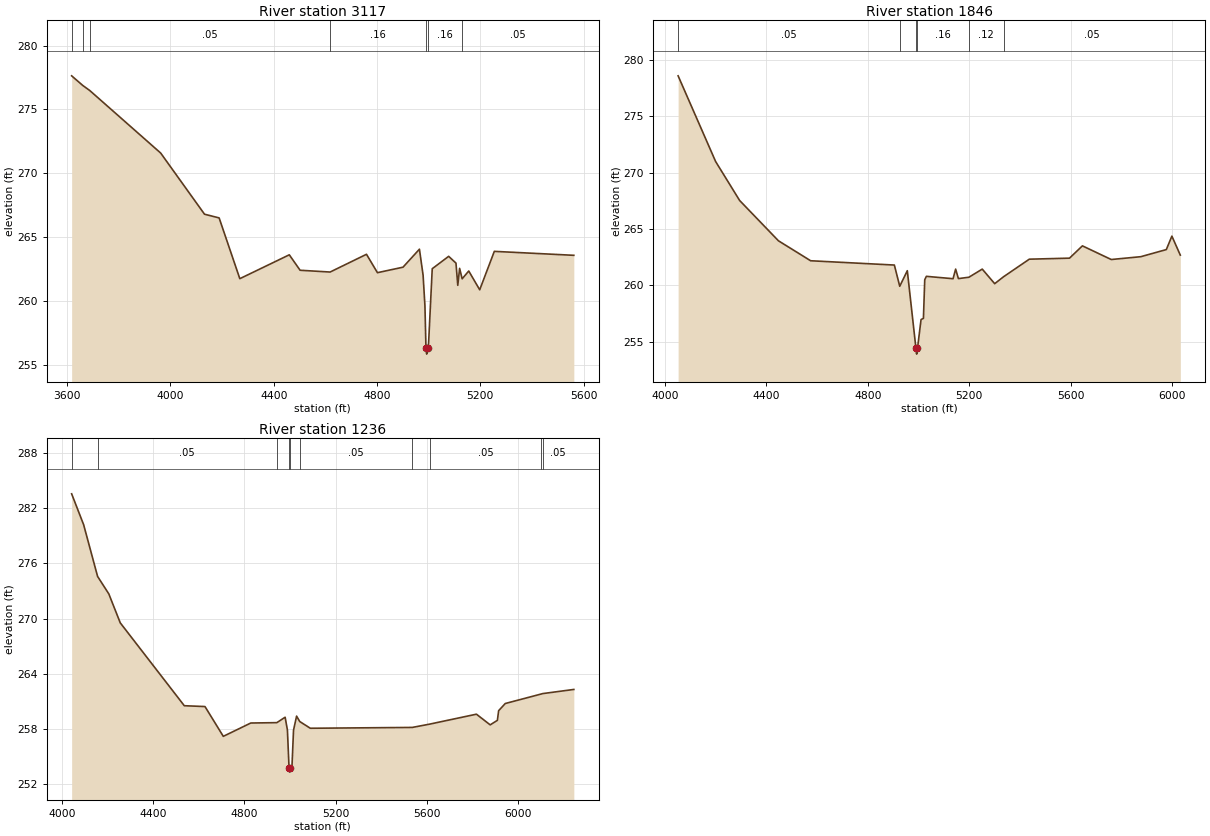
Type RM Length L Ch R = 1,3117,1271,1271,1271
BEGIN DESCRIPTION:
Mapping XS 17905933
END DESCRIPTION:
XS GIS Cut Line= 3
      3656947.36     10217255.20      3657232.09     10218192.74
      3657912.55     10218876.68
#Sta/Elev= 30
  3617.4  277.63  3660.2  276.88  3687.5  276.48  3962.2  271.58  4131.9  266.79
  4188.5  266.50  4268.6  261.74  4460.2  263.61  4502.0  262.40  4618.2  262.26
  4759.1  263.65  4801.5  262.21  4900.5  262.64  4964.1  264.05  4978.3  262.01
  4985.4  259.62  4989.4  256.33  4992.2  255.83  4995.4  256.33  4999.5  256.66
  5013.7  262.52  5077.3  263.49  5105.6  262.96  5112.6  261.22  5119.7  262.55
  5129.5  261.73  5155.1  262.34  5197.5  260.87  5254.1  263.88  5562.0  263.57
#Mann=7,-1,0
  3617.4    0.05       0  3660.2     0.1       0  3687.5    0.05       0
  4618.2    0.16       0  4989.4    0.07       0  4995.4    0.16       0
  5129.5    0.05       0
Bank Sta=4989.4,4995.4
Exp/Cntr=0.3,0.1

Type RM Length L Ch R = 1,1846,610,610,610
BEGIN DESCRIPTION:
Mapping XS abb9256e
END DESCRIPTION:
XS GIS Cut Line= 3
      3656343.21     10217401.10      3656704.31     10218498.30
      3657387.71     10218963.15
#Sta/Elev= 30
  4051.6  278.57  4199.6  270.98  4294.3  267.53  4447.4  263.96  4574.6  262.19
  4904.9  261.81  4926.1  259.93  4956.0  261.31  4990.1  254.42  4992.8  253.92
  4996.1  254.42  5010.2  256.98  5019.6  257.09  5024.8  260.51  5031.2  260.81
  5136.5  260.60  5146.7  261.45  5157.6  260.61  5199.0  260.73  5251.7  261.45
  5300.8  260.16  5336.2  260.78  5437.4  262.33  5596.0  262.42  5646.9  263.51
  5760.7  262.30  5877.3  262.55  5978.0  263.18  6000.0  264.37  6033.2  262.69
#Mann=6,-1,0
  4051.6    0.05       0  4926.1    0.16       0  4990.1    0.07       0
  4996.1    0.16       0  5199.0    0.12       0  5336.2    0.05       0
Bank Sta=4990.1,4996.1
Exp/Cntr=0.3,0.1

Type RM Length L Ch R = 1,1236,0,0,0
BEGIN DESCRIPTION:
UNT054 IN GIBB 1.0
END DESCRIPTION:
XS GIS Cut Line= 3
      3656075.20     10217469.27      3656168.96     10218580.43
      3657155.09     10219035.31
#Sta/Elev= 30
  4043.2  283.57  4095.8  280.21  4156.9  274.59  4206.1  272.69  4256.3  269.54
  4537.0  260.53  4627.6  260.44  4707.9  257.20  4828.4  258.65  4942.6  258.69
  4978.9  259.28  4988.9  257.90  4996.0  253.81  4998.7  253.31  5002.0  253.81
  5009.0  254.00  5015.7  257.87  5029.1  259.40  5043.0  258.81  5089.3  258.08
  5536.2  258.17  5612.5  258.53  5817.4  259.61  5877.6  258.45  5909.2  258.94
  5914.7  259.99  5943.7  260.77  6102.3  261.81  6108.1  261.85  6244.3  262.30
#Mann=10,-1,0
  4043.2     0.1       0  4156.9    0.05       0  4942.6    0.16       0
  4996.0    0.07       0  5002.0    0.16       0  5043.0    0.05       0
  5536.2    0.12       0  5612.5    0.05       0  6102.3    0.16       0
  6108.1    0.05       0
Bank Sta=4996,5002
Exp/Cntr=0.3,0.1

Chan Stop Cuts=-1