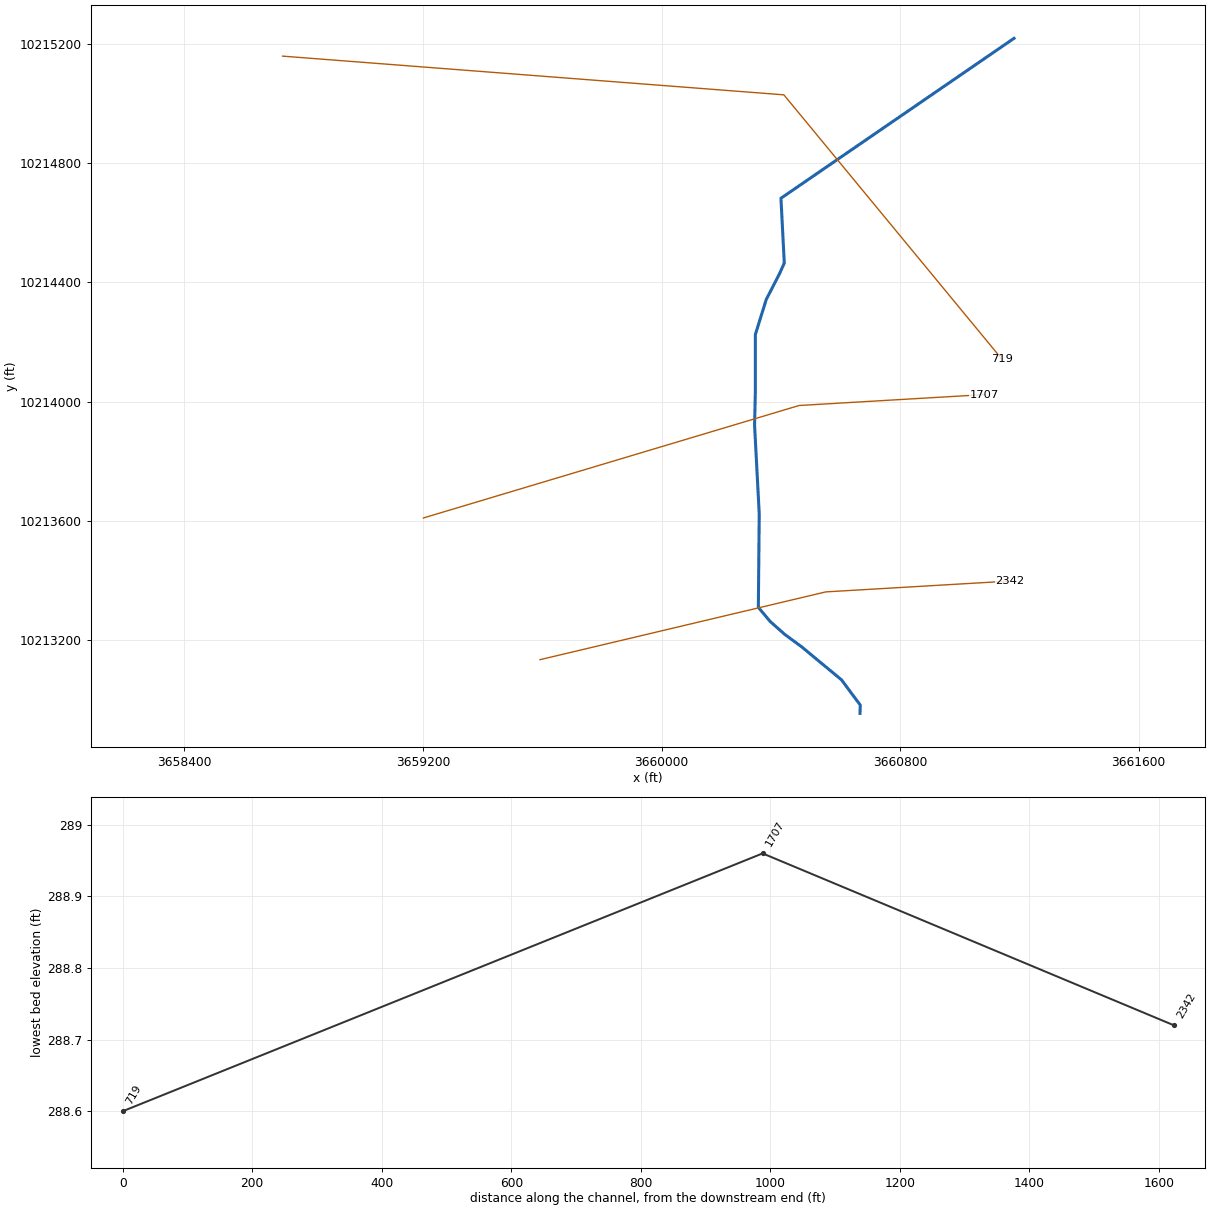
--- UNT055 IN GIBB.prj (project) ---

Proj Title=UNT055 IN GIBB Base Level Engineering
Current Plan=p01
Default Exp/Contr=0.3,0.1
English Units
Geom File=g01
Flow File=f01
Plan File=p01
BEGIN DESCRIPTION:
UNT055 IN GIBB
END DESCRIPTION:

--- UNT055 IN GIBB.p01 (plan) ---

Plan Title=Multiple Run
Short Identifier=Multiple
Geom File=g01
Flow File=f01
Subcritical Flow
K Sum by GR= 0
Std Step Tol= 0.01
Critical Tol= 0.01
Num of Std Step Trials= 20
Max Error Tol= 0.3
Flow Tol Ratio= 0.001
Split Flow NTrial= 30
Split Flow Tol= 0.02
Split Flow Ratio= 0.02
Log Output Level= 0
Friction Slope Method= 1
Unsteady Friction Slope Method= 2
Unsteady Bridges Friction Slope Method= 1
Parabolic Critical Depth
Global Vel Dist=  1 , 1 , 1
Global Log Level= 0
CheckData=True
Encroach Param= -1, 0, 0, 0
BEGIN DESCRIPTION:
Multiple Run
END DESCRIPTION:

--- UNT055 IN GIBB.f01 (steady flow) ---

Flow Title=Multiple
Number of Profiles=7
Profile Names=10-year,25-year,50-year,1pct_min,100-year,1pct_plu,500-year
River Rch & RM= UNT055 IN GIBB,Reach-1,2342
     656     878    1058     934    1264    1709    1802
Boundary for River Rch & Prof#=UNT055 IN GIBB,Reach-1,1
Up Type=0
Dn Type=3
Dn Slope=0.005
Boundary for River Rch & Prof#=UNT055 IN GIBB,Reach-1,2
Up Type=0
Dn Type=3
Dn Slope=0.005
Boundary for River Rch & Prof#=UNT055 IN GIBB,Reach-1,3
Up Type=0
Dn Type=3
Dn Slope=0.005
Boundary for River Rch & Prof#=UNT055 IN GIBB,Reach-1,4
Up Type=0
Dn Type=3
Dn Slope=0.005
Boundary for River Rch & Prof#=UNT055 IN GIBB,Reach-1,5
Up Type=0
Dn Type=3
Dn Slope=0.005
Boundary for River Rch & Prof#=UNT055 IN GIBB,Reach-1,6
Up Type=0
Dn Type=3
Dn Slope=0.005
Boundary for River Rch & Prof#=UNT055 IN GIBB,Reach-1,7
Up Type=0
Dn Type=3
Dn Slope=0.005

--- UNT055 IN GIBB.g01 (geometry) ---

Geom Title=Existing Conditions

River Reach=UNT055 IN GIBB,Reach-1
Reach XY= 16
      3660665.56     10212954.71      3660666.52     10212982.45
      3660603.58     10213067.08      3660470.12     10213177.76
      3660412.61     10213220.08      3660364.87     10213262.40
      3660324.72     10213310.14      3660327.72     10213623.59
      3660312.10     10213920.47      3660314.70     10214035.05
      3660314.70     10214225.16      3660351.16     10214342.34
      3660395.43     10214428.28      3660411.71     10214464.59
      3660400.51     10214681.93      3661181.96     10215218.21

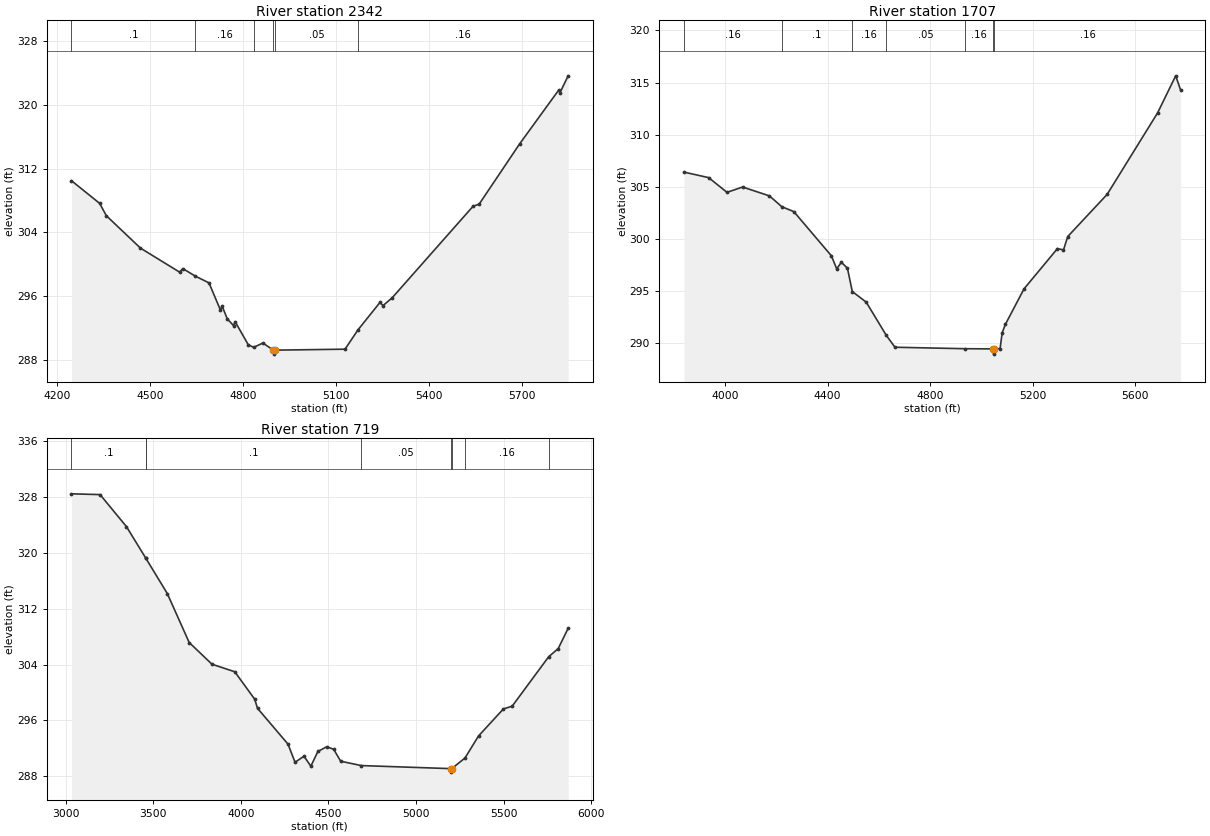
Type RM Length L Ch R = 1,2342,635,635,635
BEGIN DESCRIPTION:
UNT055 IN GIBB 2.0
END DESCRIPTION:
XS GIS Cut Line= 3
      3659592.58     10213134.74      3660550.97     10213362.07
      3661168.92     10213398.42
#Sta/Elev= 30
  4246.3  310.47  4337.2  307.63  4358.9  306.08  4469.0  302.02  4595.2  299.01
  4605.9  299.45  4645.8  298.51  4690.3  297.66  4727.4  294.24  4732.6  294.76
  4749.4  293.14  4769.6  292.30  4774.8  292.79  4817.0  289.91  4834.5  289.57
  4864.4  290.11  4898.4  289.22  4901.2  288.72  4904.4  289.22  5129.7  289.34
  5171.7  291.77  5242.4  295.20  5252.5  294.81  5282.5  295.81  5543.0  307.26
  5563.0  307.54  5693.2  315.07  5819.2  321.81  5824.2  321.53  5850.3  323.63
#Mann=6,-1,0
  4246.3     0.1       0  4645.8    0.16       0  4834.5    0.05       0
  4898.4    0.03       0  4904.4    0.05       0  5171.7    0.16       0
Bank Sta=4898.4,4904.4
Exp/Cntr=0.3,0.1

Type RM Length L Ch R = 1,1707,988,988,988
BEGIN DESCRIPTION:
UNT055 IN GIBB 2.1
END DESCRIPTION:
XS GIS Cut Line= 3
      3659201.61     10213609.95      3660461.38     10213987.07
      3661081.20     10214023.53
#Sta/Elev= 30
  3840.3  306.41  3936.7  305.88  4008.1  304.47  4069.0  304.98  4173.5  304.13
  4221.9  303.09  4268.8  302.62  4414.9  298.39  4435.8  297.14  4453.9  297.76
  4477.6  297.20  4496.5  294.96  4550.6  293.95  4629.4  290.75  4662.9  289.62
  4934.9  289.48  5044.8  289.46  5047.6  288.96  5050.8  289.46  5072.6  289.49
  5080.9  291.02  5093.4  291.82  5166.0  295.22  5296.3  299.08  5319.8  298.95
  5336.3  300.23  5490.1  304.28  5686.9  312.10  5757.1  315.64  5776.2  314.29
#Mann=7,-1,0
  3840.3    0.16       0  4221.9     0.1       0  4496.5    0.16       0
  4629.4    0.05       0  4934.9    0.16       0  5044.8    0.07       0
  5050.8    0.16       0
Bank Sta=5044.8,5050.8
Exp/Cntr=0.3,0.1

Type RM Length L Ch R = 1,719,0,0,0
BEGIN DESCRIPTION:
UNT055 IN GIBB 1.0
END DESCRIPTION:
XS GIS Cut Line= 3
      3658729.43     10215158.56      3660410.34     10215028.74
      3661142.12     10214141.63
#Sta/Elev= 30
  3032.6  328.47  3195.8  328.36  3346.2  323.78  3455.7  319.30  3455.9  319.29
  3579.5  314.19  3704.6  307.17  3834.7  304.06  3964.8  302.98  4078.4  299.06
  4094.9  297.74  4268.9  292.61  4309.1  290.01  4360.2  290.88  4399.3  289.45
  4439.5  291.56  4490.3  292.24  4529.7  291.87  4569.8  290.16  4687.3  289.54
  5197.7  289.10  5200.5  288.60  5203.7  289.10  5279.4  290.62  5357.1  293.79
  5499.1  297.66  5548.6  298.04  5757.4  305.13  5811.8  306.30  5868.5  309.21
#Mann=8,-1,0
  3032.6     0.1       0  3455.7    0.16       0  3455.9     0.1       0
  4687.3    0.05       0  5197.7   0.033       0  5203.7    0.05       0
  5279.4    0.16       0  5757.4     0.1       0
Bank Sta=5197.7,5203.7
Exp/Cntr=0.3,0.1

Chan Stop Cuts=-1