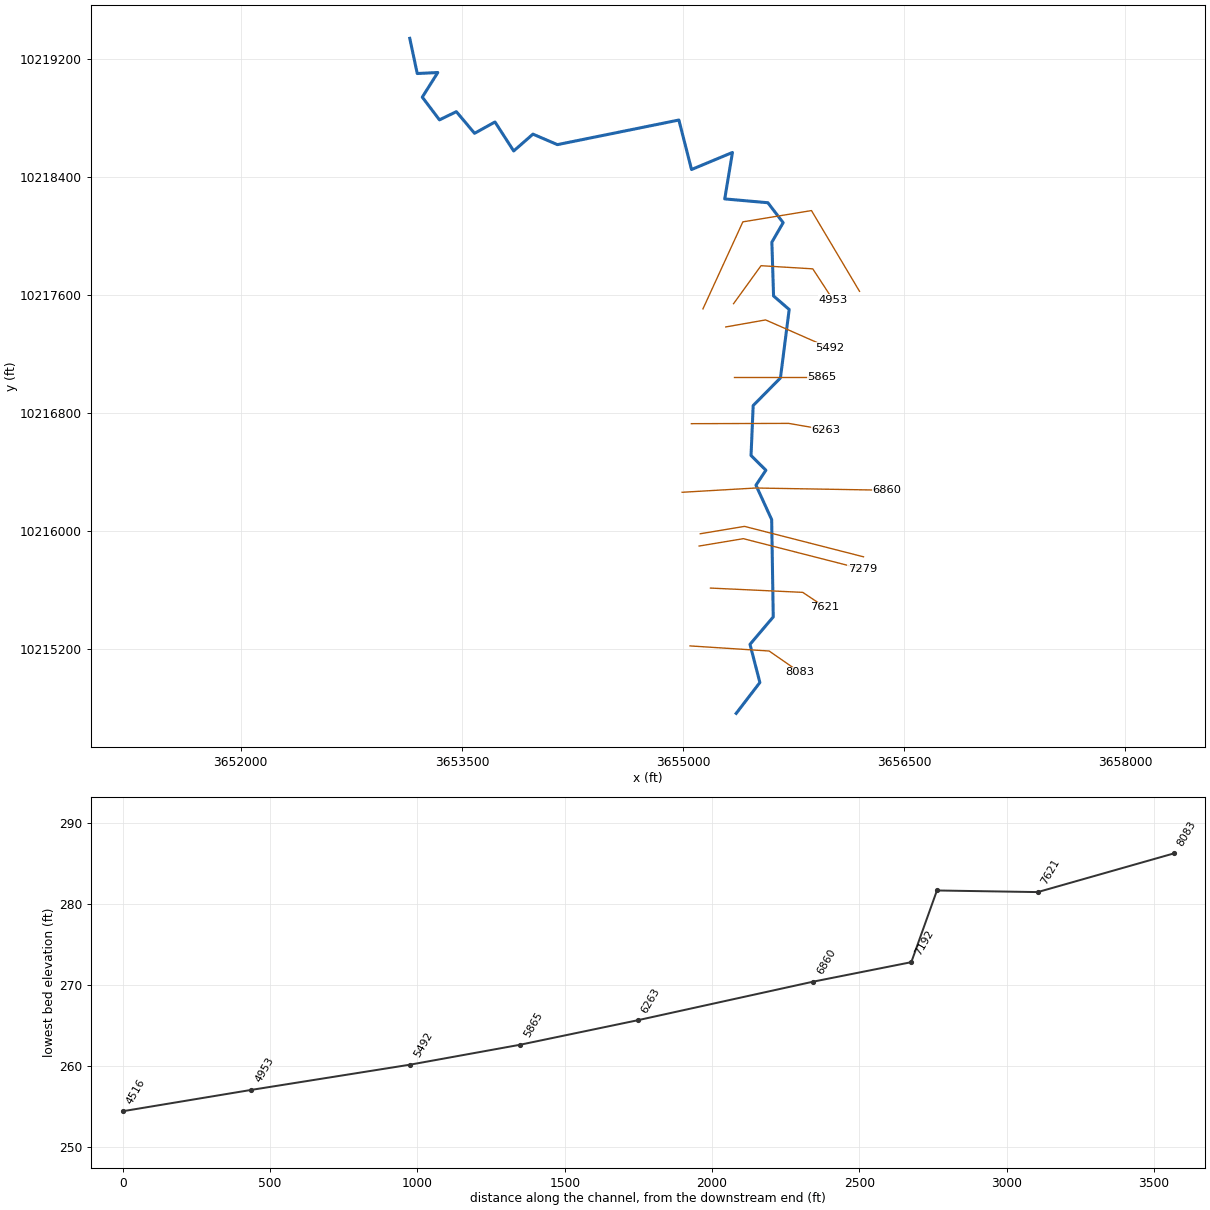
--- UNT056 IN GIBB.prj (project) ---

Proj Title=UNT056 IN GIBB Base Level Engineering
Current Plan=p01
Default Exp/Contr=0.3,0.1
English Units
Geom File=g01
Flow File=f01
Plan File=p01
BEGIN DESCRIPTION:
UNT056 IN GIBB
END DESCRIPTION:

--- UNT056 IN GIBB.p01 (plan) ---

Plan Title=Multiple Run
Short Identifier=Multiple
Geom File=g01
Flow File=f01
Subcritical Flow
K Sum by GR= 0
Std Step Tol= 0.01
Critical Tol= 0.01
Num of Std Step Trials= 20
Max Error Tol= 0.3
Flow Tol Ratio= 0.001
Split Flow NTrial= 30
Split Flow Tol= 0.02
Split Flow Ratio= 0.02
Log Output Level= 0
Friction Slope Method= 1
Unsteady Friction Slope Method= 2
Unsteady Bridges Friction Slope Method= 1
Parabolic Critical Depth
Global Vel Dist=  1 , 1 , 1
Global Log Level= 0
CheckData=True
Encroach Param= -1, 0, 0, 0
BEGIN DESCRIPTION:
Multiple Run
END DESCRIPTION:

--- UNT056 IN GIBB.f01 (steady flow) ---

Flow Title=Multiple
Number of Profiles=7
Profile Names=10-year,25-year,50-year,1pct_min,100-year,1pct_plu,500-year
River Rch & RM= UNT056 IN GIBB,Reach-1,8083
     776    1064    1305    1173    1587    2146    2349
Boundary for River Rch & Prof#=UNT056 IN GIBB,Reach-1,1
Up Type=0
Dn Type=3
Dn Slope=0.005
Boundary for River Rch & Prof#=UNT056 IN GIBB,Reach-1,2
Up Type=0
Dn Type=3
Dn Slope=0.005
Boundary for River Rch & Prof#=UNT056 IN GIBB,Reach-1,3
Up Type=0
Dn Type=3
Dn Slope=0.005
Boundary for River Rch & Prof#=UNT056 IN GIBB,Reach-1,4
Up Type=0
Dn Type=3
Dn Slope=0.005
Boundary for River Rch & Prof#=UNT056 IN GIBB,Reach-1,5
Up Type=0
Dn Type=3
Dn Slope=0.005
Boundary for River Rch & Prof#=UNT056 IN GIBB,Reach-1,6
Up Type=0
Dn Type=3
Dn Slope=0.005
Boundary for River Rch & Prof#=UNT056 IN GIBB,Reach-1,7
Up Type=0
Dn Type=3
Dn Slope=0.005

--- UNT056 IN GIBB.g01 (geometry) ---

Geom Title=Existing Conditions

River Reach=UNT056 IN GIBB,Reach-1
Reach XY= 30
      3655360.02     10214763.21      3655520.69     10214972.50
      3655453.68     10215231.34      3655611.33     10215417.32
      3655600.62     10216077.29      3655494.04     10216310.90
      3655561.36     10216412.11      3655460.68     10216512.15
      3655475.22     10216850.99      3655660.05     10217038.17
      3655719.39     10217502.45      3655613.46     10217593.90
      3655601.97     10217959.05      3655678.48     10218090.99
      3655574.80     10218226.45      3655282.39     10218252.29
      3655334.66     10218567.45      3655057.12     10218451.66
      3654971.29     10218787.31      3654147.39     10218620.45
      3653981.59     10218691.63      3653850.95     10218577.48
      3653724.21     10218774.09      3653585.76     10218697.27
      3653462.06     10218843.97      3653347.48     10218788.42
      3653231.16     10218942.50      3653336.19     10219109.60
      3653196.87     10219102.65      3653146.09     10219341.37

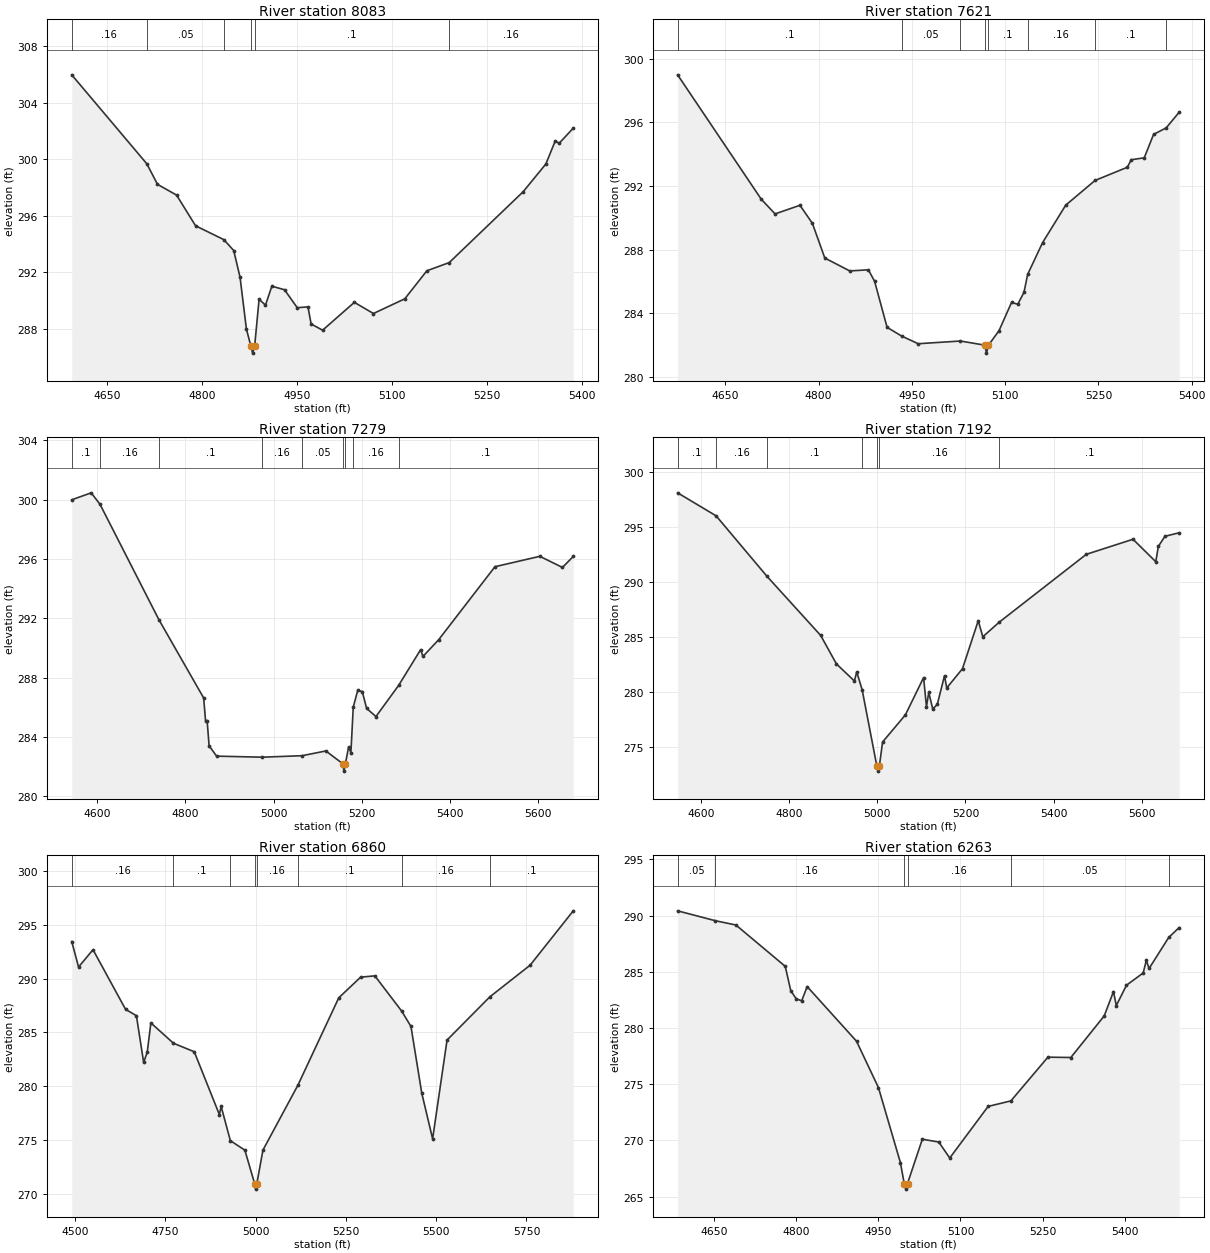
Type RM Length L Ch R = 1,8083,462,462,462
BEGIN DESCRIPTION:
UNT056 IN GIBB 10.0
END DESCRIPTION:
XS GIS Cut Line= 3
      3655047.08     10215220.76      3655583.57     10215186.15
      3655792.09     10215041.65
#Sta/Elev= 30
  4594.5  305.96  4713.0  299.67  4729.8  298.22  4759.9  297.46  4789.9  295.29
  4834.5  294.31  4850.1  293.54  4860.1  291.64  4870.1  287.99  4877.1  286.79
  4879.9  286.29  4883.1  286.79  4890.1  290.10  4900.2  289.68  4910.2  291.02
  4930.2  290.77  4950.3  289.50  4967.2  289.56  4972.2  288.35  4990.3  287.91
  5040.4  289.88  5070.5  289.09  5120.0  290.13  5154.8  292.11  5190.1  292.69
  5306.8  297.70  5342.6  299.66  5357.4  301.29  5363.5  301.12  5385.8  302.19
#Mann=6,-1,0
  4594.5    0.16       0  4713.0    0.05       0  4834.5     0.1       0
  4877.1    0.07       0  4883.1     0.1       0  5190.1    0.16       0
Bank Sta=4877.1,4883.1
Exp/Cntr=0.3,0.1

Type RM Length L Ch R = 1,7621,342,342,342
BEGIN DESCRIPTION:
UNT056 IN GIBB 9.0
END DESCRIPTION:
XS GIS Cut Line= 3
      3655185.51     10215613.03      3655811.31     10215583.94
      3655961.35     10215483.91
#Sta/Elev= 30
  4573.1  298.98  4707.7  291.17  4729.9  290.25  4769.9  290.79  4789.9  289.66
  4809.9  287.48  4850.0  286.67  4880.0  286.74  4890.0  286.02  4910.1  283.13
  4933.6  282.58  4960.1  282.10  5028.1  282.27  5067.2  282.01  5070.0  281.51
  5073.2  282.01  5090.2  282.92  5110.3  284.69  5120.3  284.58  5130.3  285.32
  5136.2  286.45  5160.3  288.45  5197.5  290.80  5244.7  292.35  5296.7  293.18
  5302.8  293.65  5323.8  293.77  5338.8  295.24  5359.1  295.65  5379.9  296.63
#Mann=8,-1,0
  4573.1     0.1       0  4933.6    0.05       0  5028.1     0.1       0
  5067.2   0.033       0  5073.2     0.1       0  5136.2    0.16       0
  5244.7     0.1       0  5359.1    0.05       0
Bank Sta=5067.2,5073.2
Exp/Cntr=0.3,0.1

Type RM Length L Ch R = 1,7279,87,87,87
BEGIN DESCRIPTION:
UNT056 IN GIBB 8.1
END DESCRIPTION:
XS GIS Cut Line= 3
      3655108.60     10215898.04      3655408.64     10215948.05
      3656215.51     10215741.78
#Sta/Elev= 30
  4542.4  300.00  4586.5  300.47  4606.6  299.69  4739.8  291.93  4841.5  286.64
  4845.8  285.09  4849.4  285.09  4853.8  283.42  4870.8  282.72  4974.7  282.65
  5064.6  282.75  5118.5  283.07  5156.8  282.21  5159.6  281.71  5162.8  282.21
  5170.1  283.34  5175.3  282.96  5180.6  286.02  5190.8  287.16  5201.1  287.07
  5210.9  285.94  5232.1  285.39  5283.5  287.49  5333.4  289.90  5338.6  289.44
  5374.3  290.57  5501.9  295.49  5603.6  296.19  5654.9  295.44  5679.4  296.18
#Mann=9,-1,0
  4542.4     0.1       0  4606.6    0.16       0  4739.8     0.1       0
  4974.7    0.16       0  5064.6    0.05       0  5156.8    0.07       0
  5162.8    0.05       0  5180.6    0.16       0  5283.5     0.1       0
Bank Sta=5156.8,5162.8
Exp/Cntr=0.3,0.1

Type RM Length L Ch R = 1,7192,332,332,332
BEGIN DESCRIPTION:
UNT056 IN GIBB 8.0
END DESCRIPTION:
XS GIS Cut Line= 3
      3655116.41     10215981.37      3655416.46     10216031.38
      3656223.32     10215825.11
#Sta/Elev= 30
  4547.4  298.14  4634.7  296.05  4749.9  290.56  4871.8  285.18  4907.5  282.59
  4948.3  281.04  4953.5  281.87  4965.8  280.24  4998.9  273.35  5001.7  272.85
  5004.9  273.35  5012.2  275.50  5063.8  277.96  5105.1  281.35  5111.6  278.70
  5116.8  280.01  5125.8  278.50  5136.1  278.91  5152.5  281.52  5157.6  280.41
  5193.3  282.16  5229.0  286.52  5239.3  285.06  5277.0  286.40  5473.9  292.55
  5579.9  293.92  5631.5  291.88  5637.3  293.27  5652.2  294.19  5684.4  294.51
#Mann=7,-1,0
  4547.4     0.1       0  4634.7    0.16       0  4749.9     0.1       0
  4965.8    0.16       0  4998.9    0.07       0  5004.9    0.16       0
  5277.0     0.1       0
Bank Sta=4998.9,5004.9
Exp/Cntr=0.3,0.1

Type RM Length L Ch R = 1,6860,597,597,597
BEGIN DESCRIPTION:
UNT056 IN GIBB 7.0
END DESCRIPTION:
XS GIS Cut Line= 3
      3654993.28     10216262.73      3655492.11     10216291.64
      3656381.61     10216276.63
#Sta/Elev= 30
  4490.4  293.45  4509.3  291.08  4549.3  292.69  4639.5  287.15  4669.5  286.56
  4689.6  282.22  4699.6  283.18  4709.6  285.89  4772.2  284.00  4829.8  283.21
  4899.3  277.38  4904.3  278.13  4929.8  274.95  4970.0  274.07  4997.1  270.95
  4999.8  270.45  5003.1  270.95  5020.1  274.08  5116.7  280.09  5230.1  288.22
  5290.7  290.14  5330.1  290.26  5404.5  286.98  5430.1  285.56  5460.1  279.35
  5490.1  275.12  5530.1  284.30  5648.6  288.31  5760.2  291.25  5879.7  296.30
#Mann=8,-1,0
  4490.4    0.16       0  4772.2     0.1       0  4929.8    0.16       0
  4997.1    0.07       0  5003.1    0.16       0  5116.7     0.1       0
  5404.5    0.16       0  5648.6     0.1       0
Bank Sta=4997.1,5003.1
Exp/Cntr=0.3,0.1

Type RM Length L Ch R = 1,6263,398,398,398
BEGIN DESCRIPTION:
UNT056 IN GIBB 6.0
END DESCRIPTION:
XS GIS Cut Line= 3
      3655055.82     10216728.01      3655715.75     10216729.91
      3655966.70     10216686.56
#Sta/Elev= 30
  4584.1  290.43  4652.9  289.55  4690.4  289.17  4780.4  285.49  4790.4  283.34
  4800.4  282.60  4810.4  282.43  4820.4  283.69  4910.4  278.83  4950.4  274.70
  4990.4  268.03  4997.4  266.17  5000.1  265.67  5003.4  266.17  5030.4  270.11
  5060.4  269.86  5080.4  268.44  5150.4  273.03  5191.9  273.52  5259.4  277.41
  5301.2  277.38  5362.1  281.08  5379.0  283.25  5384.1  282.00  5402.7  283.81
  5433.1  284.90  5438.9  286.02  5443.9  285.30  5479.7  288.06  5498.7  288.94
#Mann=6,-1,0
  4584.1    0.05       0  4652.9    0.16       0  4997.4    0.07       0
  5003.4    0.16       0  5191.9    0.05       0  5479.7    0.16       0
Bank Sta=4997.4,5003.4
Exp/Cntr=0.3,0.1

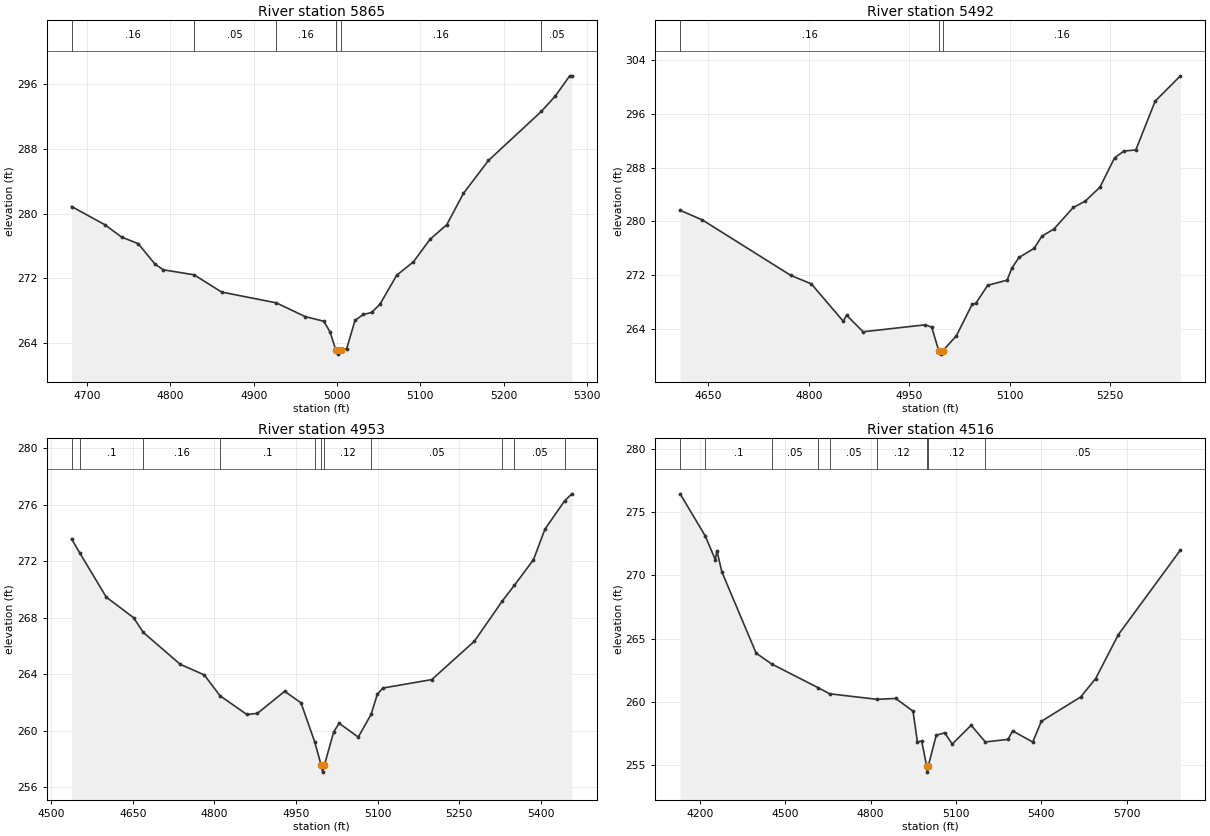
Type RM Length L Ch R = 1,5865,373,373,373
BEGIN DESCRIPTION:
UNT056 IN GIBB 5.0
END DESCRIPTION:
XS GIS Cut Line= 3
      3655342.06     10217041.64      3655642.11     10217041.64
      3655942.06     10217041.64
#Sta/Elev= 30
  4681.6  280.87  4721.6  278.62  4741.6  277.10  4761.6  276.28  4781.6  273.77
  4791.6  273.06  4828.5  272.44  4861.6  270.31  4927.2  268.98  4961.6  267.29
  4984.1  266.71  4991.6  265.40  4998.6  263.15  5001.4  262.65  5004.6  263.15
  5011.6  263.33  5021.6  266.82  5031.6  267.55  5041.6  267.79  5051.6  268.83
  5071.6  272.39  5091.6  274.04  5111.6  276.83  5131.6  278.62  5151.6  282.49
  5181.6  286.55  5245.0  292.60  5261.6  294.48  5279.1  297.00  5281.6  297.00
#Mann=6,-1,0
  4681.6    0.16       0  4828.5    0.05       0  4927.2    0.16       0
  4998.6    0.07       0  5004.6    0.16       0  5245.0    0.05       0
Bank Sta=4998.6,5004.6
Exp/Cntr=0.3,0.1

Type RM Length L Ch R = 1,5492,539,539,539
BEGIN DESCRIPTION:
UNT056 IN GIBB 4.0
END DESCRIPTION:
XS GIS Cut Line= 3
      3655289.33     10217383.97      3655559.51     10217431.66
      3655992.06     10217241.66
#Sta/Elev= 30
  4607.8  281.63  4641.1  280.19  4773.1  271.92  4803.6  270.67  4851.3  265.09
  4856.3  265.99  4880.9  263.52  4973.5  264.56  4983.3  264.21  4993.9  260.69
  4996.6  260.19  4999.9  260.69  5020.2  262.93  5043.6  267.59  5049.1  267.75
  5067.0  270.46  5095.8  271.21  5103.4  273.09  5113.7  274.60  5136.2  275.96
  5147.9  277.78  5165.8  278.84  5194.6  282.05  5212.5  282.99  5234.5  285.08
  5256.3  289.45  5270.2  290.46  5288.1  290.64  5316.9  297.90  5354.6  301.68
#Mann=3,-1,0
  4607.8    0.16       0  4993.9    0.07       0  4999.9    0.16       0
Bank Sta=4993.9,4999.9
Exp/Cntr=0.3,0.1

Type RM Length L Ch R = 1,4953,437,437,437
BEGIN DESCRIPTION:
UNT056 IN GIBB 3.0
END DESCRIPTION:
XS GIS Cut Line= 4
      3655342.11     10217541.65      3655528.34     10217799.28
      3655879.42     10217778.03      3656016.23     10217568.56
#Sta/Elev= 30
  4537.3  273.58  4552.5  272.58  4601.1  269.46  4651.4  268.00  4669.2  266.96
  4737.2  264.70  4781.4  263.95  4810.1  262.48  4859.6  261.15  4879.0  261.23
  4929.1  262.79  4959.1  261.98  4984.2  259.23  4996.2  257.57  4999.0  257.07
  5002.2  257.57  5019.3  259.92  5029.3  260.53  5064.4  259.55  5088.0  261.16
  5099.4  262.57  5109.4  263.02  5199.6  263.62  5278.0  266.34  5329.4  269.19
  5351.6  270.30  5386.6  272.11  5407.7  274.27  5443.8  276.27  5457.1  276.77
#Mann=11,-1,0
  4537.3    0.16       0  4552.5     0.1       0  4669.2    0.16       0
  4810.1     0.1       0  4984.2    0.12       0  4996.2    0.07       0
  5002.2    0.12       0  5088.0    0.05       0  5329.4     0.1       0
  5351.6    0.05       0  5443.8     0.1       0
Bank Sta=4996.2,5002.2
Exp/Cntr=0.3,0.1

Type RM Length L Ch R = 1,4516,0,0,0
BEGIN DESCRIPTION:
UNT056 IN GIBB 1.0
END DESCRIPTION:
XS GIS Cut Line= 4
      3655134.49     10217506.47      3655405.33     10218096.77
      3655870.61     10218173.16      3656196.37     10217625.61
#Sta/Elev= 30
  4130.7  276.45  4219.4  273.10  4254.4  271.23  4259.9  271.96  4277.4  270.27
  4397.9  263.84  4453.8  262.97  4614.8  261.12  4655.8  260.63  4822.9  260.19
  4888.4  260.26  4949.2  259.25  4964.5  256.82  4979.6  256.90  4996.8  254.93
  4999.6  254.43  5002.8  254.93  5030.8  257.35  5060.6  257.54  5087.0  256.65
  5153.3  258.14  5203.2  256.82  5283.2  257.02  5298.8  257.70  5369.8  256.81
  5400.1  258.45  5538.4  260.38  5590.9  261.83  5670.8  265.31  5888.8  272.00
#Mann=9,-1,0
  4130.7    0.16       0  4219.4     0.1       0  4453.8    0.05       0
  4614.8     0.1       0  4655.8    0.05       0  4822.9    0.12       0
  4996.8    0.07       0  5002.8    0.12       0  5203.2    0.05       0
Bank Sta=4996.8,5002.8
Exp/Cntr=0.3,0.1

Chan Stop Cuts=-1