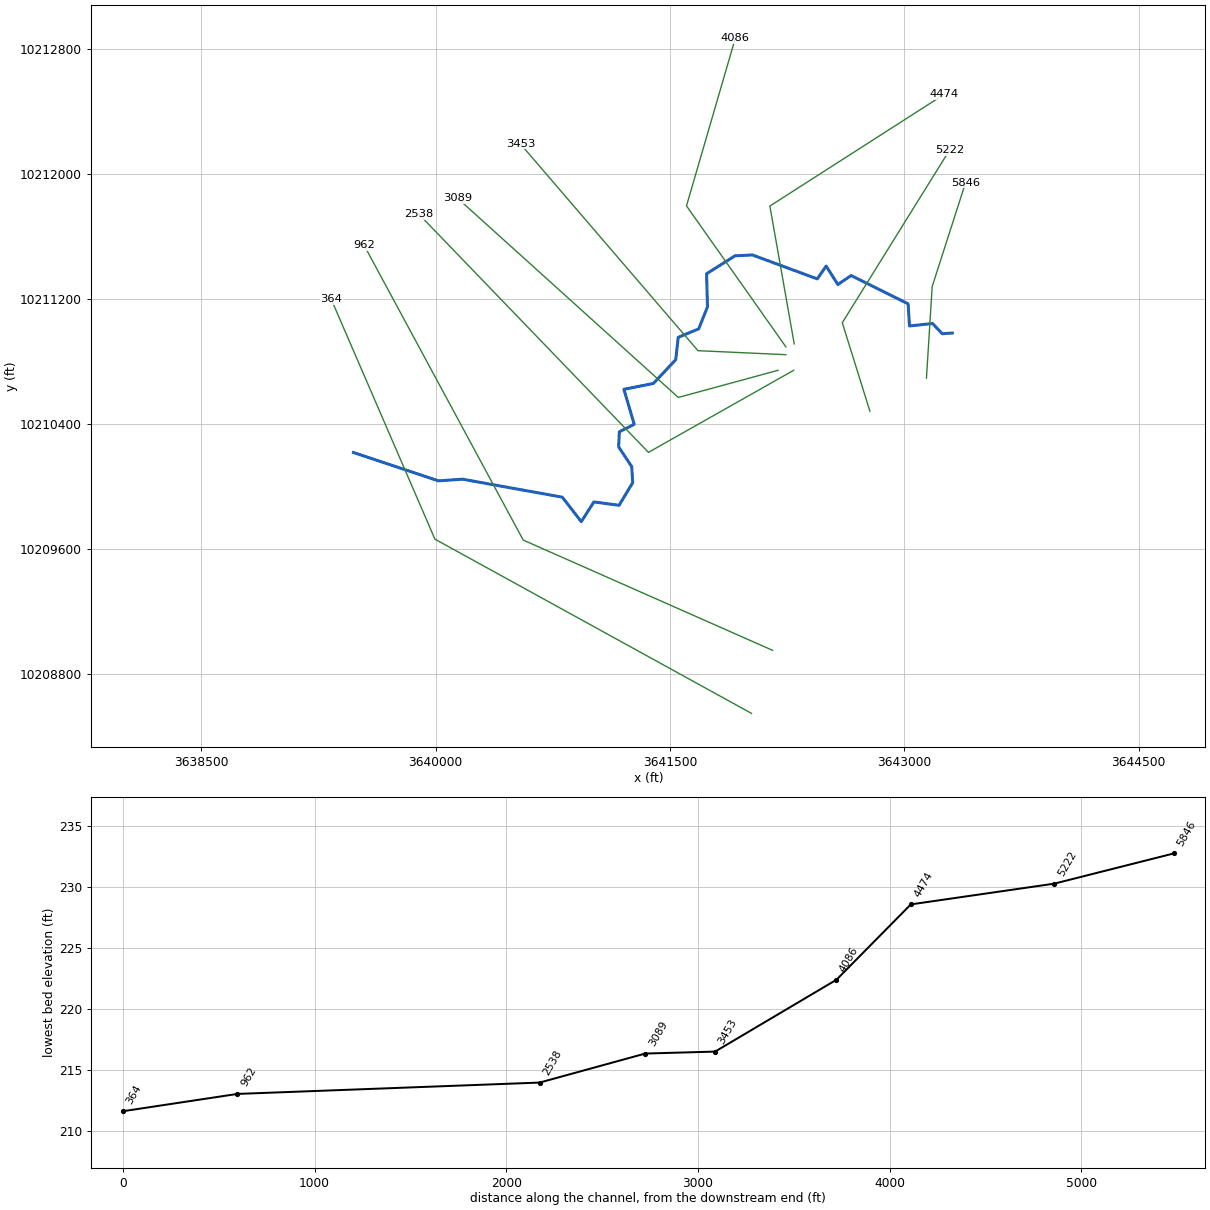
--- UNT057 IN GIBB.prj (project) ---

Proj Title=UNT057 IN GIBB Base Level Engineering
Current Plan=p01
Default Exp/Contr=0.3,0.1
English Units
Geom File=g01
Flow File=f01
Plan File=p01
BEGIN DESCRIPTION:
UNT057 IN GIBB
END DESCRIPTION:

--- UNT057 IN GIBB.p01 (plan) ---

Plan Title=Multiple Run
Short Identifier=Multiple
Geom File=g01
Flow File=f01
Subcritical Flow
K Sum by GR= 0
Std Step Tol= 0.01
Critical Tol= 0.01
Num of Std Step Trials= 20
Max Error Tol= 0.3
Flow Tol Ratio= 0.001
Split Flow NTrial= 30
Split Flow Tol= 0.02
Split Flow Ratio= 0.02
Log Output Level= 0
Friction Slope Method= 1
Unsteady Friction Slope Method= 2
Unsteady Bridges Friction Slope Method= 1
Parabolic Critical Depth
Global Vel Dist=  1 , 1 , 1
Global Log Level= 0
CheckData=True
Encroach Param= -1, 0, 0, 0
BEGIN DESCRIPTION:
Multiple Run
END DESCRIPTION:

--- UNT057 IN GIBB.f01 (steady flow) ---

Flow Title=Multiple
Number of Profiles=7
Profile Names=10-year,25-year,50-year,1pct_min,100-year,1pct_plu,500-year
River Rch & RM= UNT057 IN GIBB,Reach-1,5846
     992    1384    1717    1561    2111    2855    3196
Boundary for River Rch & Prof#=UNT057 IN GIBB,Reach-1,1
Up Type=0
Dn Type=3
Dn Slope=0.005
Boundary for River Rch & Prof#=UNT057 IN GIBB,Reach-1,2
Up Type=0
Dn Type=3
Dn Slope=0.005
Boundary for River Rch & Prof#=UNT057 IN GIBB,Reach-1,3
Up Type=0
Dn Type=3
Dn Slope=0.005
Boundary for River Rch & Prof#=UNT057 IN GIBB,Reach-1,4
Up Type=0
Dn Type=3
Dn Slope=0.005
Boundary for River Rch & Prof#=UNT057 IN GIBB,Reach-1,5
Up Type=0
Dn Type=3
Dn Slope=0.005
Boundary for River Rch & Prof#=UNT057 IN GIBB,Reach-1,6
Up Type=0
Dn Type=3
Dn Slope=0.005
Boundary for River Rch & Prof#=UNT057 IN GIBB,Reach-1,7
Up Type=0
Dn Type=3
Dn Slope=0.005

--- UNT057 IN GIBB.g01 (geometry) ---

Geom Title=Existing Conditions

River Reach=UNT057 IN GIBB,Reach-1
Reach XY= 30
      3643307.44     10210980.19      3643243.06     10210975.73
      3643181.22     10211041.18      3643033.49     10211025.47
      3643024.57     10211167.20      3642659.87     10211348.43
      3642574.84     10211290.74      3642500.04     10211408.90
      3642443.05     10211326.69      3642027.77     10211480.11
      3641916.12     10211474.36      3641734.50     10211359.83
      3641740.14     10211147.86      3641684.19     10211006.93
      3641553.01     10210952.61      3641536.92     10210809.59
      3641394.06     10210657.32      3641205.12     10210619.88
      3641271.09     10210395.52      3641175.85     10210348.23
      3641171.52     10210251.17      3641255.09     10210124.85
      3641261.41     10210022.24      3641174.11     10209877.25
      3641012.85     10209898.90      3640932.36     10209772.56
      3640810.84     10209929.33      3640171.65     10210044.45
      3640017.14     10210033.88      3639473.56     10210215.12

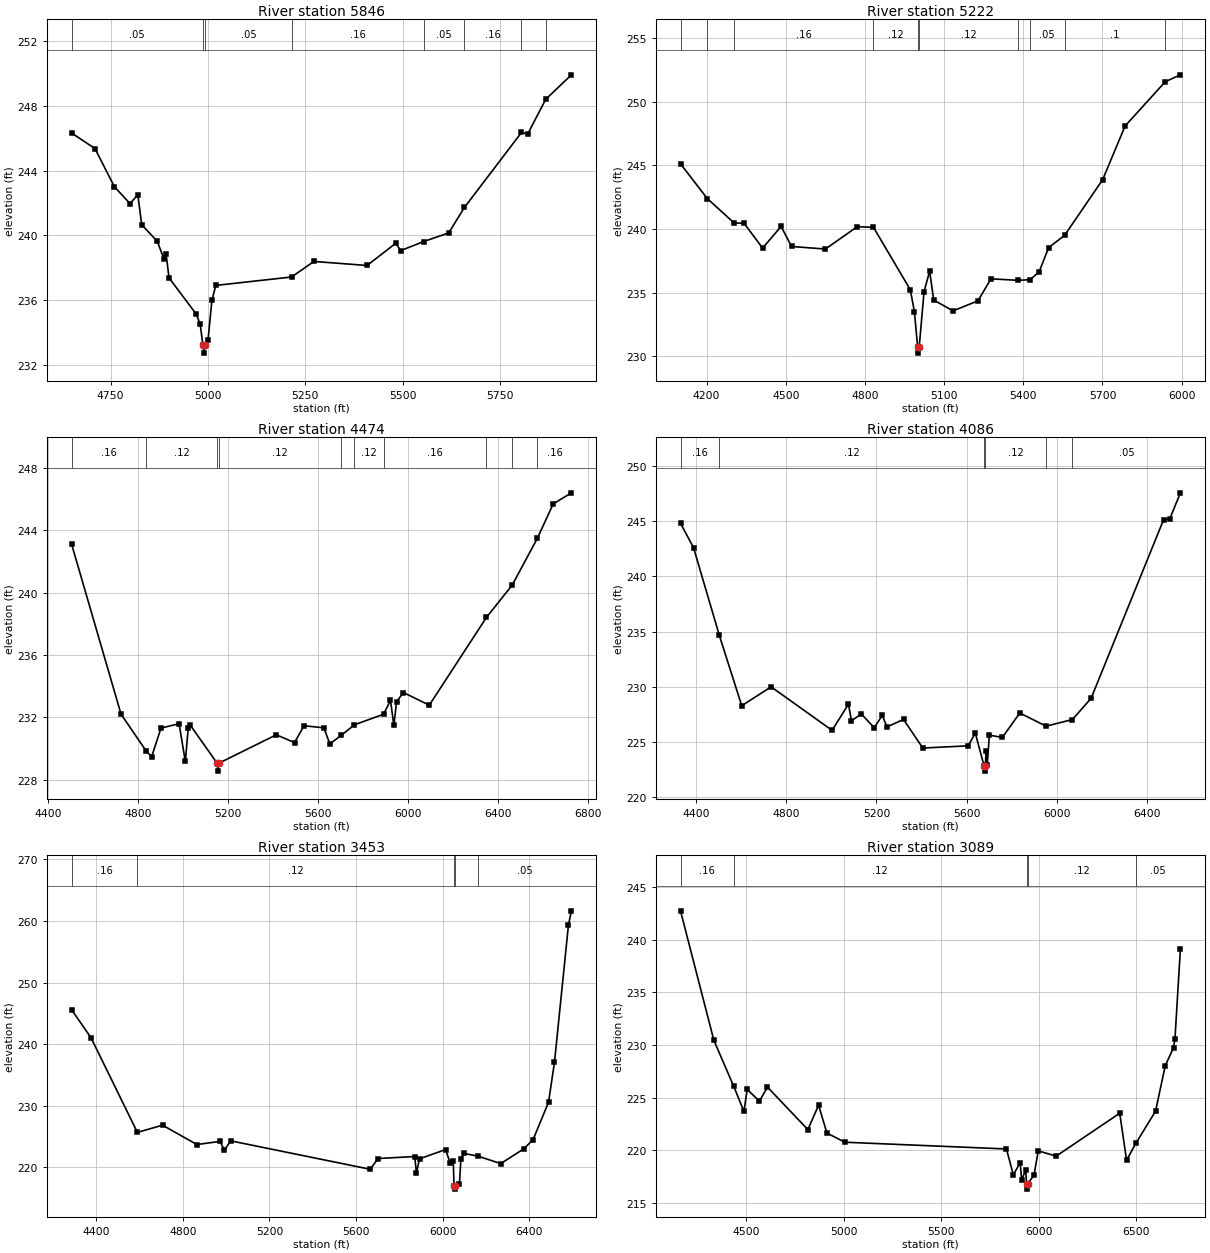
Type RM Length L Ch R = 1,5846,624,624,624
BEGIN DESCRIPTION:
UNT057 IN GIBB 11.0
END DESCRIPTION:
XS GIS Cut Line= 3
      3643142.11     10210691.68      3643178.74     10211277.63
      3643392.09     10211941.60
#Sta/Elev= 30
  4649.5  246.32  4709.6  245.36  4759.7  243.00  4799.8  241.96  4819.8  242.51
  4829.8  240.66  4869.9  239.63  4887.4  238.51  4892.4  238.88  4899.9  237.38
  4970.1  235.13  4980.1  234.50  4987.1  233.23  4989.9  232.73  4993.1  233.23
  5000.1  233.52  5010.2  235.99  5020.2  236.91  5214.9  237.43  5272.3  238.39
  5408.9  238.14  5482.4  239.51  5495.5  239.06  5554.3  239.62  5618.6  240.15
  5658.9  241.72  5805.6  246.35  5821.7  246.26  5867.9  248.40  5934.0  249.91
#Mann=8,-1,0
  4649.5    0.05       0  4987.1    0.04       0  4993.1    0.05       0
  5214.9    0.16       0  5554.3    0.05       0  5658.9    0.16       0
  5805.6    0.05       0  5867.9    0.16       0
Bank Sta=4987.1,4993.1
Exp/Cntr=0.3,0.1

Type RM Length L Ch R = 1,5222,748,748,748
BEGIN DESCRIPTION:
UNT057 IN GIBB 10.0
END DESCRIPTION:
XS GIS Cut Line= 3
      3642779.89     10210480.27      3642603.30     10211046.18
      3643289.86     10212151.24
#Sta/Elev= 30
  4101.4  245.13  4202.7  242.40  4304.4  240.48  4342.1  240.46  4412.4  238.50
  4482.6  240.21  4521.9  238.63  4650.3  238.43  4771.3  240.19  4832.5  240.13
  4972.0  235.23  4987.4  233.51  4999.7  230.75  5002.5  230.25  5005.7  230.75
  5024.0  235.08  5045.2  236.69  5060.6  234.42  5133.8  233.57  5228.3  234.36
  5277.5  236.09  5380.3  235.97  5425.3  236.02  5459.7  236.63  5496.3  238.55
  5556.3  239.50  5700.6  243.88  5785.6  248.10  5937.8  251.58  5995.2  252.12
#Mann=10,-1,0
  4101.4     0.1       0  4202.7    0.05       0  4304.4    0.16       0
  4832.5    0.12       0  4999.7    0.07       0  5005.7    0.12       0
  5380.3    0.16       0  5425.3    0.05       0  5556.3     0.1       0
  5937.8    0.16       0
Bank Sta=4999.7,5005.7
Exp/Cntr=0.3,0.1

Type RM Length L Ch R = 1,4474,388,388,388
BEGIN DESCRIPTION:
UNT057 IN GIBB 8.0
END DESCRIPTION:
XS GIS Cut Line= 3
      3642295.55     10210910.66      3642139.70     10211793.18
      3643257.19     10212509.24
#Sta/Elev= 30
  4504.4  243.12  4724.6  232.20  4837.4  229.82  4860.8  229.48  4902.2  231.31
  4982.7  231.59  5010.5  229.17  5023.3  231.31  5033.4  231.48  5152.3  229.05
  5155.0  228.55  5158.3  229.05  5415.3  230.88  5496.1  230.38  5538.4  231.46
  5626.3  231.33  5653.4  230.30  5703.7  230.84  5762.4  231.52  5892.3  232.20
  5923.0  233.09  5937.9  231.48  5950.1  233.01  5980.5  233.59  6095.5  232.78
  6349.8  238.41  6464.2  240.48  6576.0  243.48  6646.7  245.69  6727.8  246.40
#Mann=10,-1,0
  4504.4    0.16       0  4837.4    0.12       0  5152.3    0.07       0
  5158.3    0.12       0  5703.7    0.16       0  5762.4    0.12       0
  5892.3    0.16       0  6349.8    0.05       0  6464.2     0.1       0
  6576.0    0.16       0
Bank Sta=5152.3,5158.3
Exp/Cntr=0.3,0.1

Type RM Length L Ch R = 1,4086,633,633,633
BEGIN DESCRIPTION:
UNT057 IN GIBB 7.0
END DESCRIPTION:
XS GIS Cut Line= 3
      3642242.08     10210891.68      3641605.86     10211794.12
      3641918.31     10212866.88
#Sta/Elev= 30
  4329.1  244.80  4387.0  242.60  4501.3  234.68  4601.2  228.29  4731.8  230.00
  5002.7  226.06  5075.4  228.43  5088.9  226.94  5133.3  227.53  5189.9  226.30
  5225.6  227.42  5246.7  226.37  5320.1  227.05  5405.8  224.46  5607.7  224.66
  5639.0  225.82  5677.7  222.87  5680.4  222.37  5683.7  222.87  5687.0  224.17
  5692.2  222.94  5701.5  225.63  5759.2  225.42  5836.9  227.63  5953.8  226.44
  6070.8  227.04  6153.7  228.96  6476.1  245.14  6503.5  245.22  6550.6  247.56
#Mann=6,-1,0
  4329.1    0.16       0  4501.3    0.12       0  5677.7    0.07       0
  5683.7    0.12       0  5953.8    0.16       0  6070.8    0.05       0
Bank Sta=5677.7,5683.7
Exp/Cntr=0.3,0.1

Type RM Length L Ch R = 1,3453,364,364,364
BEGIN DESCRIPTION:
UNT057 IN GIBB 6.0
END DESCRIPTION:
XS GIS Cut Line= 3
      3642242.07     10210841.64      3641679.24     10210867.21
      3640542.12     10212191.62
#Sta/Elev= 30
  4285.9  245.62  4376.0  241.05  4590.0  225.69  4706.3  226.86  4864.8  223.72
  4971.3  224.23  4992.1  222.81  5020.7  224.32  5666.0  219.70  5701.1  221.45
  5871.2  221.77  5878.9  219.10  5893.1  221.40  6013.8  222.91  6034.7  220.69
  6049.0  221.06  6052.5  216.98  6055.3  216.48  6058.5  216.98  6077.5  217.24
  6084.1  221.32  6098.3  222.28  6164.6  221.82  6268.4  220.62  6374.9  223.03
  6417.7  224.51  6489.0  230.58  6516.5  237.07  6581.2  259.41  6594.9  261.66
#Mann=5,-1,0
  4285.9    0.16       0  4590.0    0.12       0  6052.5    0.07       0
  6058.5    0.12       0  6164.6    0.05       0
Bank Sta=6052.5,6058.5
Exp/Cntr=0.3,0.1

Type RM Length L Ch R = 1,3089,551,551,551
BEGIN DESCRIPTION:
UNT057 IN GIBB 5.0
END DESCRIPTION:
XS GIS Cut Line= 3
      3642192.08     10210741.64      3641553.37     10210567.74
      3640142.14     10211841.61
#Sta/Elev= 30
  4162.3  242.72  4333.4  230.43  4435.5  226.06  4487.3  223.69  4504.3  225.78
  4566.8  224.66  4607.9  226.00  4815.2  221.97  4870.3  224.28  4912.9  221.64
  5004.8  220.77  5833.5  220.13  5868.7  217.67  5903.8  218.84  5911.3  217.18
  5932.2  218.15  5936.6  216.82  5939.4  216.32  5942.6  216.82  5974.8  217.65
  5996.4  219.95  6088.4  219.45  6414.2  223.52  6449.3  219.06  6497.0  220.67
  6598.0  223.72  6647.4  228.02  6690.0  229.74  6697.4  230.58  6725.4  239.13
#Mann=5,-1,0
  4162.3    0.16       0  4435.5    0.12       0  5936.6    0.07       0
  5942.6    0.12       0  6497.0    0.05       0
Bank Sta=5936.6,5942.6
Exp/Cntr=0.3,0.1

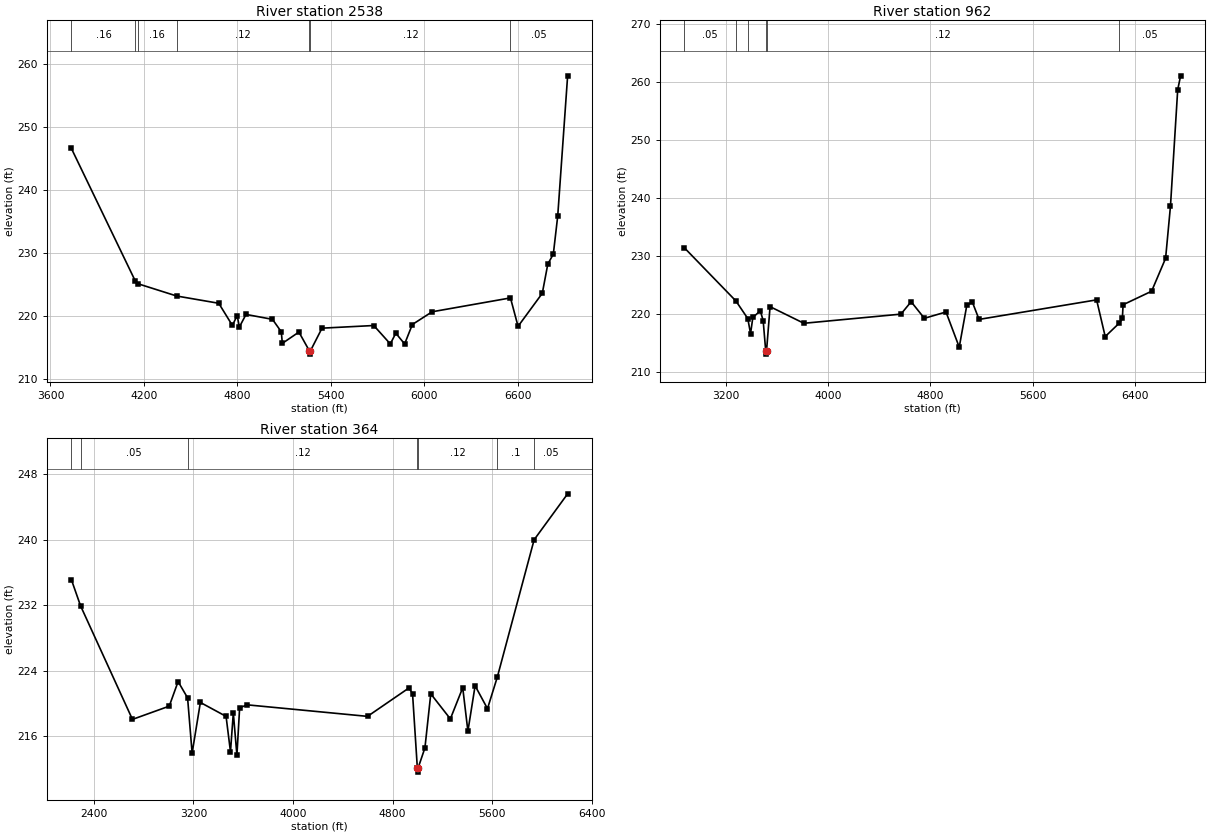
Type RM Length L Ch R = 1,2538,1576,1576,1576
BEGIN DESCRIPTION:
UNT057 IN GIBB 4.0
END DESCRIPTION:
XS GIS Cut Line= 3
      3642292.13     10210741.65      3641362.40     10210216.17
      3639892.13     10211741.62
#Sta/Elev= 30
  3734.1  246.59  4145.7  225.49  4158.9  225.13  4410.6  223.16  4680.5  222.01
  4767.9  218.50  4798.9  220.05  4813.1  218.25  4855.6  220.24  5025.4  219.46
  5082.0  217.49  5088.9  215.65  5195.2  217.44  5262.9  214.44  5265.7  213.94
  5268.9  214.44  5343.6  218.06  5676.0  218.48  5782.0  215.56  5817.5  217.26
  5874.1  215.55  5923.5  218.64  6050.8  220.66  6553.6  222.86  6602.4  218.35
  6758.0  223.59  6793.5  228.24  6828.8  229.80  6857.1  235.86  6920.7  258.10
#Mann=7,-1,0
  3734.1    0.16       0  4145.7    0.05       0  4158.9    0.16       0
  4410.6    0.12       0  5262.9    0.07       0  5268.9    0.12       0
  6553.6    0.05       0
Bank Sta=5262.9,5268.9
Exp/Cntr=0.3,0.1

Type RM Length L Ch R = 1,962,598,598,598
BEGIN DESCRIPTION:
UNT057 IN GIBB 2.0
END DESCRIPTION:
XS GIS Cut Line= 3
      3642156.68     10208948.81      3640560.59     10209654.68
      3639542.10     10211541.65
#Sta/Elev= 30
  2871.2  231.36  3275.5  222.18  3368.5  219.15  3390.3  216.54  3408.2  219.34
  3466.7  220.48  3489.0  218.81  3509.3  213.51  3512.0  213.01  3515.3  213.51
  3543.2  221.20  3808.2  218.33  4568.7  219.91  4648.8  222.05  4752.5  219.19
  4922.0  220.28  5025.8  214.21  5085.7  221.50  5129.5  221.93  5181.1  219.00
  6102.4  222.37  6169.8  216.04  6281.5  218.39  6304.3  219.16  6309.9  221.53
  6533.4  223.86  6643.1  229.54  6681.2  238.52  6738.0  258.63  6760.7  261.02
#Mann=6,-1,0
  2871.2    0.05       0  3275.5    0.16       0  3368.5    0.12       0
  3509.3    0.07       0  3515.3    0.12       0  6281.5    0.05       0
Bank Sta=3509.3,3515.3
Exp/Cntr=0.3,0.1

Type RM Length L Ch R = 1,364,0,0,0
BEGIN DESCRIPTION:
UNT057 IN GIBB 1.0
END DESCRIPTION:
XS GIS Cut Line= 3
      3642022.10     10208545.18      3639995.21     10209660.62
      3639331.25     10211196.83
#Sta/Elev= 30
  2219.5  235.11  2293.2  231.91  2710.3  218.03  3006.0  219.65  3077.1  222.65
  3153.3  220.66  3189.7  213.91  3256.0  220.10  3462.5  218.40  3497.9  214.08
  3520.7  218.82  3549.6  213.65  3571.4  219.44  3631.0  219.81  4599.0  218.40
  4931.7  221.87  4960.6  221.18  4999.2  212.09  5001.9  211.59  5005.2  212.09
  5060.1  214.55  5107.1  221.15  5264.4  218.09  5363.8  221.90  5405.4  216.59
  5463.2  222.14  5562.7  219.34  5642.3  223.23  5937.4  239.97  6206.6  245.58
#Mann=7,-1,0
  2219.5    0.16       0  2293.2    0.05       0  3153.3    0.12       0
  4999.2    0.07       0  5005.2    0.12       0  5642.3     0.1       0
  5937.4    0.05       0
Bank Sta=4999.2,5005.2
Exp/Cntr=0.3,0.1

Chan Stop Cuts=-1