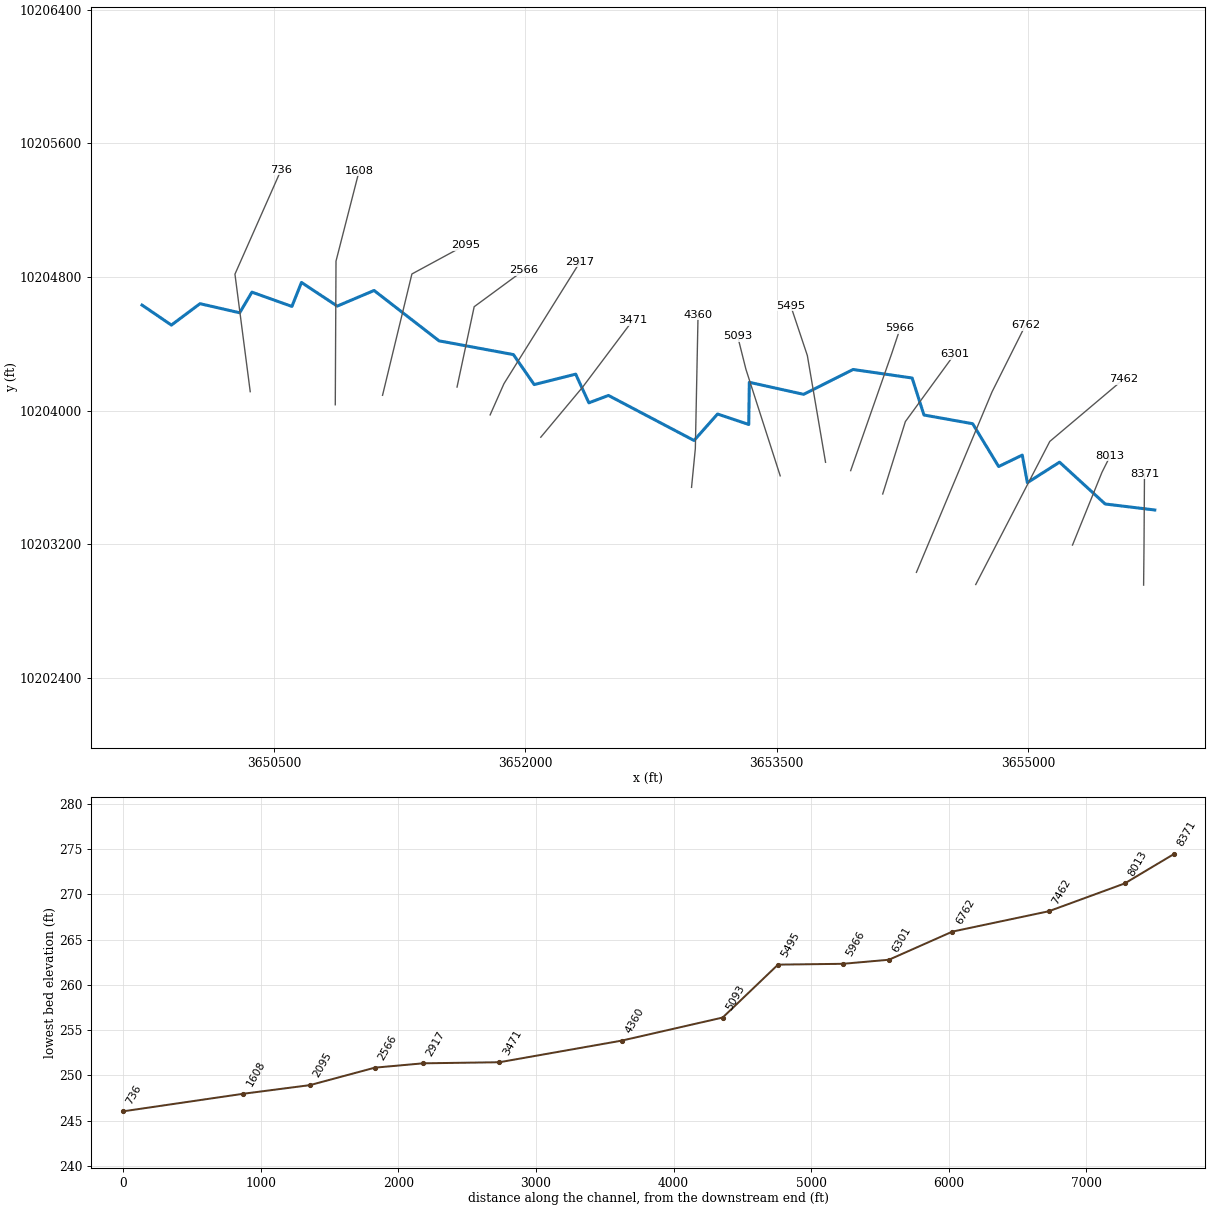
--- UNT059 IN GIBB.prj (project) ---

Proj Title=UNT059 IN GIBB Base Level Engineering
Current Plan=p01
Default Exp/Contr=0.3,0.1
English Units
Geom File=g01
Flow File=f01
Plan File=p01
BEGIN DESCRIPTION:
UNT059 IN GIBB
END DESCRIPTION:

--- UNT059 IN GIBB.p01 (plan) ---

Plan Title=Multiple Run
Short Identifier=Multiple
Geom File=g01
Flow File=f01
Subcritical Flow
K Sum by GR= 0
Std Step Tol= 0.01
Critical Tol= 0.01
Num of Std Step Trials= 20
Max Error Tol= 0.3
Flow Tol Ratio= 0.001
Split Flow NTrial= 30
Split Flow Tol= 0.02
Split Flow Ratio= 0.02
Log Output Level= 0
Friction Slope Method= 1
Unsteady Friction Slope Method= 2
Unsteady Bridges Friction Slope Method= 1
Parabolic Critical Depth
Global Vel Dist=  1 , 1 , 1
Global Log Level= 0
CheckData=True
Encroach Param= -1, 0, 0, 0
BEGIN DESCRIPTION:
Multiple Run
END DESCRIPTION:

--- UNT059 IN GIBB.f01 (steady flow) ---

Flow Title=Multiple
Number of Profiles=7
Profile Names=10-year,25-year,50-year,1pct_min,100-year,1pct_plu,500-year
River Rch & RM= UNT059 IN GIBB,Reach-1,8371
     829    1135    1389    1246    1685    2279    2482
River Rch & RM= UNT059 IN GIBB,Reach-1,6762
     952    1314    1616    1456    1969    2664    2927
River Rch & RM= UNT059 IN GIBB,Reach-1,5495
    1427    2007    2500    2278    3080    4166    4683
Boundary for River Rch & Prof#=UNT059 IN GIBB,Reach-1,1
Up Type=0
Dn Type=3
Dn Slope=0.005
Boundary for River Rch & Prof#=UNT059 IN GIBB,Reach-1,2
Up Type=0
Dn Type=3
Dn Slope=0.005
Boundary for River Rch & Prof#=UNT059 IN GIBB,Reach-1,3
Up Type=0
Dn Type=3
Dn Slope=0.005
Boundary for River Rch & Prof#=UNT059 IN GIBB,Reach-1,4
Up Type=0
Dn Type=3
Dn Slope=0.005
Boundary for River Rch & Prof#=UNT059 IN GIBB,Reach-1,5
Up Type=0
Dn Type=3
Dn Slope=0.005
Boundary for River Rch & Prof#=UNT059 IN GIBB,Reach-1,6
Up Type=0
Dn Type=3
Dn Slope=0.005
Boundary for River Rch & Prof#=UNT059 IN GIBB,Reach-1,7
Up Type=0
Dn Type=3
Dn Slope=0.005

--- UNT059 IN GIBB.g01 (geometry) ---

Geom Title=Existing Conditions

River Reach=UNT059 IN GIBB,Reach-1
Reach XY= 30
      3655757.66     10203406.21      3655461.59     10203442.16
      3655189.04     10203692.35      3654996.98     10203569.73
      3654966.60     10203734.66      3654825.54     10203666.30
      3654670.38     10203922.38      3654379.58     10203974.46
      3654309.05     10204195.82      3653956.40     10204246.82
      3653661.26     10204098.16      3653337.05     10204170.14
      3653333.59     10203917.87      3653147.32     10203980.46
      3653007.01     10203822.11      3652496.10     10204091.46
      3652379.00     10204047.31      3652300.54     10204218.96
      3652052.64     10204156.56      3651928.56     10204336.04
      3651484.51     10204418.23      3651096.86     10204719.46
      3650876.71     10204626.07      3650663.26     10204767.55
      3650606.34     10204624.05      3650367.41     10204709.62
      3650294.57     10204586.11      3650057.53     10204640.44
      3649886.72     10204512.49      3649711.59     10204632.16

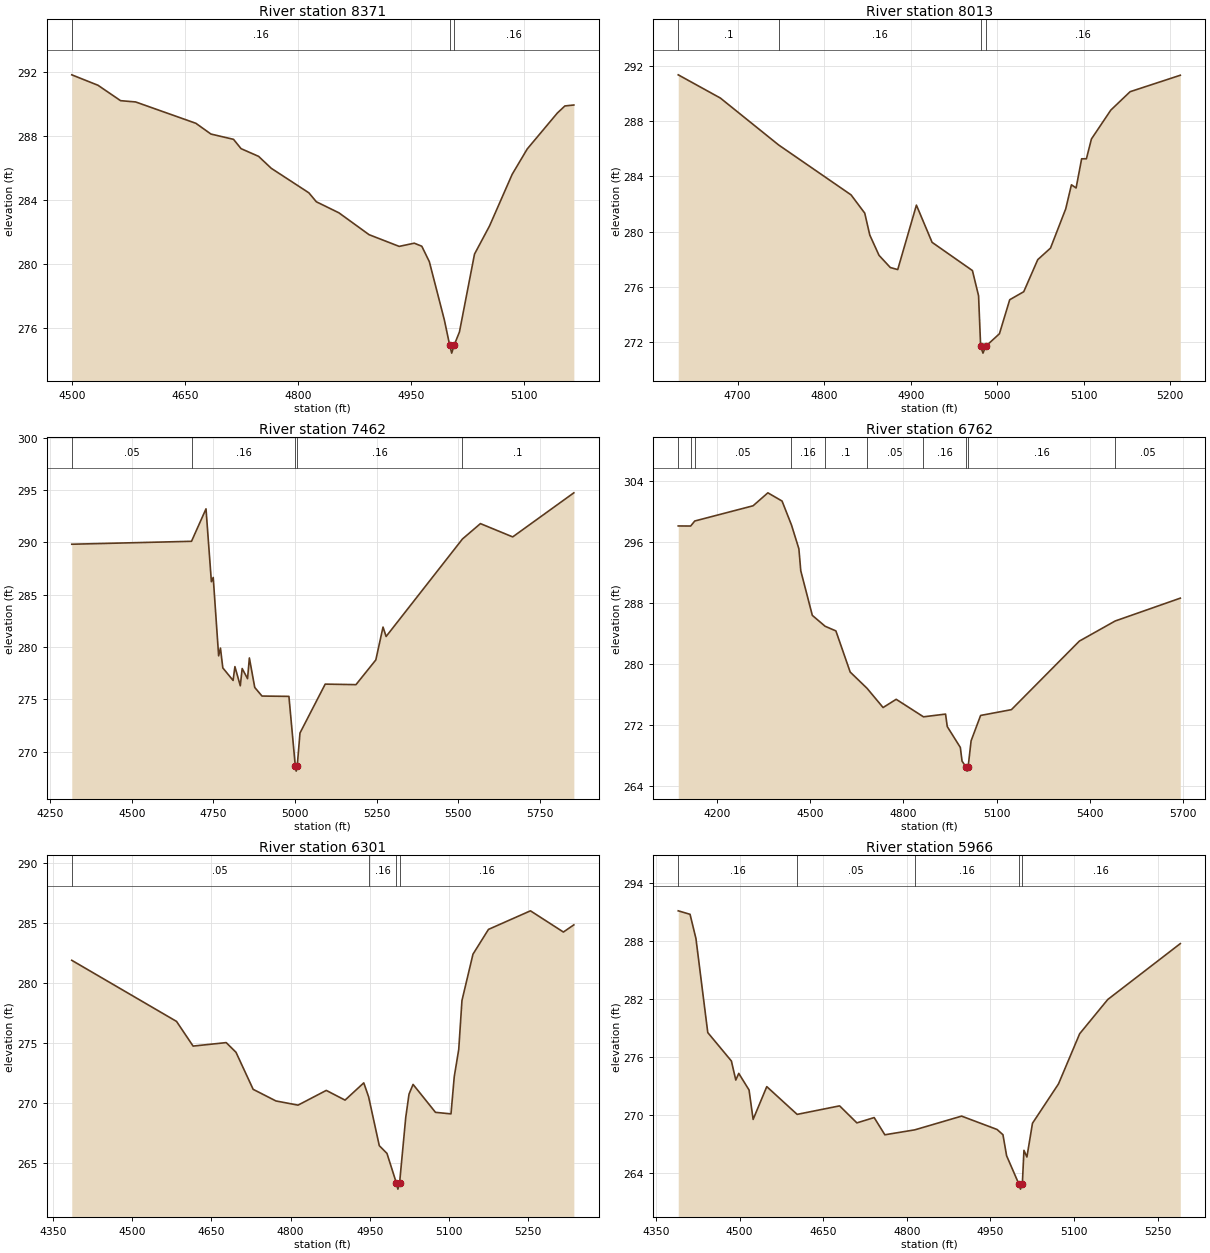
Type RM Length L Ch R = 1,8371,358,358,358
BEGIN DESCRIPTION:
UNT059 IN GIBB 17.0
END DESCRIPTION:
XS GIS Cut Line= 3
      3655690.99     10202956.88      3655693.49     10203205.01
      3655696.20     10203623.56
#Sta/Elev= 30
  4499.2  291.80  4534.0  291.15  4564.0  290.19  4584.0  290.11  4664.0  288.78
  4684.0  288.11  4714.0  287.78  4724.0  287.20  4747.3  286.72  4764.0  285.98
  4814.0  284.45  4824.0  283.89  4854.0  283.20  4894.0  281.84  4934.0  281.11
  4954.0  281.31  4964.0  281.12  4974.0  280.16  4994.0  276.52  5001.0  274.96
  5003.7  274.46  5007.0  274.96  5014.0  275.78  5034.0  280.63  5054.0  282.39
  5084.0  285.60  5104.0  287.18  5144.0  289.42  5154.0  289.86  5165.9  289.92
#Mann=3,-1,0
  4499.2    0.16       0  5001.0    0.07       0  5007.0    0.16       0
Bank Sta=5001,5007
Exp/Cntr=0.3,0.1

Type RM Length L Ch R = 1,8013,551,551,551
BEGIN DESCRIPTION:
UNT059 IN GIBB 16.0
END DESCRIPTION:
XS GIS Cut Line= 3
      3655266.51     10203196.50      3655441.93     10203630.70
      3655491.93     10203730.70
#Sta/Elev= 30
  4631.4  291.33  4680.1  289.65  4747.4  286.26  4831.1  282.65  4846.9  281.33
  4852.7  279.75  4863.4  278.28  4876.4  277.40  4885.0  277.25  4906.6  281.91
  4924.7  279.22  4971.3  277.18  4978.4  275.36  4980.8  271.71  4983.5  271.21
  4986.8  271.71  5002.5  272.61  5014.4  275.07  5030.6  275.65  5046.8  277.97
  5061.5  278.80  5079.1  281.64  5085.7  283.38  5091.1  283.15  5097.5  285.26
  5103.0  285.26  5108.8  286.69  5131.2  288.78  5153.5  290.11  5211.5  291.30
#Mann=4,-1,0
  4631.4     0.1       0  4747.4    0.16       0  4980.8    0.07       0
  4986.8    0.16       0
Bank Sta=4980.8,4986.8
Exp/Cntr=0.3,0.1

Type RM Length L Ch R = 1,7462,700,700,700
BEGIN DESCRIPTION:
UNT059 IN GIBB 15.0
END DESCRIPTION:
XS GIS Cut Line= 3
      3654688.76     10202960.31      3655130.79     10203816.32
      3655570.07     10204187.81
#Sta/Elev= 30
  4315.8  289.81  4682.8  290.09  4727.2  293.19  4743.7  286.23  4749.3  286.64
  4765.9  279.15  4771.5  279.89  4778.7  278.00  4810.2  276.80  4815.8  278.12
  4832.3  276.29  4838.0  277.94  4854.5  276.97  4860.1  278.95  4876.6  276.13
  4898.8  275.31  4981.3  275.28  5000.8  268.64  5003.6  268.14  5006.8  268.64
  5015.2  271.78  5092.5  276.45  5186.8  276.40  5247.6  278.76  5269.7  281.90
  5279.2  281.00  5513.1  290.31  5568.2  291.78  5667.1  290.51  5854.5  294.72
#Mann=5,-1,0
  4315.8    0.05       0  4682.8    0.16       0  5000.8    0.07       0
  5006.8    0.16       0  5513.1     0.1       0
Bank Sta=5000.8,5006.8
Exp/Cntr=0.3,0.1

Type RM Length L Ch R = 1,6762,461,461,461
BEGIN DESCRIPTION:
UNT059 IN GIBB 14.0
END DESCRIPTION:
XS GIS Cut Line= 3
      3654334.56     10203033.16      3654785.86     10204112.48
      3654985.87     10204512.50
#Sta/Elev= 30
  4074.5  298.08  4114.5  298.07  4127.7  298.73  4315.6  300.73  4363.2  302.43
  4408.9  301.35  4439.3  298.20  4463.1  295.08  4469.2  292.19  4506.4  286.34
  4547.6  284.91  4582.3  284.30  4628.3  278.90  4682.5  276.77  4734.3  274.24
  4776.5  275.32  4864.4  273.02  4935.5  273.38  4941.0  271.74  4983.1  269.00
  4988.6  267.21  5002.0  266.39  5004.8  265.89  5008.0  266.39  5017.8  269.87
  5048.4  273.20  5147.6  273.96  5366.4  282.96  5481.7  285.60  5691.6  288.60
#Mann=10,-1,0
  4074.5    0.08       0  4114.5    0.16       0  4127.7    0.05       0
  4439.3    0.16       0  4547.6     0.1       0  4682.5    0.05       0
  4864.4    0.16       0  5002.0    0.07       0  5008.0    0.16       0
  5481.7    0.05       0
Bank Sta=5002,5008
Exp/Cntr=0.3,0.1

Type RM Length L Ch R = 1,6301,335,335,335
BEGIN DESCRIPTION:
UNT059 IN GIBB 13.0
END DESCRIPTION:
XS GIS Cut Line= 3
      3654133.41     10203502.02      3654268.66     10203935.15
      3654561.98     10204338.15
#Sta/Elev= 30
  4385.0  281.88  4583.7  276.78  4615.1  274.72  4677.9  275.01  4696.5  274.20
  4729.0  271.11  4772.2  270.14  4814.1  269.79  4867.7  271.02  4903.3  270.21
  4938.8  271.65  4948.0  270.48  4968.2  266.41  4982.8  265.76  5000.7  263.28
  5003.5  262.78  5006.7  263.28  5018.4  268.77  5024.6  270.71  5032.3  271.52
  5074.8  269.19  5104.2  269.06  5110.4  272.17  5118.9  274.44  5125.0  278.52
  5145.9  282.39  5175.3  284.46  5254.9  286.01  5317.4  284.24  5337.2  284.84
#Mann=4,-1,0
  4385.0    0.05       0  4948.0    0.16       0  5000.7    0.07       0
  5006.7    0.16       0
Bank Sta=5000.7,5006.7
Exp/Cntr=0.3,0.1

Type RM Length L Ch R = 1,5966,471,471,471
BEGIN DESCRIPTION:
UNT059 IN GIBB 12.0
END DESCRIPTION:
XS GIS Cut Line= 3
      3653942.10     10203641.63      3654187.59     10204343.55
      3654237.36     10204492.86
#Sta/Elev= 30
  4389.9  291.11  4411.1  290.75  4421.7  288.24  4442.9  278.52  4485.3  275.58
  4493.2  273.61  4498.5  274.30  4517.0  272.58  4524.3  269.54  4548.8  272.93
  4603.3  270.06  4679.5  270.94  4710.5  269.18  4741.5  269.73  4760.7  267.95
  4814.4  268.46  4898.4  269.88  4962.0  268.50  4972.6  267.96  4979.2  265.78
  5001.4  262.83  5004.1  262.33  5007.4  262.83  5010.3  266.34  5015.6  265.65
  5025.6  269.14  5072.3  273.21  5110.3  278.40  5160.7  281.94  5290.9  287.72
#Mann=5,-1,0
  4389.9    0.16       0  4603.3    0.05       0  4814.4    0.16       0
  5001.4    0.07       0  5007.4    0.16       0
Bank Sta=5001.4,5007.4
Exp/Cntr=0.3,0.1

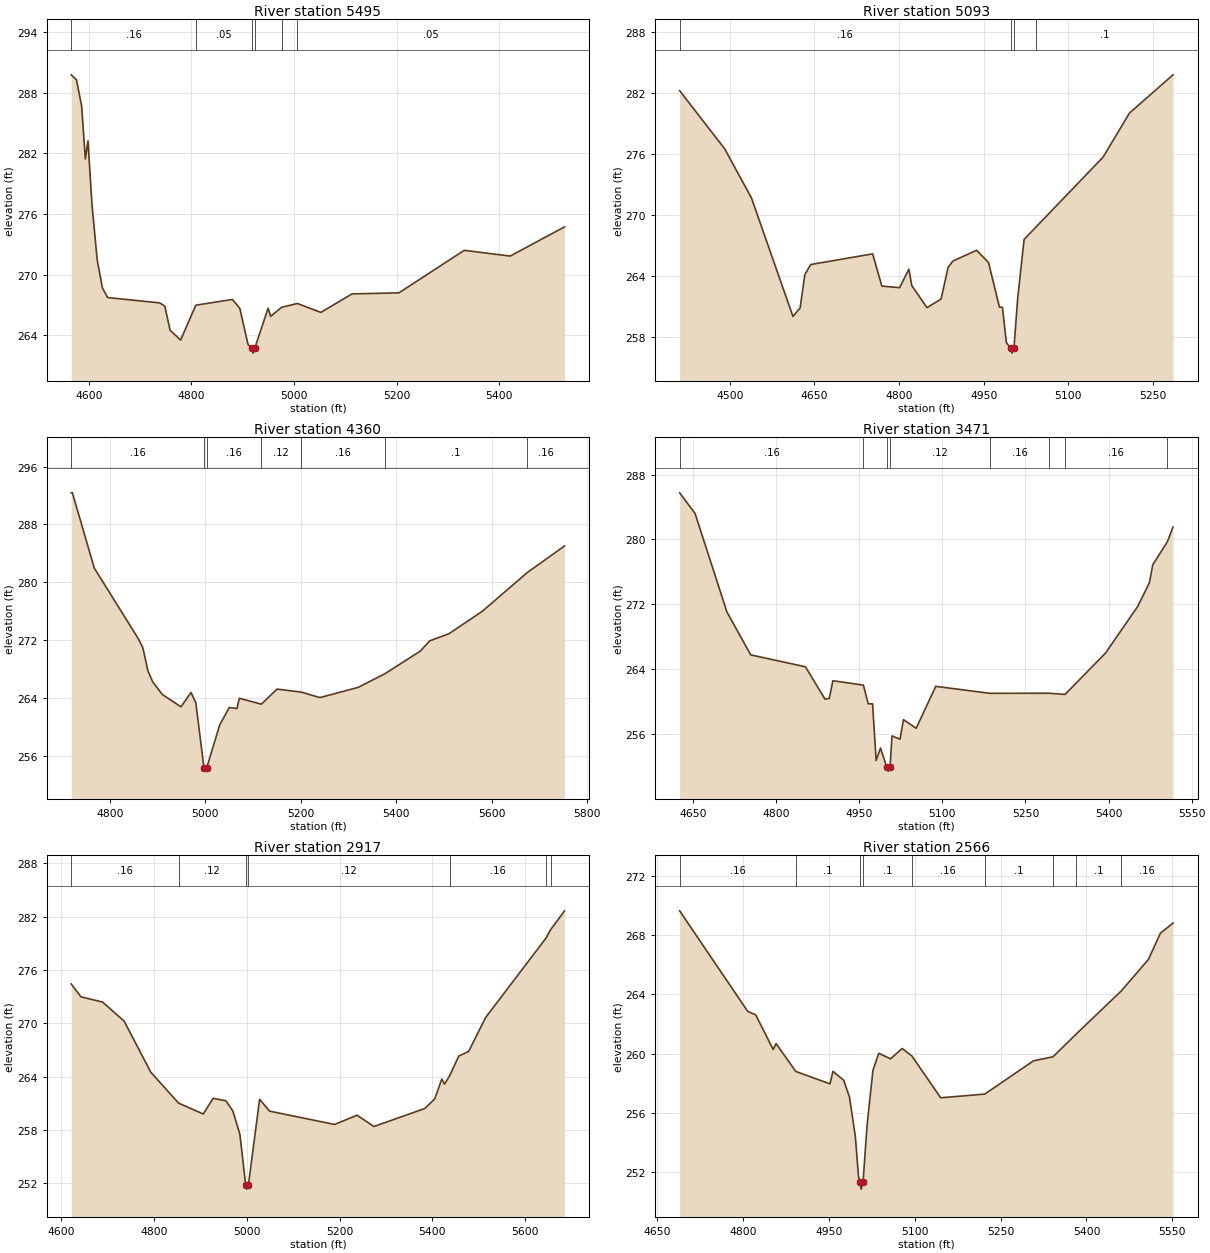
Type RM Length L Ch R = 1,5495,402,402,402
BEGIN DESCRIPTION:
UNT059 IN GIBB 11.0
END DESCRIPTION:
XS GIS Cut Line= 3
      3653792.11     10203691.61      3653683.42     10204330.36
      3653584.04     10204628.50
#Sta/Elev= 30
  4565.5  289.77  4575.7  289.29  4585.8  286.70  4593.1  281.45  4598.2  283.24
  4606.1  276.89  4616.3  271.42  4626.4  268.69  4636.5  267.74  4738.0  267.21
  4748.1  266.89  4758.3  264.51  4778.9  263.53  4808.5  266.98  4880.0  267.55
  4894.3  266.67  4910.4  263.09  4917.6  262.74  4920.3  262.24  4923.6  262.74
  4949.5  266.68  4954.5  265.88  4975.8  266.77  5006.5  267.15  5052.4  266.27
  5113.3  268.10  5204.6  268.20  5332.1  272.41  5421.7  271.84  5527.7  274.73
#Mann=6,-1,0
  4565.5    0.16       0  4808.5    0.05       0  4917.6    0.07       0
  4923.6    0.05       0  4975.8    0.16       0  5006.5    0.05       0
Bank Sta=4917.6,4923.6
Exp/Cntr=0.3,0.1

Type RM Length L Ch R = 1,5093,733,733,733
BEGIN DESCRIPTION:
UNT059 IN GIBB 10.0
END DESCRIPTION:
XS GIS Cut Line= 3
      3653521.44     10203610.49      3653316.42     10204249.15
      3653267.08     10204446.52
#Sta/Elev= 30
  4411.2  282.22  4491.0  276.50  4538.4  271.67  4612.0  260.00  4624.7  260.84
  4633.0  264.11  4643.5  265.11  4753.2  266.16  4769.5  262.99  4801.0  262.83
  4817.4  264.65  4822.6  263.03  4849.5  260.87  4874.5  261.71  4886.9  264.84
  4895.5  265.46  4937.5  266.51  4958.5  265.31  4977.9  260.92  4983.2  260.90
  4990.1  257.44  4997.6  256.89  5000.3  256.39  5003.6  256.89  5010.1  261.71
  5021.6  267.58  5042.6  268.80  5161.7  275.69  5208.2  280.01  5285.4  283.78
#Mann=4,-1,0
  4411.2    0.16       0  4997.6    0.07       0  5003.6    0.16       0
  5042.6     0.1       0
Bank Sta=4997.6,5003.6
Exp/Cntr=0.3,0.1

Type RM Length L Ch R = 1,4360,889,889,889
BEGIN DESCRIPTION:
UNT059 IN GIBB 9.0
END DESCRIPTION:
XS GIS Cut Line= 3
      3652992.10     10203541.61      3653014.79     10203774.42
      3653030.98     10204574.04
#Sta/Elev= 30
  4718.9  292.36  4721.4  292.36  4767.3  281.94  4859.6  272.16  4869.1  270.90
  4879.7  267.71  4889.7  266.19  4909.8  264.45  4948.9  262.74  4970.0  264.73
  4980.0  263.31  4997.0  254.34  4999.8  253.84  5003.0  254.34  5030.1  260.24
  5050.1  262.64  5066.2  262.51  5071.2  263.92  5117.4  263.11  5150.1  265.19
  5200.7  264.78  5240.1  264.02  5320.1  265.43  5376.0  267.31  5450.1  270.44
  5470.1  271.87  5510.2  272.85  5580.2  275.96  5674.4  281.32  5752.6  285.01
#Mann=7,-1,0
  4718.9    0.16       0  4997.0    0.07       0  5003.0    0.16       0
  5117.4    0.12       0  5200.7    0.16       0  5376.0     0.1       0
  5674.4    0.16       0
Bank Sta=4997,5003
Exp/Cntr=0.3,0.1

Type RM Length L Ch R = 1,3471,554,554,554
BEGIN DESCRIPTION:
UNT059 IN GIBB 7.0
END DESCRIPTION:
XS GIS Cut Line= 3
      3652092.13     10203841.67      3652342.11     10204141.64
      3652642.12     10204541.66
#Sta/Elev= 30
  4625.8  285.75  4653.7  283.20  4711.0  271.09  4754.0  265.78  4852.9  264.31
  4888.1  260.33  4895.9  260.41  4902.4  262.59  4957.5  262.05  4966.2  259.74
  4974.0  259.75  4980.5  252.76  4988.3  254.30  4999.6  251.95  5002.4  251.45
  5005.6  251.95  5009.1  255.79  5023.6  255.38  5029.8  257.80  5052.7  256.73
  5088.1  261.90  5185.3  261.04  5292.9  261.05  5321.4  260.90  5394.4  265.99
  5452.7  271.76  5473.6  274.64  5479.8  276.88  5506.0  279.70  5516.3  281.53
#Mann=8,-1,0
  4625.8    0.16       0  4957.5    0.12       0  4999.6    0.07       0
  5005.6    0.12       0  5185.3    0.16       0  5292.9    0.12       0
  5321.4    0.16       0  5506.0     0.1       0
Bank Sta=4999.6,5005.6
Exp/Cntr=0.3,0.1

Type RM Length L Ch R = 1,2917,351,351,351
BEGIN DESCRIPTION:
UNT059 IN GIBB 6.0
END DESCRIPTION:
XS GIS Cut Line= 3
      3651789.67     10203975.12      3651872.13     10204161.74
      3652327.11     10204891.38
#Sta/Elev= 30
  4621.2  274.43  4642.2  272.98  4688.8  272.39  4735.4  270.24  4792.9  264.49
  4852.8  261.01  4906.0  259.79  4927.2  261.55  4954.7  261.28  4969.7  260.14
  4985.0  257.49  4997.4  251.83  5000.1  251.33  5003.4  251.83  5027.5  261.44
  5049.0  260.11  5189.1  258.61  5237.6  259.65  5274.1  258.38  5383.8  260.41
  5405.0  261.48  5420.4  263.72  5426.3  263.15  5437.4  264.10  5457.0  266.31
  5478.2  266.83  5514.8  270.64  5645.1  279.59  5655.1  280.54  5685.1  282.66
#Mann=7,-1,0
  4621.2    0.16       0  4852.8    0.12       0  4997.4    0.07       0
  5003.4    0.12       0  5437.4    0.16       0  5645.1     0.1       0
  5655.1    0.16       0
Bank Sta=4997.4,5003.4
Exp/Cntr=0.3,0.1

Type RM Length L Ch R = 1,2566,471,471,471
BEGIN DESCRIPTION:
UNT059 IN GIBB 5.0
END DESCRIPTION:
XS GIS Cut Line= 3
      3651592.11     10204141.66      3651694.38     10204622.33
      3651992.09     10204841.63
#Sta/Elev= 30
  4689.8  269.65  4808.6  262.86  4822.7  262.62  4853.1  260.28  4858.2  260.68
  4892.5  258.80  4952.3  257.96  4957.4  258.81  4976.1  258.21  4986.3  257.06
  4996.5  254.41  5001.9  251.76  5004.0  251.35  5006.7  250.85  5010.0  251.35
  5016.9  255.12  5027.2  258.87  5037.4  260.03  5057.8  259.65  5078.3  260.35
  5095.1  259.85  5145.5  257.02  5222.4  257.27  5307.7  259.52  5341.6  259.79
  5382.4  261.34  5460.8  264.24  5508.2  266.37  5529.1  268.14  5551.0  268.82
#Mann=9,-1,0
  4689.8    0.16       0  4892.5     0.1       0  5004.0    0.07       0
  5010.0     0.1       0  5095.1    0.16       0  5222.4     0.1       0
  5341.6    0.16       0  5382.4     0.1       0  5460.8    0.16       0
Bank Sta=5004,5010
Exp/Cntr=0.3,0.1

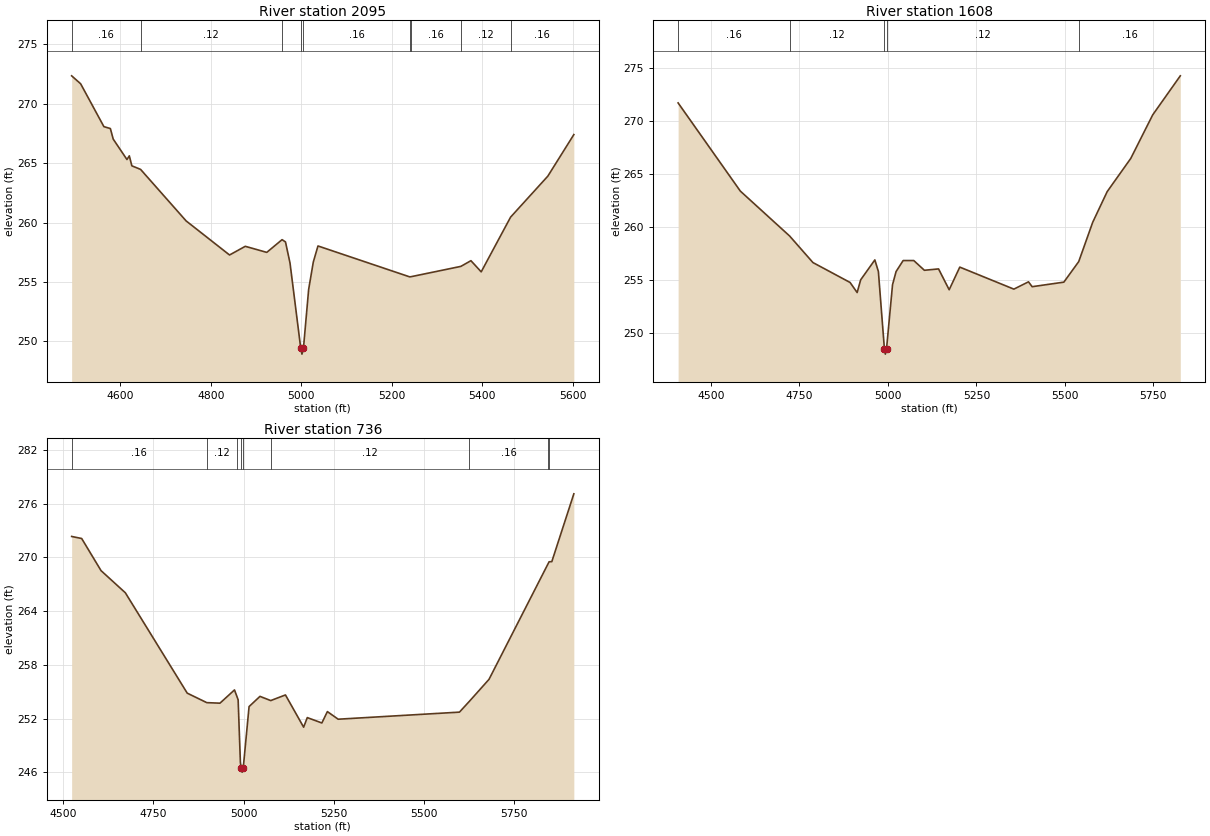
Type RM Length L Ch R = 1,2095,487,487,487
BEGIN DESCRIPTION:
UNT059 IN GIBB 4.0
END DESCRIPTION:
XS GIS Cut Line= 3
      3651147.30     10204092.29      3651322.58     10204818.18
      3651642.08     10204991.63
#Sta/Elev= 30
  4492.4  272.36  4512.3  271.69  4563.7  268.08  4578.0  267.92  4584.3  267.03
  4614.7  265.31  4619.9  265.62  4625.5  264.78  4644.8  264.48  4745.5  260.14
  4841.5  257.27  4876.3  258.00  4923.8  257.49  4957.6  258.56  4965.2  258.37
  4975.2  256.59  4998.9  249.42  5001.6  248.92  5004.9  249.42  5016.4  254.37
  5026.7  256.68  5037.0  258.03  5239.6  255.43  5242.6  255.44  5352.9  256.31
  5375.2  256.79  5397.9  255.85  5462.9  260.46  5545.2  263.91  5602.7  267.41
#Mann=9,-1,0
  4492.4    0.16       0  4644.8    0.12       0  4957.6    0.16       0
  4998.9    0.07       0  5004.9    0.16       0  5239.6    0.12       0
  5242.6    0.16       0  5352.9    0.12       0  5462.9    0.16       0
Bank Sta=4998.9,5004.9
Exp/Cntr=0.3,0.1

Type RM Length L Ch R = 1,1608,872,872,872
BEGIN DESCRIPTION:
UNT059 IN GIBB 3.0
END DESCRIPTION:
XS GIS Cut Line= 3
      3650865.18     10204035.85      3650869.52     10204895.25
      3651008.25     10205437.17
#Sta/Elev= 30
  4407.2  271.69  4583.0  263.36  4722.2  259.12  4788.1  256.61  4893.0  254.73
  4913.0  253.78  4923.0  254.98  4963.0  256.86  4973.0  255.77  4990.0  248.46
  4992.7  247.96  4996.0  248.46  5013.0  254.52  5023.0  255.76  5043.0  256.80
  5073.0  256.80  5103.0  255.88  5143.0  256.01  5173.0  254.04  5203.0  256.18
  5355.8  254.10  5397.1  254.79  5407.4  254.33  5497.0  254.76  5539.0  256.70
  5578.6  260.42  5619.4  263.31  5686.1  266.45  5748.0  270.56  5826.0  274.25
#Mann=5,-1,0
  4407.2    0.16       0  4722.2    0.12       0  4990.0    0.07       0
  4996.0    0.12       0  5539.0    0.16       0
Bank Sta=4990,4996
Exp/Cntr=0.3,0.1

Type RM Length L Ch R = 1,736,0,0,0
BEGIN DESCRIPTION:
UNT059 IN GIBB 1.0
END DESCRIPTION:
XS GIS Cut Line= 3
      3650357.36     10204114.04      3650266.22     10204817.12
      3650542.10     10205441.63
#Sta/Elev= 30
  4523.3  272.34  4551.1  272.11  4604.8  268.52  4672.1  266.05  4843.6  254.84
  4897.8  253.78  4934.3  253.72  4974.6  255.20  4982.1  254.38  4984.7  254.09
  4990.9  247.15  4992.9  246.52  4995.7  246.02  4998.9  246.52  5015.0  253.34
  5045.2  254.48  5075.0  254.01  5115.8  254.64  5166.2  251.04  5176.3  252.11
  5216.7  251.51  5232.0  252.78  5261.9  251.93  5598.0  252.72  5625.8  253.94
  5679.9  256.38  5844.5  269.36  5846.4  269.51  5854.0  269.53  5915.0  277.10
#Mann=9,-1,0
  4523.3    0.16       0  4897.8    0.12       0  4982.1    0.16       0
  4992.9    0.07       0  4998.9    0.16       0  5075.0    0.12       0
  5625.8    0.16       0  5844.5    0.05       0  5846.4    0.16       0
Bank Sta=4992.9,4998.9
Exp/Cntr=0.3,0.1

Chan Stop Cuts=-1