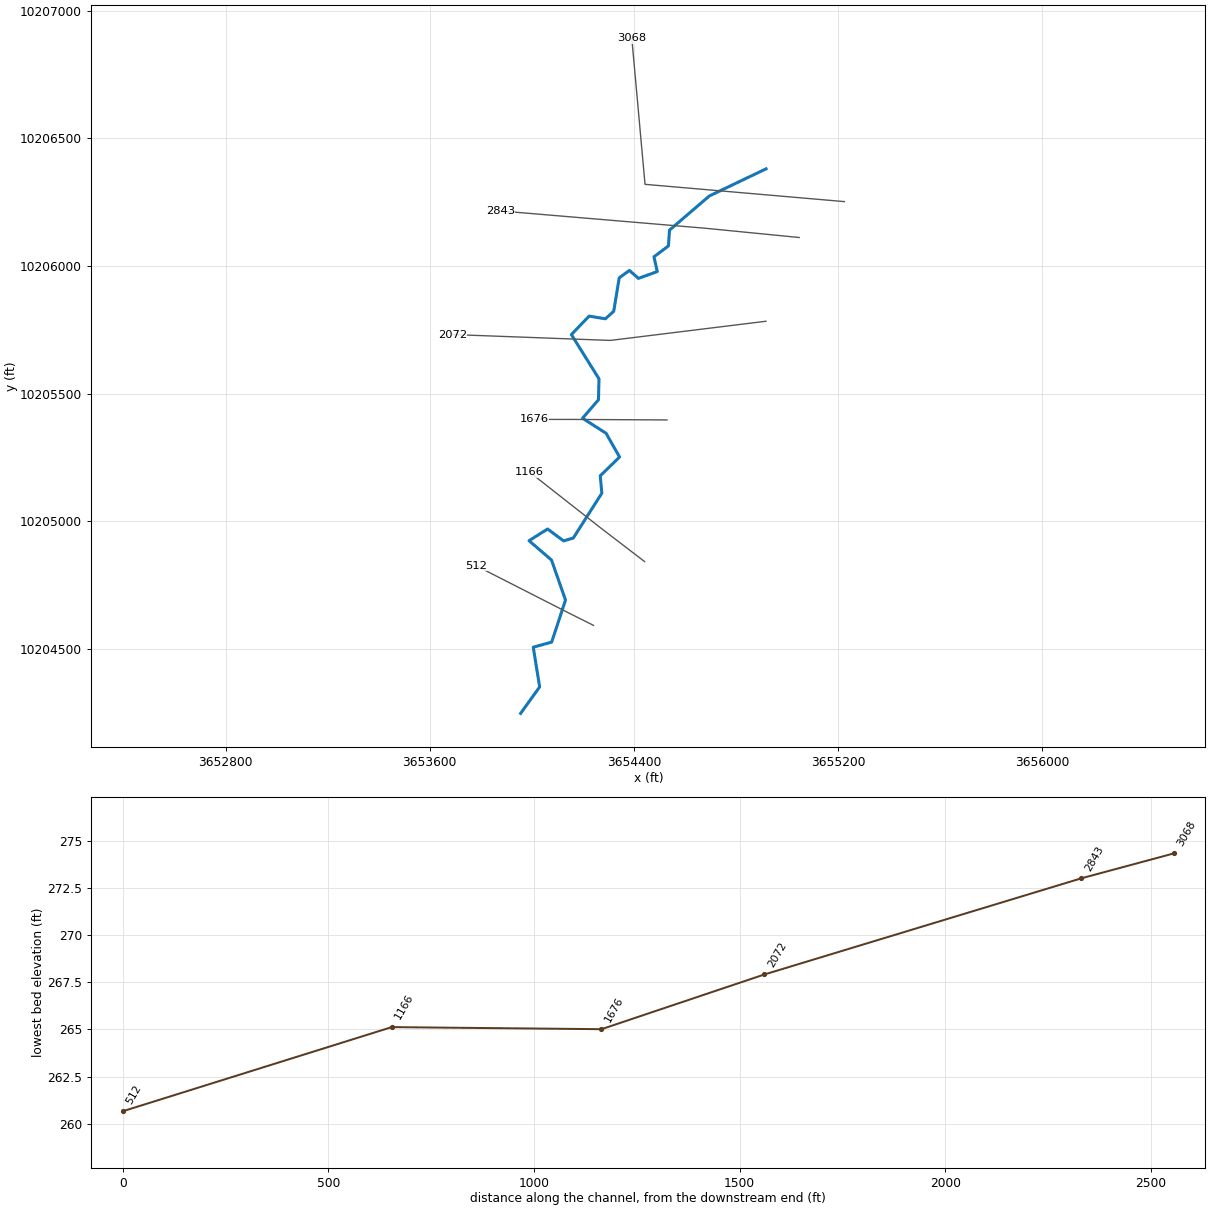
--- UNT060 IN GIBB.prj (project) ---

Proj Title=UNT060 IN GIBB Base Level Engineering
Current Plan=p01
Default Exp/Contr=0.3,0.1
English Units
Geom File=g01
Flow File=f01
Plan File=p01
Y Axis Title=Elevation
X Axis Title(PF)=Main Channel Distance
X Axis Title(XS)=Station
BEGIN DESCRIPTION:
UNT060 IN GIBB
END DESCRIPTION:
DSS Export Rating Curves= 0
DSS Export Rating Curve Sorted= 0
DSS Export Volume Flow Curves= 0
DXF OffsetX= 0
DXF OffsetY= 0
DXF ScaleX= 1
DXF ScaleY= 10

--- UNT060 IN GIBB.p01 (plan) ---

Plan Title=Multiple Run
Short Identifier=Multiple
Geom File=g01
Flow File=f01
Subcritical Flow
K Sum by GR= 0
Std Step Tol= 0.01
Critical Tol= 0.01
Num of Std Step Trials= 20
Max Error Tol= 0.3
Flow Tol Ratio= 0.001
Split Flow NTrial= 30
Split Flow Tol= 0.02
Split Flow Ratio= 0.02
Log Output Level= 0
Friction Slope Method= 1
Unsteady Friction Slope Method= 2
Unsteady Bridges Friction Slope Method= 1
Parabolic Critical Depth
Global Vel Dist=  1 , 1 , 1
Global Log Level= 0
CheckData=True
Encroach Param= -1, 0, 0, 0
BEGIN DESCRIPTION:
Multiple Run
END DESCRIPTION:

--- UNT060 IN GIBB.f01 (steady flow) ---

Flow Title=Multiple
Program Version=4.10
Number of Profiles= 7
Profile Names=10-year,25-year,50-year,1pct_min,100-year,1pct_plu,500-year
River Rch & RM=UNT060 IN GIBB,Reach-1         ,3068
     585     784     946     838    1133    1533    1626
Boundary for River Rch & Prof#=UNT060 IN GIBB,Reach-1         , 1
Up Type= 0
Dn Type= 3
Dn Slope=0.0065
Boundary for River Rch & Prof#=UNT060 IN GIBB,Reach-1         , 2
Up Type= 0
Dn Type= 3
Dn Slope=0.0065
Boundary for River Rch & Prof#=UNT060 IN GIBB,Reach-1         , 3
Up Type= 0
Dn Type= 3
Dn Slope=0.0065
Boundary for River Rch & Prof#=UNT060 IN GIBB,Reach-1         , 4
Up Type= 0
Dn Type= 3
Dn Slope=0.0065
Boundary for River Rch & Prof#=UNT060 IN GIBB,Reach-1         , 5
Up Type= 0
Dn Type= 3
Dn Slope=0.0065
Boundary for River Rch & Prof#=UNT060 IN GIBB,Reach-1         , 6
Up Type= 0
Dn Type= 3
Dn Slope=0.0065
Boundary for River Rch & Prof#=UNT060 IN GIBB,Reach-1         , 7
Up Type= 0
Dn Type= 3
Dn Slope=0.0065
DSS Import GetInterval= 0
DSS Import GetPeak= 0
DSS Import FillOption= 0

--- UNT060 IN GIBB.g01 (geometry) ---

Geom Title=Existing Conditions
Program Version=4.10

River Reach=UNT060 IN GIBB  ,Reach-1
Reach XY= 30
      3654918.16     10206380.35      3654696.15     10206274.17
       3654539.9     10206140.32      3654535.74     10206078.34
      3654478.97     10206035.63      3654491.99     10205977.82
      3654418.03     10205951.26      3654382.76     10205982.23
      3654342.73     10205953.24       3654321.2     10205821.99
      3654288.56     10205792.82      3654224.67     10205803.24
      3654155.23     10205731.02      3654263.56     10205557.41
      3654261.48     10205475.46      3654198.98     10205403.24
      3654291.34     10205344.21      3654344.12     10205251.16
      3654268.42     10205177.55      3654274.67     10205109.49
      3654162.87      10204933.8      3654124.67     10204922.68
      3654062.17     10204969.21      3653989.26     10204923.38
      3654077.45     10204847.68      3654132.31     10204690.74
      3654078.14     10204526.16      3654005.92     10204506.02
      3654030.92     10204350.46       3653956.4     10204246.82

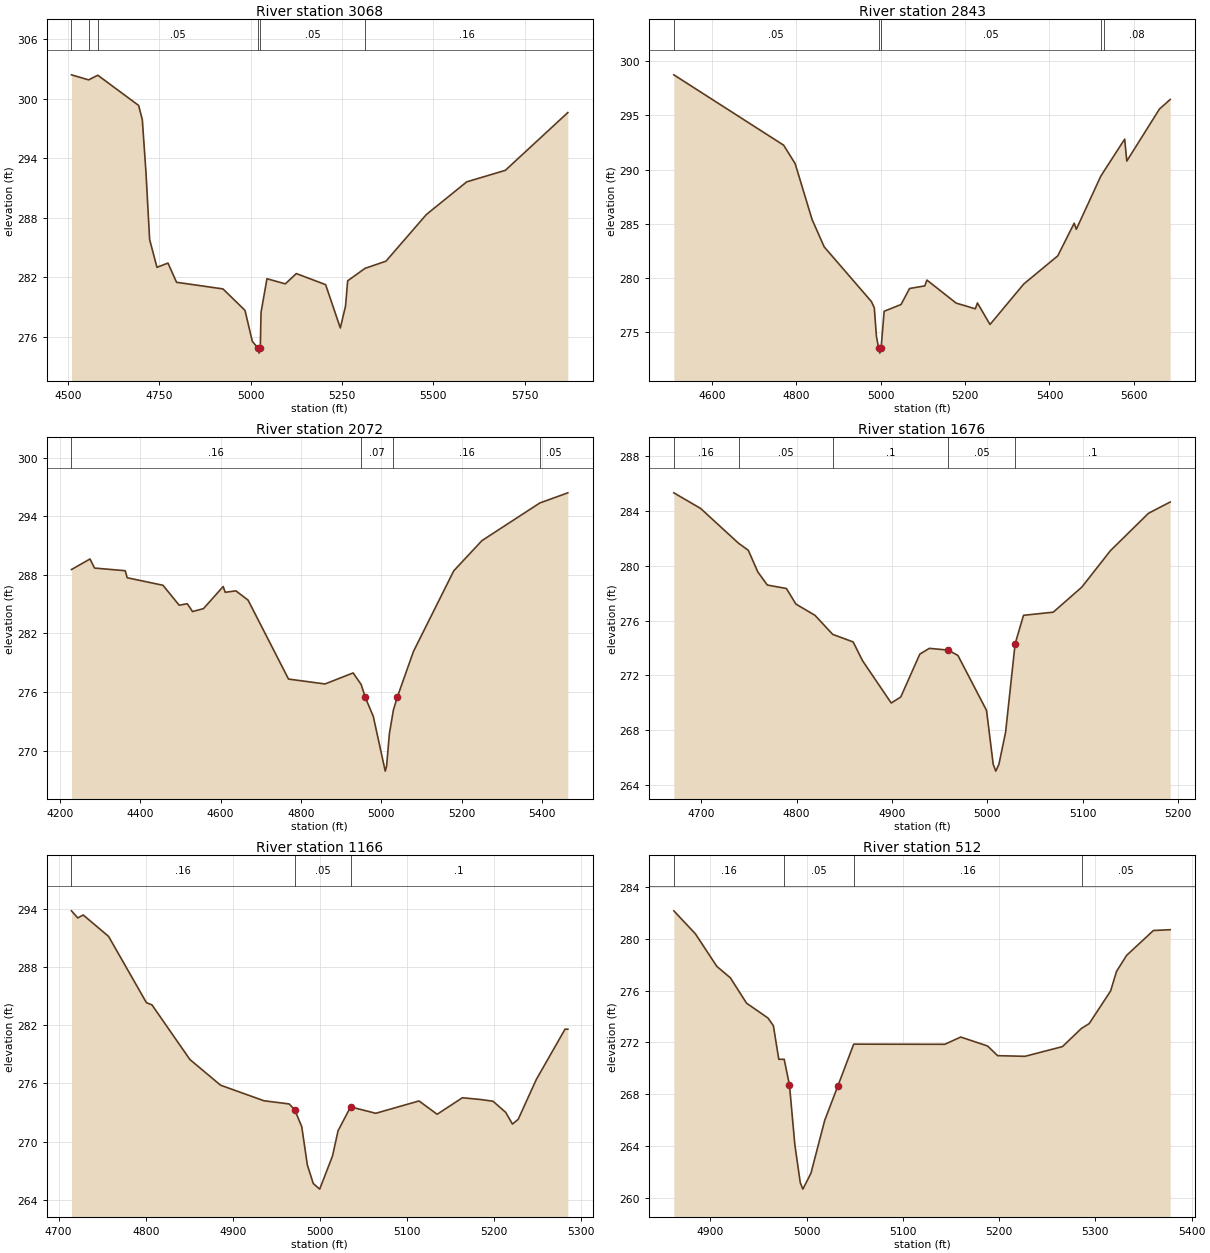
Type RM Length L Ch R = 1 ,3068    ,225,225,225
BEGIN DESCRIPTION:
UNT060 IN GIBB 6.0
END DESCRIPTION:
XS GIS Cut Line= 3
      3655225.26     10206251.95      3654443.96     10206319.66
       3654392.1     10206891.69
#Sta/Elev= 30
  4509.8  302.42  4556.8  301.91  4581.8  302.38  4693.6  299.33  4703.7  297.89
  4713.7  292.58  4723.7   285.8  4743.8  282.99  4773.9  283.42  4797.4  281.48
  4924.5  280.81  4984.7  278.65  5004.8  275.52  5020.6  274.83  5023.4  274.33
  5026.6  274.83  5028.7  278.46  5044.9  281.84  5095.1  281.32  5125.2  282.36
  5205.5  281.24  5245.7  276.87  5259.9  279.07  5265.8  281.63  5313.5  282.89
  5370.6  283.61  5481.2  288.32  5591.8  291.62  5697.4  292.78  5868.4  298.61
#Mann= 6 ,-1 , 0
  4509.8     .05       0  4556.8     .16       0  4581.8     .05       0
  5020.6     .04       0  5026.6     .05       0  5313.5     .16       0
Bank Sta=5020.6,5026.6
XS Rating Curve= 0 ,0
Exp/Cntr=0.3,0.1

Type RM Length L Ch R = 1 ,2843    ,771,771,771
BEGIN DESCRIPTION:
UNT060 IN GIBB 5.0
END DESCRIPTION:
XS GIS Cut Line= 3
      3655048.14     10206111.33      3654678.33     10206147.79
      3653876.69     10206215.46
#Sta/Elev= 30
  4509.9  298.76  4770.1  292.25  4797.3  290.55  4837.5  285.37  4866.2  282.84
  4978.1  277.78  4984.9   277.2    4990  274.55  4995.1  273.51  4997.9  273.01
  5001.1  273.51  5008.2  276.88  5048.3  277.51  5068.4  278.99  5104.6  279.23
  5109.6  279.77  5178.8  277.64  5224.3  277.11  5229.3  277.65  5259.1  275.66
  5338.9   279.4  5419.6  282.01  5458.5  285.03  5463.6  284.47  5521.3  289.36
  5529.2  289.85  5578.2  292.81  5583.2  290.78  5660.5  295.59    5686  296.48
#Mann= 5 ,-1 , 0
  4509.9     .05       0  4995.1     .04       0  5001.1     .05       0
  5521.3     .16       0  5529.2     .08       0
Bank Sta=4995.1,5001.1
XS Rating Curve= 0 ,0
Exp/Cntr=0.3,0.1

Type RM Length L Ch R = 1 ,2072    ,396,396,396
BEGIN DESCRIPTION:
UNT060 IN GIBB 4.0
END DESCRIPTION:
XS GIS Cut Line= 3
      3654917.88      10205783.2      3654308.01      10205708.1
      3653688.71     10205731.12
#Sta/Elev= 30
  4229.4  288.54  4275.5  289.62  4286.8  288.69    4363  288.42    4368   287.7
  4456.9  286.93  4497.2  284.89  4517.3  285.04  4530.5  284.24  4557.6  284.54
  4606.6   286.8  4611.7  286.21  4638.2  286.36  4668.5  285.41  4769.1  277.33
  4859.8  276.83  4929.8  277.96  4949.8  276.77  4959.9  275.46  4979.9  273.51
  5009.6  267.91  5012.9  268.41  5019.9  271.74  5029.9  274.17  5039.9  275.52
  5079.9  280.17    5180  288.41  5250.1   291.5  5393.9  295.35  5463.6  296.39
#Mann= 4 ,-1 , 0
  4229.4     .16       0  4949.8     .07       0  5029.9     .16       0
  5393.9     .05       0
Bank Sta=4959.9,5039.9
XS Rating Curve= 0 ,0
Exp/Cntr=0.3,0.1

Type RM Length L Ch R = 1 ,1676    ,510,510,510
BEGIN DESCRIPTION:
UNT060 IN GIBB 3.0
END DESCRIPTION:
XS GIS Cut Line= 3
      3654530.18     10205396.56      3654159.36     10205398.53
      3654009.38     10205398.53
#Sta/Elev= 30
  4671.2  285.32  4699.3  284.18  4739.1  281.64  4749.3  281.13  4759.3  279.55
  4769.3  278.59  4789.3  278.34  4799.3   277.2  4819.3  276.38  4837.9  274.99
  4859.3  274.44  4869.3  273.06  4899.3  269.98  4909.3  270.42  4929.3  273.55
  4939.3  273.97  4959.3  273.84  4969.3  273.45  4999.3  269.44  5006.3  265.51
    5009  265.01  5012.3  265.51  5019.3  267.85  5029.3   274.3  5038.1  276.38
  5069.3  276.61  5099.3  278.44  5129.3   281.1  5169.3  283.83    5192  284.65
#Mann= 5 ,-1 , 0
  4671.2     .16       0  4739.1     .05       0  4837.9      .1       0
  4959.3     .05       0  5029.3      .1       0
Bank Sta=4959.3,5029.3
XS Rating Curve= 0 ,0
Exp/Cntr=0.3,0.1

Type RM Length L Ch R = 1 ,1166    ,654,654,654
BEGIN DESCRIPTION:
UNT060 IN GIBB 2.0
END DESCRIPTION:
XS GIS Cut Line= 3
      3654442.08     10204841.66      3654266.13      10204976.5
      3653992.08     10205191.66
#Sta/Elev= 30
  4714.7  293.78  4721.9  293.05  4728.2  293.35  4757.3  291.15  4800.8  284.32
  4807.1   284.1  4850.7  278.47    4886  275.82  4935.8  274.22  4964.8  273.89
  4971.1  273.29  4979.2  271.55  4985.6  267.62  4992.4   265.7  4999.8  265.12
  5014.5  268.53  5020.9  271.13  5035.3  273.59  5064.2  272.93  5113.9   274.2
  5134.7  272.83  5163.7  274.53  5184.5  274.35  5198.9  274.17  5213.4  273.03
  5221.2  271.82  5227.8  272.31  5248.6  276.41  5281.6  281.59  5284.8  281.59
#Mann= 3 , 0 , 0
  4714.7     .16       0  4971.1     .05       0  5035.3      .1       0
Bank Sta=4971.1,5035.3
XS Rating Curve= 0 ,0
Exp/Cntr=0.3,0.1

Type RM Length L Ch R = 1 ,512     ,0,0,0
BEGIN DESCRIPTION:
UNT060 IN GIBB 1.0
END DESCRIPTION:
XS GIS Cut Line= 3
      3654242.11     10204591.64      3654142.11     10204641.64
      3653782.44     10204824.96
#Sta/Elev= 30
  4862.2  282.18  4884.6   280.4  4906.9  277.88  4920.9     277  4937.7  275.04
    4960  273.89  4965.6  273.29  4971.2   270.7  4976.8   270.7  4982.3   268.7
  4987.9  264.08  4993.5  261.16  4996.2  260.66  5004.6  261.89  5018.9  265.98
  5032.4  268.61    5049  271.87  5143.6  271.86  5160.2  272.42    5188  271.73
  5198.5  270.98  5226.9  270.93  5265.8  271.68  5285.6  273.09  5293.6  273.46
  5315.8  275.98    5322   277.5  5332.5  278.74  5360.3  280.66  5377.7  280.72
#Mann= 4 ,-1 , 0
  4862.2     .16       0  4976.8     .05       0    5049     .16       0
  5285.6     .05       0
Bank Sta=4982.3,5032.4
XS Rating Curve= 0 ,0
Exp/Cntr=0.3,0.1

Chan Stop Cuts=-1
Use User Specified Reach Order=0
Composite Channel Slope=5