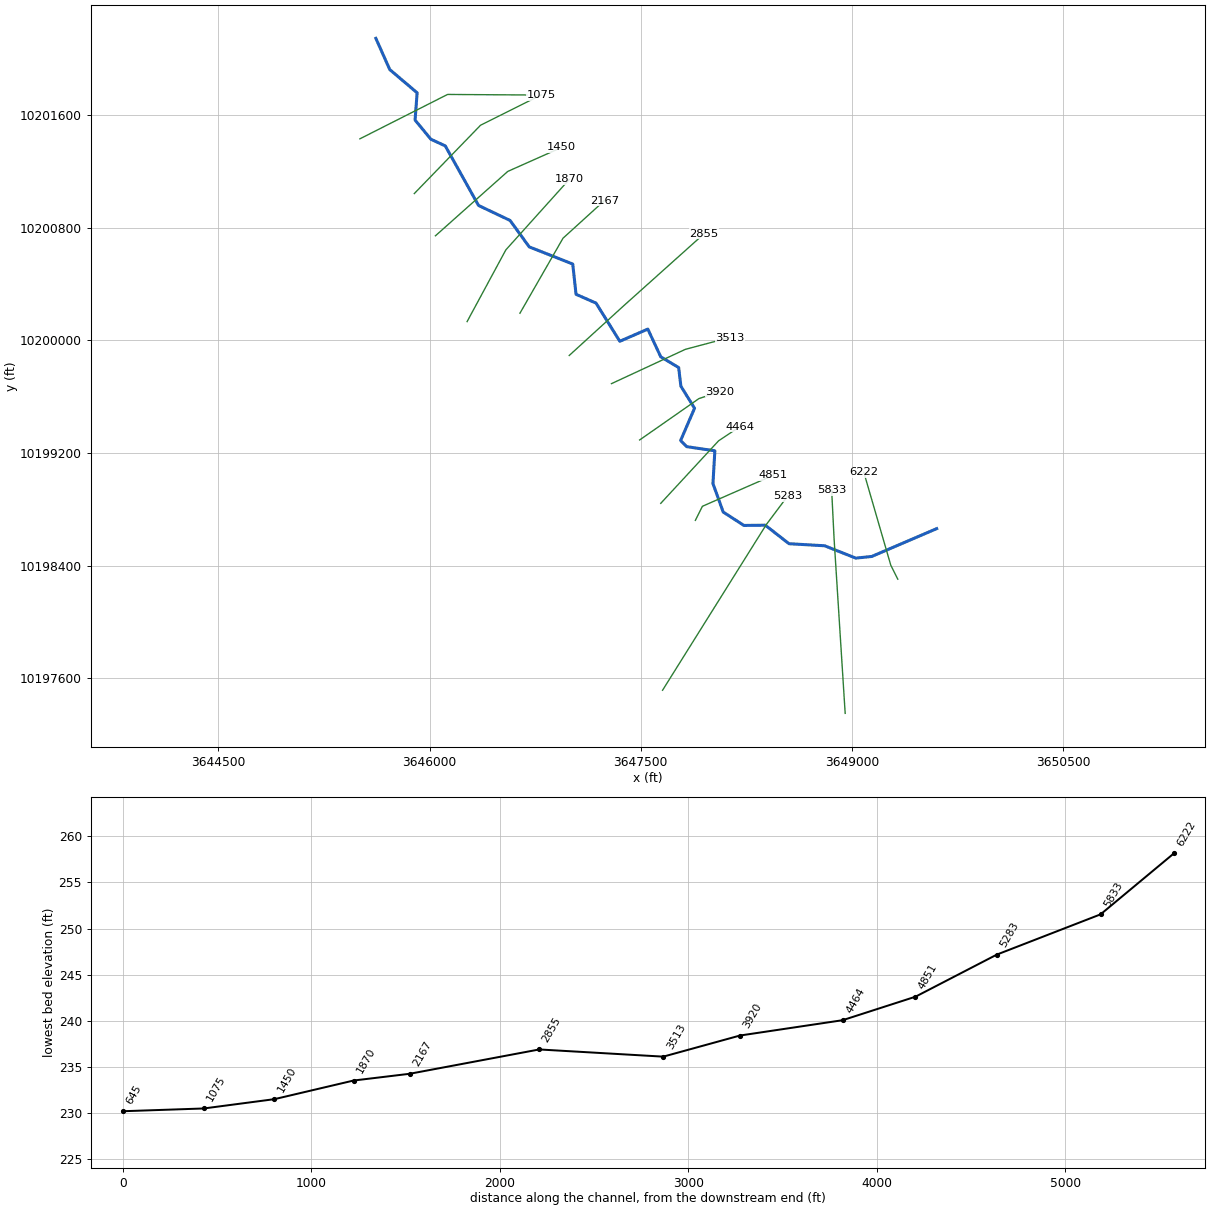
--- UNT062 IN GIBB.prj (project) ---

Proj Title=UNT062 IN GIBB Base Level Engineering
Current Plan=p01
Default Exp/Contr=0.3,0.1
English Units
Geom File=g01
Flow File=f01
Plan File=p01
BEGIN DESCRIPTION:
UNT062 IN GIBB
END DESCRIPTION:

--- UNT062 IN GIBB.p01 (plan) ---

Plan Title=Multiple Run
Short Identifier=Multiple
Geom File=g01
Flow File=f01
Subcritical Flow
K Sum by GR= 0
Std Step Tol= 0.01
Critical Tol= 0.01
Num of Std Step Trials= 20
Max Error Tol= 0.3
Flow Tol Ratio= 0.001
Split Flow NTrial= 30
Split Flow Tol= 0.02
Split Flow Ratio= 0.02
Log Output Level= 0
Friction Slope Method= 1
Unsteady Friction Slope Method= 2
Unsteady Bridges Friction Slope Method= 1
Parabolic Critical Depth
Global Vel Dist=  1 , 1 , 1
Global Log Level= 0
CheckData=True
Encroach Param= -1, 0, 0, 0
BEGIN DESCRIPTION:
Multiple Run
END DESCRIPTION:

--- UNT062 IN GIBB.f01 (steady flow) ---

Flow Title=Multiple
Number of Profiles=7
Profile Names=10-year,25-year,50-year,1pct_min,100-year,1pct_plu,500-year
River Rch & RM= UNT062 IN GIBB,Reach-1,6222
     699     959    1176    1058    1431    1936    2123
River Rch & RM= UNT062 IN GIBB,Reach-1,5833
    1178    1668    2089    1917    2593    3506    4001
River Rch & RM= UNT062 IN GIBB,Reach-1,5283
    1203    1692    2110    1925    2604    3521    3974
Boundary for River Rch & Prof#=UNT062 IN GIBB,Reach-1,1
Up Type=0
Dn Type=3
Dn Slope=0.005
Boundary for River Rch & Prof#=UNT062 IN GIBB,Reach-1,2
Up Type=0
Dn Type=3
Dn Slope=0.005
Boundary for River Rch & Prof#=UNT062 IN GIBB,Reach-1,3
Up Type=0
Dn Type=3
Dn Slope=0.005
Boundary for River Rch & Prof#=UNT062 IN GIBB,Reach-1,4
Up Type=0
Dn Type=3
Dn Slope=0.005
Boundary for River Rch & Prof#=UNT062 IN GIBB,Reach-1,5
Up Type=0
Dn Type=3
Dn Slope=0.005
Boundary for River Rch & Prof#=UNT062 IN GIBB,Reach-1,6
Up Type=0
Dn Type=3
Dn Slope=0.005
Boundary for River Rch & Prof#=UNT062 IN GIBB,Reach-1,7
Up Type=0
Dn Type=3
Dn Slope=0.005

--- UNT062 IN GIBB.g01 (geometry) ---

Geom Title=Existing Conditions

River Reach=UNT062 IN GIBB,Reach-1
Reach XY= 30
      3649601.59     10198662.16      3649140.62     10198464.49
      3649026.88     10198452.69      3648805.94     10198540.40
      3648552.77     10198555.03      3648384.26     10198686.57
      3648232.64     10198684.80      3648085.58     10198779.98
      3648012.77     10198982.29      3648026.33     10199214.77
      3647827.11     10199244.13      3647783.23     10199287.80
      3647882.04     10199517.10      3647785.07     10199673.60
      3647769.28     10199805.77      3647642.18     10199882.13
      3647550.26     10200079.14      3647351.33     10199992.58
      3647182.49     10200263.70      3647040.56     10200326.20
      3647017.13     10200541.05      3646708.10     10200663.01
      3646572.25     10200850.51      3646348.17     10200957.03
      3646112.06     10201379.95      3646009.97     10201427.17
      3645897.47     10201563.28      3645912.06     10201757.03
      3645717.61     10201922.31      3645619.00     10202143.84

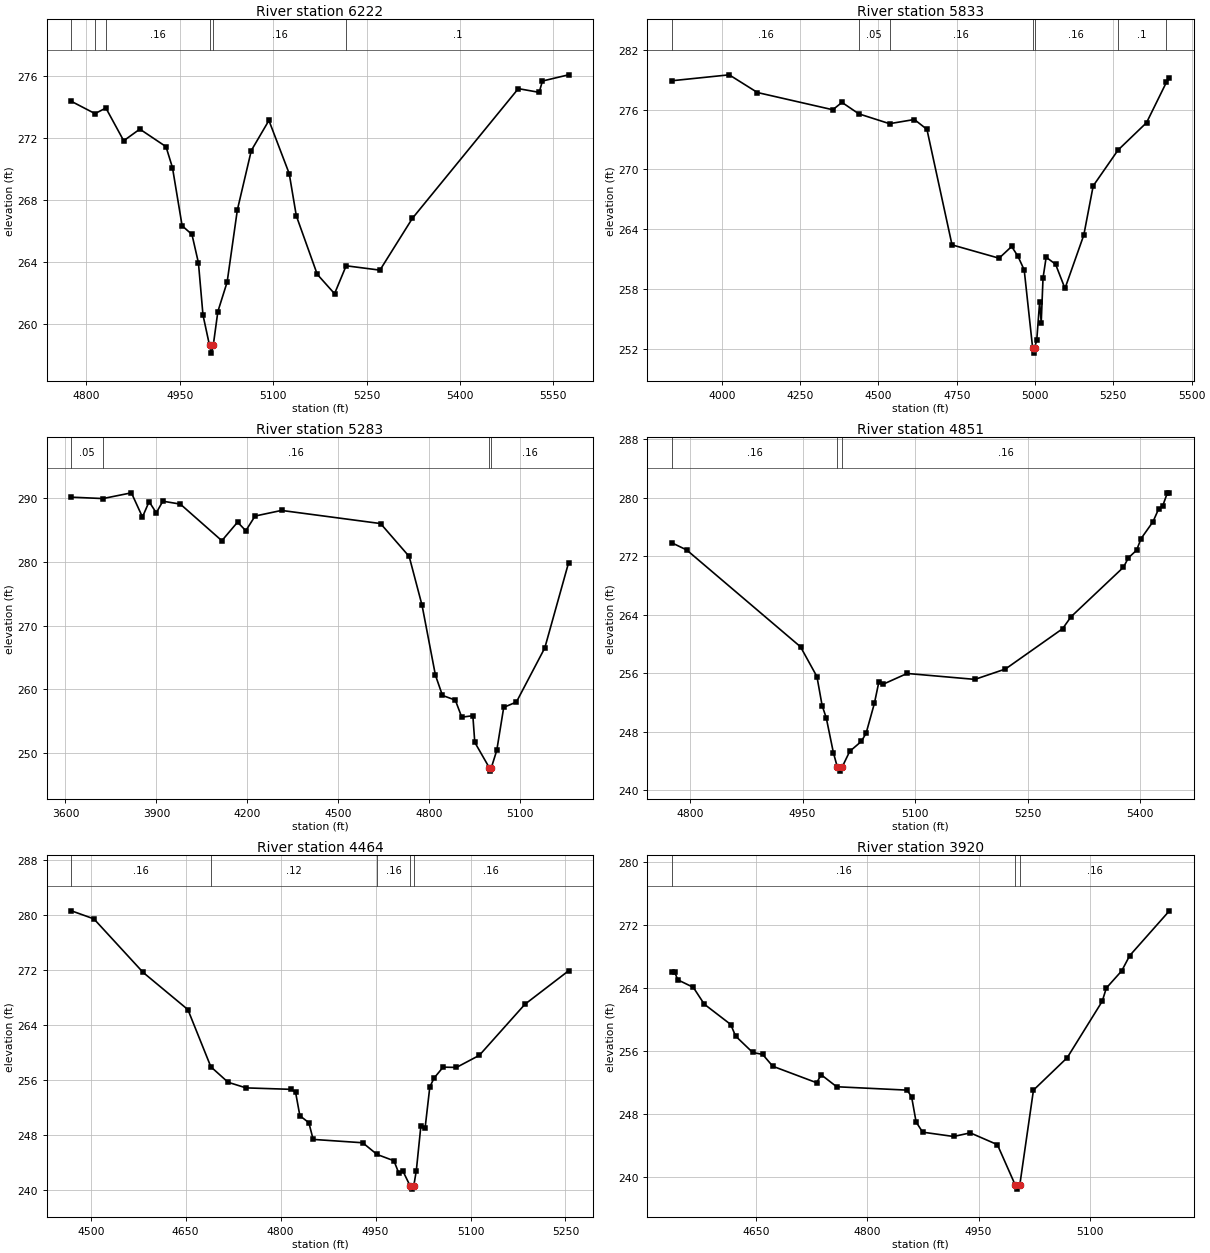
Type RM Length L Ch R = 1,6222,389,389,389
BEGIN DESCRIPTION:
UNT062 IN GIBB 14.0
END DESCRIPTION:
XS GIS Cut Line= 3
      3649325.43     10198303.11      3649275.44     10198403.10
      3649084.15     10199062.42
#Sta/Elev= 30
  4776.0  274.38  4813.9  273.59  4831.4  273.95  4860.0  271.84  4885.9  272.59
  4927.9  271.46  4938.3  270.11  4953.8  266.36  4969.6  265.80  4980.0  263.97
  4987.3  260.61  4997.8  258.65  5000.6  258.15  5003.8  258.65  5011.2  260.83
  5026.1  262.73  5042.5  267.38  5064.9  271.21  5093.2  273.15  5125.8  269.72
  5137.2  267.00  5170.8  263.23  5198.6  261.98  5217.2  263.78  5271.5  263.50
  5323.6  266.84  5493.7  275.20  5527.2  274.96  5532.4  275.69  5574.3  276.09
#Mann=6,-1,0
  4776.0    0.16       0  4813.9    0.05       0  4831.4    0.16       0
  4997.8    0.07       0  5003.8    0.16       0  5217.2     0.1       0
Bank Sta=4997.8,5003.8
Exp/Cntr=0.3,0.1

Type RM Length L Ch R = 1,5833,550,550,550
BEGIN DESCRIPTION:
UNT062 IN GIBB 13.0
END DESCRIPTION:
XS GIS Cut Line= 3
      3648951.72     10197350.22      3648873.04     10198589.16
      3648855.84     10198934.59
#Sta/Elev= 30
  3841.6  278.92  4023.4  279.51  4113.6  277.73  4354.1  276.00  4383.4  276.74
  4437.1  275.59  4535.3  274.60  4614.6  275.02  4654.7  274.03  4734.8  262.42
  4885.1  261.08  4925.2  262.26  4945.2  261.28  4965.3  259.90  4992.3  252.04
  4995.1  251.54  4998.3  252.04  5005.4  252.87  5014.6  256.69  5019.6  254.59
  5025.4  259.09  5035.4  261.18  5065.5  260.47  5095.5  258.04  5155.6  263.41
  5185.6  268.35  5265.0  271.95  5355.9  274.70  5419.2  278.75  5428.9  279.20
#Mann=7,-1,0
  3841.6    0.16       0  4437.1    0.05       0  4535.3    0.16       0
  4992.3    0.07       0  4998.3    0.16       0  5265.0     0.1       0
  5419.2    0.16       0
Bank Sta=4992.3,4998.3
Exp/Cntr=0.3,0.1

Type RM Length L Ch R = 1,5283,432,432,432
BEGIN DESCRIPTION:
UNT062 IN GIBB 12.0
END DESCRIPTION:
XS GIS Cut Line= 3
      3647654.96     10197514.53      3648392.11     10198691.64
      3648542.12     10198891.66
#Sta/Elev= 30
  3619.6  290.14  3723.6  289.92  3817.4  290.82  3853.9  287.02  3875.8  289.44
  3899.4  287.68  3921.1  289.51  3978.8  289.05  4115.6  283.31  4167.4  286.22
  4194.6  284.88  4225.2  287.18  4312.3  288.06  4638.9  286.00  4733.2  280.84
  4775.7  273.17  4819.7  262.23  4842.9  259.05  4885.3  258.32  4906.5  255.64
  4943.1  255.87  4949.5  251.69  4997.8  247.68  5000.6  247.18  5003.8  247.68
  5022.0  250.44  5044.9  257.18  5086.6  258.01  5180.3  266.50  5258.5  279.82
#Mann=4,-1,0
  3619.6    0.05       0  3723.6    0.16       0  4997.8    0.07       0
  5003.8    0.16       0
Bank Sta=4997.8,5003.8
Exp/Cntr=0.3,0.1

Type RM Length L Ch R = 1,4851,387,387,387
BEGIN DESCRIPTION:
UNT062 IN GIBB 11.0
END DESCRIPTION:
XS GIS Cut Line= 3
      3647887.95     10198720.84      3647937.94     10198820.81
      3648442.12     10199041.65
#Sta/Elev= 30
  4776.4  273.81  4795.5  272.87  4947.2  259.62  4969.1  255.54  4976.0  251.58
  4981.5  249.90  4991.0  245.14  4996.4  243.11  4999.2  242.61  5002.4  243.11
  5012.8  245.32  5028.3  246.68  5034.6  247.80  5045.6  251.87  5051.6  254.82
  5057.1  254.49  5089.2  255.97  5179.5  255.16  5220.2  256.58  5296.3  262.09
  5307.6  263.73  5377.4  270.50  5384.0  271.79  5394.9  272.83  5400.8  274.41
  5416.7  276.72  5424.2  278.46  5429.6  278.86  5435.9  280.68  5438.6  280.68
#Mann=3,-1,0
  4776.4    0.16       0  4996.4    0.07       0  5002.4    0.16       0
Bank Sta=4996.4,5002.4
Exp/Cntr=0.3,0.1

Type RM Length L Ch R = 1,4464,544,544,544
BEGIN DESCRIPTION:
UNT062 IN GIBB 10.0
END DESCRIPTION:
XS GIS Cut Line= 3
      3647642.07     10198841.61      3648052.84     10199285.79
      3648202.86     10199385.80
#Sta/Elev= 30
  4469.5  280.58  4505.0  279.41  4582.7  271.62  4653.5  266.20  4689.8  257.87
  4717.0  255.62  4745.4  254.80  4816.3  254.59  4823.6  254.19  4830.4  250.75
  4844.6  249.73  4851.4  247.30  4929.7  246.81  4952.3  245.11  4979.0  244.19
  4986.4  242.46  4993.2  242.69  5004.4  240.56  5007.1  240.06  5010.4  240.56
  5014.4  242.77  5021.5  249.20  5028.3  249.00  5035.7  254.94  5042.5  256.24
  5056.7  257.82  5077.8  257.78  5113.9  259.54  5186.0  266.98  5254.8  271.84
#Mann=5,-1,0
  4469.5    0.16       0  4689.8    0.12       0  4952.3    0.16       0
  5004.4    0.07       0  5010.4    0.16       0
Bank Sta=5004.4,5010.4
Exp/Cntr=0.3,0.1

Type RM Length L Ch R = 1,3920,407,407,407
BEGIN DESCRIPTION:
UNT062 IN GIBB 9.0
END DESCRIPTION:
XS GIS Cut Line= 3
      3647492.08     10199291.63      3647912.94     10199585.39
      3648062.98     10199635.41
#Sta/Elev= 30
  4536.4  266.05  4539.5  266.05  4543.8  265.04  4564.8  264.08  4579.6  261.94
  4615.4  259.35  4621.8  257.89  4645.0  255.79  4658.4  255.55  4672.1  254.04
  4731.4  251.94  4737.5  252.96  4758.4  251.43  4853.5  251.00  4859.6  250.16
  4865.7  246.95  4874.5  245.65  4916.3  245.10  4938.9  245.56  4975.5  244.06
  4999.7  238.90  5002.4  238.40  5005.7  238.90  5024.2  251.00  5069.8  255.13
  5117.1  262.31  5122.6  263.99  5143.4  266.18  5154.2  268.12  5207.8  273.82
#Mann=3,-1,0
  4536.4    0.16       0  4999.7    0.07       0  5005.7    0.16       0
Bank Sta=4999.7,5005.7
Exp/Cntr=0.3,0.1

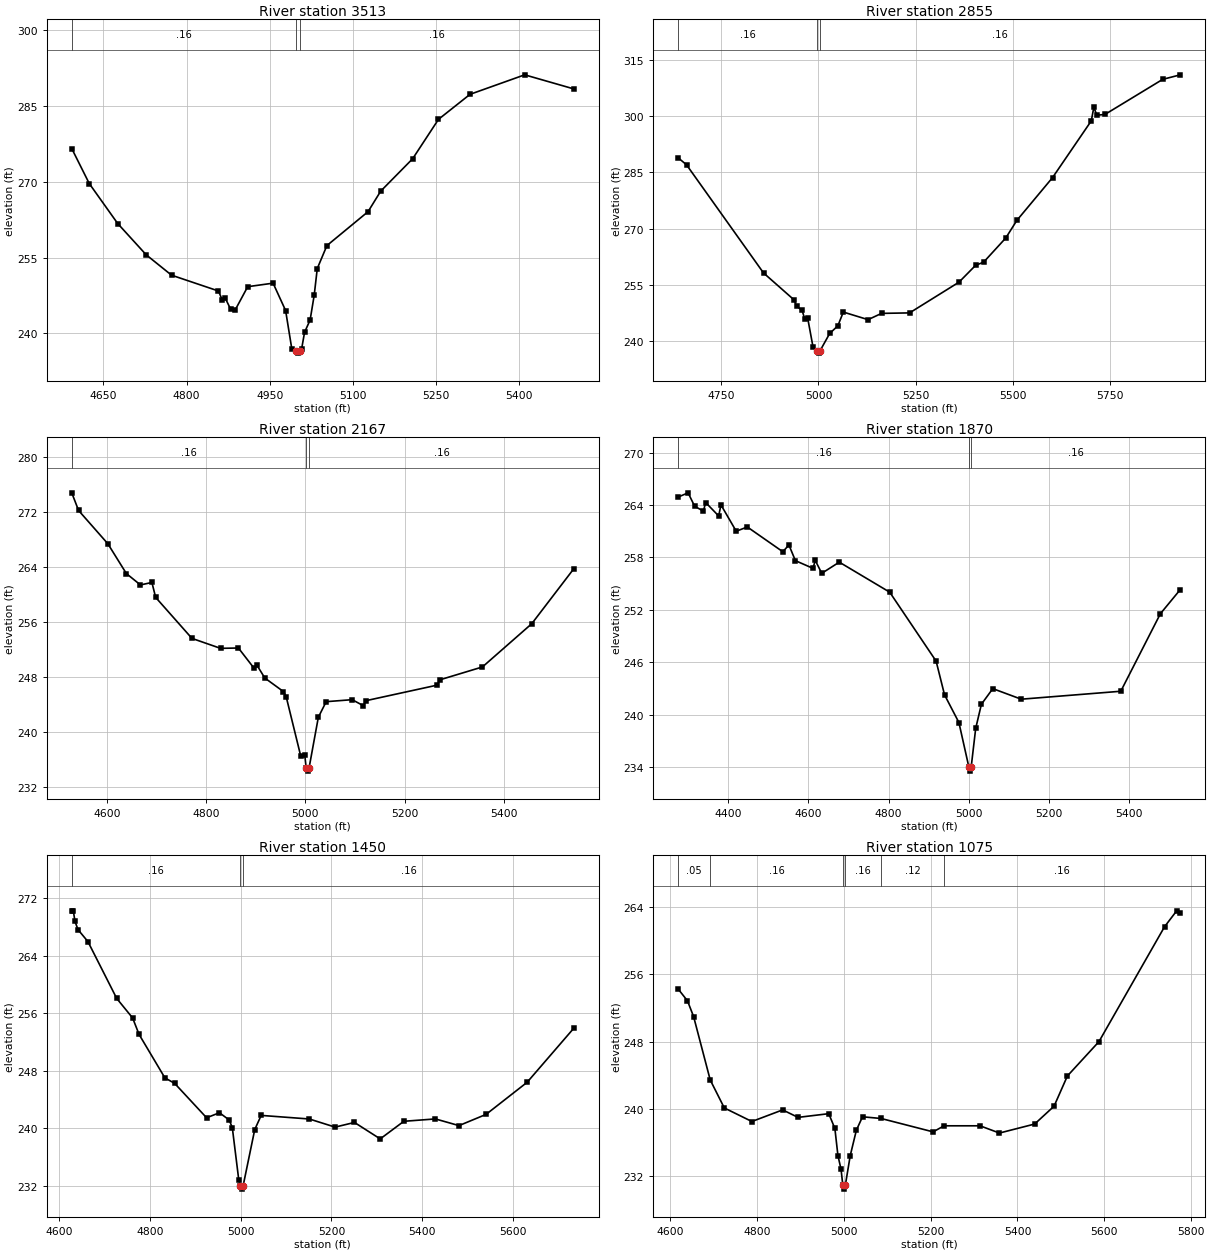
Type RM Length L Ch R = 1,3513,658,658,658
BEGIN DESCRIPTION:
UNT062 IN GIBB 8.0
END DESCRIPTION:
XS GIS Cut Line= 3
      3647292.14     10199691.66      3647817.11     10199935.39
      3648133.16     10200019.31
#Sta/Elev= 30
  4593.0  276.60  4624.6  269.67  4675.9  261.76  4727.2  255.58  4773.0  251.54
  4857.6  248.41  4864.6  246.62  4870.1  246.95  4879.6  244.81  4887.5  244.59
  4910.4  249.26  4956.2  249.96  4978.8  244.54  4990.1  236.86  4997.9  236.61
  5000.7  236.11  5003.9  236.61  5007.5  236.83  5013.0  240.24  5023.0  242.67
  5030.4  247.59  5035.9  252.85  5053.3  257.40  5127.5  264.11  5150.4  268.18
  5208.0  274.59  5254.6  282.39  5311.5  287.34  5410.1  291.20  5498.8  288.41
#Mann=3,-1,0
  4593.0    0.16       0  4997.9    0.07       0  5003.9    0.16       0
Bank Sta=4997.9,5003.9
Exp/Cntr=0.3,0.1

Type RM Length L Ch R = 1,2855,688,688,688
BEGIN DESCRIPTION:
UNT062 IN GIBB 6.0
END DESCRIPTION:
XS GIS Cut Line= 3
      3646992.09     10199891.63      3647379.64     10200245.26
      3647950.60     10200756.89
#Sta/Elev= 30
  4639.4  288.87  4660.7  287.02  4858.7  258.24  4937.0  251.09  4943.8  249.43
  4958.0  248.24  4964.7  246.02  4972.2  246.29  4986.3  238.39  4997.5  237.39
  5000.3  236.89  5003.5  237.39  5028.9  242.12  5049.9  244.16  5064.0  247.82
  5127.6  245.80  5162.3  247.47  5234.4  247.60  5361.5  255.78  5404.1  260.25
  5425.0  261.12  5481.8  267.54  5510.3  272.22  5602.2  283.63  5701.7  298.71
  5708.4  302.37  5715.9  300.22  5736.8  300.42  5885.5  309.77  5930.7  310.97
#Mann=3,-1,0
  4639.4    0.16       0  4997.5    0.07       0  5003.5    0.16       0
Bank Sta=4997.5,5003.5
Exp/Cntr=0.3,0.1

Type RM Length L Ch R = 1,2167,297,297,297
BEGIN DESCRIPTION:
UNT062 IN GIBB 5.0
END DESCRIPTION:
XS GIS Cut Line= 3
      3646642.08     10200191.60      3646947.95     10200724.38
      3647242.13     10200991.66
#Sta/Elev= 30
  4529.2  274.80  4542.9  272.23  4601.9  267.38  4639.2  263.04  4667.6  261.38
  4690.7  261.74  4698.2  259.57  4771.4  253.59  4829.0  252.14  4865.0  252.19
  4896.6  249.24  4902.4  249.68  4918.2  247.82  4955.6  245.85  4961.4  245.06
  4990.5  236.48  4998.7  236.62  5001.5  234.75  5004.3  234.25  5007.5  234.75
  5026.1  242.10  5041.9  244.37  5094.3  244.66  5116.6  243.79  5122.4  244.52
  5264.9  246.77  5271.7  247.57  5356.8  249.43  5456.2  255.73  5541.0  263.75
#Mann=3,-1,0
  4529.2    0.16       0  5001.5    0.07       0  5007.5    0.16       0
Bank Sta=5001.5,5007.5
Exp/Cntr=0.3,0.1

Type RM Length L Ch R = 1,1870,420,420,420
BEGIN DESCRIPTION:
UNT062 IN GIBB 4.0
END DESCRIPTION:
XS GIS Cut Line= 3
      3646266.89     10200132.20      3646542.11     10200641.64
      3646992.10     10201141.63
#Sta/Elev= 30
  4275.8  264.92  4300.4  265.40  4316.6  263.87  4338.5  263.30  4344.2  264.29
  4376.6  262.75  4382.3  264.02  4420.4  261.00  4448.0  261.49  4536.6  258.65
  4551.7  259.43  4567.9  257.63  4611.7  256.75  4617.4  257.66  4633.6  256.18
  4677.3  257.46  4803.0  254.02  4918.7  246.12  4939.7  242.26  4975.5  239.09
  5000.2  234.02  5002.9  233.52  5006.2  234.02  5017.4  238.42  5031.6  241.18
  5060.0  242.97  5131.0  241.76  5379.1  242.67  5477.8  251.55  5527.5  254.32
#Mann=3,-1,0
  4275.8    0.16       0  5000.2    0.07       0  5006.2    0.16       0
Bank Sta=5000.2,5006.2
Exp/Cntr=0.3,0.1

Type RM Length L Ch R = 1,1450,375,375,375
BEGIN DESCRIPTION:
UNT062 IN GIBB 3.0
END DESCRIPTION:
XS GIS Cut Line= 3
      3646042.09     10200741.62      3646555.33     10201198.54
      3646938.95     10201369.61
#Sta/Elev= 30
  4627.5  270.23  4630.9  270.23  4634.6  268.75  4641.3  267.61  4663.1  265.95
  4726.6  258.04  4761.7  255.32  4775.9  253.03  4832.8  246.99  4854.5  246.21
  4924.8  241.43  4953.2  242.13  4974.9  241.11  4981.6  240.02  4995.8  232.77
  4999.5  232.00  5002.3  231.50  5005.5  232.00  5031.0  239.79  5045.2  241.76
  5151.4  241.26  5208.2  240.13  5250.9  240.78  5307.7  238.49  5359.8  240.94
  5429.4  241.27  5481.4  240.34  5541.1  241.90  5631.7  246.37  5734.7  253.90
#Mann=3,-1,0
  4627.5    0.16       0  4999.5    0.07       0  5005.5    0.16       0
Bank Sta=4999.5,5005.5
Exp/Cntr=0.3,0.1

Type RM Length L Ch R = 1,1075,430,430,430
BEGIN DESCRIPTION:
UNT062 IN GIBB 2.0
END DESCRIPTION:
XS GIS Cut Line= 3
      3645892.11     10201041.65      3646362.53     10201526.85
      3646792.11     10201741.65
#Sta/Elev= 30
  4618.9  254.24  4640.1  252.86  4654.3  250.98  4692.5  243.46  4725.0  240.13
  4788.5  238.52  4859.3  239.90  4894.8  239.01  4965.5  239.45  4979.6  237.69
  4986.6  234.48  4993.8  232.84  4997.8  230.99  5000.5  230.49  5003.8  230.99
  5014.9  234.46  5029.1  237.49  5043.2  239.08  5085.9  238.88  5205.8  237.29
  5231.0  238.01  5313.8  238.01  5358.5  237.15  5439.6  238.22  5484.3  240.34
  5515.0  243.93  5587.7  248.01  5738.7  261.65  5766.6  263.54  5775.0  263.26
#Mann=6,-1,0
  4618.9    0.05       0  4692.5    0.16       0  4997.8    0.07       0
  5003.8    0.16       0  5085.9    0.12       0  5231.0    0.16       0
Bank Sta=4997.8,5003.8
Exp/Cntr=0.3,0.1

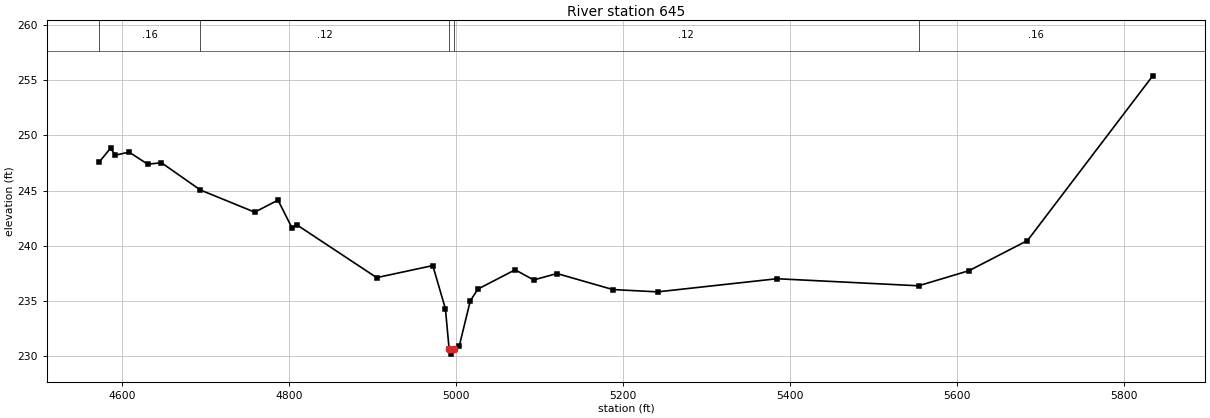
Type RM Length L Ch R = 1,645,0,0,0
BEGIN DESCRIPTION:
UNT062 IN GIBB 1.0
END DESCRIPTION:
XS GIS Cut Line= 3
      3645505.65     10201430.19      3646128.24     10201745.41
      3646692.08     10201741.64
#Sta/Elev= 30
  4573.0  247.59  4586.6  248.85  4592.2  248.21  4608.8  248.49  4631.1  247.39
  4647.5  247.53  4694.1  245.06  4759.2  243.05  4787.1  244.14  4803.7  241.65
  4809.3  241.92  4905.3  237.12  4972.5  238.21  4987.6  234.30  4992.0  230.69
  4994.7  230.19  4998.0  230.69  5004.2  230.93  5017.4  235.02  5026.5  236.08
  5071.1  237.83  5093.3  236.91  5121.2  237.49  5188.1  236.04  5241.6  235.83
  5384.7  237.02  5554.2  236.38  5614.7  237.75  5684.7  240.48  5834.7  255.40
#Mann=5,-1,0
  4573.0    0.16       0  4694.1    0.12       0  4992.0    0.07       0
  4998.0    0.12       0  5554.2    0.16       0
Bank Sta=4992,4998
Exp/Cntr=0.3,0.1

Chan Stop Cuts=-1