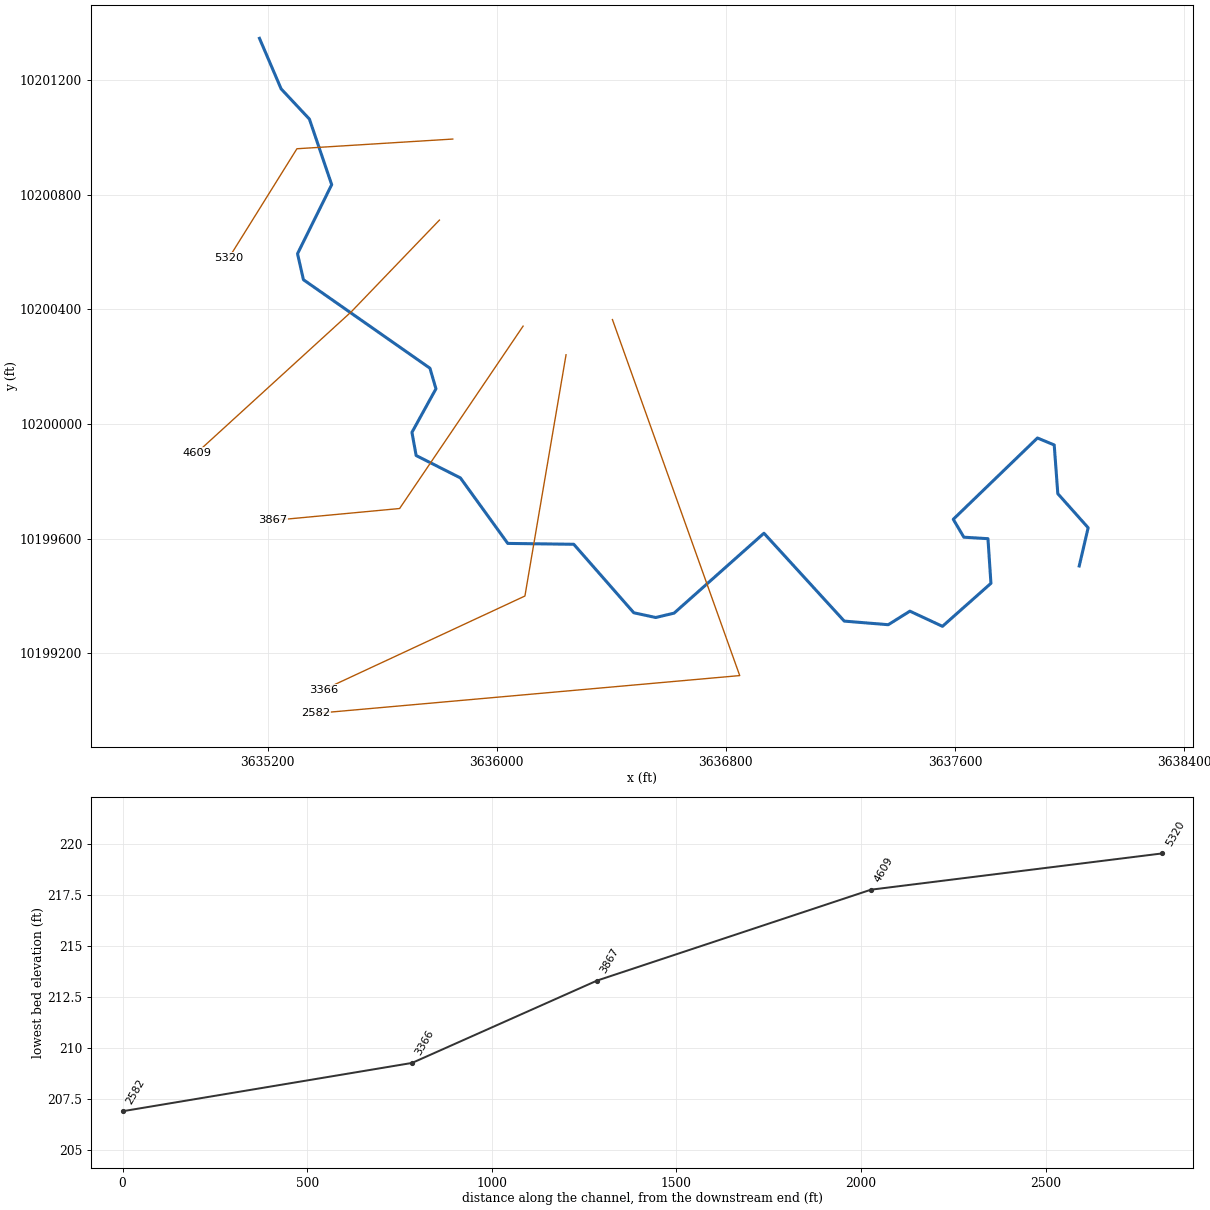
--- UNT063 IN GIBB.prj (project) ---

Proj Title=UNT063 IN GIBB Base Level Engineering
Current Plan=p01
Default Exp/Contr=0.3,0.1
English Units
Geom File=g01
Flow File=f01
Plan File=p01
Y Axis Title=Elevation
X Axis Title(PF)=Main Channel Distance
X Axis Title(XS)=Station
BEGIN DESCRIPTION:
UNT063 IN GIBB
END DESCRIPTION:
DSS Export Rating Curves= 0
DSS Export Rating Curve Sorted= 0
DSS Export Volume Flow Curves= 0
DXF OffsetX= 0
DXF OffsetY= 0
DXF ScaleX= 1
DXF ScaleY= 10

--- UNT063 IN GIBB.p01 (plan) ---

Plan Title=Multiple Run
Short Identifier=Multiple
Geom File=g01
Flow File=f01
Subcritical Flow
K Sum by GR= 0
Std Step Tol= 0.01
Critical Tol= 0.01
Num of Std Step Trials= 20
Max Error Tol= 0.3
Flow Tol Ratio= 0.001
Split Flow NTrial= 30
Split Flow Tol= 0.02
Split Flow Ratio= 0.02
Log Output Level= 0
Friction Slope Method= 1
Unsteady Friction Slope Method= 2
Unsteady Bridges Friction Slope Method= 1
Parabolic Critical Depth
Global Vel Dist=  1 , 1 , 1
Global Log Level= 0
CheckData=True
Encroach Param= -1, 0, 0, 0
BEGIN DESCRIPTION:
Multiple Run
END DESCRIPTION:

--- UNT063 IN GIBB.f01 (steady flow) ---

Flow Title=Multiple
Program Version=4.10
Number of Profiles= 7
Profile Names=10-year,25-year,50-year,1pct_min,100-year,1pct_plu,500-year
River Rch & RM=UNT063 IN GIBB,Reach-1         ,5320
     589     783     939     824    1115    1507    1574
Boundary for River Rch & Prof#=UNT063 IN GIBB,Reach-1         , 1
Up Type= 0
Dn Type= 3
Dn Slope=0.005
Boundary for River Rch & Prof#=UNT063 IN GIBB,Reach-1         , 2
Up Type= 0
Dn Type= 3
Dn Slope=0.005
Boundary for River Rch & Prof#=UNT063 IN GIBB,Reach-1         , 3
Up Type= 0
Dn Type= 3
Dn Slope=0.005
Boundary for River Rch & Prof#=UNT063 IN GIBB,Reach-1         , 4
Up Type= 0
Dn Type= 3
Dn Slope=0.005
Boundary for River Rch & Prof#=UNT063 IN GIBB,Reach-1         , 5
Up Type= 0
Dn Type= 3
Dn Slope=0.005
Boundary for River Rch & Prof#=UNT063 IN GIBB,Reach-1         , 6
Up Type= 0
Dn Type= 3
Dn Slope=0.005
Boundary for River Rch & Prof#=UNT063 IN GIBB,Reach-1         , 7
Up Type= 0
Dn Type= 3
Dn Slope=0.005
DSS Import GetInterval= 0
DSS Import GetPeak= 0
DSS Import FillOption= 0

--- UNT063 IN GIBB.g01 (geometry) ---

Geom Title=Existing Conditions
Program Version=4.10

River Reach=UNT063 IN GIBB  ,Reach-1
Reach XY= 30
      3635171.69     10201346.54      3635247.35     10201170.03
      3635346.05     10201064.59      3635423.86     10200835.61
      3635304.56     10200594.54      3635325.18     10200503.77
      3635766.88     10200194.79      3635787.89     10200122.91
      3635704.06     10199970.82      3635718.72     10199889.89
      3635873.23     10199811.77       3636038.6     10199583.03
      3636269.06       10199580.       3636478.7     10199340.85
      3636555.09     10199324.35      3636619.32     10199339.54
      3636933.13     10199618.62      3637213.51     10199311.77
      3637367.15     10199299.18      3637442.67     10199346.49
      3637556.39     10199293.54      3637725.66     10199443.71
      3637715.24     10199599.53      3637631.04     10199604.74
      3637594.15     10199667.24      3637887.99     10199951.09
      3637946.58     10199926.78      3637959.17     10199756.64
      3638065.07     10199637.72      3638033.93     10199504.28

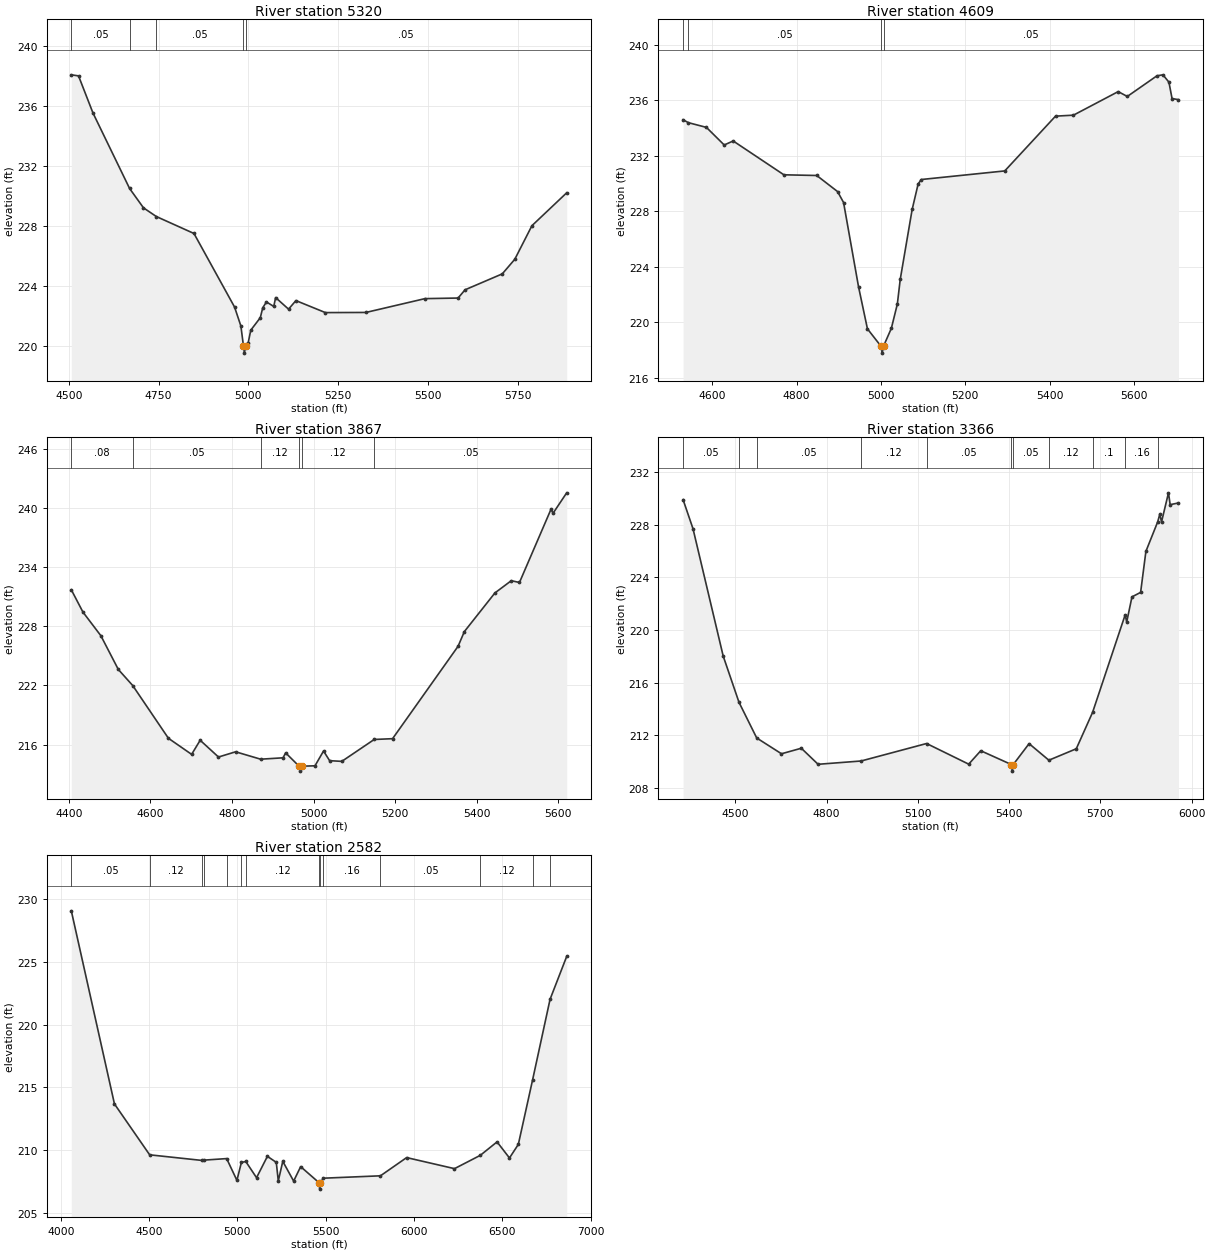
Type RM Length L Ch R = 1 ,5320    ,789,789,789
BEGIN DESCRIPTION:
UNT063 IN GIBB 9.0
END DESCRIPTION:
XS GIS Cut Line= 3
      3635846.73     10200994.91     3635302.459    10200961.055
      3635065.48    10200580.847
#Sta/Elev= 30
    4507  238.09  4527.1  238.02  4567.3  235.55  4669.3  230.52    4708  229.23
  4743.8  228.65  4848.7  227.52  4961.7  222.62  4979.3  221.36  4986.4  220.05
  4989.1  219.55  4992.4  220.05  4999.4  220.21  5006.9  221.08  5033.4  221.91
  5040.2  222.57  5050.5  222.96  5070.9  222.66  5076.1  223.25  5112.1  222.48
  5132.6  223.05  5214.7  222.25  5327.6  222.26  5491.9  223.18  5584.3  223.22
  5603.8  223.77  5707.4  224.83  5742.2   225.8    5790  228.04  5886.8  230.23
#Mann= 5 ,-1 , 0
    4507     .05       0  4669.3     .08       0  4743.8     .05       0
  4986.4     .03       0  4992.4     .05       0
Bank Sta=4986.4,4992.4
XS Rating Curve= 0 ,0
Exp/Cntr=0.3,0.1

Type RM Length L Ch R = 1 ,4609    ,742,742,742
BEGIN DESCRIPTION:
UNT063 IN GIBB 7.0
END DESCRIPTION:
XS GIS Cut Line= 3
      3635799.92     10200711.85      3635492.11     10200391.64
      3634952.66     10199899.31
#Sta/Elev= 30
  4530.8   234.6  4543.3  234.39  4586.1  234.05  4628.3  232.78  4649.6  233.07
  4769.8  230.63  4847.7  230.58  4897.1  229.42  4911.3  228.63  4946.8  222.55
  4967.9  219.52    5000  218.27  5002.8  217.77    5006  218.27  5024.6  219.56
  5038.8  221.31  5045.6  223.08  5073.9  228.13  5088.1  229.97  5095.5  230.29
  5293.5  230.91  5413.8  234.86  5456.3  234.93  5562.4  236.63    5584  236.28
  5654.3  237.77  5668.5  237.84  5682.7  237.31  5690.1  236.13  5705.3  236.05
#Mann= 4 ,-1 , 0
  4530.8     .08       0  4543.3     .05       0    5000     .03       0
    5006     .05       0
Bank Sta=5000,5006
XS Rating Curve= 0 ,0
Exp/Cntr=0.3,0.1

Type RM Length L Ch R = 1 ,3867    ,501,501,501
BEGIN DESCRIPTION:
UNT063 IN GIBB 5.0
END DESCRIPTION:
XS GIS Cut Line= 3
      3636092.11     10200341.66        3635661.     10199704.88
      3635216.84     10199663.24
#Sta/Elev= 30
  4405.8   231.7  4434.3  229.44  4478.3  227.04  4521.1  223.62  4556.4  221.99
    4644  216.64  4700.9  215.01  4721.9  216.44  4766.8  214.74  4808.8  215.27
  4870.2  214.52  4925.1  214.66  4931.6  215.16  4964.5  213.81  4967.3  213.31
  4970.5  213.81  5003.5  213.85  5024.5  215.35  5039.4  214.37  5069.3   214.3
  5148.8  216.52  5193.8   216.6  5354.5  225.97  5369.9  227.46  5444.9  231.38
    5485  232.62  5505.1  232.44  5582.4  239.86  5587.5  239.46  5620.9  241.53
#Mann= 6 ,-1 , 0
  4405.8     .08       0  4556.4     .05       0  4870.2     .12       0
  4964.5     .07       0  4970.5     .12       0  5148.8     .05       0
Bank Sta=4964.5,4970.5
XS Rating Curve= 0 ,0
Exp/Cntr=0.3,0.1

Type RM Length L Ch R = 1 ,3366    ,784,784,784
BEGIN DESCRIPTION:
UNT063 IN GIBB 3.0
END DESCRIPTION:
XS GIS Cut Line= 3
       3636242.1     10200241.61       3636098.5     10199399.32
      3635397.07     10199072.91
#Sta/Elev= 30
  4328.6  229.91  4361.2   227.7  4460.4  218.02  4512.4   214.5  4570.6  211.79
    4652  210.59  4717.2  211.01  4772.3  209.79  4913.6  210.04  5128.9  211.37
  5267.3   209.8  5306.9  210.82  5407.7  209.77  5410.4  209.27  5413.7  209.77
  5465.8  211.36  5530.8   210.1  5620.9  210.97  5674.5  213.74  5781.5  221.15
  5786.6  220.61  5803.9  222.52  5832.3  222.86  5849.7  225.98  5888.4  228.22
  5895.5  228.82    5901  228.21  5923.9  230.43  5929.4  229.53  5956.7  229.66
#Mann= 11 ,-1 , 0
  4328.6     .05       0  4512.4     .08       0  4570.6     .05       0
  4913.6     .12       0  5128.9     .05       0  5407.7     .07       0
  5413.7     .05       0  5530.8     .12       0  5674.5      .1       0
  5781.5     .16       0  5888.4      .1       0
Bank Sta=5407.7,5413.7
XS Rating Curve= 0 ,0
Exp/Cntr=0.3,0.1

Type RM Length L Ch R = 1 ,2582    ,0,0,0
BEGIN DESCRIPTION:
UNT063 IN GIBB 1.0
END DESCRIPTION:
XS GIS Cut Line= 3
      3636404.08     10200364.56       3636848.5     10199121.55
      3635369.35      10198989.6
#Sta/Elev= 30
    4060  229.05  4304.3  213.68  4503.7  209.63  4802.5  209.18  4812.5  209.21
  4939.7  209.33  4997.7   207.6  5023.1  209.02  5047.9   209.1  5108.9  207.81
  5170.4  209.51  5220.7  209.03    5232  207.55  5257.5  209.11    5319  207.54
  5358.7  208.69  5463.8   207.4  5466.6   206.9  5469.8   207.4  5487.2  207.77
  5810.6  207.96  5958.8  209.41  6229.8  208.53    6376  209.59  6470.8  210.66
  6541.1  209.38  6591.3  210.46  6672.3  215.61    6771  222.01  6865.1  225.42
#Mann= 14 ,-1 , 0
    4060     .05       0  4503.7     .12       0  4802.5     .05       0
  4812.5     .12       0  4939.7     .16       0  5023.1     .05       0
  5047.9     .12       0  5463.8     .07       0  5469.8     .12       0
  5487.2     .16       0  5810.6     .05       0    6376     .12       0
  6672.3     .16       0    6771      .1       0
Bank Sta=5463.8,5469.8
XS Rating Curve= 0 ,0
Exp/Cntr=0.3,0.1
Stream Node=UNT063 IN GIBB  ,Reach-1         , 0 , 0 ,Upstream end
Stream Node=UNT063 IN GIBB  ,Reach-1         , 0 , 1 ,Downstream end

Chan Stop Cuts=-1
Use User Specified Reach Order=0
Composite Channel Slope=5