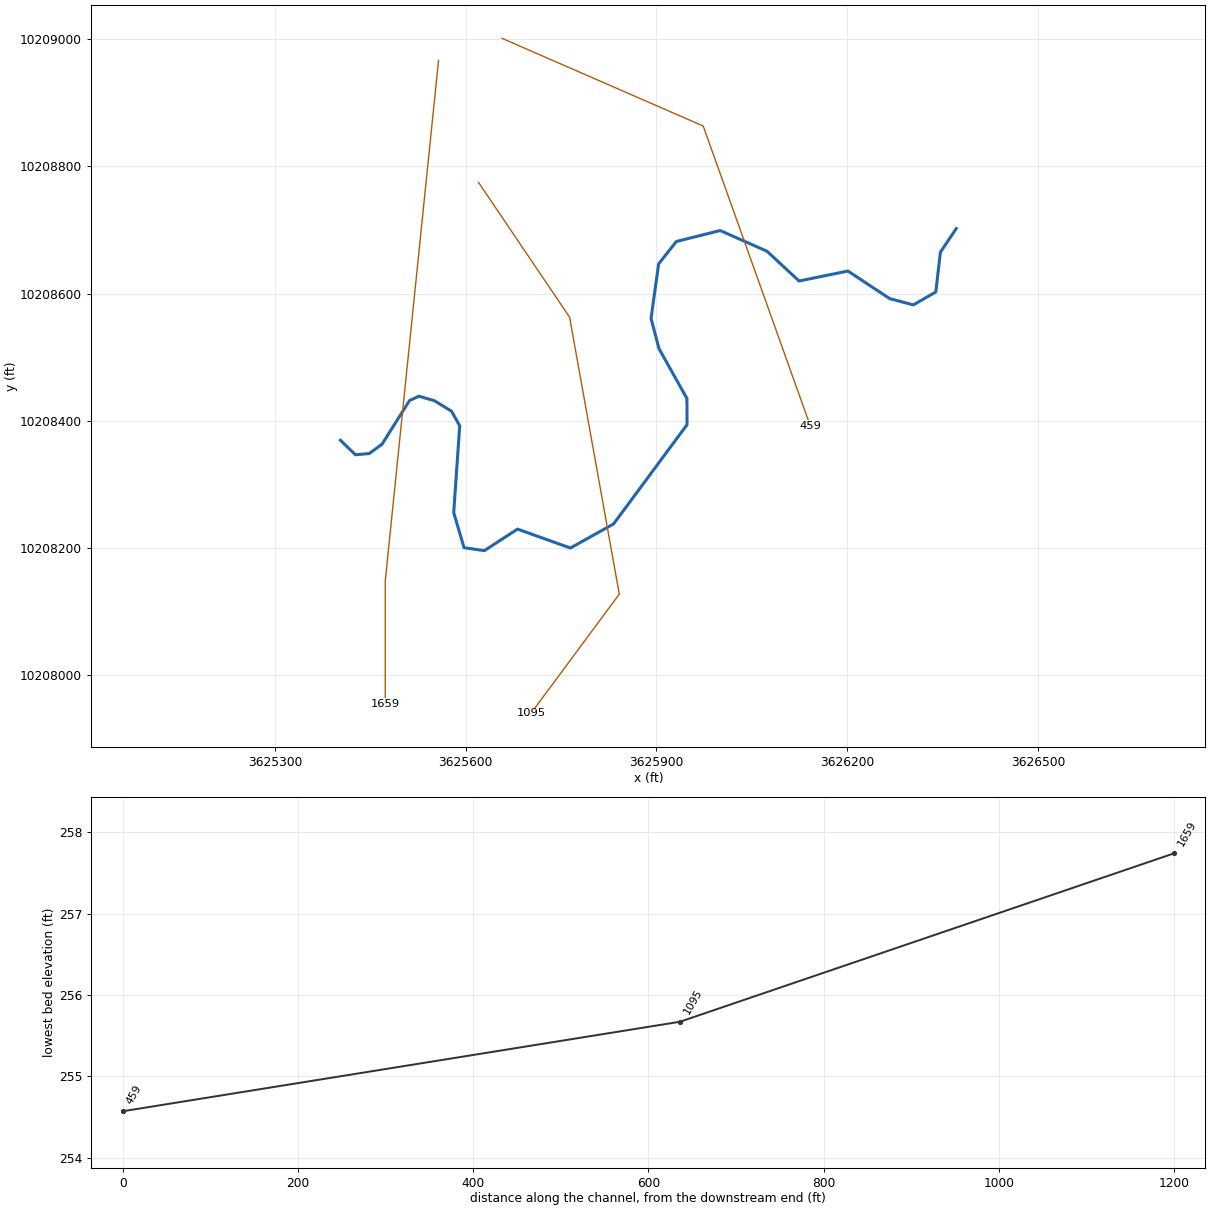
--- UNT064 IN GIBB.prj (project) ---

Proj Title=UNT064 IN GIBB Base Level Engineering
Current Plan=p01
Default Exp/Contr=0.3,0.1
English Units
Geom File=g01
Flow File=f01
Plan File=p01
BEGIN DESCRIPTION:
UNT064 IN GIBB
END DESCRIPTION:

--- UNT064 IN GIBB.p01 (plan) ---

Plan Title=Multiple Run
Short Identifier=Multiple
Geom File=g01
Flow File=f01
Subcritical Flow
K Sum by GR= 0
Std Step Tol= 0.01
Critical Tol= 0.01
Num of Std Step Trials= 20
Max Error Tol= 0.3
Flow Tol Ratio= 0.001
Split Flow NTrial= 30
Split Flow Tol= 0.02
Split Flow Ratio= 0.02
Log Output Level= 0
Friction Slope Method= 1
Unsteady Friction Slope Method= 2
Unsteady Bridges Friction Slope Method= 1
Parabolic Critical Depth
Global Vel Dist=  1 , 1 , 1
Global Log Level= 0
CheckData=True
Encroach Param= -1, 0, 0, 0
BEGIN DESCRIPTION:
Multiple Run
END DESCRIPTION:

--- UNT064 IN GIBB.f01 (steady flow) ---

Flow Title=Multiple
Number of Profiles=7
Profile Names=10-year,25-year,50-year,1pct_min,100-year,1pct_plu,500-year
River Rch & RM= UNT064 IN GIBB,Reach-1,1659
     516     685     822     722     977    1321    1382
Boundary for River Rch & Prof#=UNT064 IN GIBB,Reach-1,1
Up Type=0
Dn Type=3
Dn Slope=0.005
Boundary for River Rch & Prof#=UNT064 IN GIBB,Reach-1,2
Up Type=0
Dn Type=3
Dn Slope=0.005
Boundary for River Rch & Prof#=UNT064 IN GIBB,Reach-1,3
Up Type=0
Dn Type=3
Dn Slope=0.005
Boundary for River Rch & Prof#=UNT064 IN GIBB,Reach-1,4
Up Type=0
Dn Type=3
Dn Slope=0.005
Boundary for River Rch & Prof#=UNT064 IN GIBB,Reach-1,5
Up Type=0
Dn Type=3
Dn Slope=0.005
Boundary for River Rch & Prof#=UNT064 IN GIBB,Reach-1,6
Up Type=0
Dn Type=3
Dn Slope=0.005
Boundary for River Rch & Prof#=UNT064 IN GIBB,Reach-1,7
Up Type=0
Dn Type=3
Dn Slope=0.005

--- UNT064 IN GIBB.g01 (geometry) ---

Geom Title=Existing Conditions

River Reach=UNT064 IN GIBB,Reach-1
Reach XY= 30
      3625403.17     10208369.28      3625426.82     10208346.44
      3625448.51     10208348.38      3625468.65     10208363.17
      3625511.88     10208431.79      3625526.71     10208438.52
      3625551.11     10208431.36      3625577.81     10208414.95
      3625590.73     10208392.04      3625581.31     10208255.55
      3625597.48     10208200.38      3625629.48     10208195.62
      3625681.65     10208229.56      3625764.80     10208199.80
      3625832.70     10208237.68      3625948.25     10208393.78
      3625948.01     10208435.01      3625904.12     10208513.24
      3625891.61     10208560.81      3625903.55     10208646.57
      3625931.46     10208681.86      3626000.38     10208699.02
      3626074.00     10208666.43      3626124.38     10208619.69
      3626201.20     10208635.36      3626266.86     10208592.00
      3626304.11     10208582.12      3626339.43     10208602.45
      3626346.60     10208664.89      3626371.59     10208702.16

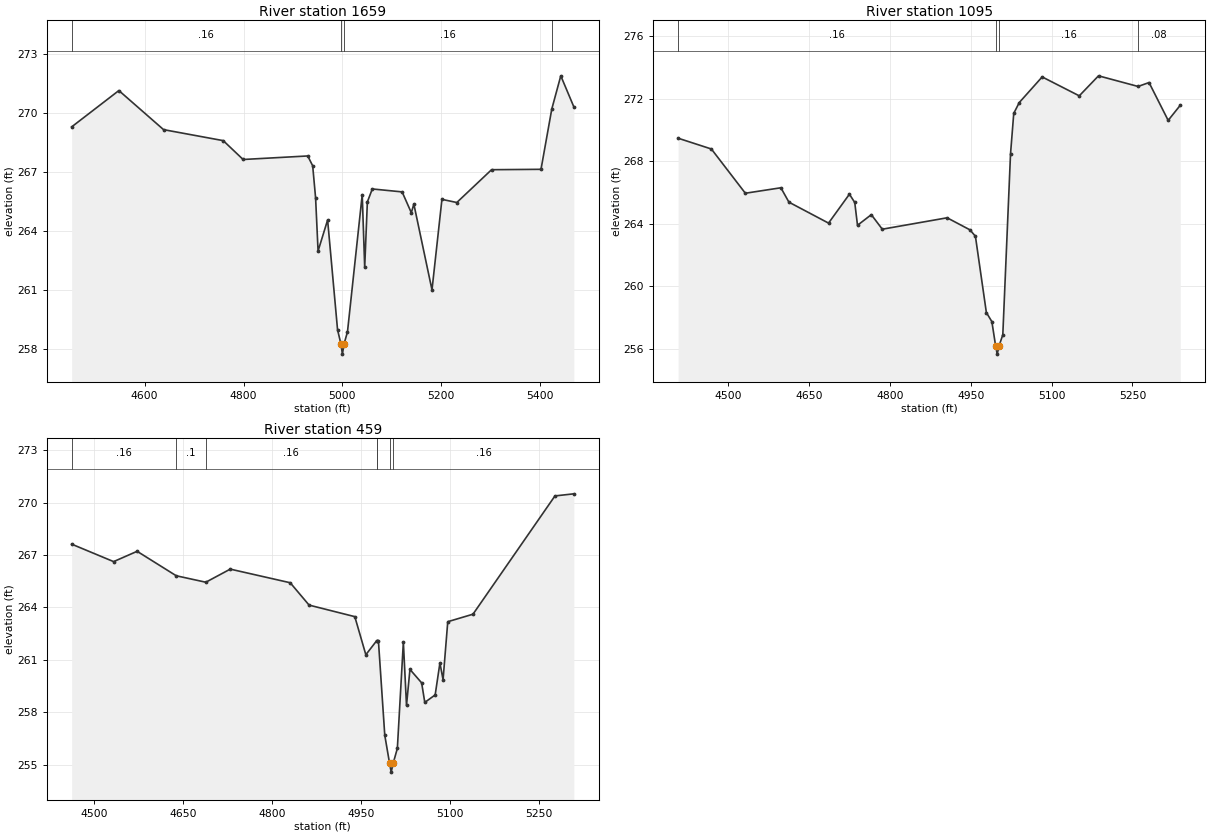
Type RM Length L Ch R = 1,1659,564,564,564
BEGIN DESCRIPTION:
UNT064 IN GIBB 2.0
END DESCRIPTION:
XS GIS Cut Line= 3
      3625557.46     10208966.61      3625473.64     10208148.12
      3625473.64     10207955.19
#Sta/Elev= 30
  4452.4  269.31  4547.9  271.16  4638.3  269.17  4759.0  268.61  4799.2  267.65
  4929.9  267.83  4939.9  267.33  4945.8  265.69  4950.8  262.99  4970.1  264.57
  4990.2  258.98  4997.2  258.24  5000.0  257.74  5003.2  258.24  5010.3  258.88
  5040.1  265.86  5045.1  262.16  5050.5  265.49  5060.5  266.15  5120.8  266.00
  5139.4  264.94  5144.5  265.38  5181.2  261.01  5201.3  265.62  5231.4  265.46
  5301.7  267.13  5401.7  267.15  5423.5  270.22  5441.7  271.91  5468.1  270.33
#Mann=4,-1,0
  4452.4    0.16       0  4997.2    0.07       0  5003.2    0.16       0
  5423.5    0.08       0
Bank Sta=4997.2,5003.2
Exp/Cntr=0.3,0.1

Type RM Length L Ch R = 1,1095,636,636,636
BEGIN DESCRIPTION:
UNT064 IN GIBB 2.1
END DESCRIPTION:
XS GIS Cut Line= 4
      3625620.42     10208774.55      3625763.52     10208562.84
      3625841.69     10208127.29      3625702.79     10207939.77
#Sta/Elev= 30
  4407.3  269.48  4469.0  268.79  4532.0  265.96  4597.9  266.31  4612.8  265.39
  4686.3  264.05  4725.0  265.90  4734.9  265.37  4740.0  263.91  4765.6  264.59
  4786.0  263.66  4906.2  264.39  4948.5  263.62  4958.7  263.21  4979.0  258.33
  4989.2  257.75  4996.3  256.17  4999.1  255.67  5002.3  256.17  5009.5  256.91
  5023.8  268.47  5029.8  271.07  5040.0  271.76  5082.5  273.40  5151.3  272.19
  5187.0  273.47  5260.4  272.79  5280.7  273.04  5316.2  270.62  5338.7  271.59
#Mann=4,-1,0
  4407.3    0.16       0  4996.3    0.07       0  5002.3    0.16       0
  5260.4    0.08       0
Bank Sta=4996.3,5002.3
Exp/Cntr=0.3,0.1

Type RM Length L Ch R = 1,459,0,0,0
BEGIN DESCRIPTION:
UNT064 IN GIBB 1.0
END DESCRIPTION:
XS GIS Cut Line= 3
      3625657.30     10209001.29      3625973.64     10208863.40
      3626142.10     10208391.66
#Sta/Elev= 30
  4462.5  267.62  4533.2  266.62  4572.8  267.21  4638.7  265.81  4688.5  265.44
  4729.7  266.19  4830.7  265.41  4862.5  264.13  4939.5  263.47  4958.1  261.29
  4976.3  262.09  4976.8  262.09  4979.3  262.08  4990.0  256.68  4998.1  255.07
  5000.8  254.57  5004.1  255.07  5011.2  255.93  5021.3  262.01  5026.6  258.39
  5032.4  260.45  5052.1  259.68  5057.4  258.56  5074.9  258.99  5082.9  260.82
  5088.2  259.86  5096.1  263.18  5138.6  263.61  5276.7  270.38  5308.5  270.50
#Mann=7,-1,0
  4462.5    0.16       0  4638.7     0.1       0  4688.5    0.16       0
  4976.3     0.1       0  4976.8    0.16       0  4998.1    0.07       0
  5004.1    0.16       0
Bank Sta=4998.1,5004.1
Exp/Cntr=0.3,0.1

Chan Stop Cuts=-1