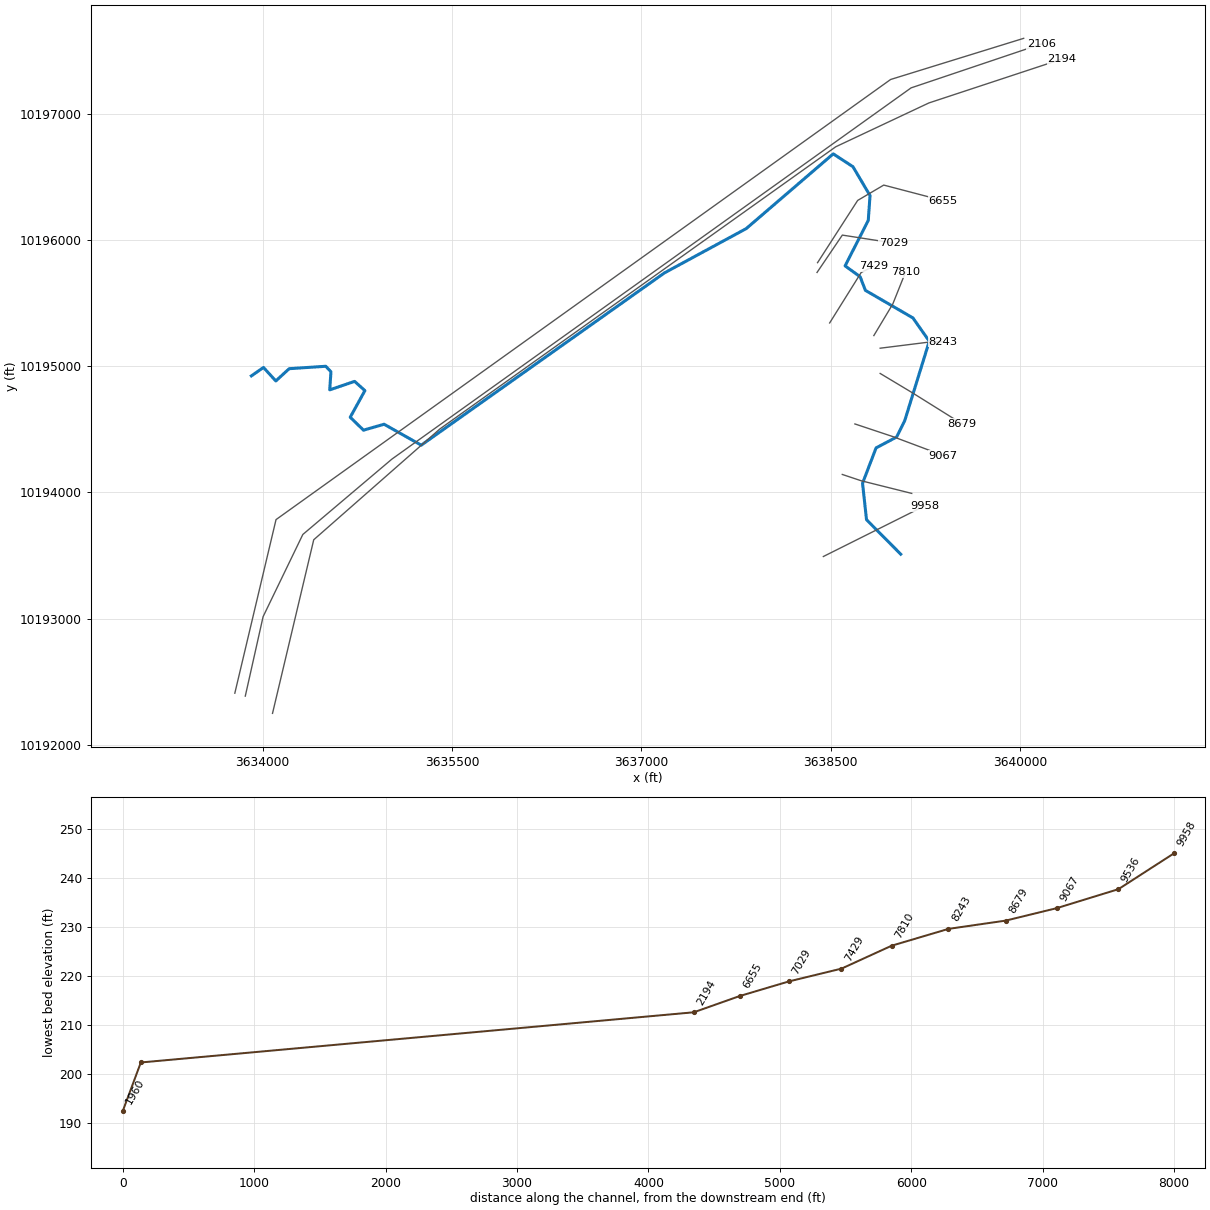
--- UNT066 IN GIBB.prj (project) ---

Proj Title=UNT066 IN GIBB Base Level Engineering
Current Plan=p01
Default Exp/Contr=0.3,0.1
English Units
Geom File=g01
Flow File=f01
Plan File=p01
Y Axis Title=Elevation
X Axis Title(PF)=Main Channel Distance
X Axis Title(XS)=Station
BEGIN DESCRIPTION:
UNT066 IN GIBB
END DESCRIPTION:
DSS Export Rating Curves= 0
DSS Export Rating Curve Sorted= 0
DSS Export Volume Flow Curves= 0
DXF OffsetX= 0
DXF OffsetY= 0
DXF ScaleX= 1
DXF ScaleY= 10

--- UNT066 IN GIBB.p01 (plan) ---

Plan Title=Multiple Run
Short Identifier=Multiple
Geom File=g01
Flow File=f01
Subcritical Flow
K Sum by GR= 0
Std Step Tol= 0.01
Critical Tol= 0.01
Num of Std Step Trials= 20
Max Error Tol= 0.3
Flow Tol Ratio= 0.001
Split Flow NTrial= 30
Split Flow Tol= 0.02
Split Flow Ratio= 0.02
Log Output Level= 0
Friction Slope Method= 1
Unsteady Friction Slope Method= 2
Unsteady Bridges Friction Slope Method= 1
Parabolic Critical Depth
Global Vel Dist=  1 , 1 , 1
Global Log Level= 0
CheckData=True
Encroach Param= -1, 0, 0, 0
BEGIN DESCRIPTION:
Multiple Run
END DESCRIPTION:

--- UNT066 IN GIBB.f01 (steady flow) ---

Flow Title=Multiple
Program Version=4.10
Number of Profiles= 7
Profile Names=10-year,25-year,50-year,1pct_min,100-year,1pct_plu,500-year
River Rch & RM=UNT066 IN GIBB,Reach-1         ,9958
     940    1286    1572    1406    1902    2572    2787
Boundary for River Rch & Prof#=UNT066 IN GIBB,Reach-1         , 1
Up Type= 0
Dn Type= 3
Dn Slope=0.005
Boundary for River Rch & Prof#=UNT066 IN GIBB,Reach-1         , 2
Up Type= 0
Dn Type= 3
Dn Slope=0.005
Boundary for River Rch & Prof#=UNT066 IN GIBB,Reach-1         , 3
Up Type= 0
Dn Type= 3
Dn Slope=0.005
Boundary for River Rch & Prof#=UNT066 IN GIBB,Reach-1         , 4
Up Type= 0
Dn Type= 3
Dn Slope=0.005
Boundary for River Rch & Prof#=UNT066 IN GIBB,Reach-1         , 5
Up Type= 0
Dn Type= 3
Dn Slope=0.005
Boundary for River Rch & Prof#=UNT066 IN GIBB,Reach-1         , 6
Up Type= 0
Dn Type= 3
Dn Slope=0.005
Boundary for River Rch & Prof#=UNT066 IN GIBB,Reach-1         , 7
Up Type= 0
Dn Type= 3
Dn Slope=0.005
DSS Import GetInterval= 0
DSS Import GetPeak= 0
DSS Import FillOption= 0

--- UNT066 IN GIBB.g01 (geometry) ---

Geom Title=Existing Conditions
Program Version=4.10

River Reach=UNT066 IN GIBB  ,Reach-1
Reach XY= 30
      3639055.03     10193510.14      3638784.03     10193783.16
      3638752.56     10194072.08      3638859.92     10194352.02
      3639022.73     10194438.12      3639087.16     10194569.13
      3639281.25     10195196.82      3639151.39     10195381.56
      3638774.97     10195599.83      3638733.49     10195707.79
      3638614.21     10195793.53      3638797.81     10196153.73
      3638811.84     10196350.26      3638676.47     10196579.25
      3638520.22     10196680.81      3637830.98      10196088.8
      3637183.41     10195738.11       3635257.2     10194373.52
      3634962.93     10194539.32      3634799.73     10194492.45
       3634694.7     10194594.88      3634811.02     10194805.81
      3634729.42     10194878.73      3634532.37     10194811.89
      3634541.92     10194955.12      3634501.12     10194998.52
      3634211.19     10194979.42      3634105.29      10194882.2
      3634007.67     10194989.04      3633911.59     10194922.16

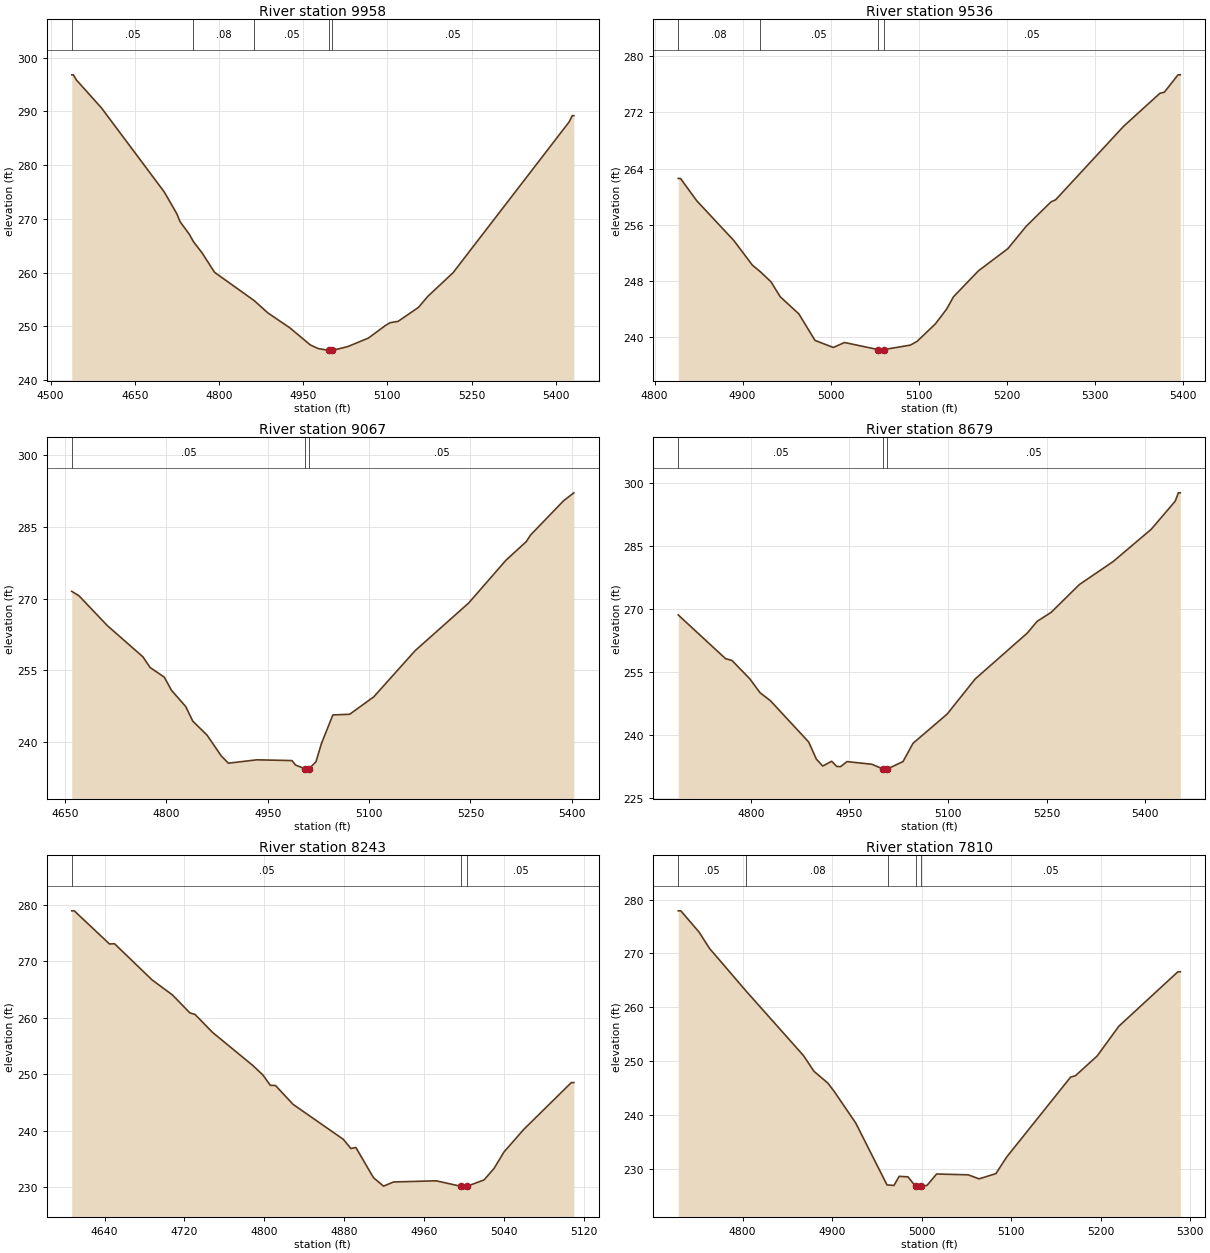
Type RM Length L Ch R = 1 ,9958    ,422,422,422
BEGIN DESCRIPTION:
UNT066 IN GIBB 19.0
END DESCRIPTION:
XS GIS Cut Line= 3
      3638442.08     10193491.63      3638842.11     10193691.64
      3639242.14     10193891.66
#Sta/Elev= 30
  4537.7  296.79  4540.5  296.79  4546.1  295.82  4590.8  290.61  4702.6  274.99
    4725  270.93  4730.6  269.48  4747.4   267.1  4754.5  265.75  4769.7   263.7
  4792.1  260.06  4862.6  254.81  4887.1  252.51  4926.2  249.74  4962.6  246.56
  4976.6  245.88  4995.9  245.53  4998.7  245.03  5001.9  245.53  5029.7  246.26
    5066  247.82  5096.7  250.18  5105.1   250.7  5119.1  250.94  5155.4  253.54
  5172.2  255.61  5216.9  259.97  5423.8  288.03  5429.4   289.2  5432.2   289.2
#Mann= 5 ,-1 , 0
  4537.7     .05       0  4754.5     .08       0  4862.6     .05       0
  4995.9     .03       0  5001.9     .05       0
Bank Sta=4995.9,5001.9
XS Rating Curve= 0 ,0
Exp/Cntr=0.3,0.1

Type RM Length L Ch R = 1 ,9536    ,469,469,469
BEGIN DESCRIPTION:
UNT066 IN GIBB 18.0
END DESCRIPTION:
XS GIS Cut Line= 3
      3638592.14     10194141.63      3638742.11     10194091.64
      3639142.12     10193991.64
#Sta/Elev= 30
  4826.9  262.59  4829.5  262.59  4847.9  259.42  4890.1  253.75  4911.2  250.24
    4920  249.34  4932.3  247.88  4942.8  245.75  4963.9  243.32  4982.3  239.54
    5003  238.54  5015.9  239.24  5054.1  238.23  5056.9  237.73  5060.1  238.23
  5090.6  238.87  5098.4  239.42    5119  241.89  5131.9  244.01  5139.6  245.75
  5167.9  249.44  5201.4   252.6  5222.1  255.77  5250.4  259.26  5255.6  259.55
  5332.9  270.02  5374.1  274.71  5379.2  274.87  5394.7  277.34  5397.3  277.34
#Mann= 4 ,-1 , 0
  4826.9     .08       0    4920     .05       0  5054.1     .03       0
  5060.1     .05       0
Bank Sta=5054.1,5060.1
XS Rating Curve= 0 ,0
Exp/Cntr=0.3,0.1

Type RM Length L Ch R = 1 ,9067    ,388,388,388
BEGIN DESCRIPTION:
UNT066 IN GIBB 17.0
END DESCRIPTION:
XS GIS Cut Line= 3
      3638692.09     10194541.65      3638992.11     10194441.64
      3639392.07     10194291.66
#Sta/Elev= 30
  4659.8   271.5  4670.4  270.59  4712.5  264.33  4765.2  257.79  4775.8  255.56
  4796.8  253.54  4807.4   250.8  4828.5  247.39    4839  244.33  4860.1   241.4
  4881.2  237.04  4891.7  235.52  4933.9  236.23  4985.8  236.07  4991.2  235.13
  5005.1  234.36  5007.8  233.86  5011.1  234.36  5021.4  235.83  5029.4  239.61
  5046.4  245.63  5071.3  245.77  5106.9  249.41  5168.3   259.1  5247.5  269.07
  5302.7  278.03  5332.9  281.94  5339.2  283.32  5388.1  290.49  5403.2  292.14
#Mann= 3 ,-1 , 0
  4659.8     .05       0  5005.1    .035       0  5011.1     .05       0
Bank Sta=5005.1,5011.1
XS Rating Curve= 0 ,0
Exp/Cntr=0.3,0.1

Type RM Length L Ch R = 1 ,8679    ,436,436,436
BEGIN DESCRIPTION:
UNT066 IN GIBB 16.0
END DESCRIPTION:
XS GIS Cut Line= 3
      3638892.07     10194941.66      3639142.11     10194791.64
      3639542.12     10194541.64
#Sta/Elev= 30
  4689.8  268.49  4761.8  258.08  4771.5  257.66  4798.7  253.27  4814.2  249.97
  4829.8   248.1  4888.1  238.26  4899.8  234.17  4909.5  232.53  4923.1  233.67
  4930.9  232.42  4936.7   232.4  4946.4  233.59  4984.3  232.95  5001.4  231.82
  5004.1  231.32  5007.4  231.82  5031.5  233.59  5046.8  237.95  5098.7  244.91
  5141.2  253.25  5220.2  264.14  5235.5  266.97  5256.7   269.1  5299.8  275.74
  5351.1  281.21  5408.9  288.88  5445.4  295.57  5450.1  297.55  5453.1  297.55
#Mann= 3 ,-1 , 0
  4689.8     .05       0  5001.4    .035       0  5007.4     .05       0
Bank Sta=5001.4,5007.4
XS Rating Curve= 0 ,0
Exp/Cntr=0.3,0.1

Type RM Length L Ch R = 1 ,8243    ,433,433,433
BEGIN DESCRIPTION:
UNT066 IN GIBB 15.0
END DESCRIPTION:
XS GIS Cut Line= 3
       3638892.1     10195141.64      3639292.11     10195191.64
      3639392.09     10195191.64
#Sta/Elev= 30
  4607.2  278.91  4609.7  278.91    4645  273.04    4650  273.09  4687.8  266.66
    4708  264.03  4725.6  260.83  4730.7  260.57  4748.3  257.38  4788.6  251.53
  4798.7  249.85  4806.2  248.01  4811.3  247.99  4828.9  244.65  4879.3  238.45
  4886.9  236.82  4891.9     237  4909.5  231.66  4919.6  230.16  4929.7   230.9
  4972.5   231.1  4997.2  230.13    5000  229.63  5003.2  230.13  5020.3  231.26
  5030.3  233.28  5040.3  236.21  5060.3  240.24  5107.8   248.5  5110.3   248.5
#Mann= 3 ,-1 , 0
  4607.2     .05       0  4997.2    .035       0  5003.2     .05       0
Bank Sta=4997.2,5003.2
XS Rating Curve= 0 ,0
Exp/Cntr=0.3,0.1

Type RM Length L Ch R = 1 ,7810    ,381,381,381
BEGIN DESCRIPTION:
UNT066 IN GIBB 14.0
END DESCRIPTION:
XS GIS Cut Line= 3
       3638842.1     10195241.64      3638992.11     10195491.64
       3639092.1     10195741.63
#Sta/Elev= 30
  4728.2  277.93  4731.1  277.93  4751.5  273.97  4763.2  270.93  4804.3  262.96
  4868.1  251.02  4879.8   248.1  4895.4  245.89  4903.1  244.19  4926.5  238.47
  4961.4  226.97    4963  226.95  4969.2  226.88    4975  228.57  4984.8  228.47
  4993.4  226.69  4996.2  226.19  4999.4  226.69  5006.1  226.89  5016.8     229
  5052.1  228.85  5064.2   228.1    5083  229.07  5095.1  232.17  5166.5  247.02
  5171.9  247.28  5196.1  250.94  5220.3  256.47  5286.3   266.6    5289   266.6
#Mann= 5 ,-1 , 0
  4728.2     .05       0  4804.3     .08       0    4963     .05       0
  4993.4     .03       0  4999.4     .05       0
Bank Sta=4993.4,4999.4
XS Rating Curve= 0 ,0
Exp/Cntr=0.3,0.1

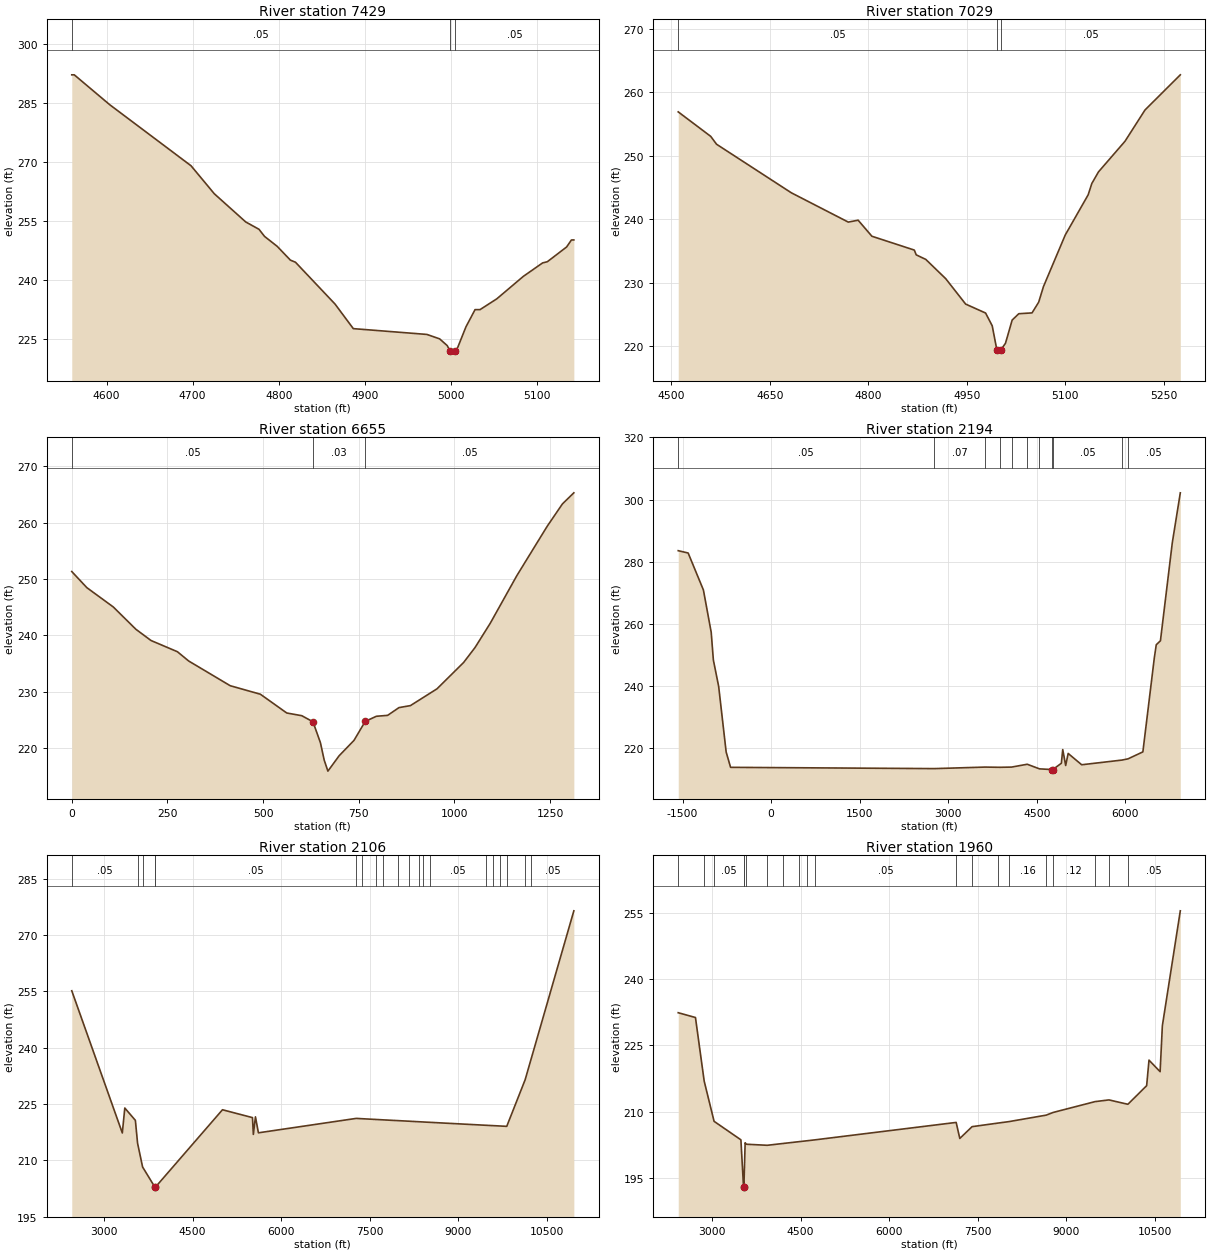
Type RM Length L Ch R = 1 ,7429    ,400,400,400
BEGIN DESCRIPTION:
UNT066 IN GIBB 13.0
END DESCRIPTION:
XS GIS Cut Line= 3
      3638492.11     10195341.65      3638742.11     10195741.64
      3638842.11     10195791.65
#Sta/Elev= 30
  4559.5  292.07  4562.4  292.07  4603.7  284.48  4698.1  269.02  4725.2  261.91
  4761.7  254.77  4777.1  252.91  4783.5  251.12  4798.3  248.58  4813.6  245.09
  4819.5  244.56  4865.5  233.95  4886.7  227.73  4972.2  226.26    4987  225.14
  4995.8  223.44  4999.3  222.02    5002  221.52  5005.3  222.02  5008.2  223.04
  5017.6  228.18  5028.2  232.55    5034  232.55  5053.5  235.29  5084.3  240.98
  5106.7  244.39  5112.2  244.69  5134.6  248.43  5140.2  250.21    5143  250.21
#Mann= 3 ,-1 , 0
  4559.5     .05       0  4999.3     .03       0  5005.3     .05       0
Bank Sta=4999.3,5005.3
XS Rating Curve= 0 ,0
Exp/Cntr=0.3,0.1

Type RM Length L Ch R = 1 ,7029    ,374,374,374
BEGIN DESCRIPTION:
UNT066 IN GIBB 12.0
END DESCRIPTION:
XS GIS Cut Line= 3
       3638392.1     10195741.63      3638592.51     10196037.53
      3638995.31     10195975.02
#Sta/Elev= 30
  4510.4  256.93  4559.9  253.07  4568.8  251.83  4682.7  244.18  4769.5  239.56
  4784.5  239.86  4805.5  237.33  4870.1  235.15    4873   234.4  4887.6  233.68
    4918  230.64  4948.3  226.64  4978.7  225.23  4988.8  223.22  4995.9  219.41
  4998.7  218.91  5001.9  219.41    5009  220.46  5019.2  224.12  5029.3  225.12
  5049.5  225.25  5059.6  226.94  5066.9   229.4  5100.1  237.53    5135  243.86
  5140.6  245.65  5150.7  247.47  5191.2  252.31  5221.6  257.23  5275.4  262.77
#Mann= 3 ,-1 , 0
  4510.4     .05       0  4995.9    .035       0  5001.9     .05       0
Bank Sta=4995.9,5001.9
XS Rating Curve= 0 ,0
Exp/Cntr=0.3,0.1

Type RM Length L Ch R = 1 ,6655    ,350,350,350
XS GIS Cut Line= 4
     3638396.191    10195819.059     3638713.899    10196312.115
     3638920.497    10196433.643     3639390.983    10196310.379
#Sta/Elev= 30
       0  251.33   39.44  248.47  108.46  245.05  167.62  241.09  207.06   239.1
  276.09  237.11  305.67  235.46  414.13  231.08  493.01  229.57  562.03  226.24
  601.26  225.76  630.52  224.68  650.03  220.96  659.79   217.9  669.54  215.93
   698.8  218.65  737.82  221.39  767.08  224.75  796.34  225.66  825.61  225.82
  855.41   227.2  885.22  227.55  954.76  230.53  1024.3   235.2 1054.11  237.85
 1093.85  242.15 1163.39   250.6 1242.87  259.37 1282.61  263.33 1312.41  265.29
#Mann= 3 ,-1 , 0
       0     .05       0  630.52     .03       0  767.08     .05       0
Bank Sta=630.52,767.08
XS Rating Curve= 0 ,0
Exp/Cntr=0.3,0.1

Type RM Length L Ch R = 1 ,2194    ,4207,4207,4207
BEGIN DESCRIPTION:
UNT066 IN GIBB 1.2
END DESCRIPTION:
XS GIS Cut Line= 6
      3634079.17     10192249.25      3634405.57     10193624.28
     3635404.264    10194501.698     3638540.115    10196736.941
     3639277.962    10197084.164     3640330.479    10197431.386
#Sta/Elev= 30
   -1573  283.55 -1404.9   282.8 -1146.5   270.9 -1014.7  257.31  -977.7  248.34
  -888.1  239.87  -761.5  218.79  -686.6  213.83  2764.7  213.42  3624.6  213.91
  3873.2  213.84  4073.2  213.91  4338.3  214.82  4545.7  213.34  4764.8  213.11
  4767.6  212.61  4770.8  213.11  4916.5  215.14  4939.8  219.55  4989.6  214.43
  5031.9   218.3  5260.4  214.66  5944.6  216.17  6046.7  216.57  6297.2   218.8
  6491.5  249.12  6524.1  253.29  6594.6  254.55  6795.6  286.11  6931.3  302.17
#Mann= 11 ,-1 , 0
   -1573     .05       0  2764.7     .07       0  3624.6     .05       0
  3873.2     .07       0  4073.2     .05       0  4338.3     .08       0
  4545.7     .05       0  4764.8     .03       0  4770.8     .05       0
  5944.6     .08       0  6046.7     .05       0
Bank Sta=4764.8,4770.8
XS Rating Curve= 0 ,0
Exp/Cntr=0.3,0.1

Type RM Length L Ch R = 1 ,2106    ,138,138,138
BEGIN DESCRIPTION:
UNT066 IN GIBB 1.1
END DESCRIPTION:
XS GIS Cut Line= 6
     3633863.465    10192385.813     3634004.524    10193015.153
     3634319.195    10193666.195      3635024.49    10194262.983
     3639136.903    10197203.521     3640167.719    10197550.743
#Sta/Elev= 30
  2452.2  255.18  3308.3  217.32  3350.5  223.96  3529.6  220.68  3566.8  214.59
    3652  208.26  3861.5  202.87  3864.2  202.37  3867.5  202.87  5004.7   223.5
  5513.1  221.41  5527.9  216.94  5563.5  221.62  5613.9  217.36  7270.3   221.2
  7374.8  221.11    7598  220.92  7727.1  220.81  7984.4   220.6  8166.5  220.45
  8341.5   220.3  8402.8  220.25  8520.9  220.15  9465.7  219.37  9591.2  219.27
  9701.9  219.18    9820  219.08 10130.8  231.45 10232.9  237.01 10956.6  276.46
#Mann= 20 ,-1 , 0
  2452.2     .05       0  3566.8     .12       0    3652     .05       0
  3861.5     .03       0  3867.5     .05       0  7270.3      .1       0
  7374.8     .05       0    7598      .1       0  7727.1     .05       0
  7984.4     .08       0  8166.5     .08       0  8341.5     .16       0
  8402.8     .05       0  8520.9     .05       0  9465.7     .05       0
  9591.2      .1       0  9701.9     .05       0    9820     .05       0
 10130.8     .08       0 10232.9     .05       0
Bank Sta=3861.5,3867.5
XS Rating Curve= 0 ,0
Exp/Cntr=0.3,0.1

Type RM Length L Ch R = 1 ,1960    ,0,0,0
BEGIN DESCRIPTION:
UNT066 IN GIBB 1.0
END DESCRIPTION:
XS GIS Cut Line= 4
      3633780.58     10192409.04      3634106.96       10193784.
      3638975.01     10197270.11      3640028.85     10197595.97
#Sta/Elev= 30
  2427.2  232.38    2719  231.29  2866.8  216.88  3034.3  207.78  3488.5  203.59
  3533.3  192.92  3536.1  192.42  3539.3  192.92  3560.4  202.92  3580.5  202.59
  3935.2  202.35  4202.8  202.76  4472.9  203.17  4606.1  203.37    4736  203.57
  7134.4  207.53  7196.3   203.9  7404.1  206.57  7848.6  207.39  8027.1  207.71
  8659.4  209.18  8777.5  209.79  9486.2  212.24  9722.4  212.63 10042.9  211.64
 10360.9  215.85 10400.6  221.64   10589  219.02 10627.1  229.44   10931  255.46
#Mann= 20 ,-1 , 0
  2427.2     .05       0  2866.8     .16       0  3034.3     .05       0
  3533.3     .03       0  3539.3     .12       0  3580.5     .05       0
  3935.2     .05       0  4202.8      .1       0  4472.9     .05       0
  4606.1      .1       0    4736     .05       0  7134.4     .16       0
  7404.1      .1       0  7848.6     .16       0  8027.1     .16       0
  8659.4     .05       0  8777.5     .12       0  9486.2      .1       0
  9722.4     .16       0 10042.9     .05       0
Bank Sta=3533.3,3539.3
XS Rating Curve= 0 ,0
Exp/Cntr=0.3,0.1
Stream Node=UNT066 IN GIBB  ,Reach-1         , 0 , 0 ,Upstream end
Stream Node=UNT066 IN GIBB  ,Reach-1         , 0 , 1 ,Downstream end

Chan Stop Cuts=-1
Use User Specified Reach Order=0
Composite Channel Slope=5