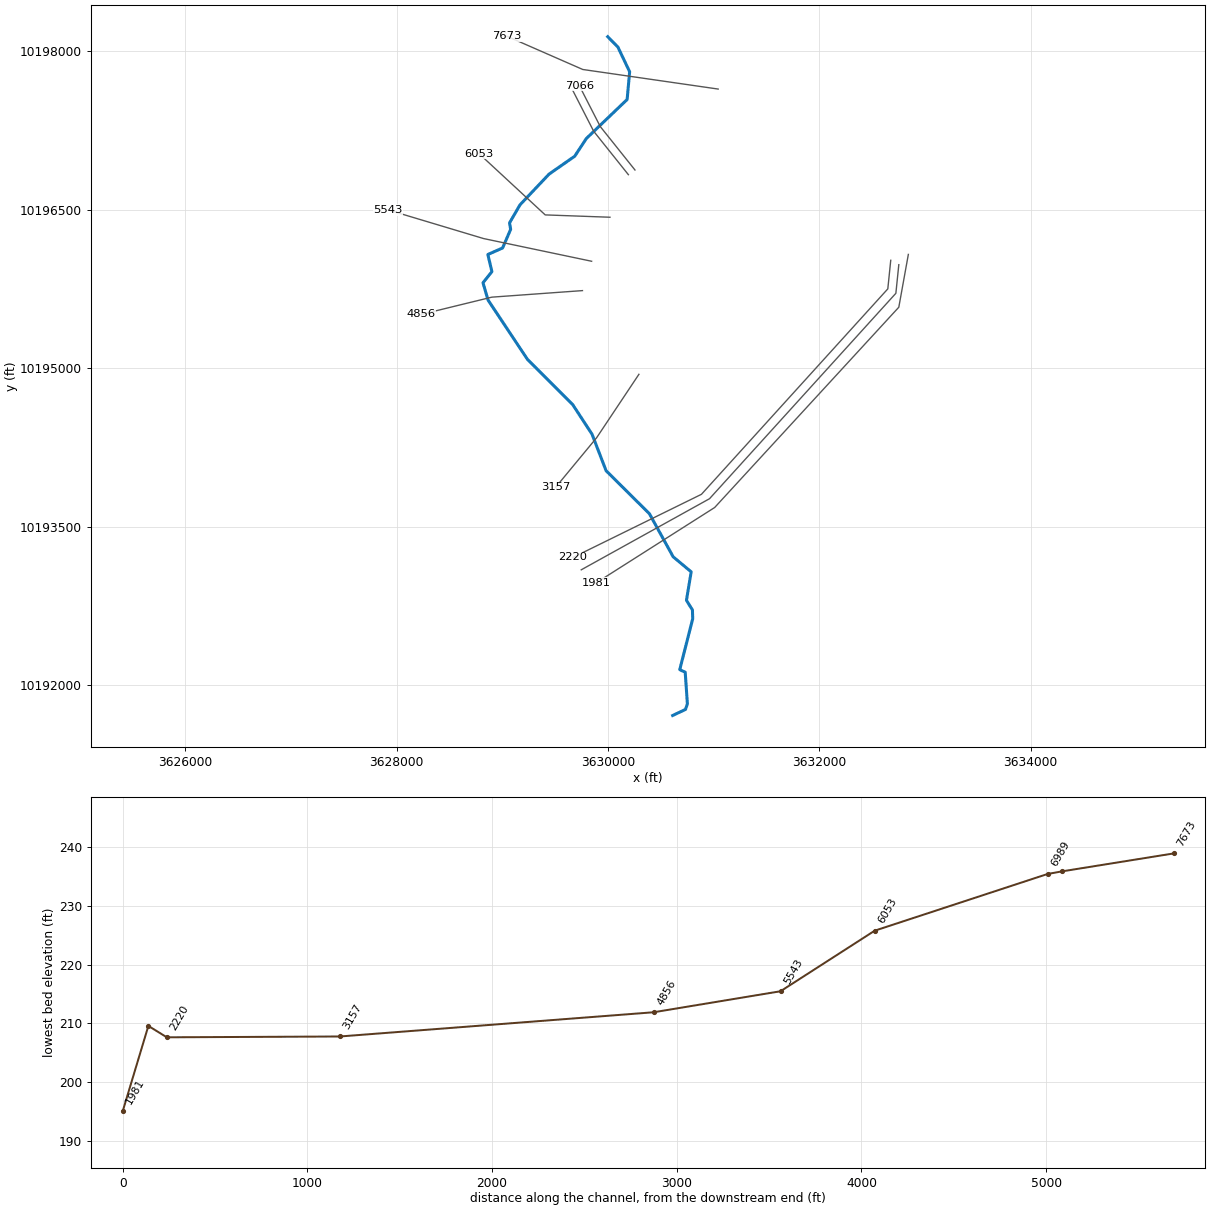
--- UNT067 IN GIBB.prj (project) ---

Proj Title=UNT067 IN GIBB Base Level Engineering
Current Plan=p01
Default Exp/Contr=0.3,0.1
English Units
Geom File=g01
Flow File=f01
Plan File=p01
Y Axis Title=Elevation
X Axis Title(PF)=Main Channel Distance
X Axis Title(XS)=Station
BEGIN DESCRIPTION:
UNT067 IN GIBB
END DESCRIPTION:
DSS Export Rating Curves= 0
DSS Export Rating Curve Sorted= 0
DSS Export Volume Flow Curves= 0
DXF OffsetX= 0
DXF OffsetY= 0
DXF ScaleX= 1
DXF ScaleY= 10

--- UNT067 IN GIBB.p01 (plan) ---

Plan Title=Multiple Run
Short Identifier=Multiple
Geom File=g01
Flow File=f01
Subcritical Flow
K Sum by GR= 0
Std Step Tol= 0.01
Critical Tol= 0.01
Num of Std Step Trials= 20
Max Error Tol= 0.3
Flow Tol Ratio= 0.001
Split Flow NTrial= 30
Split Flow Tol= 0.02
Split Flow Ratio= 0.02
Log Output Level= 0
Friction Slope Method= 1
Unsteady Friction Slope Method= 2
Unsteady Bridges Friction Slope Method= 1
Parabolic Critical Depth
Global Vel Dist=  1 , 1 , 1
Global Log Level= 0
CheckData=True
Encroach Param= -1, 0, 0, 0
BEGIN DESCRIPTION:
Multiple Run
END DESCRIPTION:

--- UNT067 IN GIBB.f01 (steady flow) ---

Flow Title=Multiple
Number of Profiles=7
Profile Names=10-year,25-year,50-year,1pct_min,100-year,1pct_plu,500-year
River Rch & RM= UNT067 IN GIBB,Reach-1,7673
     567     754     904     795    1076    1455    1523
Boundary for River Rch & Prof#=UNT067 IN GIBB,Reach-1,1
Up Type=0
Dn Type=3
Dn Slope=0.005
Boundary for River Rch & Prof#=UNT067 IN GIBB,Reach-1,2
Up Type=0
Dn Type=3
Dn Slope=0.005
Boundary for River Rch & Prof#=UNT067 IN GIBB,Reach-1,3
Up Type=0
Dn Type=3
Dn Slope=0.005
Boundary for River Rch & Prof#=UNT067 IN GIBB,Reach-1,4
Up Type=0
Dn Type=3
Dn Slope=0.005
Boundary for River Rch & Prof#=UNT067 IN GIBB,Reach-1,5
Up Type=0
Dn Type=3
Dn Slope=0.005
Boundary for River Rch & Prof#=UNT067 IN GIBB,Reach-1,6
Up Type=0
Dn Type=3
Dn Slope=0.005
Boundary for River Rch & Prof#=UNT067 IN GIBB,Reach-1,7
Up Type=0
Dn Type=3
Dn Slope=0.005

--- UNT067 IN GIBB.g01 (geometry) ---

Geom Title=Existing Conditions
Program Version=4.10

River Reach=UNT067 IN GIBB  ,Reach-1
Reach XY= 30
      3629996.59     10198137.16      3630093.42     10198038.68
      3630204.23     10197805.49      3630180.47     10197542.71
      3629794.66     10197173.84      3629684.43     10197006.06
      3629440.78     10196835.75      3629167.11     10196546.53
      3629067.15     10196374.65      3629077.97      10196313.5
      3629001.62     10196137.35       3628862.2     10196075.63
       3628900.5     10195913.53      3628816.11     10195808.13
      3628863.83     10195644.53      3629236.44     10195083.91
      3629664.82     10194655.52      3629848.42     10194374.27
      3629981.23     10194029.22       3630391.5     10193621.71
      3630616.24     10193214.16      3630786.71     10193071.78
      3630741.87     10192802.07      3630798.74     10192710.94
      3630801.11     10192626.73      3630678.63     10192146.17
      3630730.28     10192121.41      3630750.81      10191821.6
      3630732.87     10191769.41      3630611.59     10191712.16

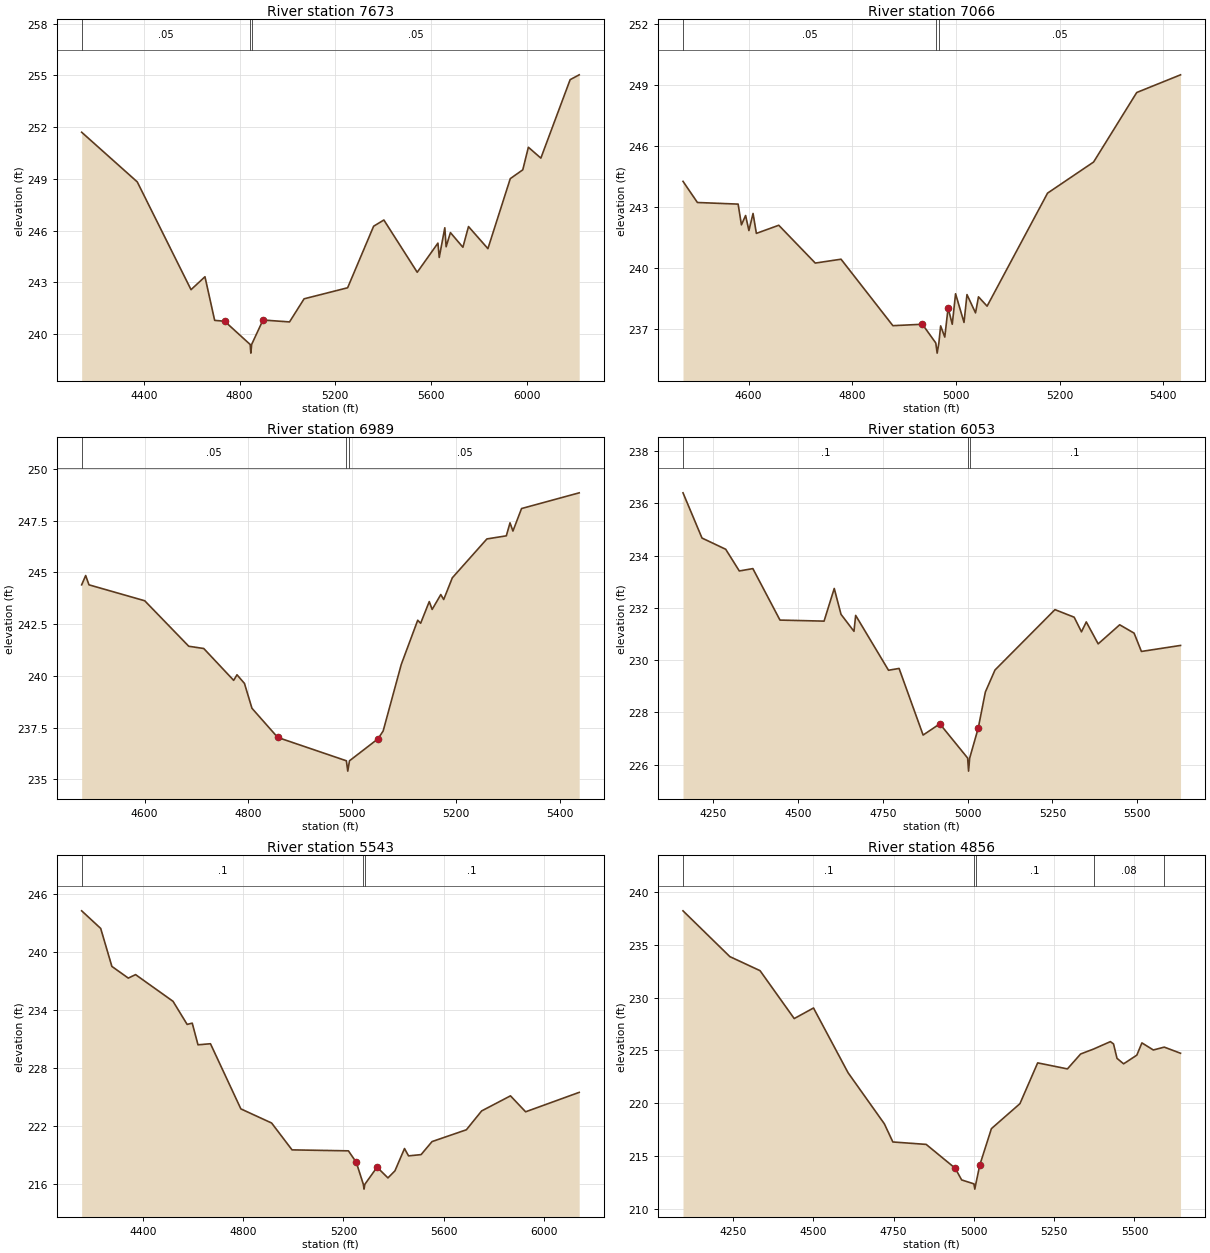
Type RM Length L Ch R = 1 ,7673    ,607,607,607
BEGIN DESCRIPTION:
UNT067 IN GIBB 14.0
END DESCRIPTION:
XS GIS Cut Line= 3
      3631042.15     10197641.64      3629760.58     10197826.95
      3629042.07     10198141.66
#Sta/Elev= 30
  4139.7   251.7  4372.1  248.82  4596.7  242.57    4655  243.32  4695.5  240.79
  4737.3  240.74    4844  239.39  4846.8  238.89    4850  239.39  4897.5  240.81
  5008.4   240.7  5069.3  242.04  5251.2  242.68  5359.9  246.25  5402.7  246.61
  5542.1  243.58  5628.6  245.27  5634.1  244.44  5657.4  246.16  5662.9  245.06
  5680.8  245.88    5733  245.03  5756.4  246.23  5837.5  244.95    5931  249.01
  5983.2  249.52  6006.6  250.83  6058.8   250.2  6181.2  254.75    6219  255.03
#Mann= 3 ,-1 , 0
  4139.7     .05       0    4844     .03       0    4850     .05       0
Bank Sta=4737.3,4897.5
XS Rating Curve= 0 ,0
Exp/Cntr=0.3,0.1

Type RM Length L Ch R = 1 ,7066    ,77,77,77
BEGIN DESCRIPTION:
UNT067 IN GIBB 13.0
END DESCRIPTION:
XS GIS Cut Line= 3
      3630254.87     10196875.43      3629926.24     10197286.64
      3629728.85     10197672.26
#Sta/Elev= 30
  4473.6  244.28  4501.4  243.24  4579.9  243.16  4586.3  242.14  4594.3   242.6
  4600.7  241.86  4608.7   242.7  4615.1  241.72  4658.3  242.12  4728.7  240.26
  4778.4  240.45  4878.4  237.18  4935.3  237.25  4961.1  236.33  4963.8  235.83
  4967.1  236.33  4970.5  237.17  4978.5  236.62  4984.9  238.06  4992.9  237.25
  4999.3  238.75  5015.6  237.34  5021.3  238.71  5037.8  237.81  5043.5   238.6
  5060.1  238.14  5176.7   243.7  5265.5  245.23  5348.7  248.65  5433.2  249.52
#Mann= 3 ,-1 , 0
  4473.6     .05       0  4961.1     .03       0  4967.1     .05       0
Bank Sta=4935.3,4984.9
XS Rating Curve= 0 ,0
Exp/Cntr=0.3,0.1

Type RM Length L Ch R = 1 ,6989    ,936,936,936
BEGIN DESCRIPTION:
UNT067 IN GIBB 12.0
END DESCRIPTION:
XS GIS Cut Line= 3
      3630192.37     10196831.17      3629863.74     10197242.37
      3629667.08     10197626.58
#Sta/Elev= 30
  4478.9   244.4  4486.6  244.85    4493   244.4  4600.3  243.63  4685.1  241.43
    4714  241.32  4771.6  239.78    4778  240.05  4792.4  239.63  4806.8  238.43
  4856.4  237.02  4988.6  235.89  4991.3  235.39  4994.6  235.89  5049.4  236.95
  5059.4  237.33  5094.3  240.55    5126  242.69  5131.6  242.54  5148.2  243.59
  5153.8  243.21  5170.4  243.93    5176  243.69  5192.6  244.74  5259.2  246.62
  5296.6  246.77  5303.7   247.4  5309.3     247  5325.9  248.09  5436.9  248.85
#Mann= 3 ,-1 , 0
  4478.9     .05       0  4988.6     .03       0  4994.6     .05       0
Bank Sta=4856.4,5049.4
XS Rating Curve= 0 ,0
Exp/Cntr=0.3,0.1

Type RM Length L Ch R = 1 ,6053    ,510,510,510
BEGIN DESCRIPTION:
UNT067 IN GIBB 10.0
END DESCRIPTION:
XS GIS Cut Line= 3
      3630018.05     10196428.31      3629405.05     10196450.46
      3628778.03     10197030.99
#Sta/Elev= 30
  4160.2   236.4  4216.2  234.67  4286.2  234.24  4326.3  233.41  4366.3   233.5
  4446.3  231.53  4576.4  231.49  4606.4  232.74  4626.4  231.75  4664.6   231.1
  4669.6  231.71  4766.5  229.61  4797.7  229.68  4868.6  227.13  4917.9  227.56
    5000  226.25  5002.7  225.75    5006  226.25  5031.3   227.4  5052.3  228.78
  5080.7  229.62  5257.6  231.93  5314.3  231.64  5335.8  231.08    5350  231.46
  5385.1  230.62  5448.6  231.35  5491.1  231.03  5512.7  230.33  5628.1  230.56
#Mann= 3 ,-1 , 0
  4160.2      .1       0    5000     .05       0    5006      .1       0
Bank Sta=4917.9,5031.3
XS Rating Curve= 0 ,0
Exp/Cntr=0.3,0.1

Type RM Length L Ch R = 1 ,5543    ,687,687,687
BEGIN DESCRIPTION:
UNT067 IN GIBB 9.0
END DESCRIPTION:
XS GIS Cut Line= 3
       3629844.4     10196011.65      3628821.72     10196226.51
      3627919.15     10196497.21
#Sta/Elev= 30
  4154.2  244.24  4230.2  242.42  4274.9  238.49  4340.5  237.28  4369.5  237.64
  4519.1  234.88  4575.5  232.49  4595.9  232.62  4618.9  230.38  4668.7  230.49
  4790.1  223.75  4912.9  222.29  4994.5  219.51  5219.7  219.41    5251  218.23
  5279.3  215.95  5282.1  215.45  5285.3  215.95  5334.1  217.72  5377.6  216.61
  5405.5  217.34  5443.7  219.65  5459.8  218.89  5509.9  219.02  5553.8  220.37
  5690.9  221.59  5751.8  223.54    5867   225.1  5927.5  223.45  6141.5  225.46
#Mann= 3 ,-1 , 0
  4154.2      .1       0  5279.3      .5       0  5285.3      .1       0
Bank Sta=5251,5334.1
XS Rating Curve= 0 ,0
Exp/Cntr=0.3,0.1

Type RM Length L Ch R = 1 ,4856    ,1699,1699,1699
BEGIN DESCRIPTION:
UNT067 IN GIBB 8.0
END DESCRIPTION:
XS GIS Cut Line= 3
      3629757.59     10195733.87       3628899.4     10195671.85
      3628229.84     10195508.17
#Sta/Elev= 30
  4093.8   238.2  4239.7  233.87  4333.8  232.54  4440.2  228.01  4500.3  229.01
  4607.9  222.89  4720.9  218.06  4747.5  216.34  4851.2  216.11  4941.5  213.86
  4961.7  212.75  4999.9  212.38  5002.7  211.88  5005.9  212.38  5018.3  214.17
  5054.4   217.6  5143.2  219.96  5198.5  223.82  5291.2  223.25  5332.3  224.66
  5372.8  225.13    5425  225.83  5434.8  225.61  5445.6  224.25  5466.2  223.73
  5507.3  224.55  5523.2  225.71  5558.8  225.04  5592.8  225.31  5643.5  224.73
#Mann= 5 ,-1 , 0
  4093.8      .1       0  4999.9     .05       0  5005.9      .1       0
  5372.8     .08       0  5592.8     .05       0
Bank Sta=4941.5,5018.3
XS Rating Curve= 0 ,0
Exp/Cntr=0.3,0.1

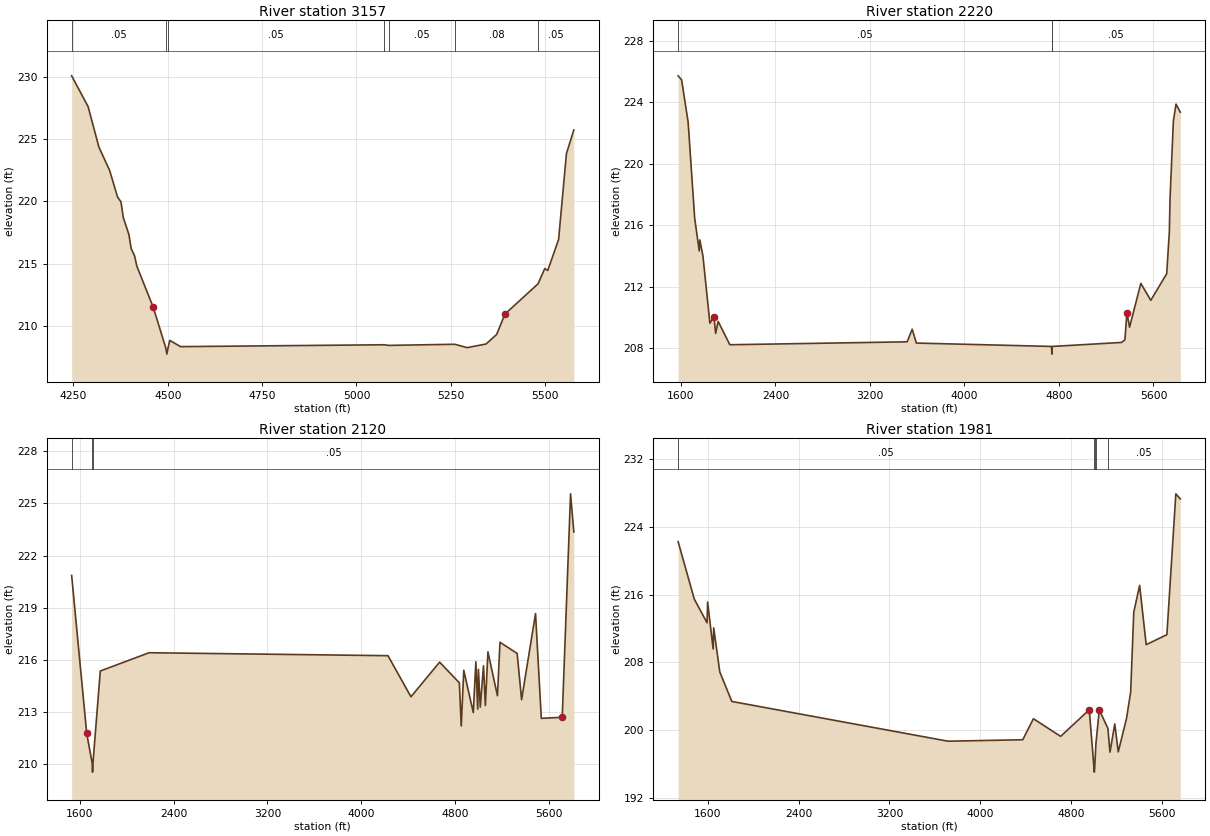
Type RM Length L Ch R = 1 ,3157    ,937,937,937
BEGIN DESCRIPTION:
UNT067 IN GIBB 7.0
END DESCRIPTION:
XS GIS Cut Line= 3
      3630292.08     10194941.61      3629892.11     10194341.64
      3629503.98      10193872.3
#Sta/Elev= 30
  4245.6  230.06  4289.1   227.6  4317.7  224.36  4346.2  222.48  4367.2  220.35
  4376.3  219.96  4382.3  218.71  4397.3  217.34  4403.3  216.22  4412.3  215.63
  4418.3  214.81  4461.9   211.5  4494.9  208.26  4497.7  207.76  4500.9  208.26
  4505.5  208.86    4534  208.36  5072.9  208.51  5085.4  208.46  5260.4  208.55
    5293  208.28    5343  208.57  5371.1  209.33  5393.3  210.97  5480.8  213.39
  5498.8  214.62  5506.6  214.46  5535.3  216.94  5556.1  223.83  5575.7  225.72
#Mann= 7 ,-1 , 0
  4245.6     .05       0  4494.9    .033       0  4500.9     .05       0
  5072.9     .08       0  5085.4     .05       0  5260.4     .08       0
  5480.8     .05       0
Bank Sta=4461.9,5393.3
XS Rating Curve= 0 ,0
Exp/Cntr=0.3,0.1

Type RM Length L Ch R = 1 ,2220    ,100,100,100
BEGIN DESCRIPTION:
UNT067 IN GIBB 5.0
END DESCRIPTION:
XS GIS Cut Line= 4
      3632675.73     10196020.98      3632647.96     10195750.18
      3630884.07     10193805.73       3629668.8     10193208.52
#Sta/Elev= 30
  1575.6  225.72  1605.1  225.46  1660.3  222.72  1715.7  216.47  1754.5  214.33
  1759.5  215.05    1786  213.99  1844.6  209.63  1879.2  210.05  1893.4  208.97
  1914.4  209.75  2013.7  208.23  3514.7  208.42  3557.2  209.24  3592.4  208.34
  4737.1  208.12  4739.9  207.62  4743.1  208.12  5330.2  208.38  5358.2  208.55
  5375.1  210.32  5397.6  209.37  5493.1  212.22  5577.4  211.12  5712.1  212.85
  5734.4  215.57  5740.4  217.75  5768.4  222.77  5790.9  223.88  5827.2  223.35
#Mann= 3 ,-1 , 0
  1575.6     .05       0  4737.1    .033       0  4743.1     .05       0
Bank Sta=1879.2,5375.1
XS Rating Curve= 0 ,0
Exp/Cntr=0.3,0.1

Type RM Length L Ch R = 1 ,2120    ,139,139,139
BEGIN DESCRIPTION:
UNT067 IN GIBB 4.0
END DESCRIPTION:
XS GIS Cut Line= 4
      3632752.12     10195979.33      3632724.34     10195708.51
      3630960.46     10193764.07      3629746.15       10193091.
#Sta/Elev= 30
  1529.4  220.86  1657.8  211.79    1705  210.06  1707.8  209.56    1711  210.06
    1774  215.37  2190.1  216.42    4229  216.25  4425.2  213.89    4670  215.88
  4838.3  214.69  4854.3  212.21    4876  215.41  4957.3  212.98  4979.1   215.9
  4995.1  213.18  5000.8  215.47  5016.8   213.3  5044.3  215.67  5060.3  213.39
  5082.1  216.47  5163.4  213.95  5185.1  217.02  5331.6  216.38  5369.4  213.72
  5488.4  218.67  5537.7  212.65  5716.2  212.71  5787.2  225.55  5815.3  223.36
#Mann= 3 ,-1 , 0
  1529.4     .05       0    1705    .033       0    1711     .05       0
Bank Sta=1657.8,5716.2
XS Rating Curve= 0 ,0
Exp/Cntr=0.3,0.1

Type RM Length L Ch R = 1 ,1981    ,0,0,0
BEGIN DESCRIPTION:
UNT067 IN GIBB 1.0
END DESCRIPTION:
XS GIS Cut Line= 4
       3632842.4     10196076.54      3632752.12     10195576.57
      3631009.07     10193680.73      3629884.11     10192965.48
#Sta/Elev= 30
  1341.2  222.25  1483.4  215.47  1595.6  212.67  1600.7  215.12  1649.2  209.59
  1654.2  212.07  1707.8  206.87  1813.6  203.39  3714.3   198.7  4372.1  198.87
    4466  201.35  4705.4  199.27  4957.1  202.41  4998.7  195.55  5001.4  195.05
  5004.7  195.55  5015.4  198.38  5045.2  202.38  5120.9  200.22  5139.2  197.41
  5181.5  200.73    5212  197.44  5284.9   201.4  5321.3  204.52  5348.4  213.91
    5400  217.09  5457.6  210.09  5639.7  211.27  5718.4  227.89  5757.7  227.29
#Mann= 5 ,-1 , 0
  1341.2     .05       0  4998.7     .03       0  5004.7     .05       0
  5015.4     .12       0  5120.9     .05       0
Bank Sta=4957.1,5045.2
XS Rating Curve= 0 ,0
Exp/Cntr=0.3,0.1

Chan Stop Cuts=-1
Use User Specified Reach Order=0
Composite Channel Slope=5