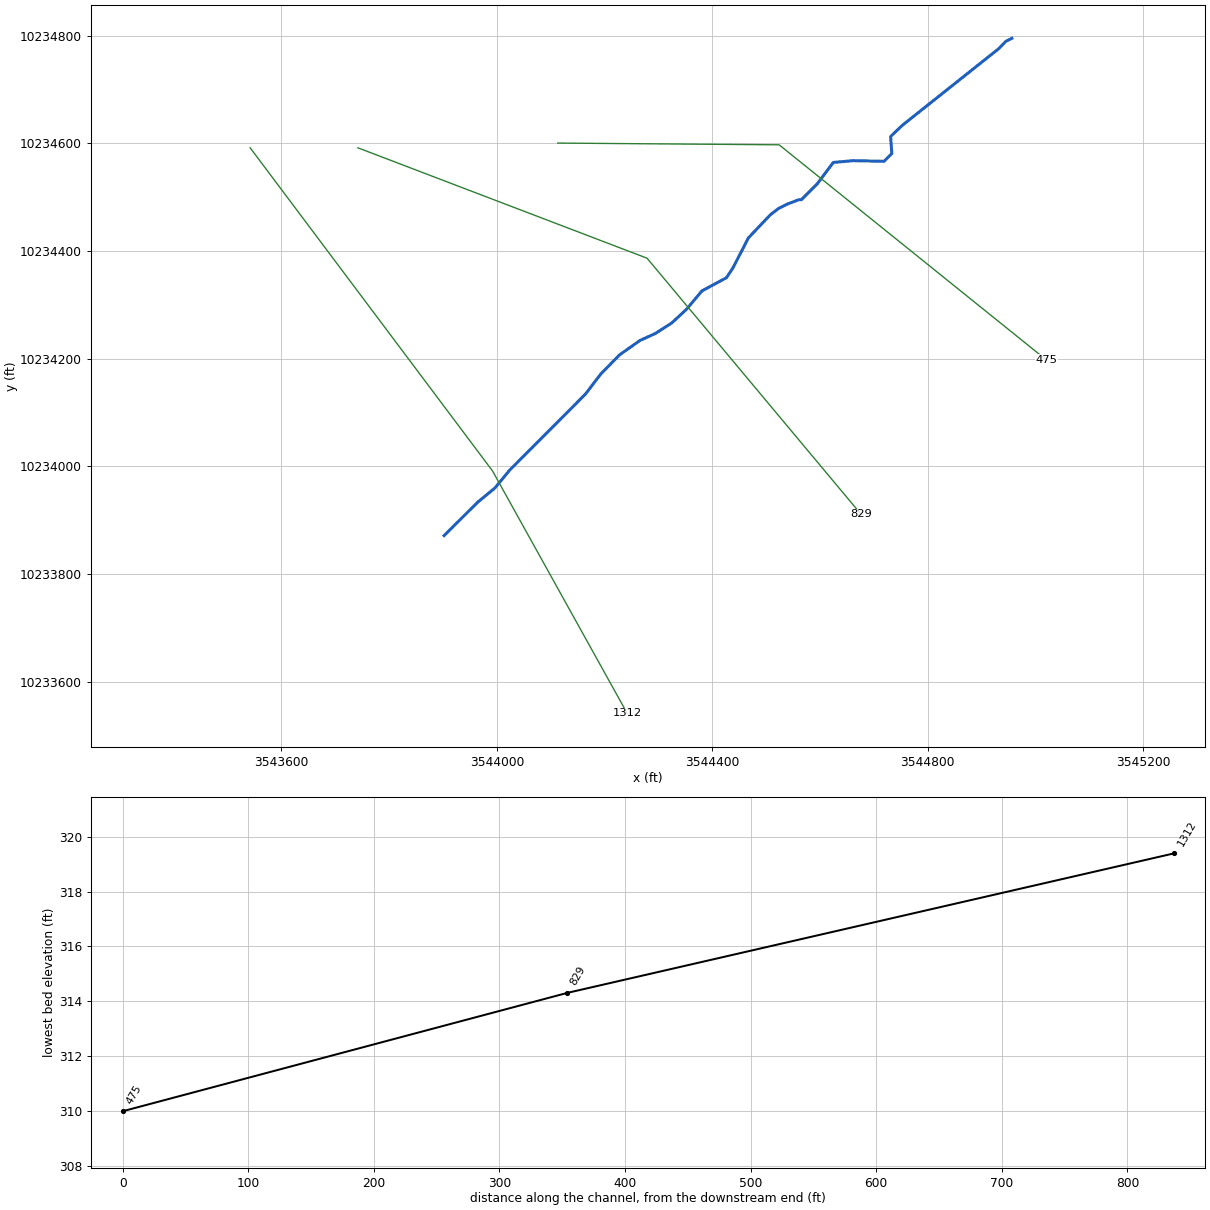
--- UNT074 IN GIBB.prj (project) ---

Proj Title=UNT074 IN GIBB Base Level Engineering
Current Plan=p01
Default Exp/Contr=0.3,0.1
English Units
Geom File=g01
Flow File=f01
Plan File=p01
BEGIN DESCRIPTION:
UNT074 IN GIBB
END DESCRIPTION:

--- UNT074 IN GIBB.p01 (plan) ---

Plan Title=Multiple Run
Short Identifier=Multiple
Geom File=g01
Flow File=f01
Subcritical Flow
K Sum by GR= 0
Std Step Tol= 0.01
Critical Tol= 0.01
Num of Std Step Trials= 20
Max Error Tol= 0.3
Flow Tol Ratio= 0.001
Split Flow NTrial= 30
Split Flow Tol= 0.02
Split Flow Ratio= 0.02
Log Output Level= 0
Friction Slope Method= 1
Unsteady Friction Slope Method= 2
Unsteady Bridges Friction Slope Method= 1
Parabolic Critical Depth
Global Vel Dist=  1 , 1 , 1
Global Log Level= 0
CheckData=True
Encroach Param= -1, 0, 0, 0
BEGIN DESCRIPTION:
Multiple Run
END DESCRIPTION:

--- UNT074 IN GIBB.f01 (steady flow) ---

Flow Title=Multiple
Number of Profiles=7
Profile Names=10-year,25-year,50-year,1pct_min,100-year,1pct_plu,500-year
River Rch & RM= UNT074 IN GIBB,Reach-1,1312
     261     335     393     338     457     618     620
Boundary for River Rch & Prof#=UNT074 IN GIBB,Reach-1,1
Up Type=0
Dn Type=3
Dn Slope=0.005
Boundary for River Rch & Prof#=UNT074 IN GIBB,Reach-1,2
Up Type=0
Dn Type=3
Dn Slope=0.005
Boundary for River Rch & Prof#=UNT074 IN GIBB,Reach-1,3
Up Type=0
Dn Type=3
Dn Slope=0.005
Boundary for River Rch & Prof#=UNT074 IN GIBB,Reach-1,4
Up Type=0
Dn Type=3
Dn Slope=0.005
Boundary for River Rch & Prof#=UNT074 IN GIBB,Reach-1,5
Up Type=0
Dn Type=3
Dn Slope=0.005
Boundary for River Rch & Prof#=UNT074 IN GIBB,Reach-1,6
Up Type=0
Dn Type=3
Dn Slope=0.005
Boundary for River Rch & Prof#=UNT074 IN GIBB,Reach-1,7
Up Type=0
Dn Type=3
Dn Slope=0.005

--- UNT074 IN GIBB.g01 (geometry) ---

Geom Title=Existing Conditions

River Reach=UNT074 IN GIBB,Reach-1
Reach XY= 30
      3543902.11     10233871.64      3543964.91     10233934.03
      3543996.59     10233960.14      3544023.39     10233992.69
      3544164.25     10234134.09      3544193.33     10234172.06
      3544227.98     10234207.36      3544265.85     10234233.96
      3544294.60     10234247.05      3544324.88     10234266.51
      3544352.02     10234291.70      3544380.83     10234325.96
      3544426.43     10234350.51      3544438.23     10234368.41
      3544467.22     10234424.56      3544507.93     10234467.38
      3544523.15     10234478.97      3544539.25     10234487.09
      3544560.57     10234495.30      3544565.43     10234495.30
      3544595.06     10234524.93      3544624.69     10234564.44
      3544660.90     10234567.73      3544719.06     10234566.63
      3544733.33     10234580.90      3544731.14     10234612.72
      3544753.08     10234633.57      3544932.17     10234775.94
      3544944.81     10234789.23      3544956.11     10234794.89

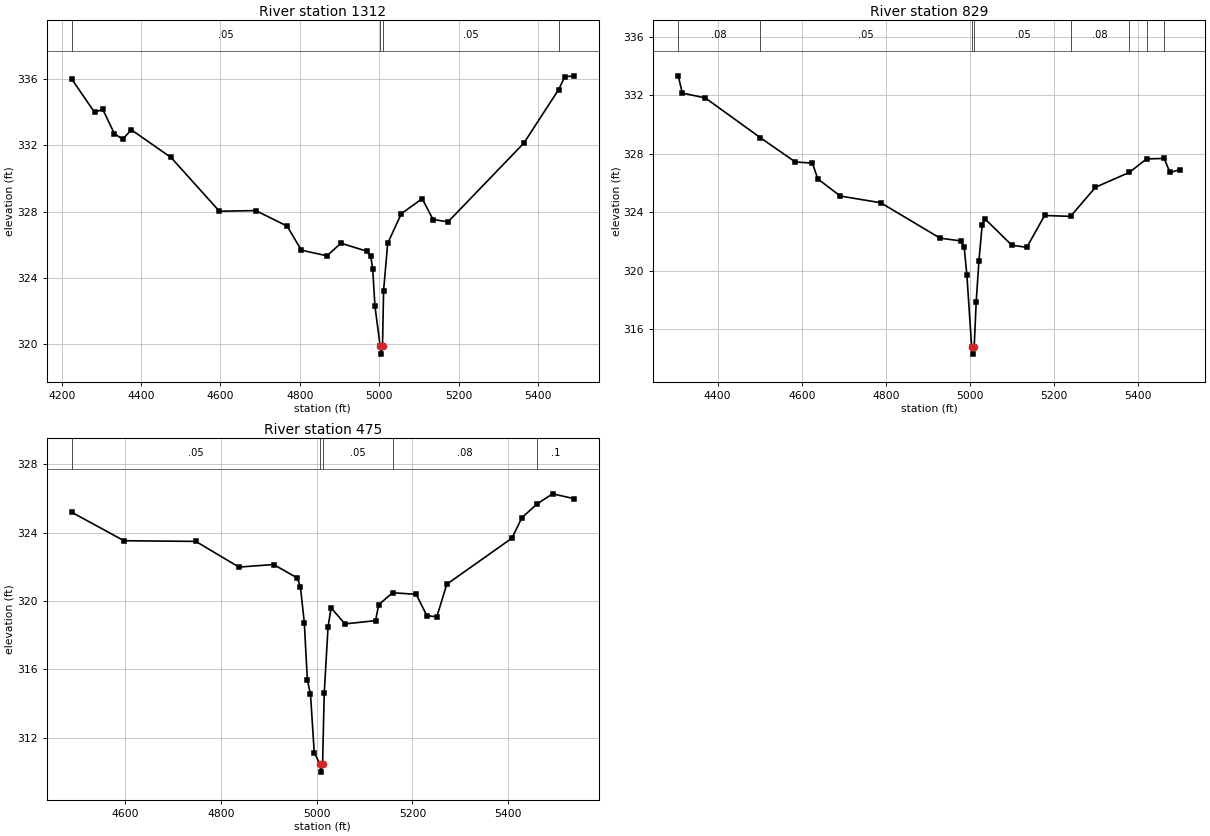
Type RM Length L Ch R = 1,1312,483,483,483
BEGIN DESCRIPTION:
UNT074 IN GIBB 12.0
END DESCRIPTION:
XS GIS Cut Line= 3
      3543542.08     10234591.67      3543992.11     10233991.64
      3544242.10     10233541.66
#Sta/Elev= 30
  4225.4  336.00  4282.7  334.00  4303.6  334.17  4332.7  332.71  4353.6  332.37
  4375.4  332.94  4475.4  331.27  4597.3  328.02  4689.0  328.06  4768.1  327.12
  4803.6  325.67  4868.1  325.33  4903.6  326.09  4968.1  325.61  4978.3  325.33
  4983.4  324.56  4989.2  322.28  5002.2  319.89  5004.9  319.39  5008.2  319.89
  5010.9  323.22  5021.2  326.08  5055.5  327.87  5108.1  328.78  5135.6  327.52
  5173.3  327.38  5364.4  332.14  5451.6  335.36  5467.3  336.14  5490.2  336.20
#Mann=4,-1,0
  4225.4    0.05       0  5002.2    0.04       0  5008.2    0.05       0
  5451.6    0.08       0
Bank Sta=5002.2,5008.2
Exp/Cntr=0.3,0.1

Type RM Length L Ch R = 1,829,354,354,354
BEGIN DESCRIPTION:
UNT074 IN GIBB 11.0
END DESCRIPTION:
XS GIS Cut Line= 3
      3543742.07     10234591.65      3544278.93     10234386.72
      3544676.07     10233911.45
#Sta/Elev= 30
  4306.2  333.34  4315.9  332.16  4370.5  331.83  4501.0  329.12  4584.5  327.45
  4625.3  327.37  4638.1  326.29  4691.6  325.12  4787.9  324.66  4928.9  322.24
  4978.7  322.05  4986.2  321.63  4992.7  319.69  5004.0  314.81  5006.8  314.31
  5010.0  314.81  5014.8  317.90  5021.3  320.69  5029.1  323.16  5035.6  323.56
  5099.4  321.76  5135.1  321.61  5177.5  323.79  5239.1  323.73  5298.5  325.72
  5379.1  326.74  5420.1  327.66  5461.9  327.69  5475.5  326.73  5500.2  326.93
#Mann=8,-1,0
  4306.2    0.08       0  4501.0    0.05       0  5004.0    0.04       0
  5010.0    0.05       0  5239.1    0.08       0  5379.1    0.05       0
  5420.1    0.08       0  5461.9     0.1       0
Bank Sta=5004,5010
Exp/Cntr=0.3,0.1

Type RM Length L Ch R = 1,475,0,0,0
BEGIN DESCRIPTION:
UNT074 IN GIBB 10.0
END DESCRIPTION:
XS GIS Cut Line= 3
      3544113.12     10234600.42      3544524.15     10234597.22
      3545020.40     10234197.74
#Sta/Elev= 30
  4488.8  325.18  4597.8  323.52  4747.8  323.48  4837.8  321.98  4910.1  322.13
  4959.8  321.34  4966.2  320.80  4974.2  318.74  4980.6  315.38  4987.1  314.56
  4995.0  311.14  5006.4  310.50  5009.1  310.00  5012.4  310.50  5015.8  314.60
  5023.8  318.48  5030.2  319.60  5059.0  318.66  5123.0  318.85  5129.4  319.78
  5158.5  320.48  5207.7  320.39  5230.1  319.14  5250.9  319.08  5271.7  320.98
  5407.7  323.67  5428.5  324.87  5460.6  325.68  5492.5  326.26  5536.9  325.98
#Mann=5,-1,0
  4488.8    0.05       0  5006.4    0.04       0  5012.4    0.05       0
  5158.5    0.08       0  5460.6     0.1       0
Bank Sta=5006.4,5012.4
Exp/Cntr=0.3,0.1

Chan Stop Cuts=-1