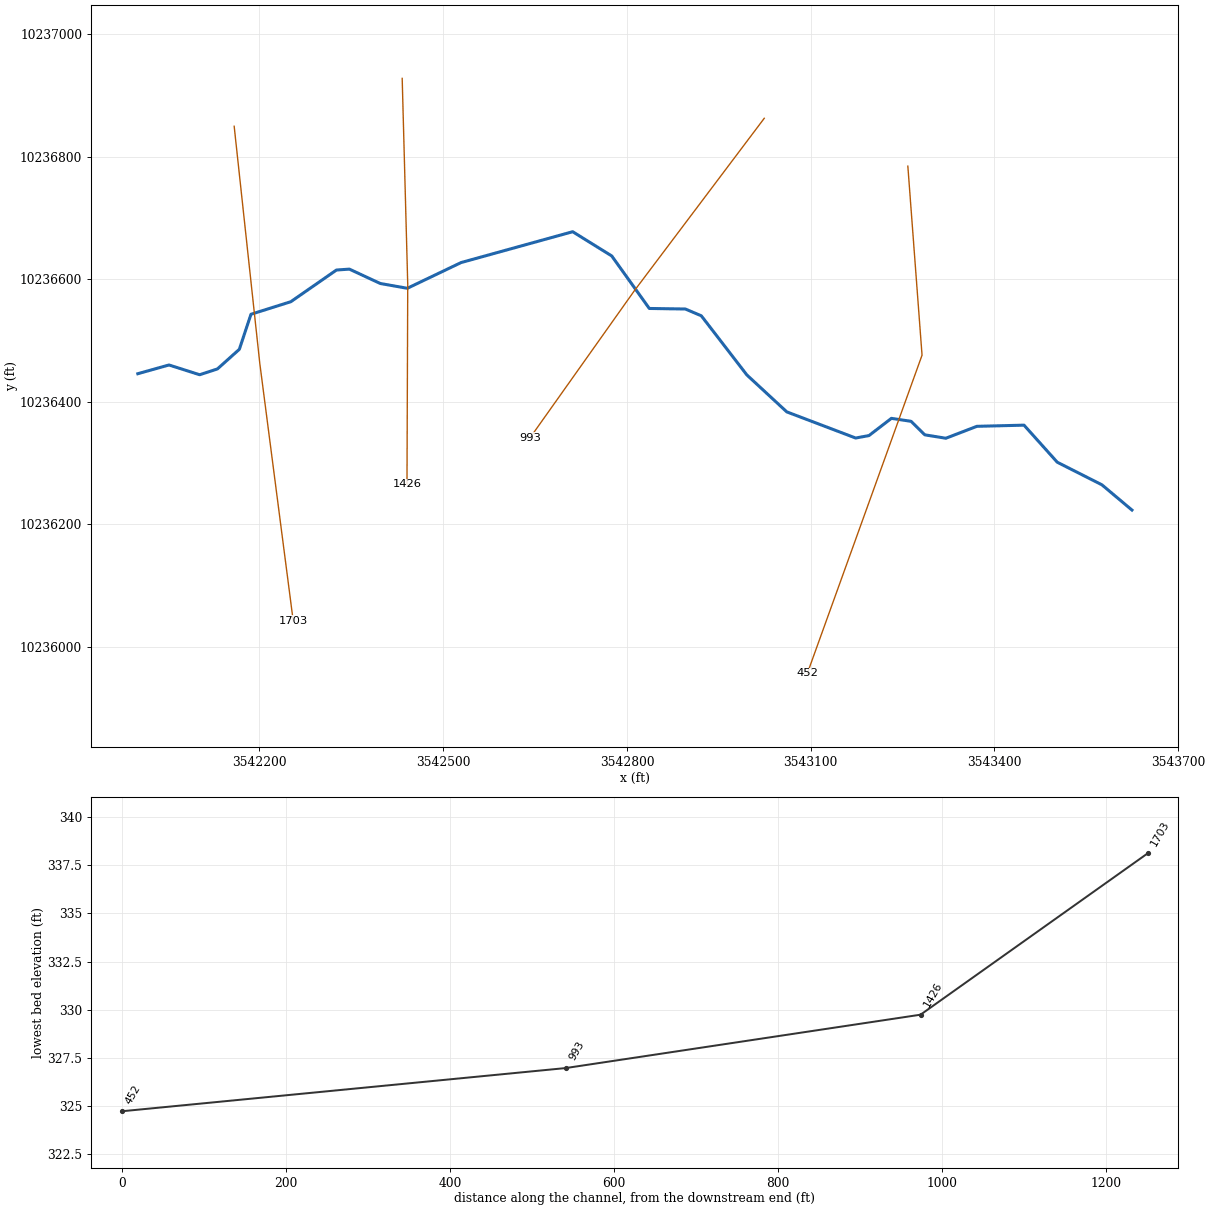
--- UNT075 IN GIBB.prj (project) ---

Proj Title=UNT075 IN GIBB Base Level Engineering
Current Plan=p01
Default Exp/Contr=0.3,0.1
English Units
Geom File=g01
Flow File=f01
Plan File=p01
BEGIN DESCRIPTION:
UNT075 IN GIBB
END DESCRIPTION:

--- UNT075 IN GIBB.p01 (plan) ---

Plan Title=Multiple Run
Short Identifier=Multiple
Geom File=g01
Flow File=f01
Subcritical Flow
K Sum by GR= 0
Std Step Tol= 0.01
Critical Tol= 0.01
Num of Std Step Trials= 20
Max Error Tol= 0.3
Flow Tol Ratio= 0.001
Split Flow NTrial= 30
Split Flow Tol= 0.02
Split Flow Ratio= 0.02
Log Output Level= 0
Friction Slope Method= 1
Unsteady Friction Slope Method= 2
Unsteady Bridges Friction Slope Method= 1
Parabolic Critical Depth
Global Vel Dist=  1 , 1 , 1
Global Log Level= 0
CheckData=True
Encroach Param= -1, 0, 0, 0
BEGIN DESCRIPTION:
Multiple Run
END DESCRIPTION:

--- UNT075 IN GIBB.f01 (steady flow) ---

Flow Title=Multiple
Number of Profiles=7
Profile Names=10-year,25-year,50-year,1pct_min,100-year,1pct_plu,500-year
River Rch & RM= UNT075 IN GIBB,Reach-1,1703
     205     259     300     256     346     467     459
Boundary for River Rch & Prof#=UNT075 IN GIBB,Reach-1,1
Up Type=0
Dn Type=3
Dn Slope=0.005
Boundary for River Rch & Prof#=UNT075 IN GIBB,Reach-1,2
Up Type=0
Dn Type=3
Dn Slope=0.005
Boundary for River Rch & Prof#=UNT075 IN GIBB,Reach-1,3
Up Type=0
Dn Type=3
Dn Slope=0.005
Boundary for River Rch & Prof#=UNT075 IN GIBB,Reach-1,4
Up Type=0
Dn Type=3
Dn Slope=0.005
Boundary for River Rch & Prof#=UNT075 IN GIBB,Reach-1,5
Up Type=0
Dn Type=3
Dn Slope=0.005
Boundary for River Rch & Prof#=UNT075 IN GIBB,Reach-1,6
Up Type=0
Dn Type=3
Dn Slope=0.005
Boundary for River Rch & Prof#=UNT075 IN GIBB,Reach-1,7
Up Type=0
Dn Type=3
Dn Slope=0.005

--- UNT075 IN GIBB.g01 (geometry) ---

Geom Title=Existing Conditions

River Reach=UNT075 IN GIBB,Reach-1
Reach XY= 30
      3542001.44     10236445.82      3542052.32     10236460.08
      3542102.40     10236444.15      3542131.36     10236453.60
      3542167.16     10236485.61      3542186.17     10236542.85
      3542251.22     10236563.37      3542325.74     10236615.10
      3542346.78     10236616.58      3542397.29     10236593.11
      3542441.43     10236585.29      3542529.19     10236627.27
      3542711.40     10236677.65      3542775.16     10236638.07
      3542836.49     10236552.34      3542895.35     10236551.47
      3542921.39     10236540.36      3542995.80     10236443.77
      3543060.90     10236383.53      3543173.40     10236340.82
      3543195.10     10236344.82      3543231.73     10236372.94
      3543263.85     10236368.08      3543286.25     10236346.03
      3543320.62     10236340.48      3543371.32     10236359.92
      3543448.23     10236361.83      3543502.50     10236301.33
      3543575.41     10236264.44      3543624.46     10236223.21

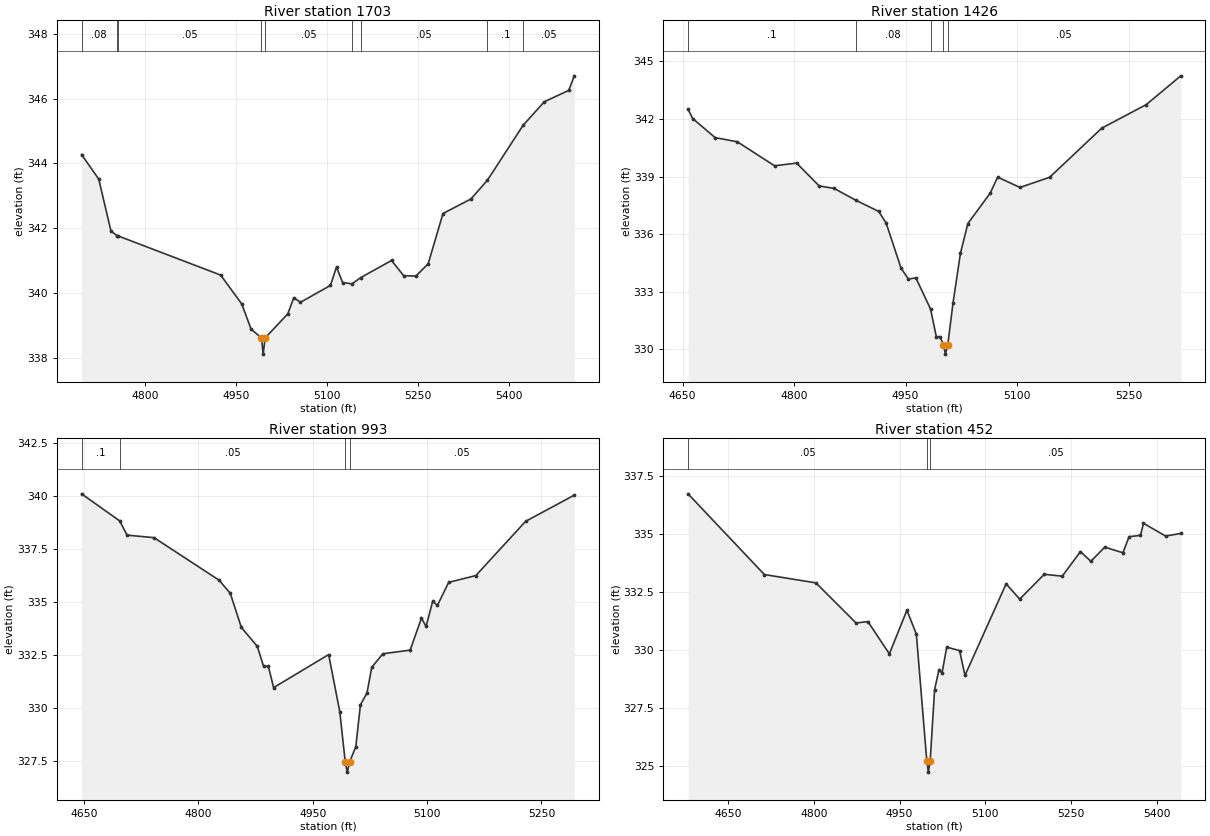
Type RM Length L Ch R = 1,1703,277,277,277
BEGIN DESCRIPTION:
UNT075 IN GIBB 8.0
END DESCRIPTION:
XS GIS Cut Line= 3
      3542158.74     10236849.84      3542200.61     10236462.48
      3542255.10     10236042.52
#Sta/Elev= 30
  4694.5  344.27  4722.9  343.51  4743.0  341.91  4752.8  341.77  4754.6  341.76
  4924.0  340.55  4958.8  339.66  4974.3  338.88  4991.4  338.61  4994.2  338.11
  4997.4  338.61  5034.7  339.35  5044.7  339.85  5055.7  339.71  5105.1  340.23
  5115.2  340.80  5125.3  340.32  5140.8  340.28  5154.9  340.47  5206.0  341.00
  5226.1  340.53  5246.3  340.52  5266.5  340.90  5290.9  342.45  5337.1  342.90
  5364.3  343.48  5423.0  345.17  5458.1  345.90  5498.4  346.25  5507.6  346.70
#Mann=9,-1,0
  4694.5    0.08       0  4752.8     0.1       0  4754.6    0.05       0
  4991.4    0.04       0  4997.4    0.05       0  5140.8    0.08       0
  5154.9    0.05       0  5364.3     0.1       0  5423.0    0.05       0
Bank Sta=4991.4,4997.4
Exp/Cntr=0.3,0.1

Type RM Length L Ch R = 1,1426,433,433,433
BEGIN DESCRIPTION:
UNT075 IN GIBB 7.0
END DESCRIPTION:
XS GIS Cut Line= 3
      3542433.05     10236928.02      3542442.11     10236591.64
      3542440.87     10236265.25
#Sta/Elev= 30
  4657.3  342.51  4663.7  342.02  4693.7  341.03  4723.7  340.81  4773.7  339.56
  4803.4  339.70  4833.7  338.51  4853.8  338.38  4882.7  337.77  4913.8  337.18
  4923.8  336.58  4943.8  334.23  4953.8  333.65  4963.8  333.72  4983.6  332.09
  4991.3  330.65  4996.3  330.65  5000.8  330.24  5003.6  329.74  5006.8  330.24
  5013.8  332.41  5023.8  335.00  5033.8  336.55  5063.8  338.13  5073.8  338.97
  5103.8  338.43  5143.8  338.96  5213.8  341.52  5273.8  342.75  5320.2  344.25
#Mann=5,-1,0
  4657.3     0.1       0  4882.7    0.08       0  4983.6    0.05       0
  5000.8    0.04       0  5006.8    0.05       0
Bank Sta=5000.8,5006.8
Exp/Cntr=0.3,0.1

Type RM Length L Ch R = 1,993,541,541,541
BEGIN DESCRIPTION:
UNT075 IN GIBB 6.0
END DESCRIPTION:
XS GIS Cut Line= 3
      3543024.18     10236862.85      3542812.52     10236581.90
      3542642.11     10236341.65
#Sta/Elev= 30
  4646.9  340.11  4697.0  338.83  4706.6  338.16  4742.0  338.04  4827.4  336.03
  4842.0  335.41  4856.5  333.80  4877.4  332.91  4885.7  331.96  4891.9  331.97
  4898.8  330.96  4971.0  332.52  4985.6  329.82  4992.7  327.47  4995.4  326.97
  4998.7  327.47  5006.6  328.17  5012.7  330.15  5021.3  330.71  5027.5  331.92
  5042.2  332.56  5077.9  332.73  5092.7  334.24  5098.8  333.85  5107.5  335.04
  5113.6  334.84  5128.4  335.93  5164.0  336.25  5229.3  338.81  5293.2  340.05
#Mann=4,-1,0
  4646.9     0.1       0  4697.0    0.05       0  4992.7    0.04       0
  4998.7    0.05       0
Bank Sta=4992.7,4998.7
Exp/Cntr=0.3,0.1

Type RM Length L Ch R = 1,452,0,0,0
BEGIN DESCRIPTION:
UNT075 IN GIBB 5.0
END DESCRIPTION:
XS GIS Cut Line= 3
      3543258.57     10236784.74      3543281.76     10236476.05
      3543094.51     10235956.63
#Sta/Elev= 30
  4580.0  336.73  4713.5  333.25  4803.7  332.89  4873.9  331.16  4894.6  331.22
  4932.1  329.83  4962.8  331.71  4979.3  330.68  4997.5  325.23  5000.3  324.73
  5003.5  325.23  5011.2  328.29  5018.9  329.15  5024.2  329.00  5032.4  330.12
  5054.9  329.97  5064.3  328.90  5136.3  332.85  5160.0  332.19  5203.0  333.26
  5234.4  333.18  5266.3  334.24  5284.4  333.82  5308.8  334.43  5340.5  334.19
  5351.3  334.88  5371.2  334.94  5376.5  335.46  5415.1  334.91  5441.7  335.02
#Mann=3,-1,0
  4580.0    0.05       0  4997.5    0.04       0  5003.5    0.05       0
Bank Sta=4997.5,5003.5
Exp/Cntr=0.3,0.1

Chan Stop Cuts=-1