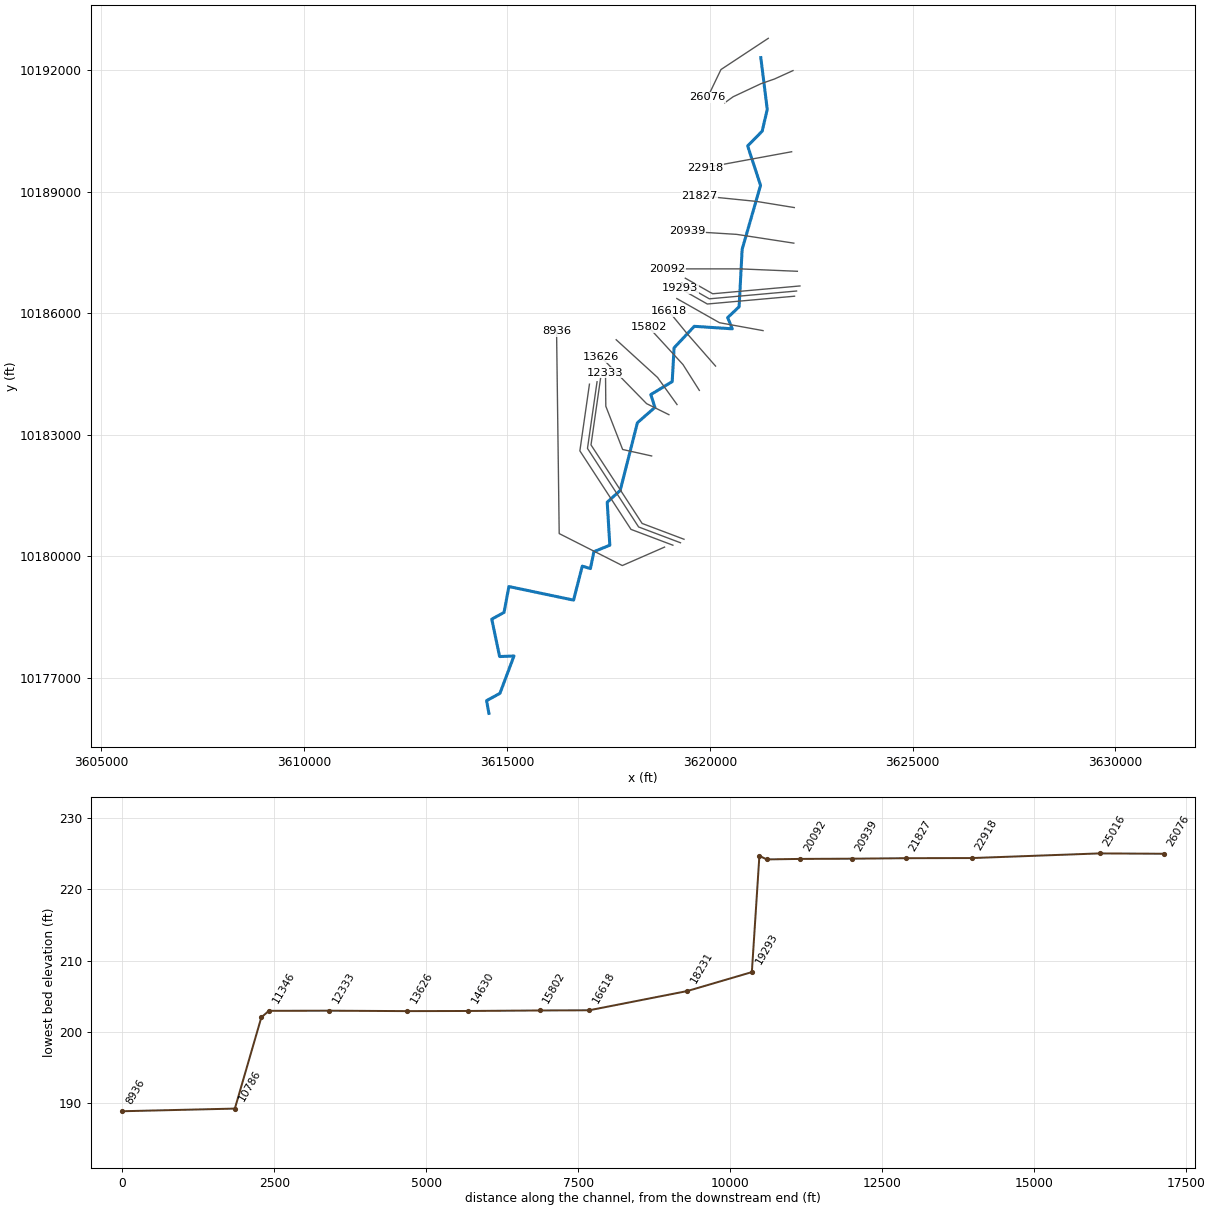
--- UNT101 IN GIBB.prj (project) ---

Proj Title=UNT101 IN GIBB Base Level Engineering
Current Plan=p01
Default Exp/Contr=0.3,0.1
English Units
Geom File=g01
Flow File=f01
Plan File=p01
Y Axis Title=Elevation
X Axis Title(PF)=Main Channel Distance
X Axis Title(XS)=Station
BEGIN DESCRIPTION:
UNT101 IN GIBB
END DESCRIPTION:
DSS Export Rating Curves= 0
DSS Export Rating Curve Sorted= 0
DSS Export Volume Flow Curves= 0
DXF OffsetX= 0
DXF OffsetY= 0
DXF ScaleX= 1
DXF ScaleY= 10

--- UNT101 IN GIBB.p01 (plan) ---

Plan Title=Multiple Run
Short Identifier=Multiple
Geom File=g01
Flow File=f01
Subcritical Flow
K Sum by GR= 0
Std Step Tol= 0.01
Critical Tol= 0.01
Num of Std Step Trials= 20
Max Error Tol= 0.3
Flow Tol Ratio= 0.001
Split Flow NTrial= 30
Split Flow Tol= 0.02
Split Flow Ratio= 0.02
Log Output Level= 0
Friction Slope Method= 1
Unsteady Friction Slope Method= 2
Unsteady Bridges Friction Slope Method= 1
Parabolic Critical Depth
Global Vel Dist=  1 , 1 , 1
Global Log Level= 0
CheckData=True
Encroach Param= -1, 0, 0, 0
BEGIN DESCRIPTION:
Multiple Run
END DESCRIPTION:

--- UNT101 IN GIBB.f01 (steady flow) ---

Flow Title=Multiple
Program Version=4.10
Number of Profiles= 7
Profile Names=10-year,25-year,50-year,1pct_min,100-year,1pct_plu,500-year
River Rch & RM=UNT101 IN GIBB,Reach-1         ,26076
     615     825     994     878    1188    1606    1698
River Rch & RM=UNT101 IN GIBB,Reach-1         ,22918
     943    1288    1572    1403    1897    2566    2770
River Rch & RM=UNT101 IN GIBB,Reach-1         ,19536
    1252    1731    2130    1915    2590    3503    3838
River Rch & RM=UNT101 IN GIBB,Reach-1         ,11346
    1287    1779    2188    1965    2658    3595    3932
Boundary for River Rch & Prof#=UNT101 IN GIBB,Reach-1         , 1
Up Type= 0
Dn Type= 3
Dn Slope=0.005
Boundary for River Rch & Prof#=UNT101 IN GIBB,Reach-1         , 2
Up Type= 0
Dn Type= 3
Dn Slope=0.005
Boundary for River Rch & Prof#=UNT101 IN GIBB,Reach-1         , 3
Up Type= 0
Dn Type= 3
Dn Slope=0.005
Boundary for River Rch & Prof#=UNT101 IN GIBB,Reach-1         , 4
Up Type= 0
Dn Type= 3
Dn Slope=0.005
Boundary for River Rch & Prof#=UNT101 IN GIBB,Reach-1         , 5
Up Type= 0
Dn Type= 3
Dn Slope=0.005
Boundary for River Rch & Prof#=UNT101 IN GIBB,Reach-1         , 6
Up Type= 0
Dn Type= 3
Dn Slope=0.005
Boundary for River Rch & Prof#=UNT101 IN GIBB,Reach-1         , 7
Up Type= 0
Dn Type= 3
Dn Slope=0.005
DSS Import GetInterval= 0
DSS Import GetPeak= 0
DSS Import FillOption= 0

--- UNT101 IN GIBB.g01 (geometry) ---

Geom Title=Existing Conditions
Program Version=4.10

River Reach=UNT101 IN GIBB  ,Reach-1
Reach XY= 30
      3621258.03     10192307.02      3621416.52     10191029.38
      3621292.11     10190491.64      3620933.88     10190126.61
      3621251.64     10189154.65      3620797.93     10187573.31
      3620723.18     10186156.53      3620440.89     10185888.47
      3620555.48     10185611.74       3619617.8     10185673.37
      3619119.54     10185142.12      3619073.53     10184307.92
      3618546.19     10183988.91      3618646.88      10183671.2
      3618215.02     10183292.51      3617790.54     10181619.76
      3617470.91     10181330.68      3617534.81     10180269.18
      3617141.83     10180108.96      3617056.76     10179692.29
      3616855.95      10179751.9      3616640.98     10178913.47
      3615046.39     10179248.63      3614926.89     10178609.97
       3614624.2      10178443.1      3614817.48     10177520.12
      3615171.52     10177533.57      3614825.43     10176611.09
       3614495.8     10176431.45      3614554.11     10176117.19

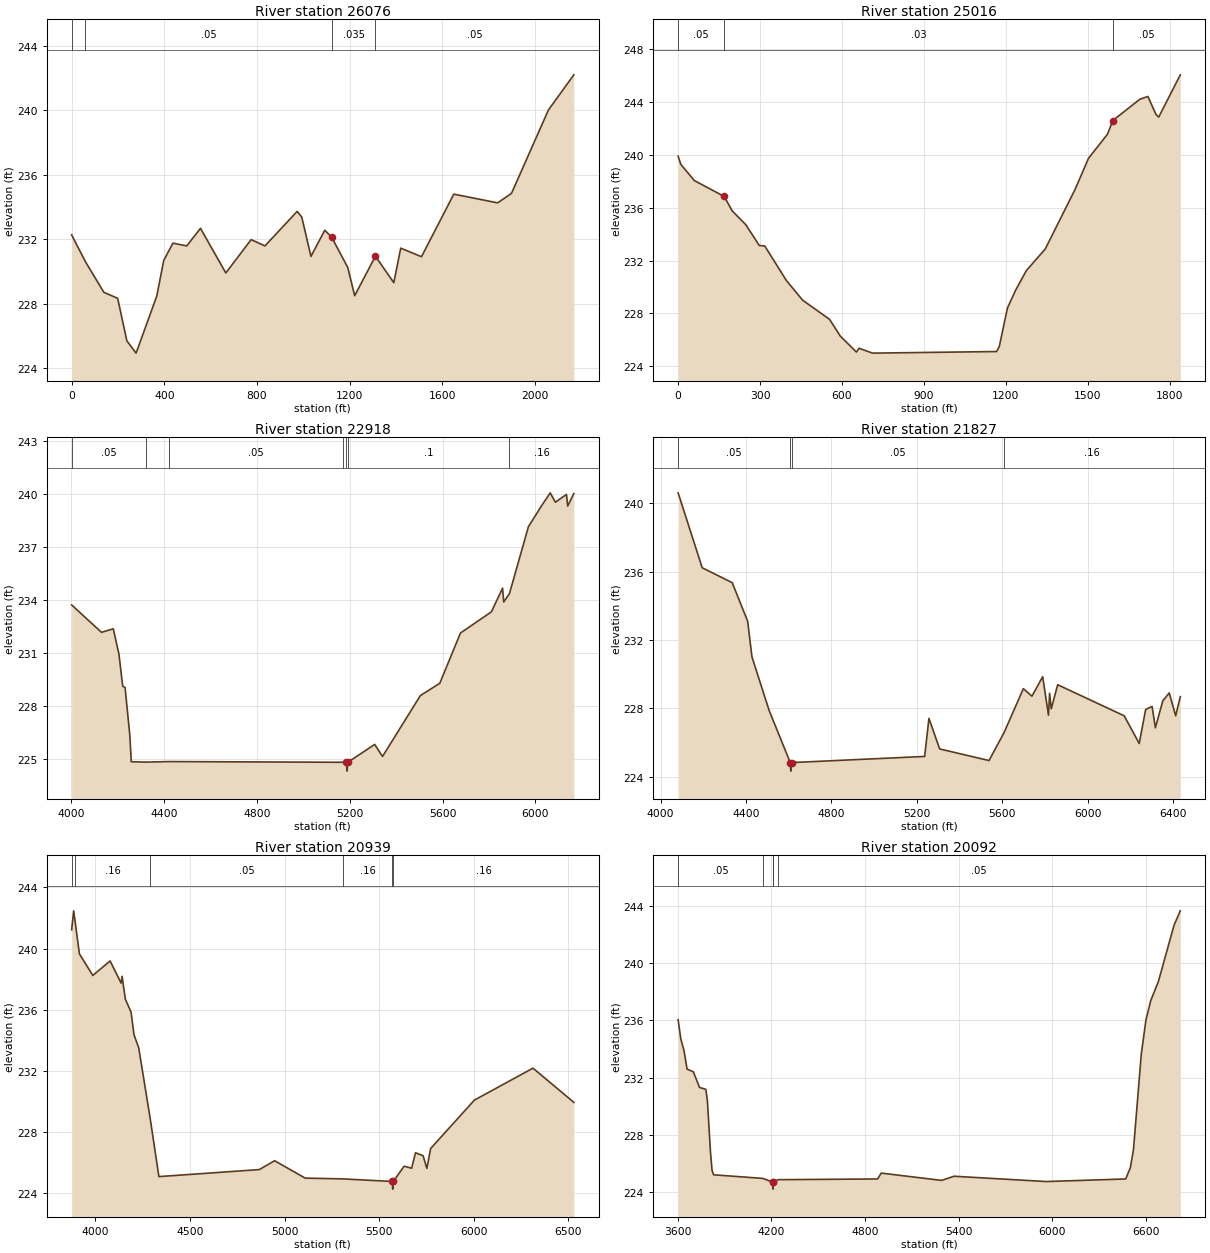
Type RM Length L Ch R = 1 ,26076   ,1060,1060,1060
BEGIN DESCRIPTION:
UNT101 IN GIBB 31.0
END DESCRIPTION:
XS GIS Cut Line= 3
      3621441.91    10192783.251     3620275.243    10192012.418
     3619948.854    10191331.862
#Sta/Elev= 30
       0  232.27   59.59  230.61  139.04  228.71  198.63  228.34  238.35   225.7
  278.08  224.94  367.46  228.48  397.25  230.68  436.98  231.76  496.57  231.59
  556.15  232.68   665.4  229.91  774.64  231.98  834.23  231.59  973.27  233.73
  993.13  233.38 1032.86  230.94 1092.45  232.56 1122.24  232.13 1191.76  230.25
 1221.55   228.5 1310.94  230.95 1390.39  229.31 1420.24  231.45  1509.9  230.92
 1649.38   234.8 1838.66  234.26 1898.44  234.85 2057.83  240.02 2167.42   242.2
#Mann= 4 ,-1 , 0
       0     .08       0   59.59     .05       0 1122.24    .035       0
 1310.94     .05       0
Bank Sta=1122.24,1310.94
XS Rating Curve= 0 ,0
Exp/Cntr=0.3,0.1

Type RM Length L Ch R = 1 ,25016   ,2098,2098,2098
XS GIS Cut Line= 5
     3622051.933     10191986.96     3621593.599    10191778.628
     3621263.738    10191664.043     3620576.238    10191341.116
     3620367.905    10191191.821
#Sta/Elev= 30
       0  239.91    9.91  239.29   59.46  238.06  168.46  236.86  198.19  235.76
  247.74  234.72  297.28  233.14   317.1  233.11  396.38  230.49  455.83     229
  554.42  227.55  593.72  226.28  652.67  225.07  662.49  225.36  711.62  224.99
 1165.85  225.11 1175.74  225.49 1205.44   228.4 1235.13  229.74 1274.73  231.24
 1344.02  232.88  1452.9  237.38 1502.39  239.75 1571.68  241.57 1591.48  242.61
 1690.23  244.22 1719.85  244.43 1749.47  243.06 1759.34  242.87 1838.33  246.07
#Mann= 3 ,-1 , 0
       0     .05       0  168.46     .03       0 1591.48     .05       0
Bank Sta=168.46,1591.48
XS Rating Curve= 0 ,0
Exp/Cntr=0.3,0.1

Type RM Length L Ch R = 1 ,22918   ,1091,1091,1091
BEGIN DESCRIPTION:
UNT101 IN GIBB 30.0
END DESCRIPTION:
XS GIS Cut Line= 2
      3622018.41     10189983.38       3619892.1     10189591.64
#Sta/Elev= 30
    4003  233.74  4131.4  232.19  4182.3  232.39  4206.7  230.95  4222.9  229.14
  4233.1  229.07  4253.5  226.36  4259.7  224.87  4324.2  224.85  4423.8  224.88
  5171.5  224.84  5185.9  224.84  5188.7  224.34  5191.9  224.84  5307.7  225.85
  5341.5  225.17  5504.2  228.61  5588.1  229.31    5677  232.15  5810.3  233.35
  5858.2  234.69  5863.3  233.91  5887.9  234.38  5969.4  238.16  6022.4  239.27
  6063.4  240.08  6085.6  239.55  6133.5  239.99  6138.6  239.33  6165.1  240.04
#Mann= 7 ,-1 , 0
    4003     .05       0  4324.2     .08       0  4423.8     .05       0
  5171.5      .1       0  5185.9    .033       0  5191.9      .1       0
  5887.9     .16       0
Bank Sta=5185.9,5191.9
XS Rating Curve= 0 ,0
Exp/Cntr=0.3,0.1

Type RM Length L Ch R = 1 ,21827   ,888,888,888
BEGIN DESCRIPTION:
UNT101 IN GIBB 29.0
END DESCRIPTION:
XS GIS Cut Line= 3
      3622083.53     10188605.35      3621150.39     10188757.25
      3619750.61     10188898.32
#Sta/Elev= 30
  4081.9  240.62  4194.8  236.23  4335.2  235.36  4407.6   233.1  4427.8  231.01
  4508.9  227.85  4607.2  224.82  4609.9  224.32  4613.2  224.82  5236.7  225.18
  5256.8  227.41    5307  225.62  5538.2  224.94  5608.8  226.58    5699  229.15
  5739.2  228.71  5789.5  229.85  5816.8   227.6  5821.9  228.88  5829.7  227.97
  5859.8  229.38  6171.4  227.56  6241.7  225.94  6271.9  227.93    6302  228.11
  6317.4  226.86  6352.3  228.44  6382.4   228.9  6412.5  227.56  6434.2  228.68
#Mann= 4 ,-1 , 0
  4081.9     .05       0  4607.2    .033       0  4613.2     .05       0
  5608.8     .16       0
Bank Sta=4607.2,4613.2
XS Rating Curve= 0 ,0
Exp/Cntr=0.3,0.1

Type RM Length L Ch R = 1 ,20939   ,847,847,847
BEGIN DESCRIPTION:
UNT101 IN GIBB 28.0
END DESCRIPTION:
XS GIS Cut Line= 3
      3622072.69     10187726.44       3620662.1     10187943.45
      3619436.54     10188019.37
#Sta/Elev= 30
  3874.3  241.23    3885  242.47  3893.5  241.69  3915.4  239.65  3986.2  238.24
  4077.6  239.19  4135.8  237.74  4140.9  238.18  4158.2  236.69  4188.5  235.83
  4204.1  234.35    4229   233.5    4290  228.84  4335.6  225.07  4866.8  225.53
  4947.4  226.11  5109.2  224.97  5309.3  224.92    5569  224.75  5571.8  224.25
    5575  224.75  5632.1  225.75  5671.9  225.62  5692.2  226.63  5732.3  226.44
  5752.3  225.61  5772.4  226.91  6003.9  230.08  6313.4  232.17  6529.4  229.93
#Mann= 6 ,-1 , 0
  3874.3     .05       0  3893.5     .16       0    4290     .05       0
  5309.3     .16       0    5569    .033       0    5575     .16       0
Bank Sta=5569,5575
XS Rating Curve= 0 ,0
Exp/Cntr=0.3,0.1

Type RM Length L Ch R = 1 ,20092   ,556,556,556
BEGIN DESCRIPTION:
UNT101 IN GIBB 27.0
END DESCRIPTION:
XS GIS Cut Line= 3
      3622159.53     10187031.99      3620742.11     10187091.64
      3618942.08     10187091.64
#Sta/Elev= 30
  3602.7  236.05  3620.1   234.7  3640.2  233.91  3660.2   232.6  3700.2  232.42
  3740.2  231.32  3780.3  231.19  3790.3  230.41  3810.3  226.78  3820.3  225.53
  3830.3  225.22  4145.1  224.97  4207.7  224.72  4210.4  224.22  4213.7  224.72
  4244.1  224.88  4881.3  224.93  4904.4  225.34  5291.4  224.83  5371.4  225.12
  5961.4  224.75  6471.4  224.93  6501.4  225.72  6521.4     227  6571.4  233.66
  6601.4  236.05  6631.4  237.37  6681.4  238.74  6781.4  242.66  6821.4  243.66
#Mann= 5 ,-1 , 0
  3602.7     .05       0  4145.1     .07       0  4207.7    .033       0
  4213.7     .07       0  4244.1     .05       0
Bank Sta=4207.7,4213.7
XS Rating Curve= 0 ,0
Exp/Cntr=0.3,0.1

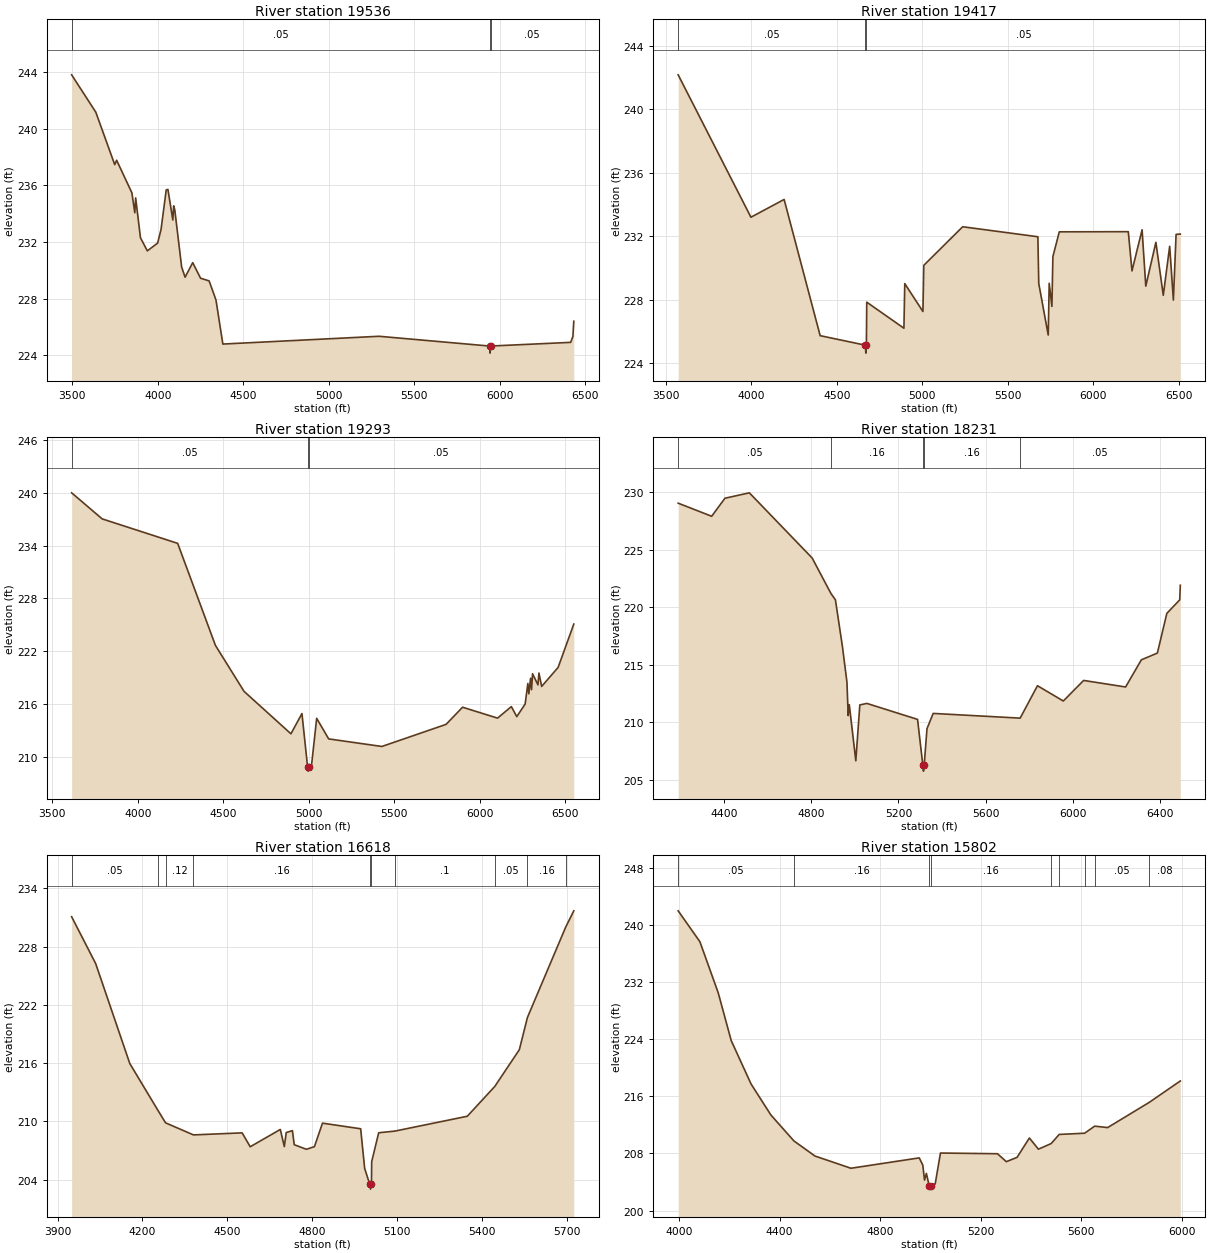
Type RM Length L Ch R = 1 ,19536   ,119,119,119
BEGIN DESCRIPTION:
UNT101 IN GIBB 26.0
END DESCRIPTION:
XS GIS Cut Line= 3
      3622222.95     10186669.79      3620071.88     10186477.07
      3619396.15     10186861.26
#Sta/Elev= 30
  3496.2   243.8  3637.6  241.16  3748.1  237.46  3759.3  237.77  3848.5  235.47
  3865.6  234.06  3870.6  235.11  3898.7   232.3  3938.8  231.37  3999.1  231.92
  4019.1  232.88  4049.3  235.67  4059.3  235.71  4088.1  233.55  4093.1  234.55
  4099.5  234.26  4139.6  230.23  4159.7  229.51  4204.4  230.54  4250.1  229.44
  4300.3  229.25  4340.4   227.9  4380.6  224.79  5294.2  225.34  5940.6  224.65
  5943.4  224.15  5946.6  224.65  6414.8  224.91    6428  225.32  6433.2   226.4
#Mann= 3 ,-1 , 0
  3496.2     .05       0  5940.6    .033       0  5946.6     .05       0
Bank Sta=5940.6,5946.6
XS Rating Curve= 0 ,0
Exp/Cntr=0.3,0.1

Type RM Length L Ch R = 1 ,19417   ,124,124,124
BEGIN DESCRIPTION:
UNT101 IN GIBB 25.0
END DESCRIPTION:
XS GIS Cut Line= 3
      3622139.55     10186544.78      3619988.54     10186352.07
      3619311.98     10186736.74
#Sta/Elev= 30
  3572.1  242.18  3997.9  233.21    4192  234.33  4402.9  225.75  4667.4  225.15
  4670.2  224.65  4673.4  225.15  4675.4  227.86  4892.9  226.22  4897.9  229.03
  5004.2  227.27  5009.2  230.18  5236.7  232.61  5676.7  231.98  5681.8  229.04
  5737.2  225.79  5742.9  229.05  5758.8  227.59  5764.5  230.73    5802  232.29
  6205.7   232.3  6227.3  229.83  6286.4  232.42    6308  228.87  6367.1  231.63
  6410.4  228.29  6447.8  231.38  6469.5  227.99  6485.3  232.13    6510  232.15
#Mann= 3 ,-1 , 0
  3572.1     .05       0  4667.4     .03       0  4673.4     .05       0
Bank Sta=4667.4,4673.4
XS Rating Curve= 0 ,0
Exp/Cntr=0.3,0.1

Type RM Length L Ch R = 1 ,19293   ,1062,1062,1062
BEGIN DESCRIPTION:
UNT101 IN GIBB 24.0
END DESCRIPTION:
XS GIS Cut Line= 3
      3622090.02     10186416.81      3619939.02      10186224.1
      3619262.36     10186608.82
#Sta/Elev= 30
  3613.6  239.99  3792.2  237.03    4234  234.25  4454.9  222.66  4622.3  217.44
  4896.6  212.62  4961.1  214.92    4994  208.88  4996.8  208.38    5000  208.88
  5017.1  209.03  5047.2  214.38  5117.5  212.04  5428.8  211.18  5804.3  213.69
  5900.9  215.64  6105.5   214.4  6186.3  215.71    6218  214.57    6267     216
  6282.9  218.34  6288.6  217.16  6298.7  218.93  6304.5  217.63  6310.3  219.44
    6342  218.18  6347.7  219.52  6363.6     218  6459.9  220.16  6551.6  225.08
#Mann= 3 ,-1 , 0
  3613.6     .05       0    4994     .03       0    5000     .05       0
Bank Sta=4994,5000
XS Rating Curve= 0 ,0
Exp/Cntr=0.3,0.1

Type RM Length L Ch R = 1 ,18231   ,1613,1613,1613
BEGIN DESCRIPTION:
UNT101 IN GIBB 23.0
END DESCRIPTION:
XS GIS Cut Line= 3
      3621313.18     10185567.14      3620238.93     10185762.46
      3619186.76     10186359.05
#Sta/Elev= 30
  4190.3  229.04  4343.9   227.9  4404.8  229.47  4516.6  229.94  4804.4  224.27
  4890.6  221.18  4911.1  220.63  4943.5  216.52  4963.9  213.46  4969.5  210.56
  4974.6  211.51  5004.5  206.63  5022.9  211.49  5055.3  211.62  5287.5  210.23
  5311.8  206.23  5314.6  205.73  5317.8  206.23  5330.7  209.42    5359  210.75
  5757.7  210.34  5837.1  213.16  5955.4  211.83  6048.7  213.62    6241  213.05
  6313.1  215.41  6386.6     216  6429.9  219.45  6489.1  220.63  6491.7   221.9
#Mann= 5 ,-1 , 0
  4190.3     .05       0  4890.6     .16       0  5311.8     .07       0
  5317.8     .16       0  5757.7     .05       0
Bank Sta=5311.8,5317.8
XS Rating Curve= 0 ,0
Exp/Cntr=0.3,0.1

Type RM Length L Ch R = 1 ,16618   ,816,816,816
BEGIN DESCRIPTION:
UNT101 IN GIBB 21.0
END DESCRIPTION:
XS GIS Cut Line= 3
       3620142.1     10184691.65      3619442.11     10185491.64
      3618992.13     10186041.61
#Sta/Elev= 30
  3949.8  231.07  4034.7  226.25  4155.3  215.96  4253.9  211.18  4281.6  209.86
  4380.1  208.62    4552  208.83  4580.5   207.4  4686.8  209.18    4701  207.42
  4707.7  208.86  4729.5  209.06  4736.1  207.61  4778.8  207.14  4807.3  207.41
  4835.8  209.83  4970.6  209.25  4984.8  205.17  5002.7  203.54  5005.4  203.04
  5008.7  203.54  5009.5  205.86  5034.3  208.84  5091.2  209.01  5347.3  210.54
  5444.4  213.61  5531.1  217.39  5559.6   220.7  5694.6  229.99  5723.4  231.68
#Mann= 10 ,-1 , 0
  3949.8     .05       0  4253.9     .16       0  4281.6     .12       0
  4380.1     .16       0  5002.7     .07       0  5008.7     .16       0
  5091.2      .1       0  5444.4     .05       0  5559.6     .16       0
  5694.6     .05       0
Bank Sta=5002.7,5008.7
XS Rating Curve= 0 ,0
Exp/Cntr=0.3,0.1

Type RM Length L Ch R = 1 ,15802   ,1172,1172,1172
BEGIN DESCRIPTION:
UNT101 IN GIBB 19.0
END DESCRIPTION:
XS GIS Cut Line= 3
      3619742.11     10184091.64      3619338.75     10184729.48
      3618498.47     10185646.14
#Sta/Elev= 30
  3996.7  241.94  4083.2  237.62  4156.1  230.47  4207.8  223.79  4286.6  217.73
  4365.5  213.39  4457.1  209.76    4541  207.64  4684.2  205.93    4956  207.38
  4970.2  206.37    4977  204.27  4984.4  205.21  4995.5  203.51  4998.2  203.01
  5001.5  203.51  5019.5  203.73  5040.5  208.06  5267.4  207.96  5302.6  206.85
  5345.1  207.45  5394.4  210.16  5430.2   208.6    5481  209.38  5512.9  210.66
  5614.1  210.83  5654.3  211.82  5705.8  211.62  5871.5  215.15  5994.9  218.14
#Mann= 9 ,-1 , 0
  3996.7     .05       0  4457.1     .16       0  4995.5     .07       0
  5001.5     .16       0    5481      .1       0  5512.9     .16       0
  5614.1      .1       0  5654.3     .05       0  5871.5     .08       0
Bank Sta=4995.5,5001.5
XS Rating Curve= 0 ,0
Exp/Cntr=0.3,0.1

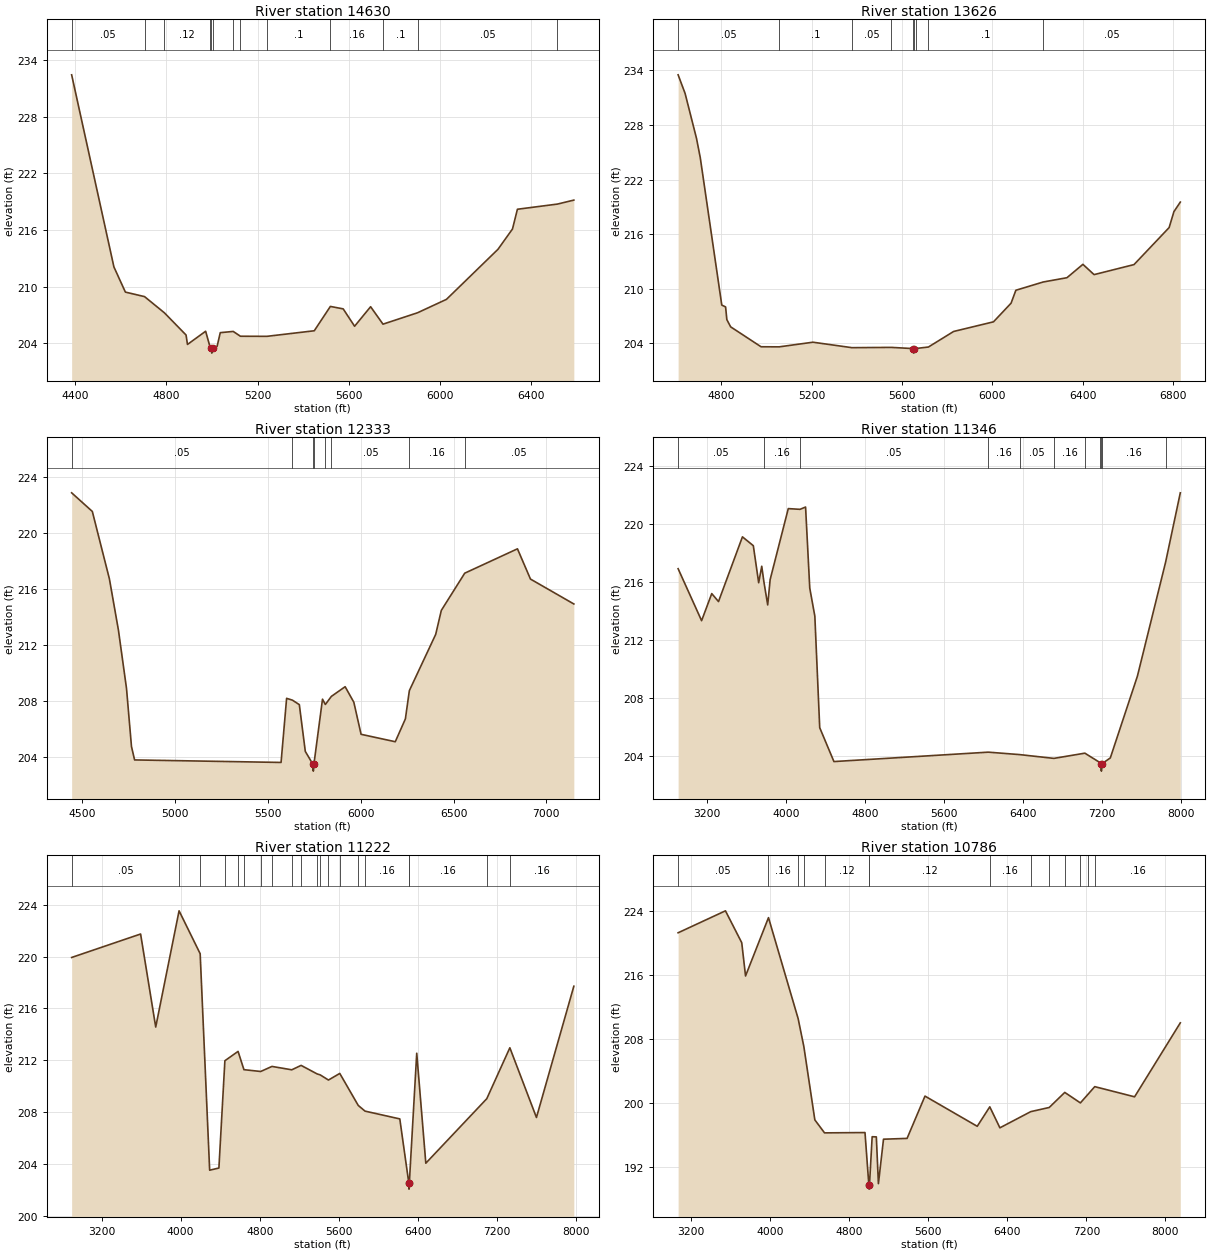
Type RM Length L Ch R = 1 ,14630   ,1004,1004,1004
BEGIN DESCRIPTION:
UNT101 IN GIBB 17.0
END DESCRIPTION:
XS GIS Cut Line= 3
      3619192.12     10183741.63      3618712.37     10184410.03
      3617692.08     10185341.67
#Sta/Elev= 30
  4384.2  232.44  4569.7  212.08    4620  209.41  4704.2  208.93  4791.5  207.21
  4886.4  204.86  4892.6  203.86  4972.4  205.26  4990.3  203.71  4996.7  203.44
  4999.4  202.94  5002.7  203.44  5022.7  203.66  5036.6  205.11  5093.4  205.24
    5125  204.73  5241.3  204.72  5449.2  205.31  5519.9  207.89  5576.2  207.63
  5626.2  205.79  5696.5  207.86  5750.9  206.01  5902.7  207.22  6029.5  208.64
  6255.8  213.95  6319.3   216.1  6340.9  218.19  6516.8  218.74  6588.6  219.16
#Mann= 13 ,-1 , 0
  4384.2     .05       0  4704.2     .16       0  4791.5     .12       0
  4990.3     .07       0  4996.7     .07       0  5002.7     .07       0
  5093.4     .16       0    5125     .07       0  5241.3      .1       0
  5519.9     .16       0  5750.9      .1       0  5902.7     .05       0
  6516.8     .08       0
Bank Sta=4996.7,5002.7
XS Rating Curve= 0 ,0
Exp/Cntr=0.3,0.1

Type RM Length L Ch R = 1 ,13626   ,1293,1293,1293
BEGIN DESCRIPTION:
UNT101 IN GIBB 16.0
END DESCRIPTION:
XS GIS Cut Line= 3
       3618992.1     10183491.64      3618441.53      10183764.2
      3617316.95     10184916.55
#Sta/Elev= 30
  4608.2  233.51  4639.1  231.47  4689.5  226.54  4706.3  224.41  4801.6   208.2
  4818.5     208  4824.1   206.6  4840.9  205.81  4975.5  203.62    5056  203.61
  5205.3  204.12  5378.1  203.52  5552.5  203.55  5648.8  203.42  5651.5  202.92
  5654.8  203.42  5661.4  203.43  5716.9  203.59  5828.5   205.3  6005.2  206.36
  6083.1  208.41  6104.3  209.83  6225.6  210.74  6330.6  211.21  6401.3  212.68
  6450.7  211.55  6627.6  212.65  6783.2  216.72  6804.4  218.47  6832.7  219.52
#Mann= 9 ,-1 , 0
  4608.2     .05       0    5056      .1       0  5378.1     .05       0
  5552.5      .1       0  5648.8    .035       0  5654.8      .1       0
  5661.4     .05       0  5716.9      .1       0  6225.6     .05       0
Bank Sta=5648.8,5654.8
XS Rating Curve= 0 ,0
Exp/Cntr=0.3,0.1

Type RM Length L Ch R = 1 ,12333   ,987,987,987
BEGIN DESCRIPTION:
UNT101 IN GIBB 12.0
END DESCRIPTION:
XS GIS Cut Line= 4
      3618566.49     10182472.54      3617851.25     10182632.25
      3617436.07      10183701.1      3617428.95     10184525.17
#Sta/Elev= 30
  4444.1  222.86  4555.4  221.53  4647.4  216.71    4696  213.05  4739.4  208.89
  4766.2  204.74  4782.9  203.78  5571.5   203.6  5601.4  208.18  5632.5  208.05
  5669.8  207.73    5702  204.39  5742.5  203.48  5745.3  202.98  5748.5  203.48
  5794.6  208.12  5809.9  207.74  5842.4  208.32  5916.5  209.01  5963.3   207.9
  6002.3  205.61  6186.4  205.08  6240.8  206.71  6262.2  208.73  6404.1  212.75
  6434.2  214.46  6560.3  217.12  6844.2  218.86  6914.2   216.7  7147.7  214.92
#Mann= 8 ,-1 , 0
  4444.1     .05       0  5632.5      .1       0  5742.5    .033       0
  5748.5      .1       0  5809.9      .1       0  5842.4     .05       0
  6262.2     .16       0  6560.3     .05       0
Bank Sta=5742.5,5748.5
XS Rating Curve= 0 ,0
Exp/Cntr=0.3,0.1

Type RM Length L Ch R = 1 ,11346   ,124,124,124
BEGIN DESCRIPTION:
UNT101 IN GIBB 11.0
END DESCRIPTION:
XS GIS Cut Line= 4
      3619364.33     10180415.96      3618331.38     10180806.57
      3617070.94     10182745.42      3617307.07     10184391.59
#Sta/Elev= 30
  2909.4  216.94    3147  213.35  3249.6  215.22    3318  214.67  3560.1  219.14
  3670.1  218.53  3724.3  215.97  3755.3  217.11  3776.8  216.05  3815.6  214.44
  3840.4  216.19  4023.7  221.09  4142.7  221.04  4198.7   221.2  4241.1   215.6
  4292.5  213.66  4341.8  205.96  4485.6  203.62  6047.1  204.27  6365.9   204.1
  6710.5  203.84  7023.9   204.2  7174.4  203.56  7188.3  203.46    7191  202.96
  7194.3  203.46  7281.2  203.87    7555  209.51  7840.3  217.38  7989.3  222.18
#Mann= 11 ,-1 , 0
  2909.4     .05       0  3776.8     .16       0  4142.7     .05       0
  6047.1     .16       0  6365.9     .05       0  6710.5     .16       0
  7023.9     .12       0  7174.4     .16       0  7188.3    .033       0
  7194.3     .16       0  7840.3     .05       0
Bank Sta=7188.3,7194.3
XS Rating Curve= 0 ,0
Exp/Cntr=0.3,0.1

Type RM Length L Ch R = 1 ,11222   ,436,436,436
BEGIN DESCRIPTION:
UNT101 IN GIBB 3.0
END DESCRIPTION:
XS GIS Cut Line= 4
      3619277.52     10180329.15      3618244.58     10180719.76
      3616984.14     10182658.61      3617220.27     10184304.79
#Sta/Elev= 30
  2897.4  219.93  3594.9  221.74  3747.8  214.56  3984.1  223.53  4197.4  220.22
  4293.4  203.51    4387  203.68  4447.5  211.96  4580.8  212.68  4640.2  211.27
  4809.5  211.13  4923.8  211.52  5124.1  211.26  5218.4   211.6    5381  210.94
  5411.1  210.87  5495.3  210.47  5609.6  210.98  5796.5  208.51  5865.2  208.07
  6216.8  207.47  6307.4  202.55  6310.1  202.05  6313.4  202.55  6388.1  212.54
    6480  204.05  7096.7  209.03  7330.1  212.96  7599.1  207.58  7977.3  217.71
#Mann= 20 ,-1 , 0
  2897.4     .05       0  3984.1     .16       0  4197.4     .05       0
  4447.5     .16       0  4580.8     .05       0  4640.2     .16       0
  4809.5     .05       0  4923.8      .1       0  5124.1     .05       0
  5218.4      .1       0    5381     .05       0  5411.1     .12       0
  5495.3     .16       0  5609.6     .16       0  5796.5     .12       0
  5865.2     .16       0  6307.4     .07       0  6313.4     .16       0
  7096.7     .12       0  7330.1     .16       0
Bank Sta=6307.4,6313.4
XS Rating Curve= 0 ,0
Exp/Cntr=0.3,0.1

Type RM Length L Ch R = 1 ,10786   ,1850,1850,1850
BEGIN DESCRIPTION:
UNT101 IN GIBB 2.0
END DESCRIPTION:
XS GIS Cut Line= 4
      3619090.02     10180269.27      3618057.02      10180659.9
      3616796.58     10182598.75      3617032.71     10184244.96
#Sta/Elev= 30
  3069.9  221.27  3548.8  224.01  3713.6  220.03  3751.9  215.88  3984.1  223.16
    4284  210.56  4341.8  207.07    4453  197.92  4551.1   196.3  4960.3  196.34
  4999.5  189.78  5002.3  189.28  5005.5  189.78  5032.8  195.82    5075   195.8
  5096.1  189.96  5147.5  195.51    5386  195.61  5567.2  200.89  6095.7  197.12
  6222.7  199.55    6325  196.93    6637  198.95  6824.2  199.47  6981.2  201.35
  7139.1  200.04  7211.7  201.05  7284.5  202.07  7687.4   200.8  8149.9  210.03
#Mann= 14 ,-1 , 0
  3069.9     .05       0  3984.1     .16       0    4284     .05       0
  4341.8     .16       0  4551.1     .12       0  4999.5     .07       0
  5005.5     .12       0  6222.7     .16       0    6637     .12       0
  6824.2     .16       0  6981.2     .12       0  7139.1     .16       0
  7211.7     .12       0  7284.5     .16       0
Bank Sta=4999.5,5005.5
XS Rating Curve= 0 ,0
Exp/Cntr=0.3,0.1

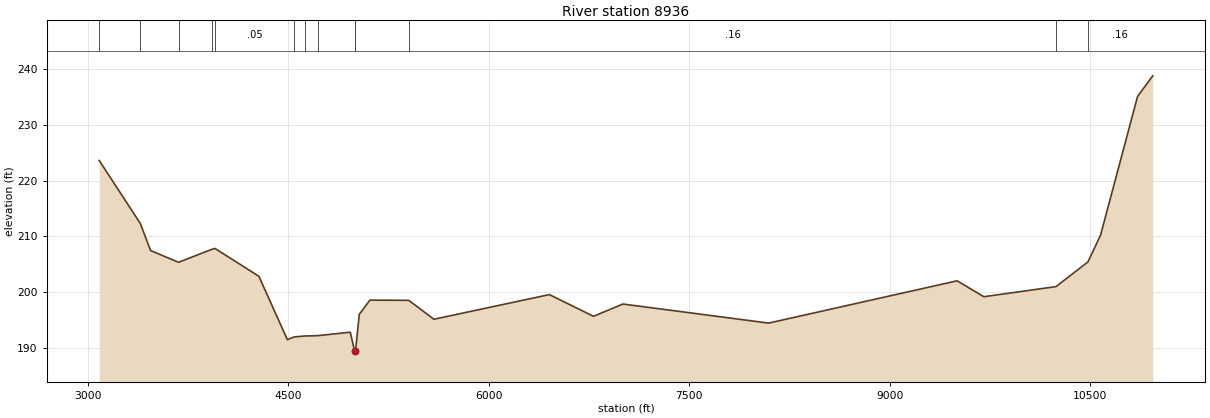
Type RM Length L Ch R = 1 ,8936    ,0,0,0
BEGIN DESCRIPTION:
UNT101 IN GIBB 1.0
END DESCRIPTION:
XS GIS Cut Line= 4
       3618884.8     10180222.54      3617843.12      10179766.8
       3616286.9     10180556.23      3616222.01      10185554.8
#Sta/Elev= 30
  3087.6  223.62  3394.8  212.34  3471.8  207.48    3681  205.37    3930  207.69
  3953.5  207.85  4281.8  202.87    4495  191.51  4547.6     192  4626.5  192.16
  4721.7  192.22  4965.8  192.84  4998.5  189.41  5001.2  188.91  5004.5  189.41
  5033.1  196.05  5112.8  198.59  5403.4  198.55  5591.4  195.16  6455.1  199.58
  6785.1  195.69  7005.1  197.89  8095.2  194.47  9505.3  202.05  9705.3   199.2
 10244.8  201.01 10483.6  205.43 10578.2  210.23 10855.4  235.11 10968.6  238.79
#Mann= 13 ,-1 , 0
  3087.6     .05       0  3394.8     .16       0    3681     .05       0
    3930     .12       0  3953.5     .05       0  4547.6     .12       0
  4626.5     .05       0  4721.7     .12       0  4998.5     .07       0
  5004.5     .12       0  5403.4     .16       0 10244.8     .05       0
 10483.6     .16       0
Bank Sta=4998.5,5004.5
XS Rating Curve= 0 ,0
Exp/Cntr=0.3,0.1

Chan Stop Cuts=-1
Use User Specified Reach Order=0
Composite Channel Slope=5