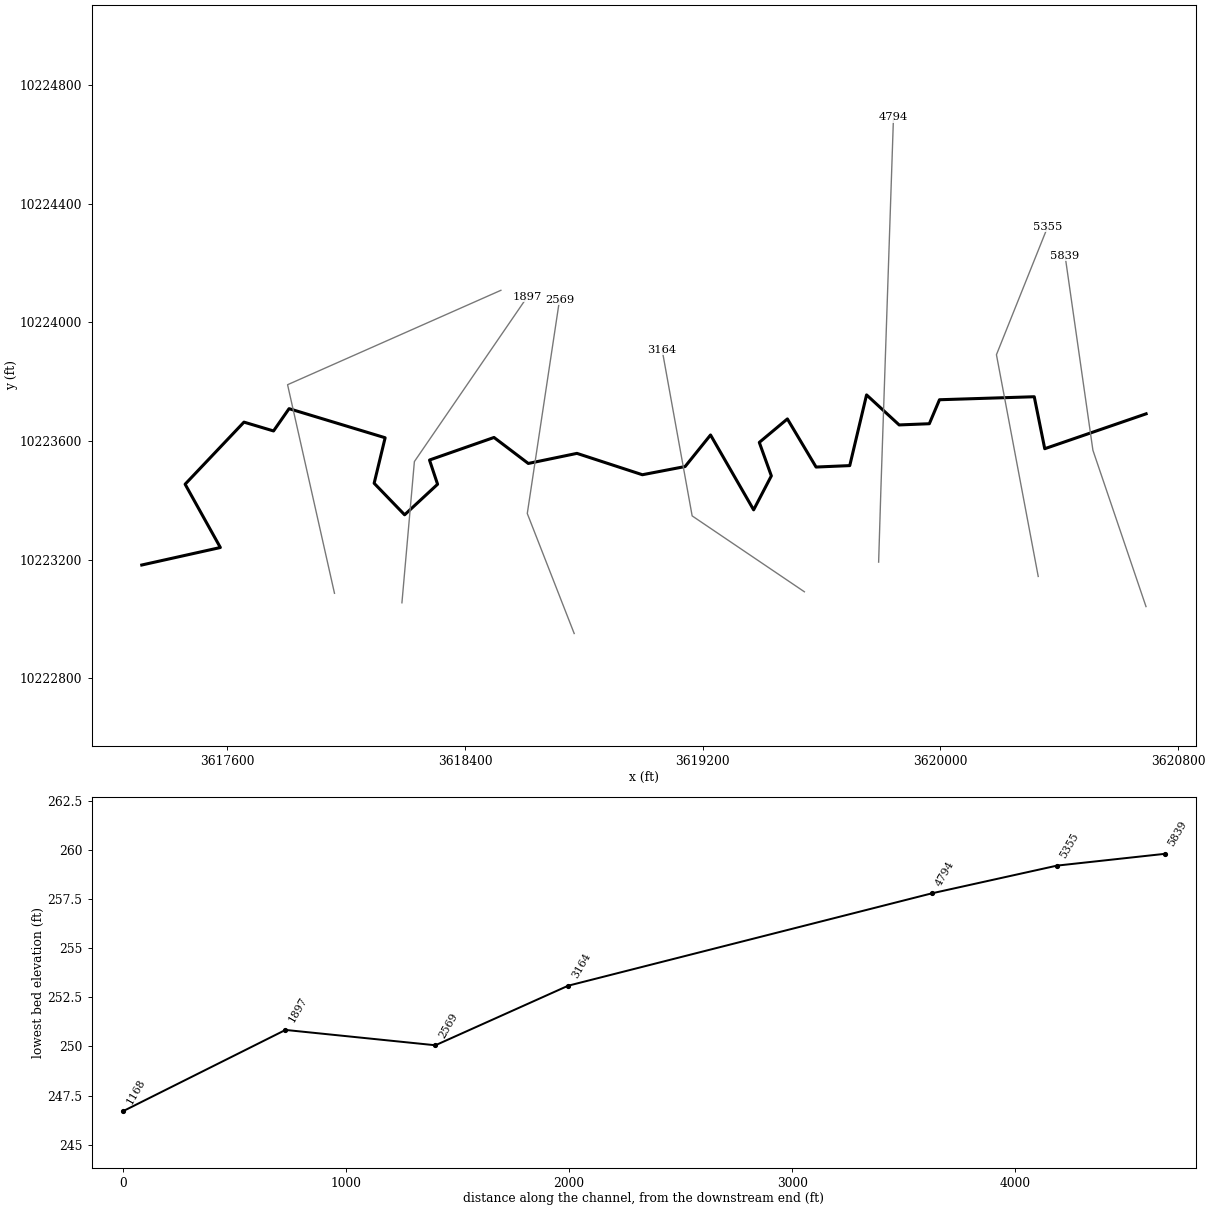
--- UNT114 IN GIBB.prj (project) ---

Proj Title=UNT114 IN GIBB Base Level Engineering
Current Plan=p01
Default Exp/Contr=0.3,0.1
English Units
Geom File=g01
Flow File=f01
Plan File=p01
BEGIN DESCRIPTION:
UNT114 IN GIBB
END DESCRIPTION:

--- UNT114 IN GIBB.p01 (plan) ---

Plan Title=Multiple Run
Short Identifier=Multiple
Geom File=g01
Flow File=f01
Subcritical Flow
K Sum by GR= 0
Std Step Tol= 0.01
Critical Tol= 0.01
Num of Std Step Trials= 20
Max Error Tol= 0.3
Flow Tol Ratio= 0.001
Split Flow NTrial= 30
Split Flow Tol= 0.02
Split Flow Ratio= 0.02
Log Output Level= 0
Friction Slope Method= 1
Unsteady Friction Slope Method= 2
Unsteady Bridges Friction Slope Method= 1
Parabolic Critical Depth
Global Vel Dist=  1 , 1 , 1
Global Log Level= 0
CheckData=True
Encroach Param= -1, 0, 0, 0
BEGIN DESCRIPTION:
Multiple Run
END DESCRIPTION:

--- UNT114 IN GIBB.f01 (steady flow) ---

Flow Title=Multiple
Number of Profiles=7
Profile Names=10-year,25-year,50-year,1pct_min,100-year,1pct_plu,500-year
River Rch & RM= UNT114 IN GIBB,Reach-1,5839
     516     685     820     720     974    1317    1375
River Rch & RM= UNT114 IN GIBB,Reach-1,2569
     642     862    1040     920    1244    1682    1782
Boundary for River Rch & Prof#=UNT114 IN GIBB,Reach-1,1
Up Type=0
Dn Type=3
Dn Slope=0.005
Boundary for River Rch & Prof#=UNT114 IN GIBB,Reach-1,2
Up Type=0
Dn Type=3
Dn Slope=0.005
Boundary for River Rch & Prof#=UNT114 IN GIBB,Reach-1,3
Up Type=0
Dn Type=3
Dn Slope=0.005
Boundary for River Rch & Prof#=UNT114 IN GIBB,Reach-1,4
Up Type=0
Dn Type=3
Dn Slope=0.005
Boundary for River Rch & Prof#=UNT114 IN GIBB,Reach-1,5
Up Type=0
Dn Type=3
Dn Slope=0.005
Boundary for River Rch & Prof#=UNT114 IN GIBB,Reach-1,6
Up Type=0
Dn Type=3
Dn Slope=0.005
Boundary for River Rch & Prof#=UNT114 IN GIBB,Reach-1,7
Up Type=0
Dn Type=3
Dn Slope=0.005

--- UNT114 IN GIBB.g01 (geometry) ---

Geom Title=Existing Conditions

River Reach=UNT114 IN GIBB,Reach-1
Reach XY= 30
      3620692.48     10223691.64      3620351.24     10223574.00
      3620315.94     10223749.23      3619996.94     10223739.10
      3619962.76     10223658.22      3619861.23     10223654.16
      3619751.50     10223755.42      3619694.90     10223517.03
      3619581.50     10223512.17      3619484.98     10223674.42
      3619390.43     10223595.26      3619430.99     10223482.39
      3619371.32     10223367.82      3619226.28     10223620.33
      3619140.74     10223513.86      3618996.90     10223486.23
      3618776.58     10223558.27      3618612.77     10223524.27
      3618497.44     10223611.91      3618280.30     10223535.83
      3618307.50     10223454.11      3618196.54     10223351.10
      3618093.97     10223457.48      3618130.98     10223610.95
      3617807.59     10223709.00      3617755.34     10223633.84
      3617655.84     10223663.62      3617457.67     10223454.25
      3617576.31     10223240.83      3617311.75     10223181.84

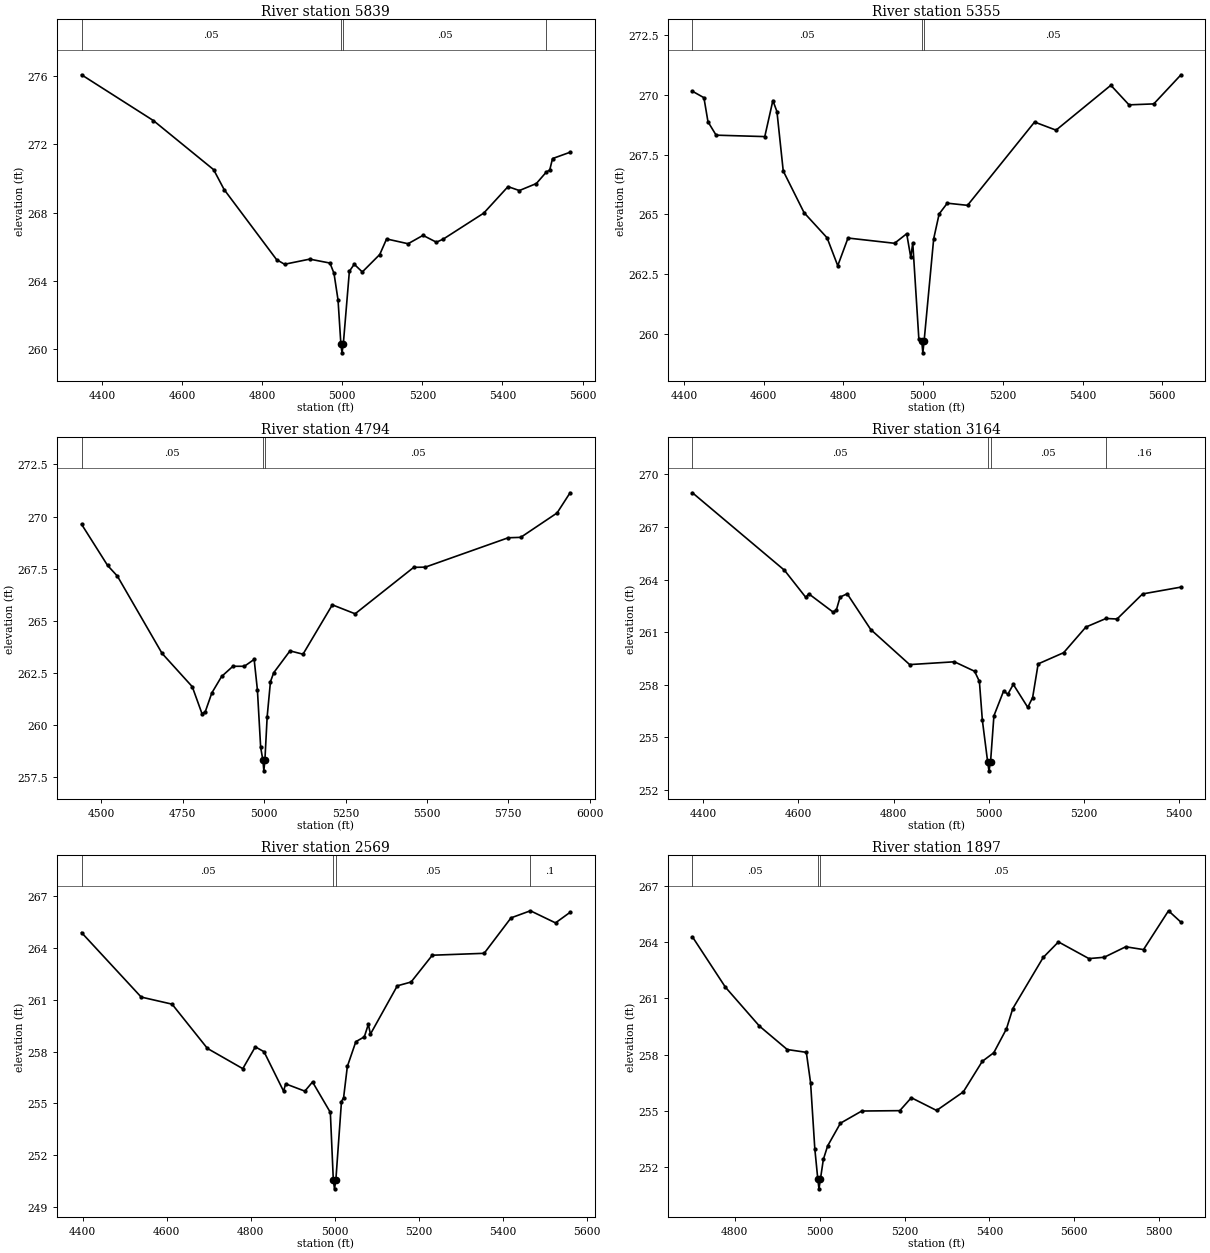
Type RM Length L Ch R = 1,5839,484,484,484
BEGIN DESCRIPTION:
UNT114 IN GIBB 7.0
END DESCRIPTION:
XS GIS Cut Line= 3
      3620692.10     10223041.65      3620513.38     10223568.80
      3620419.63     10224225.01
#Sta/Elev= 30
  4349.2  276.06  4528.7  273.38  4679.0  270.51  4705.1  269.35  4836.1  265.25
  4856.0  264.98  4918.8  265.28  4969.3  265.05  4979.4  264.45  4989.5  262.89
  4996.6  260.30  4999.4  259.80  5002.6  260.30  5017.8  264.57  5029.9  264.98
  5050.1  264.53  5093.6  265.55  5110.7  266.46  5164.3  266.18  5201.6  266.67
  5235.0  266.27  5252.1  266.45  5353.2  267.97  5413.8  269.52  5442.1  269.29
  5484.5  269.70  5509.7  270.38  5517.9  270.49  5524.9  271.16  5568.7  271.53
#Mann=4,-1,0
  4349.2    0.05       0  4996.6    0.03       0  5002.6    0.05       0
  5509.7    0.16       0
Bank Sta=4996.6,5002.6
Exp/Cntr=0.3,0.1

Type RM Length L Ch R = 1,5355,561,561,561
BEGIN DESCRIPTION:
UNT114 IN GIBB 5.0
END DESCRIPTION:
XS GIS Cut Line= 3
      3620329.31     10223143.30      3620188.66     10223890.93
      3620361.38     10224322.73
#Sta/Elev= 30
  4421.3  270.16  4450.1  269.89  4460.3  268.88  4480.7  268.32  4602.8  268.26
  4623.1  269.77  4633.3  269.31  4649.1  266.82  4701.5  265.07  4759.1  264.02
  4785.9  262.85  4811.6  264.01  4928.4  263.79  4958.9  264.19  4969.1  263.20
  4974.1  263.80  4989.4  259.78  4996.6  259.70  4999.4  259.20  5002.6  259.70
  5026.6  263.98  5040.3  265.02  5060.7  265.47  5111.5  265.38  5279.7  268.87
  5333.6  268.53  5471.1  270.41  5516.7  269.59  5578.8  269.63  5647.1  270.85
#Mann=3,-1,0
  4421.3    0.05       0  4996.6    0.03       0  5002.6    0.05       0
Bank Sta=4996.6,5002.6
Exp/Cntr=0.3,0.1

Type RM Length L Ch R = 1,4794,1630,1630,1630
BEGIN DESCRIPTION:
UNT114 IN GIBB 4.0
END DESCRIPTION:
XS GIS Cut Line= 3
      3619792.10     10223191.60      3619799.84     10223441.19
      3619842.11     10224691.66
#Sta/Elev= 30
  4439.0  269.63  4519.1  267.65  4549.1  267.14  4686.4  263.43  4779.2  261.83
  4809.2  260.53  4819.2  260.63  4839.3  261.53  4869.3  262.32  4904.1  262.81
  4939.3  262.81  4969.3  263.14  4979.3  261.68  4989.3  258.92  4996.3  258.29
  4999.1  257.79  5002.3  258.29  5009.3  260.39  5019.4  262.07  5029.4  262.50
  5079.4  263.55  5119.4  263.39  5209.5  265.76  5279.5  265.33  5459.6  267.56
  5495.2  267.57  5749.8  268.98  5788.3  269.00  5899.9  270.17  5939.9  271.14
#Mann=3,-1,0
  4439.0    0.05       0  4996.3    0.03       0  5002.3    0.05       0
Bank Sta=4996.3,5002.3
Exp/Cntr=0.3,0.1

Type RM Length L Ch R = 1,3164,595,595,595
BEGIN DESCRIPTION:
UNT114 IN GIBB 3.0
END DESCRIPTION:
XS GIS Cut Line= 3
      3619542.14     10223091.62      3619164.42     10223347.44
      3619063.16     10223908.27
#Sta/Elev= 30
  4377.5  268.95  4570.8  264.53  4615.7  262.98  4621.7  263.19  4672.6  262.15
  4679.5  262.24  4687.6  263.00  4702.5  263.19  4752.0  261.15  4833.7  259.15
  4927.7  259.31  4970.1  258.77  4980.2  258.19  4986.4  255.98  4997.6  253.59
  5000.3  253.09  5003.6  253.59  5010.7  256.23  5031.0  257.64  5039.9  257.46
  5051.4  258.02  5081.8  256.71  5092.0  257.27  5103.6  259.19  5157.2  259.83
  5203.8  261.29  5246.1  261.78  5269.3  261.75  5322.9  263.18  5403.6  263.57
#Mann=4,-1,0
  4377.5    0.05       0  4997.6    0.03       0  5003.6    0.05       0
  5246.1    0.16       0
Bank Sta=4997.6,5003.6
Exp/Cntr=0.3,0.1

Type RM Length L Ch R = 1,2569,672,672,672
BEGIN DESCRIPTION:
Mapping XS 120aee70
END DESCRIPTION:
XS GIS Cut Line= 3
      3618767.36     10222950.82      3618609.44     10223355.47
      3618718.01     10224075.97
#Sta/Elev= 30
  4397.6  264.88  4539.6  261.15  4613.1  260.74  4697.3  258.18  4781.5  257.01
  4811.3  258.27  4832.0  257.99  4878.5  255.71  4883.6  256.13  4929.2  255.71
  4947.5  256.24  4989.9  254.48  4997.0  250.56  4999.8  250.06  5003.0  250.56
  5016.4  255.11  5021.5  255.34  5030.4  257.14  5050.6  258.57  5070.8  258.85
  5080.3  259.57  5085.4  259.01  5149.3  261.80  5182.1  262.02  5232.6  263.57
  5356.1  263.68  5420.0  265.73  5466.2  266.14  5525.9  265.44  5560.6  266.05
#Mann=4,-1,0
  4397.6    0.05       0  4997.0    0.03       0  5003.0    0.05       0
  5466.2     0.1       0
Bank Sta=4997,5003
Exp/Cntr=0.3,0.1

Type RM Length L Ch R = 1,1897,729,729,729
BEGIN DESCRIPTION:
UNT114 IN GIBB 2.0
END DESCRIPTION:
XS GIS Cut Line= 3
      3618187.49     10223054.42      3618229.44     10223530.67
      3618609.45     10224085.88
#Sta/Elev= 30
  4700.4  264.28  4777.9  261.60  4858.2  259.52  4923.7  258.27  4968.7  258.12
  4978.7  256.50  4988.7  252.97  4995.8  251.34  4998.5  250.84  5001.8  251.34
  5008.8  252.41  5018.9  253.13  5049.0  254.34  5099.2  254.99  5188.9  255.01
  5216.0  255.70  5275.6  255.02  5338.5  256.01  5383.2  257.64  5410.3  258.10
  5440.1  259.37  5455.0  260.45  5526.7  263.18  5562.6  264.01  5634.4  263.12
  5670.3  263.19  5721.1  263.75  5763.0  263.60  5821.9  265.67  5851.3  265.06
#Mann=3,-1,0
  4700.4    0.05       0  4995.8    0.03       0  5001.8    0.05       0
Bank Sta=4995.8,5001.8
Exp/Cntr=0.3,0.1

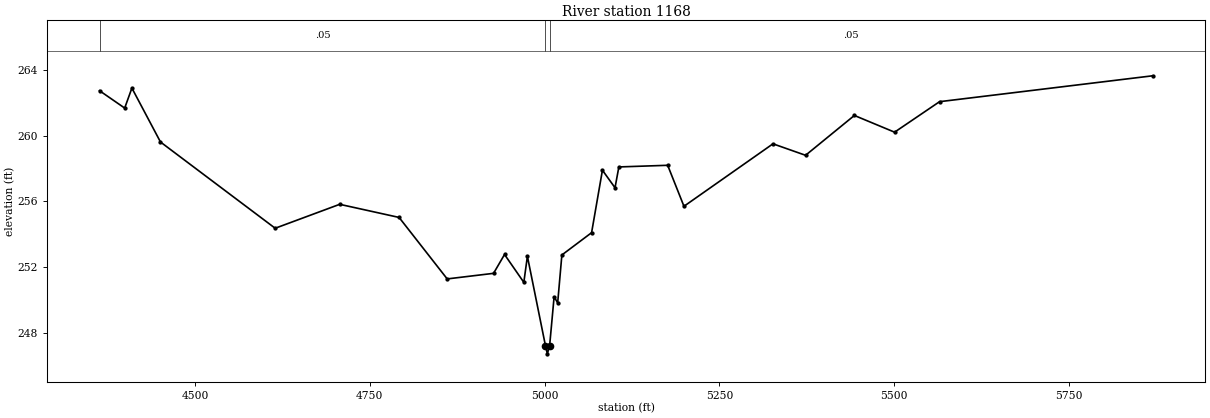
Type RM Length L Ch R = 1,1168,0,0,0
BEGIN DESCRIPTION:
UNT114 IN GIBB 1.0
END DESCRIPTION:
XS GIS Cut Line= 3
      3617960.48     10223086.51      3617802.56     10223789.76
      3618520.61     10224108.07
#Sta/Elev= 30
  4363.4  262.75  4399.4  261.69  4409.7  262.91  4450.6  259.62  4614.6  254.36
  4706.9  255.82  4791.8  255.02  4860.6  251.27  4926.9  251.61  4942.6  252.76
  4970.2  251.06  4975.3  252.65  5001.1  247.20  5003.8  246.70  5007.1  247.20
  5013.5  250.18  5018.6  249.81  5024.6  252.73  5067.1  254.09  5082.6  257.90
  5100.6  256.83  5106.1  258.10  5175.9  258.20  5199.2  255.70  5326.5  259.51
  5373.1  258.81  5442.9  261.24  5500.4  260.22  5564.7  262.08  5869.6  263.66
#Mann=3,-1,0
  4363.4    0.05       0  5001.1    0.03       0  5007.1    0.05       0
Bank Sta=5001.1,5007.1
Exp/Cntr=0.3,0.1

Chan Stop Cuts=-1