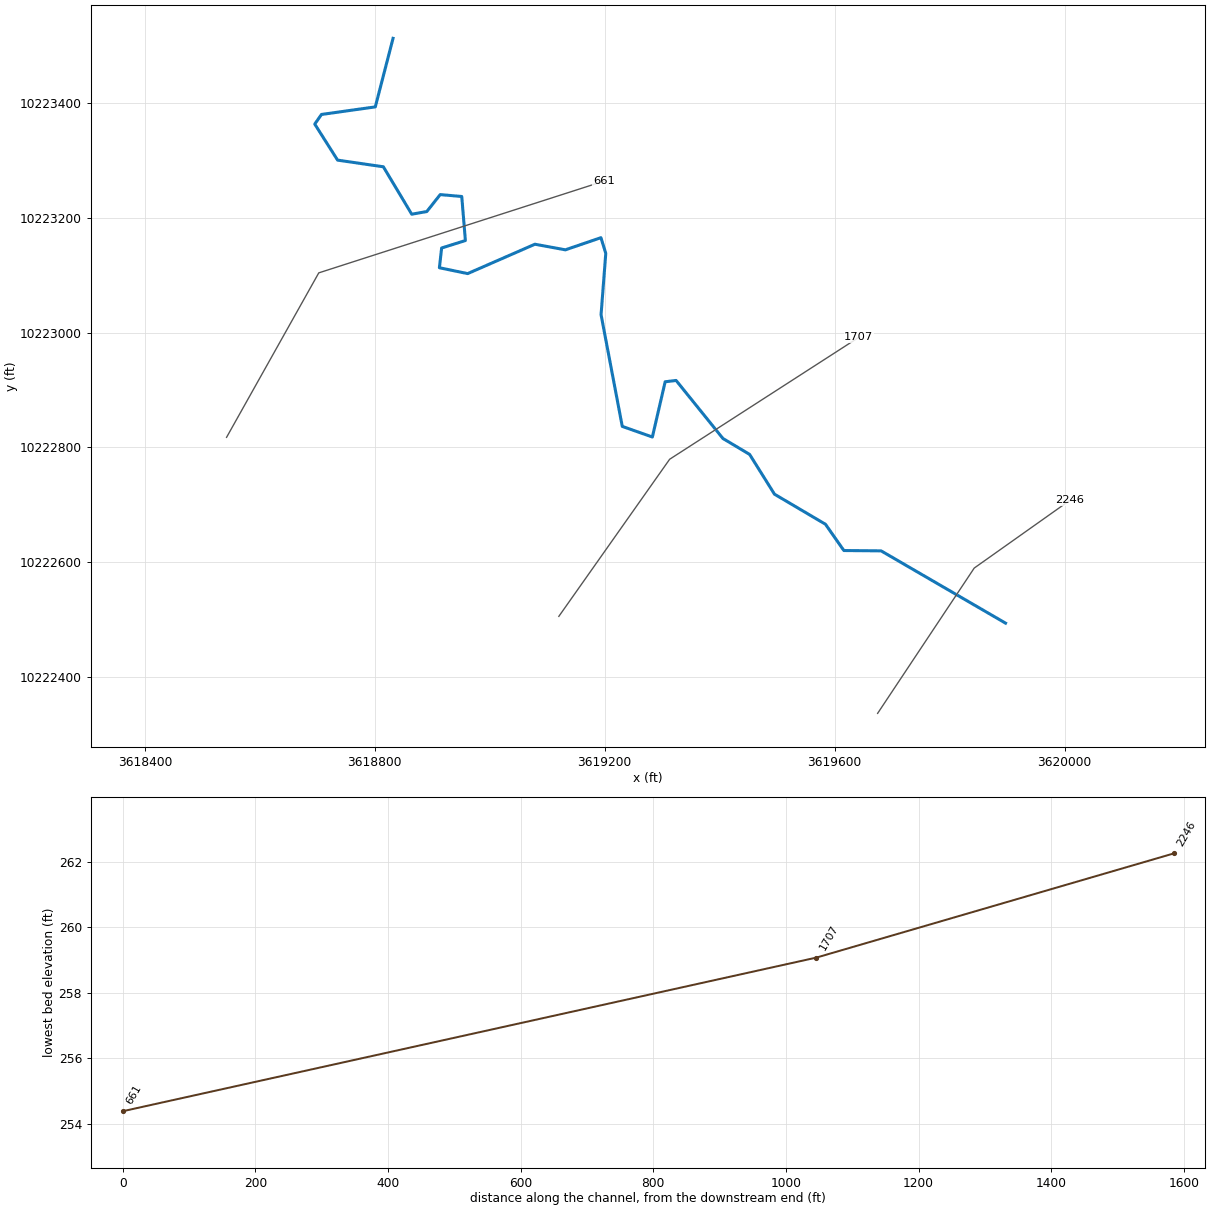
--- UNT115 IN GIBB.prj (project) ---

Proj Title=UNT115 IN GIBB Base Level Engineering
Current Plan=p01
Default Exp/Contr=0.3,0.1
English Units
Geom File=g01
Flow File=f01
Plan File=p01
BEGIN DESCRIPTION:
UNT115 IN GIBB
END DESCRIPTION:

--- UNT115 IN GIBB.p01 (plan) ---

Plan Title=Multiple Run
Short Identifier=Multiple
Geom File=g01
Flow File=f01
Subcritical Flow
K Sum by GR= 0
Std Step Tol= 0.01
Critical Tol= 0.01
Num of Std Step Trials= 20
Max Error Tol= 0.3
Flow Tol Ratio= 0.001
Split Flow NTrial= 30
Split Flow Tol= 0.02
Split Flow Ratio= 0.02
Log Output Level= 0
Friction Slope Method= 1
Unsteady Friction Slope Method= 2
Unsteady Bridges Friction Slope Method= 1
Parabolic Critical Depth
Global Vel Dist=  1 , 1 , 1
Global Log Level= 0
CheckData=True
Encroach Param= -1, 0, 0, 0
BEGIN DESCRIPTION:
Multiple Run
END DESCRIPTION:

--- UNT115 IN GIBB.f01 (steady flow) ---

Flow Title=Multiple
Number of Profiles=7
Profile Names=10-year,25-year,50-year,1pct_min,100-year,1pct_plu,500-year
River Rch & RM= UNT115 IN GIBB,Reach-1,2246
     161     198     225     189     255     346     328
Boundary for River Rch & Prof#=UNT115 IN GIBB,Reach-1,1
Up Type=0
Dn Type=3
Dn Slope=0.005
Boundary for River Rch & Prof#=UNT115 IN GIBB,Reach-1,2
Up Type=0
Dn Type=3
Dn Slope=0.005
Boundary for River Rch & Prof#=UNT115 IN GIBB,Reach-1,3
Up Type=0
Dn Type=3
Dn Slope=0.005
Boundary for River Rch & Prof#=UNT115 IN GIBB,Reach-1,4
Up Type=0
Dn Type=3
Dn Slope=0.005
Boundary for River Rch & Prof#=UNT115 IN GIBB,Reach-1,5
Up Type=0
Dn Type=3
Dn Slope=0.005
Boundary for River Rch & Prof#=UNT115 IN GIBB,Reach-1,6
Up Type=0
Dn Type=3
Dn Slope=0.005
Boundary for River Rch & Prof#=UNT115 IN GIBB,Reach-1,7
Up Type=0
Dn Type=3
Dn Slope=0.005

--- UNT115 IN GIBB.g01 (geometry) ---

Geom Title=Existing Conditions

River Reach=UNT115 IN GIBB,Reach-1
Reach XY= 30
      3619897.36     10222494.40      3619680.88     10222620.15
      3619616.07     10222620.72      3619584.10     10222666.42
      3619495.37     10222718.76      3619452.06     10222788.02
      3619405.69     10222815.65      3619324.18     10222916.64
      3619305.16     10222914.32      3619282.92     10222818.24
      3619230.53     10222836.70      3619193.66     10223030.97
      3619201.84     10223137.76      3619193.44     10223165.01
      3619131.52     10223143.87      3619078.55     10223153.64
      3618961.61     10223102.54      3618912.37     10223112.72
      3618916.28     10223147.06      3618957.60     10223160.05
      3618951.28     10223236.68      3618913.79     10223239.96
      3618890.51     10223210.51      3618864.25     10223205.83
      3618814.89     10223288.35      3618735.26     10223299.95
      3618695.53     10223362.66      3618707.24     10223379.40
      3618800.87     10223392.58      3618831.75     10223511.84

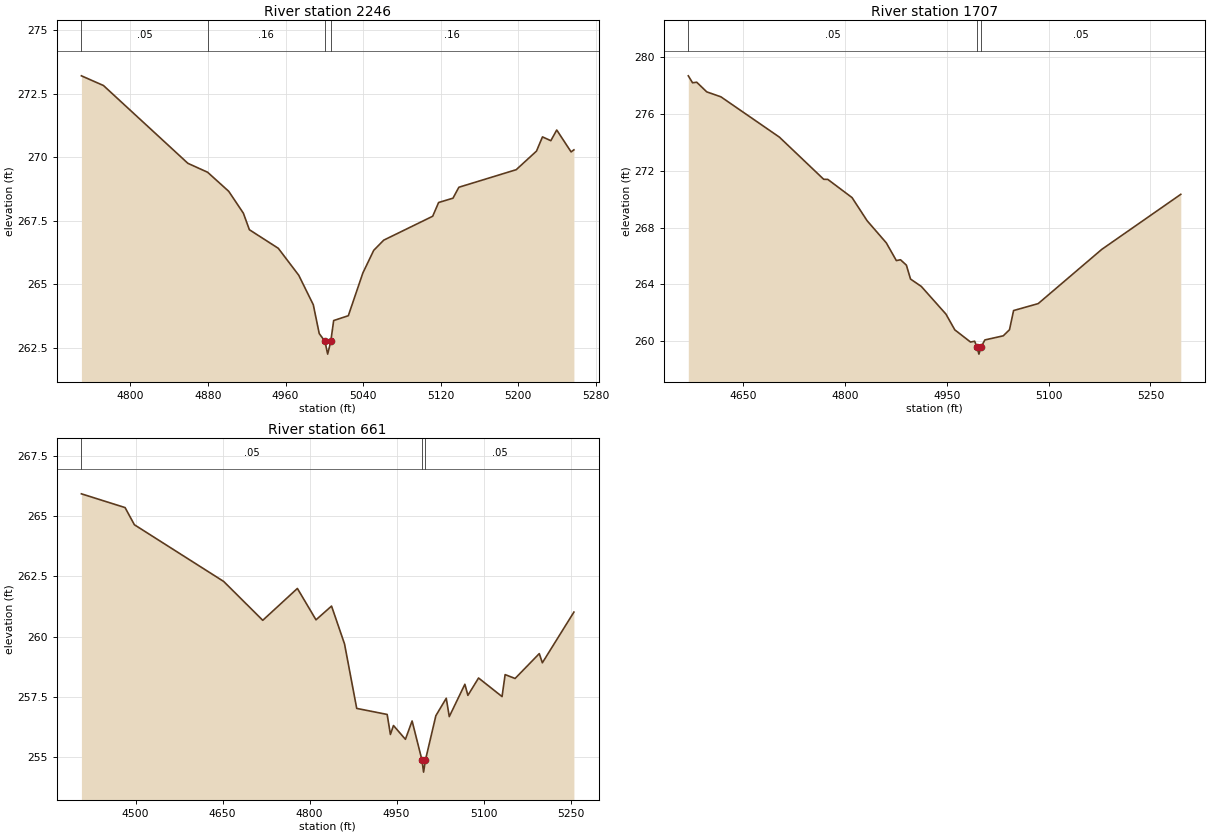
Type RM Length L Ch R = 1,2246,539,539,539
BEGIN DESCRIPTION:
UNT115 IN GIBB 3.0
END DESCRIPTION:
XS GIS Cut Line= 3
      3619674.80     10222337.41      3619842.86     10222590.20
      3620009.53     10222708.25
#Sta/Elev= 30
  4749.5  273.20  4772.2  272.82  4859.3  269.76  4879.6  269.41  4901.4  268.66
  4916.5  267.80  4922.7  267.15  4952.5  266.42  4973.6  265.36  4988.6  264.20
  4994.7  263.07  5000.6  262.76  5003.4  262.26  5006.6  262.76  5009.6  263.58
  5024.7  263.77  5039.7  265.45  5050.9  266.34  5061.2  266.74  5111.7  267.68
  5117.8  268.22  5132.6  268.39  5138.7  268.82  5197.8  269.51  5218.7  270.24
  5224.9  270.80  5233.5  270.65  5239.6  271.07  5254.4  270.21  5257.3  270.29
#Mann=4,-1,0
  4749.5    0.05       0  4879.6    0.16       0  5000.6    0.07       0
  5006.6    0.16       0
Bank Sta=5000.6,5006.6
Exp/Cntr=0.3,0.1

Type RM Length L Ch R = 1,1707,1046,1046,1046
BEGIN DESCRIPTION:
UNT115 IN GIBB 2.0
END DESCRIPTION:
XS GIS Cut Line= 3
      3619120.21     10222506.20      3619312.95     10222779.50
      3619642.08     10222991.63
#Sta/Elev= 30
  4568.8  278.69  4575.1  278.20  4581.2  278.24  4596.0  277.56  4616.9  277.21
  4703.1  274.37  4768.4  271.40  4774.5  271.39  4810.2  270.11  4832.4  268.48
  4860.7  266.92  4875.5  265.67  4881.6  265.73  4890.3  265.35  4896.4  264.37
  4912.3  263.85  4948.6  261.90  4961.7  260.79  4984.9  259.93  4990.9  259.99
  4994.4  259.58  4997.2  259.08  5000.4  259.58  5006.0  260.08  5033.1  260.37
  5042.3  260.80  5048.3  262.15  5084.6  262.64  5178.3  266.46  5294.8  270.34
#Mann=3,-1,0
  4568.8    0.05       0  4994.4    0.03       0  5000.4    0.05       0
Bank Sta=4994.4,5000.4
Exp/Cntr=0.3,0.1

Type RM Length L Ch R = 1,661,0,0,0
BEGIN DESCRIPTION:
UNT115 IN GIBB 1.0
END DESCRIPTION:
XS GIS Cut Line= 3
      3618542.10     10222817.66      3618702.52     10223103.80
      3619198.64     10223263.41
#Sta/Elev= 30
  4406.5  265.92  4481.8  265.35  4497.8  264.64  4651.8  262.29  4719.2  260.68
  4778.9  262.00  4811.0  260.70  4837.8  261.27  4860.2  259.70  4881.2  257.03
  4933.7  256.78  4939.3  255.95  4944.6  256.32  4965.2  255.75  4976.7  256.51
  4993.7  254.89  4996.5  254.39  4999.7  254.89  5017.7  256.73  5035.6  257.45
  5040.8  256.69  5067.7  258.03  5072.9  257.57  5091.3  258.29  5131.8  257.52
  5137.1  258.43  5154.3  258.27  5196.0  259.30  5201.3  258.92  5255.7  261.02
#Mann=3,-1,0
  4406.5    0.05       0  4993.7    0.03       0  4999.7    0.05       0
Bank Sta=4993.7,4999.7
Exp/Cntr=0.3,0.1

Chan Stop Cuts=-1