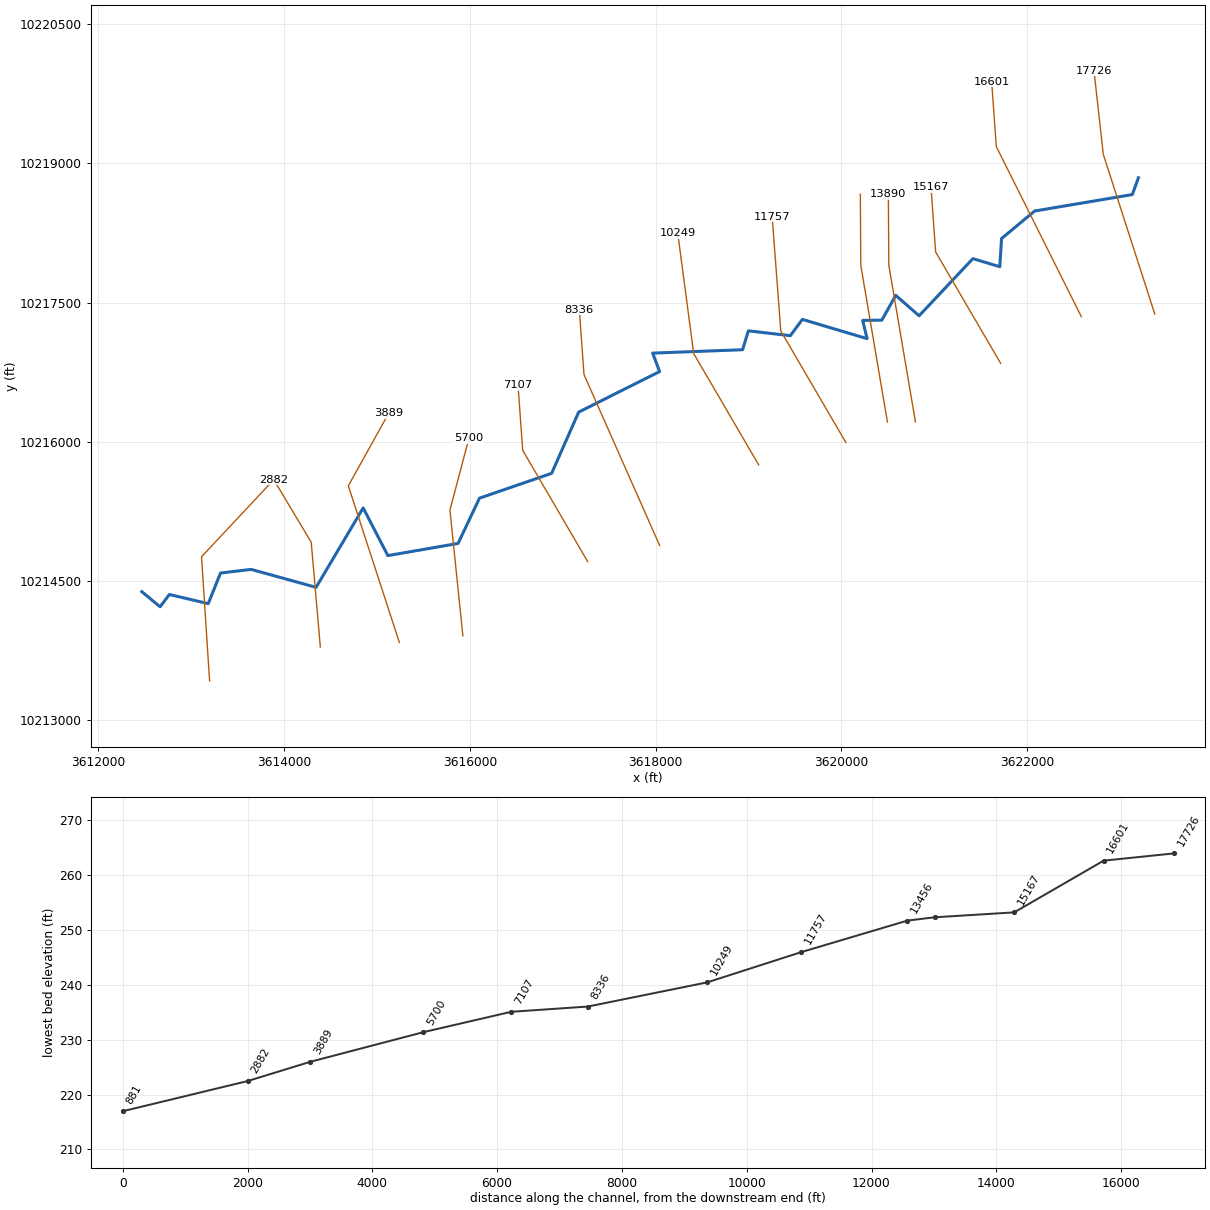
--- UNT116 IN GIBB.prj (project) ---

Proj Title=UNT116 IN GIBB Base Level Engineering
Current Plan=p01
Default Exp/Contr=0.3,0.1
English Units
Geom File=g01
Flow File=f01
Plan File=p01
BEGIN DESCRIPTION:
UNT116 IN GIBB
END DESCRIPTION:

--- UNT116 IN GIBB.p01 (plan) ---

Plan Title=Multiple Run
Short Identifier=Multiple
Geom File=g01
Flow File=f01
Subcritical Flow
K Sum by GR= 0
Std Step Tol= 0.01
Critical Tol= 0.01
Num of Std Step Trials= 20
Max Error Tol= 0.3
Flow Tol Ratio= 0.001
Split Flow NTrial= 30
Split Flow Tol= 0.02
Split Flow Ratio= 0.02
Log Output Level= 0
Friction Slope Method= 1
Unsteady Friction Slope Method= 2
Unsteady Bridges Friction Slope Method= 1
Parabolic Critical Depth
Global Vel Dist=  1 , 1 , 1
Global Log Level= 0
CheckData=True
Encroach Param= -1, 0, 0, 0
BEGIN DESCRIPTION:
Multiple Run
END DESCRIPTION:

--- UNT116 IN GIBB.f01 (steady flow) ---

Flow Title=Multiple
Number of Profiles=7
Profile Names=10-year,25-year,50-year,1pct_min,100-year,1pct_plu,500-year
River Rch & RM= UNT116 IN GIBB,Reach-1,17726
     463     607     721     627     848    1147    1176
River Rch & RM= UNT116 IN GIBB,Reach-1,11757
     763    1029    1244    1102    1490    2015    2139
River Rch & RM= UNT116 IN GIBB,Reach-1,5700
     893    1211    1471    1306    1766    2388    2551
Boundary for River Rch & Prof#=UNT116 IN GIBB,Reach-1,1
Up Type=0
Dn Type=3
Dn Slope=0.005
Boundary for River Rch & Prof#=UNT116 IN GIBB,Reach-1,2
Up Type=0
Dn Type=3
Dn Slope=0.005
Boundary for River Rch & Prof#=UNT116 IN GIBB,Reach-1,3
Up Type=0
Dn Type=3
Dn Slope=0.005
Boundary for River Rch & Prof#=UNT116 IN GIBB,Reach-1,4
Up Type=0
Dn Type=3
Dn Slope=0.005
Boundary for River Rch & Prof#=UNT116 IN GIBB,Reach-1,5
Up Type=0
Dn Type=3
Dn Slope=0.005
Boundary for River Rch & Prof#=UNT116 IN GIBB,Reach-1,6
Up Type=0
Dn Type=3
Dn Slope=0.005
Boundary for River Rch & Prof#=UNT116 IN GIBB,Reach-1,7
Up Type=0
Dn Type=3
Dn Slope=0.005

--- UNT116 IN GIBB.g01 (geometry) ---

Geom Title=Existing Conditions

River Reach=UNT116 IN GIBB,Reach-1
Reach XY= 30
      3623196.57     10218844.51      3623130.89     10218664.18
      3622080.60     10218487.23      3621723.91     10218190.88
      3621704.57     10217887.10      3621415.04     10217974.07
      3620836.14     10217358.57      3620584.83     10217578.62
      3620435.09     10217311.69      3620229.11     10217308.50
      3620276.56     10217112.43      3619579.83     10217319.77
      3619450.58     10217144.42      3618998.95     10217196.56
      3618936.59     10216993.02      3617968.50     10216956.59
      3618043.38     10216757.83      3617172.32     10216321.07
      3616881.48     10215661.86      3616105.00     10215394.55
      3615874.27     10214906.96      3615118.64     10214775.89
      3614853.20     10215289.19      3614346.22     10214434.17
      3613646.71     10214627.29      3613318.30     10214588.21
      3613185.29     10214258.64      3612766.97     10214356.98
      3612667.63     10214224.25      3612470.75     10214387.45

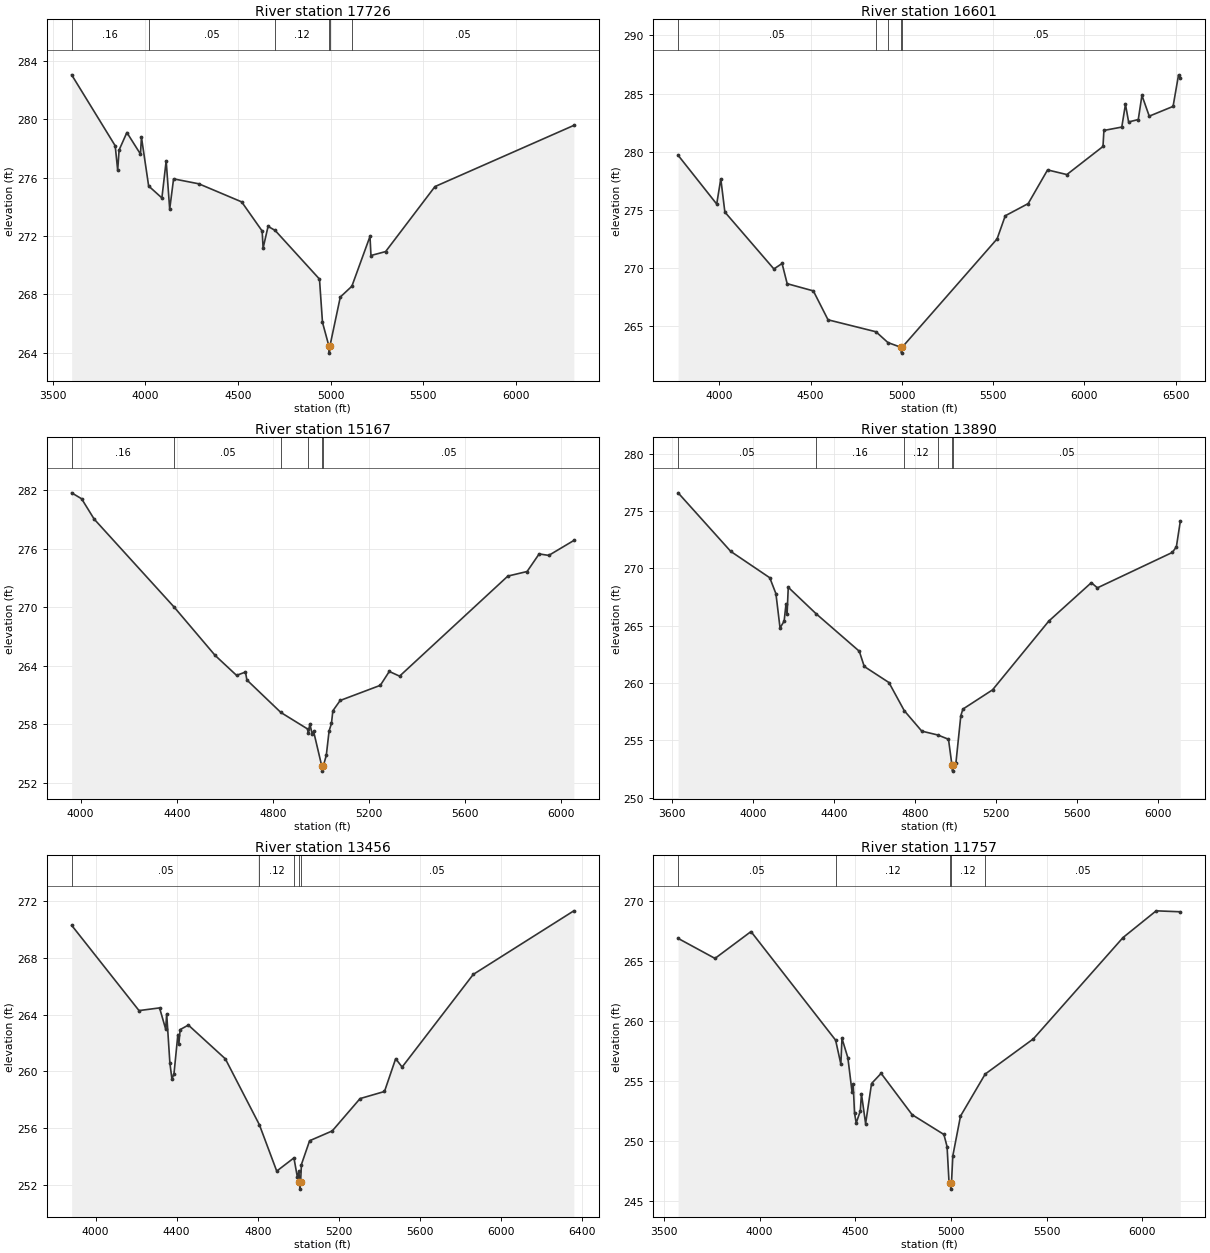
Type RM Length L Ch R = 1,17726,1125,1125,1125
BEGIN DESCRIPTION:
UNT116 IN GIBB 8.0
END DESCRIPTION:
XS GIS Cut Line= 3
      3623372.65     10217377.80      3622818.58     10219097.43
      3622718.63     10219997.01
#Sta/Elev= 30
  3602.1  283.06  3837.3  278.19  3850.7  276.51  3858.3  277.90  3900.3  279.10
  3973.7  277.62  3979.0  278.78  4017.9  275.43  4089.4  274.61  4112.5  277.16
  4131.5  273.84  4152.5  275.92  4289.0  275.58  4520.2  274.34  4630.8  272.34
  4636.0  271.17  4662.8  272.66  4701.0  272.38  4940.4  269.04  4956.6  266.07
  4991.0  264.46  4993.7  263.96  4997.0  264.46  5052.8  267.81  5115.2  268.55
  5213.1  271.97  5218.4  270.66  5297.6  270.93  5563.9  275.39  6313.9  279.59
#Mann=6,-1,0
  3602.1    0.16       0  4017.9    0.05       0  4701.0    0.12       0
  4991.0    0.07       0  4997.0    0.12       0  5115.2    0.05       0
Bank Sta=4991,4997
Exp/Cntr=0.3,0.1

Type RM Length L Ch R = 1,16601,1434,1434,1434
BEGIN DESCRIPTION:
UNT116 IN GIBB 7.1
END DESCRIPTION:
XS GIS Cut Line= 3
      3622582.38     10217349.28      3621667.11     10219181.23
      3621617.11     10219881.18
#Sta/Elev= 30
  3775.0  279.68  3986.3  275.48  4008.7  277.65  4031.0  274.79  4299.4  269.89
  4344.2  270.36  4372.1  268.62  4515.4  268.00  4595.8  265.51  4858.2  264.48
  4923.7  263.55  4995.4  263.14  4998.1  262.64  5001.4  263.14  5521.5  272.48
  5566.2  274.47  5691.7  275.52  5797.9  278.42  5903.5  278.02  6101.3  280.44
  6106.3  281.82  6204.2  282.11  6224.3  284.07  6241.6  282.55  6294.5  282.76
  6314.5  284.84  6354.6  283.05  6485.0  283.89  6515.0  286.61  6524.6  286.32
#Mann=5,-1,0
  3775.0    0.05       0  4858.2    0.07       0  4923.7    0.05       0
  4995.4   0.035       0  5001.4    0.05       0
Bank Sta=4995.4,5001.4
Exp/Cntr=0.3,0.1

Type RM Length L Ch R = 1,15167,1277,1277,1277
BEGIN DESCRIPTION:
UNT116 IN GIBB 7.2
END DESCRIPTION:
XS GIS Cut Line= 3
      3621714.33     10216845.80      3621014.33     10218045.81
      3620964.33     10218745.77
#Sta/Elev= 30
  3962.6  281.72  4004.1  281.11  4056.3  279.03  4388.8  270.03  4559.8  265.07
  4649.2  263.02  4686.4  263.36  4692.2  262.55  4833.7  259.22  4944.9  257.53
  4948.5  257.08  4954.3  258.05  4964.2  257.02  4970.0  257.28  5004.2  253.71
  5007.0  253.21  5010.2  253.71  5022.9  254.83  5034.5  257.32  5044.4  258.10
  5050.2  259.39  5080.8  260.45  5247.9  262.00  5285.1  263.42  5328.1  262.94
  5778.8  273.19  5859.0  273.66  5909.1  275.46  5949.2  275.31  6053.6  276.84
#Mann=6,-1,0
  3962.6    0.16       0  4388.8    0.05       0  4833.7    0.12       0
  4944.9    0.05       0  5004.2    0.03       0  5010.2    0.05       0
Bank Sta=5004.2,5010.2
Exp/Cntr=0.3,0.1

Type RM Length L Ch R = 1,13890,434,434,434
BEGIN DESCRIPTION:
UNT116 IN GIBB 7.7
END DESCRIPTION:
XS GIS Cut Line= 3
      3620797.07     10216215.43      3620510.18     10217904.08
      3620505.41     10218671.02
#Sta/Elev= 30
  3630.7  276.59  3890.6  271.48  4083.3  269.18  4113.7  267.79  4134.0  264.80
  4154.3  265.40  4163.6  266.92  4168.7  265.99  4174.6  268.35  4312.1  266.04
  4525.3  262.77  4549.9  261.44  4671.6  260.04  4747.6  257.58  4833.9  255.80
  4913.5  255.46  4965.8  255.09  4983.1  252.81  4985.8  252.31  4989.1  252.81
  5002.5  253.02  5026.6  257.14  5036.8  257.72  5183.3  259.40  5461.1  265.40
  5671.1  268.75  5701.1  268.30  6071.1  271.39  6091.1  271.88  6110.5  274.11
#Mann=6,-1,0
  3630.7    0.05       0  4312.1    0.16       0  4747.6    0.12       0
  4913.5    0.05       0  4983.1    0.03       0  4989.1    0.05       0
Bank Sta=4983.1,4989.1
Exp/Cntr=0.3,0.1

Type RM Length L Ch R = 1,13456,1699,1699,1699
BEGIN DESCRIPTION:
UNT116 IN GIBB 7.3
END DESCRIPTION:
XS GIS Cut Line= 3
      3620495.58     10216213.82      3620208.69     10217902.52
      3620203.92     10218668.01
#Sta/Elev= 30
  3881.7  270.30  4214.2  264.29  4315.6  264.48  4345.6  262.99  4350.7  264.06
  4366.4  260.62  4376.5  259.47  4386.7  259.83  4405.9  262.60  4411.0  261.97
  4417.1  262.95  4457.7  263.27  4640.2  260.89  4808.1  256.25  4893.8  252.98
  4978.7  253.91  4995.2  252.59  5003.7  252.98  5005.7  252.21  5008.5  251.71
  5011.7  252.21  5015.5  253.44  5056.1  255.12  5167.7  255.81  5305.1  258.09
  5425.6  258.59  5480.8  260.90  5512.6  260.31  5863.7  266.84  6360.1  271.32
#Mann=5,-1,0
  3881.7    0.05       0  4808.1    0.12       0  4978.7    0.05       0
  5005.7    0.03       0  5011.7    0.05       0
Bank Sta=5005.7,5011.7
Exp/Cntr=0.3,0.1

Type RM Length L Ch R = 1,11757,1508,1508,1508
BEGIN DESCRIPTION:
UNT116 IN GIBB 7.4
END DESCRIPTION:
XS GIS Cut Line= 3
      3620047.67     10215995.10      3619347.66     10217195.11
      3619254.75     10218427.35
#Sta/Elev= 30
  3573.9  266.89  3766.7  265.22  3954.9  267.46  4397.1  258.40  4424.6  256.40
  4430.4  258.55  4461.3  256.92  4483.3  254.05  4489.1  254.70  4496.1  252.30
  4504.8  251.49  4526.3  252.49  4532.1  253.93  4553.9  251.43  4585.0  254.78
  4635.0  255.63  4797.1  252.18  4963.2  250.53  4979.7  249.52  4989.8  246.59
  4996.8  246.47  4999.5  245.97  5002.8  246.47  5009.8  248.75  5049.9  252.06
  5179.0  255.57  5431.0  258.51  5899.5  266.96  6072.8  269.19  6198.9  269.11
#Mann=5,-1,0
  3573.9    0.05       0  4397.1    0.12       0  4996.8    0.07       0
  5002.8    0.12       0  5179.0    0.05       0
Bank Sta=4996.8,5002.8
Exp/Cntr=0.3,0.1

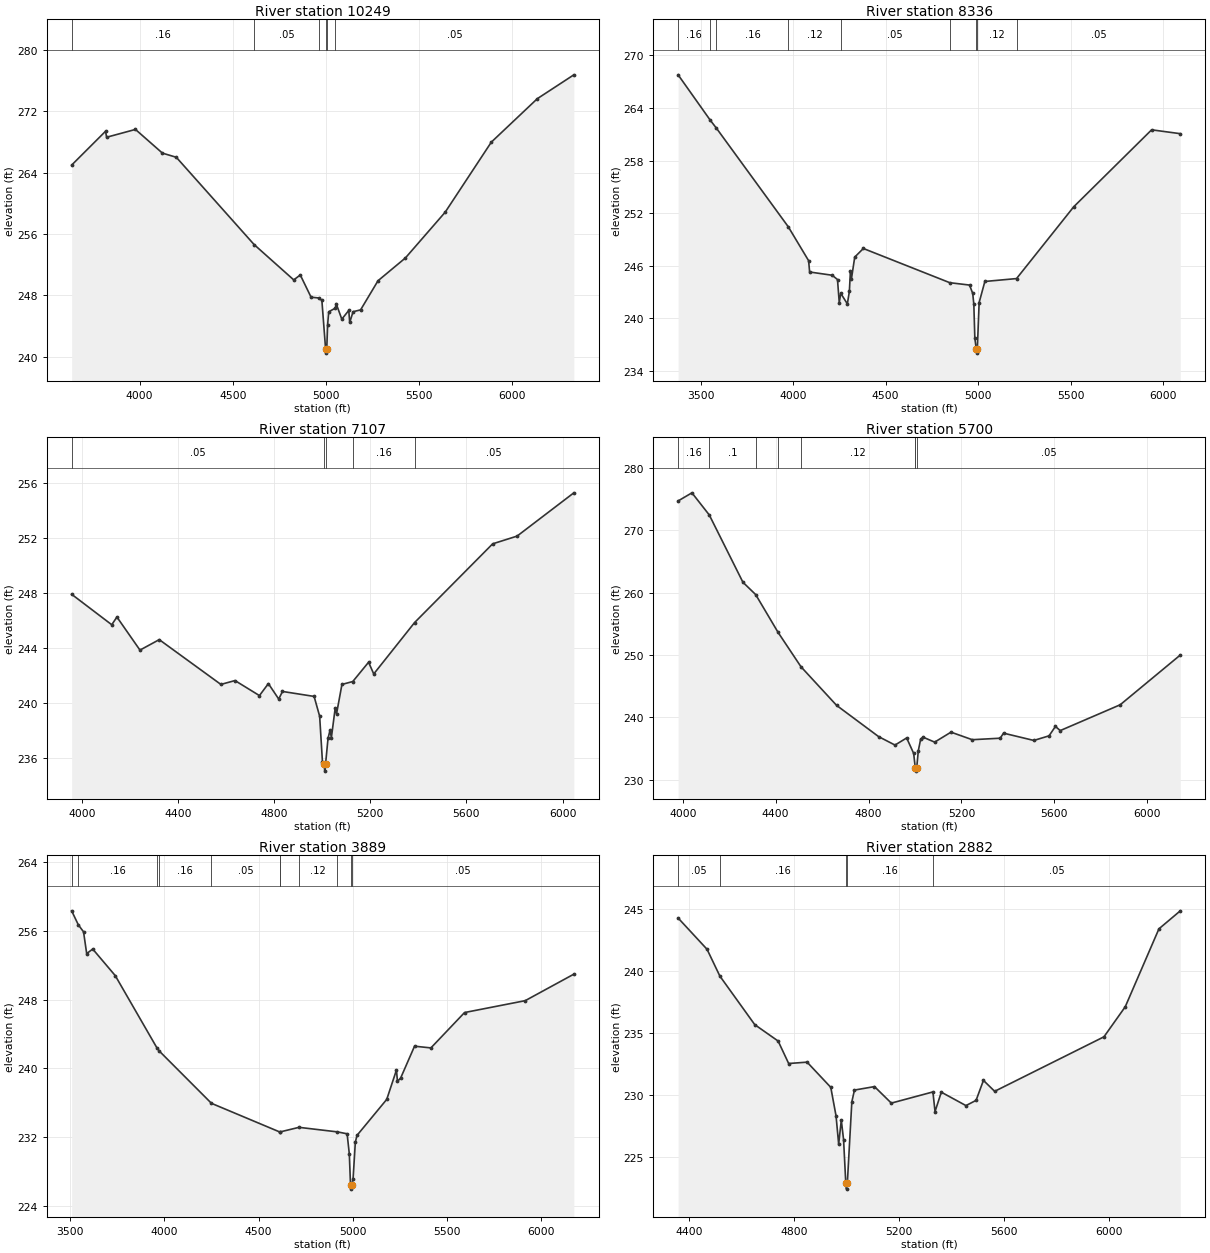
Type RM Length L Ch R = 1,10249,1913,1913,1913
BEGIN DESCRIPTION:
UNT116 IN GIBB 7.5
END DESCRIPTION:
XS GIS Cut Line= 3
      3619110.17     10215752.05      3618410.16     10216952.06
      3618239.07     10218245.84
#Sta/Elev= 30
  3635.9  264.97  3817.7  269.38  3823.5  268.60  3978.2  269.62  4122.9  266.53
  4197.3  265.99  4614.7  254.61  4827.4  250.00  4862.6  250.64  4920.5  247.74
  4964.2  247.64  4978.4  247.32  4998.5  240.95  5001.3  240.45  5004.5  240.95
  5009.3  244.18  5015.1  245.84  5050.8  246.32  5055.0  246.91  5085.3  244.88
  5122.7  246.02  5127.7  244.45  5145.8  245.85  5186.1  246.09  5279.6  249.89
  5426.5  252.86  5640.0  258.83  5887.4  267.96  6134.3  273.63  6330.2  276.74
#Mann=6,-1,0
  3635.9    0.16       0  4614.7    0.05       0  4964.2    0.16       0
  4998.5    0.07       0  5004.5    0.16       0  5050.8    0.05       0
Bank Sta=4998.5,5004.5
Exp/Cntr=0.3,0.1

Type RM Length L Ch R = 1,8336,1229,1229,1229
BEGIN DESCRIPTION:
UNT116 IN GIBB 7.6
END DESCRIPTION:
XS GIS Cut Line= 3
      3618043.98     10214884.74      3617229.61     10216726.36
      3617179.61     10217426.33
#Sta/Elev= 30
  3378.1  267.77  3551.4  262.61  3585.5  261.68  3973.9  250.44  4083.7  246.58
  4089.2  245.29  4211.1  244.92  4239.9  244.43  4249.4  241.80  4257.5  242.86
  4293.2  241.65  4304.1  243.08  4309.8  245.38  4315.2  244.50  4333.1  246.99
  4379.7  247.97  4847.0  244.07  4953.8  243.80  4971.1  242.85  4977.1  241.59
  4982.5  237.76  4990.0  236.54  4992.7  236.04  4996.0  236.54  5005.8  241.81
  5036.7  244.21  5208.0  244.54  5517.4  252.73  5938.4  261.50  6093.5  261.06
#Mann=9,-1,0
  3378.1    0.16       0  3551.4    0.05       0  3585.5    0.16       0
  3973.9    0.12       0  4257.5    0.05       0  4847.0    0.12       0
  4990.0    0.07       0  4996.0    0.12       0  5208.0    0.05       0
Bank Sta=4990,4996
Exp/Cntr=0.3,0.1

Type RM Length L Ch R = 1,7107,1407,1407,1407
BEGIN DESCRIPTION:
UNT116 IN GIBB 7.0
END DESCRIPTION:
XS GIS Cut Line= 3
      3617269.87     10214710.41      3616569.88     10215910.39
      3616520.02     10216608.49
#Sta/Elev= 30
  3957.7  247.91  4124.5  245.70  4146.0  246.26  4241.9  243.86  4322.1  244.62
  4578.5  241.37  4637.2  241.65  4738.9  240.56  4776.1  241.43  4819.1  240.31
  4834.8  240.86  4966.3  240.50  4989.4  239.06  5001.1  235.73  5007.9  235.58
  5010.7  235.08  5013.9  235.58  5024.2  237.45  5032.4  238.04  5038.2  237.51
  5053.9  239.63  5059.7  239.24  5082.1  241.37  5127.2  241.58  5192.9  242.98
  5214.4  242.13  5384.4  245.86  5709.1  251.57  5810.7  252.13  6046.8  255.27
#Mann=5,-1,0
  3957.7    0.05       0  5007.9    0.03       0  5013.9    0.05       0
  5127.2    0.16       0  5384.4    0.05       0
Bank Sta=5007.9,5013.9
Exp/Cntr=0.3,0.1

Type RM Length L Ch R = 1,5700,1811,1811,1811
BEGIN DESCRIPTION:
UNT116 IN GIBB 6.0
END DESCRIPTION:
XS GIS Cut Line= 3
      3615925.95     10213912.47      3615787.06     10215266.64
      3615992.09     10216041.60
#Sta/Elev= 30
  3980.0  274.70  4039.5  276.00  4114.2  272.45  4259.1  261.66  4314.1  259.68
  4410.7  253.61  4509.1  248.11  4662.7  241.91  4843.7  236.90  4914.1  235.55
  4964.3  236.69  4994.5  234.21  5001.0  232.04  5001.5  231.87  5004.3  231.37
  5007.5  231.87  5014.6  234.66  5024.6  236.49  5034.7  236.82  5084.9  236.02
  5155.3  237.62  5246.8  236.41  5367.1  236.65  5381.6  237.46  5512.0  236.29
  5577.6  237.03  5605.1  238.54  5625.7  237.87  5884.0  242.01  6142.9  249.99
#Mann=8,-1,0
  3980.0    0.16       0  4114.2     0.1       0  4314.1    0.16       0
  4410.7     0.1       0  4509.1    0.12       0  5001.0    0.05       0
  5001.5    0.07       0  5007.5    0.05       0
Bank Sta=5001.5,5007.5
Exp/Cntr=0.3,0.1

Type RM Length L Ch R = 1,3889,1007,1007,1007
BEGIN DESCRIPTION:
UNT116 IN GIBB 4.0
END DESCRIPTION:
XS GIS Cut Line= 3
      3615242.12     10213841.61      3614693.31     10215527.06
      3615126.77     10216307.29
#Sta/Elev= 30
  3508.4  258.31  3543.9  256.68  3571.5  255.87  3588.2  253.34  3620.2  253.87
  3739.8  250.78  3960.3  242.41  3972.8  242.03  4250.4  235.94  4612.9  232.61
  4613.1  232.61  4715.1  233.15  4919.2  232.62  4970.3  232.40  4982.0  230.05
  4988.3  226.47  4991.1  225.97  4994.3  226.47  5001.8  227.11  5013.9  231.43
  5022.9  232.22  5180.6  236.40  5232.2  239.81  5237.4  238.50  5254.2  238.87
  5328.1  242.58  5415.0  242.38  5593.5  246.49  5915.4  247.87  6173.5  250.95
#Mann=11,-1,0
  3508.4     0.1       0  3543.9    0.16       0  3960.3    0.12       0
  3972.8    0.16       0  4250.4    0.05       0  4612.9    0.16       0
  4613.1    0.05       0  4715.1    0.12       0  4919.2    0.05       0
  4988.3    0.03       0  4994.3    0.05       0
Bank Sta=4988.3,4994.3
Exp/Cntr=0.3,0.1

Type RM Length L Ch R = 1,2882,2001,2001,2001
BEGIN DESCRIPTION:
UNT116 IN GIBB 2.0
END DESCRIPTION:
XS GIS Cut Line= 3
      3614392.11     10213791.64      3614294.00     10214919.42
      3613892.13     10215591.60
#Sta/Elev= 30
  4356.8  244.29  4467.2  241.77  4516.1  239.61  4649.1  235.70  4738.2  234.38
  4778.4  232.57  4848.7  232.68  4939.0  230.65  4959.1  228.35  4969.1  226.07
  4979.1  228.01  4987.8  226.44  4996.2  222.95  4999.0  222.45  5002.2  222.95
  5019.3  229.48  5029.3  230.43  5105.7  230.71  5169.9  229.38  5328.5  230.28
  5336.6  228.70  5360.6  230.26  5454.5  229.18  5493.1  229.60  5521.2  231.21
  5564.0  230.33  5980.8  234.72  6062.0  237.14  6190.5  243.42  6272.0  244.87
#Mann=5,-1,0
  4356.8    0.05       0  4516.1    0.16       0  4996.2    0.07       0
  5002.2    0.16       0  5328.5    0.05       0
Bank Sta=4996.2,5002.2
Exp/Cntr=0.3,0.1

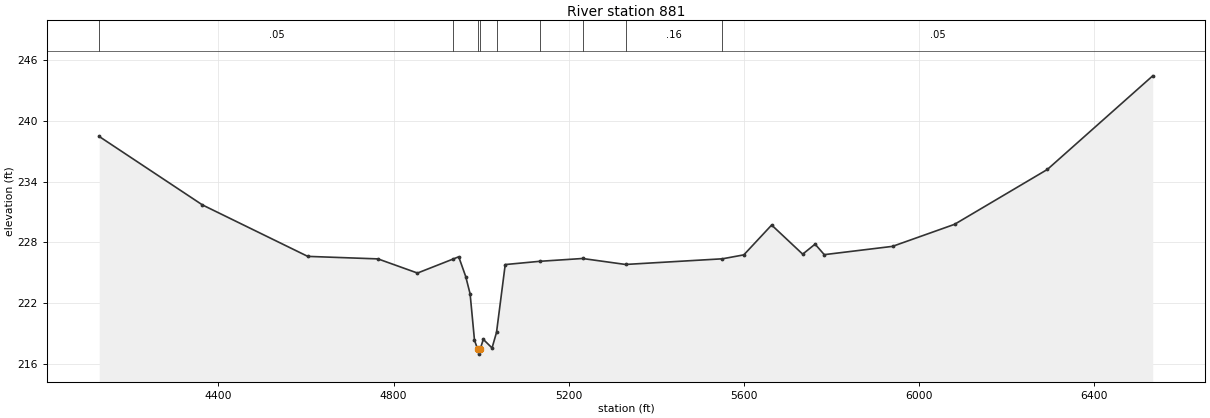
Type RM Length L Ch R = 1,881,0,0,0
BEGIN DESCRIPTION:
UNT116 IN GIBB 1.0
END DESCRIPTION:
XS GIS Cut Line= 3
      3613200.25     10213426.41      3613113.45     10214763.17
      3613842.13     10215541.67
#Sta/Elev= 30
  4127.8  238.48  4363.5  231.71  4604.0  226.62  4764.4  226.37  4854.6  224.97
  4936.8  226.37  4948.8  226.58  4964.8  224.62  4974.8  222.91  4984.8  218.33
  4991.9  217.45  4994.6  216.95  4997.9  217.45  5004.9  218.41  5024.9  217.56
  5035.1  219.10  5055.0  225.81  5133.3  226.13  5231.5  226.41  5329.7  225.82
  5551.0  226.38  5599.9  226.77  5663.4  229.72  5734.3  226.84  5762.6  227.83
  5783.6  226.79  5939.4  227.61  6081.1  229.79  6293.1  235.22  6533.7  244.48
#Mann=9,-1,0
  4127.8    0.05       0  4936.8    0.16       0  4991.9    0.07       0
  4997.9    0.16       0  5035.1    0.12       0  5133.3    0.16       0
  5231.5    0.12       0  5329.7    0.16       0  5551.0    0.05       0
Bank Sta=4991.9,4997.9
Exp/Cntr=0.3,0.1

Chan Stop Cuts=-1