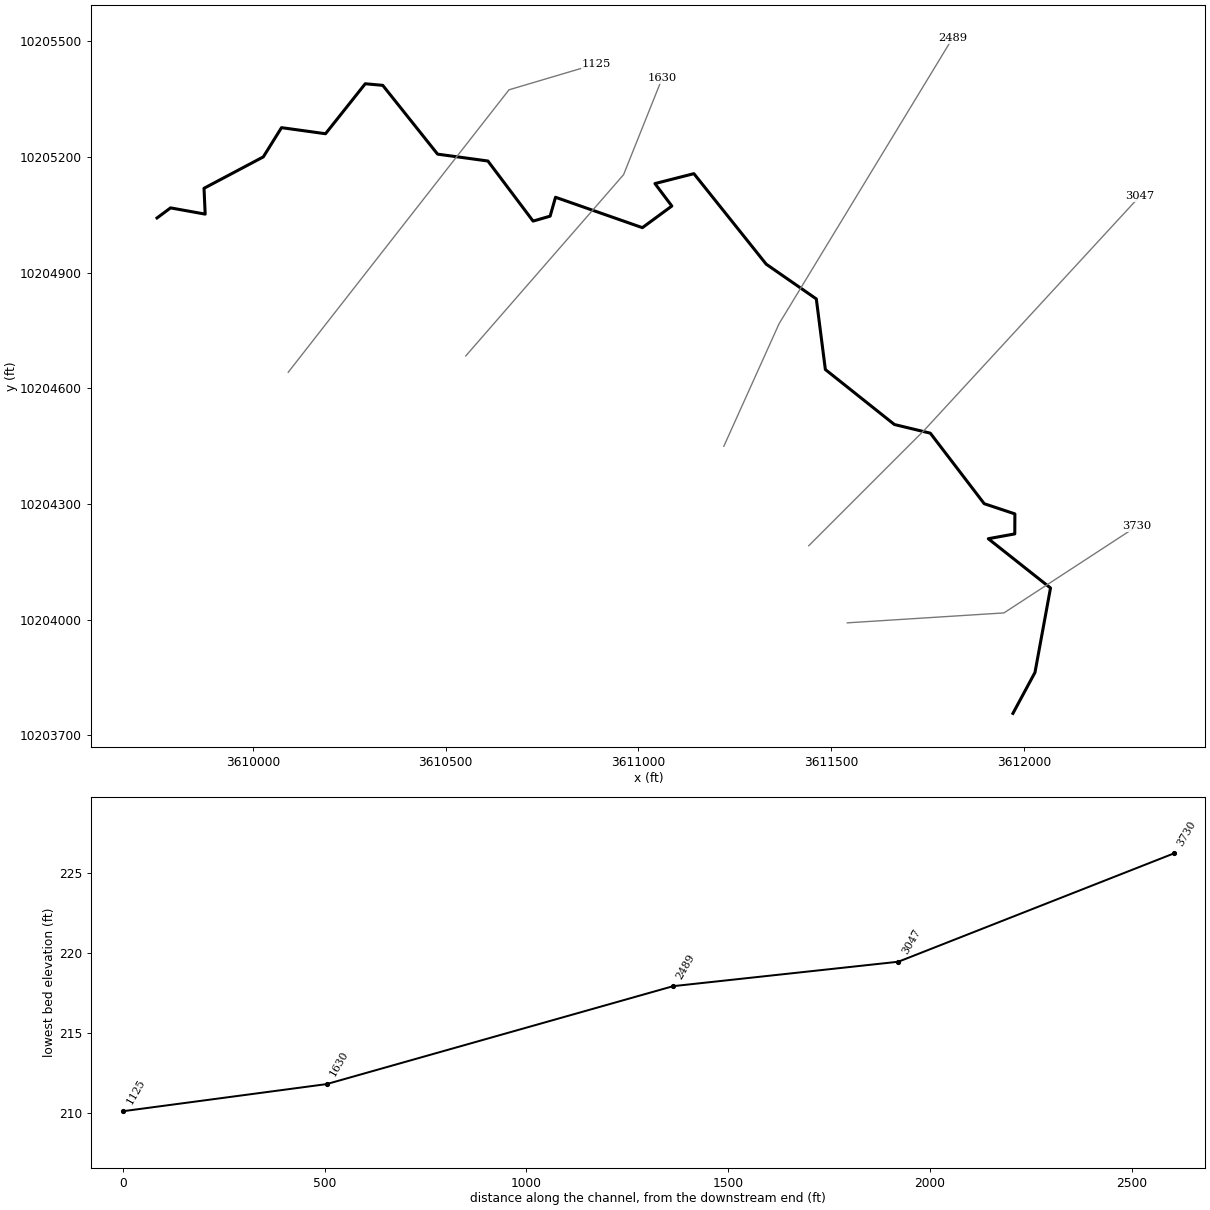
--- UNT119 IN GIBB.prj (project) ---

Proj Title=UNT119 IN GIBB Base Level Engineering
Current Plan=p01
Default Exp/Contr=0.3,0.1
English Units
Geom File=g01
Flow File=f01
Plan File=p01
BEGIN DESCRIPTION:
UNT119 IN GIBB
END DESCRIPTION:

--- UNT119 IN GIBB.p01 (plan) ---

Plan Title=Multiple Run
Short Identifier=Multiple
Geom File=g01
Flow File=f01
Subcritical Flow
K Sum by GR= 0
Std Step Tol= 0.01
Critical Tol= 0.01
Num of Std Step Trials= 20
Max Error Tol= 0.3
Flow Tol Ratio= 0.001
Split Flow NTrial= 30
Split Flow Tol= 0.02
Split Flow Ratio= 0.02
Log Output Level= 0
Friction Slope Method= 1
Unsteady Friction Slope Method= 2
Unsteady Bridges Friction Slope Method= 1
Parabolic Critical Depth
Global Vel Dist=  1 , 1 , 1
Global Log Level= 0
CheckData=True
Encroach Param= -1, 0, 0, 0
BEGIN DESCRIPTION:
Multiple Run
END DESCRIPTION:

--- UNT119 IN GIBB.f01 (steady flow) ---

Flow Title=Multiple
Number of Profiles=7
Profile Names=10-year,25-year,50-year,1pct_min,100-year,1pct_plu,500-year
River Rch & RM= UNT119 IN GIBB,Reach-1,3730
     392     520     623     550     744    1006    1058
Boundary for River Rch & Prof#=UNT119 IN GIBB,Reach-1,1
Up Type=0
Dn Type=3
Dn Slope=0.005
Boundary for River Rch & Prof#=UNT119 IN GIBB,Reach-1,2
Up Type=0
Dn Type=3
Dn Slope=0.005
Boundary for River Rch & Prof#=UNT119 IN GIBB,Reach-1,3
Up Type=0
Dn Type=3
Dn Slope=0.005
Boundary for River Rch & Prof#=UNT119 IN GIBB,Reach-1,4
Up Type=0
Dn Type=3
Dn Slope=0.005
Boundary for River Rch & Prof#=UNT119 IN GIBB,Reach-1,5
Up Type=0
Dn Type=3
Dn Slope=0.005
Boundary for River Rch & Prof#=UNT119 IN GIBB,Reach-1,6
Up Type=0
Dn Type=3
Dn Slope=0.005
Boundary for River Rch & Prof#=UNT119 IN GIBB,Reach-1,7
Up Type=0
Dn Type=3
Dn Slope=0.005

--- UNT119 IN GIBB.g01 (geometry) ---

Geom Title=Existing Conditions

River Reach=UNT119 IN GIBB,Reach-1
Reach XY= 30
      3611971.75     10203756.84      3612028.92     10203863.01
      3612069.20     10204082.06      3611907.76     10204209.87
      3611976.53     10204222.34      3611976.80     10204274.24
      3611897.26     10204300.68      3611757.49     10204483.59
      3611664.31     10204506.07      3611485.24     10204648.65
      3611461.75     10204831.84      3611331.79     10204921.96
      3611144.25     10205156.70      3611043.21     10205131.00
      3611087.02     10205072.77      3611010.66     10205016.64
      3610785.32     10205095.50      3610771.33     10205046.49
      3610727.15     10205033.70      3610609.93     10205189.53
      3610479.46     10205207.34      3610337.26     10205385.77
      3610291.82     10205389.90      3610188.75     10205260.25
      3610074.64     10205276.05      3610027.38     10205200.16
      3609873.62     10205118.78      3609876.64     10205051.77
      3609786.87     10205067.96      3609751.75     10205041.84

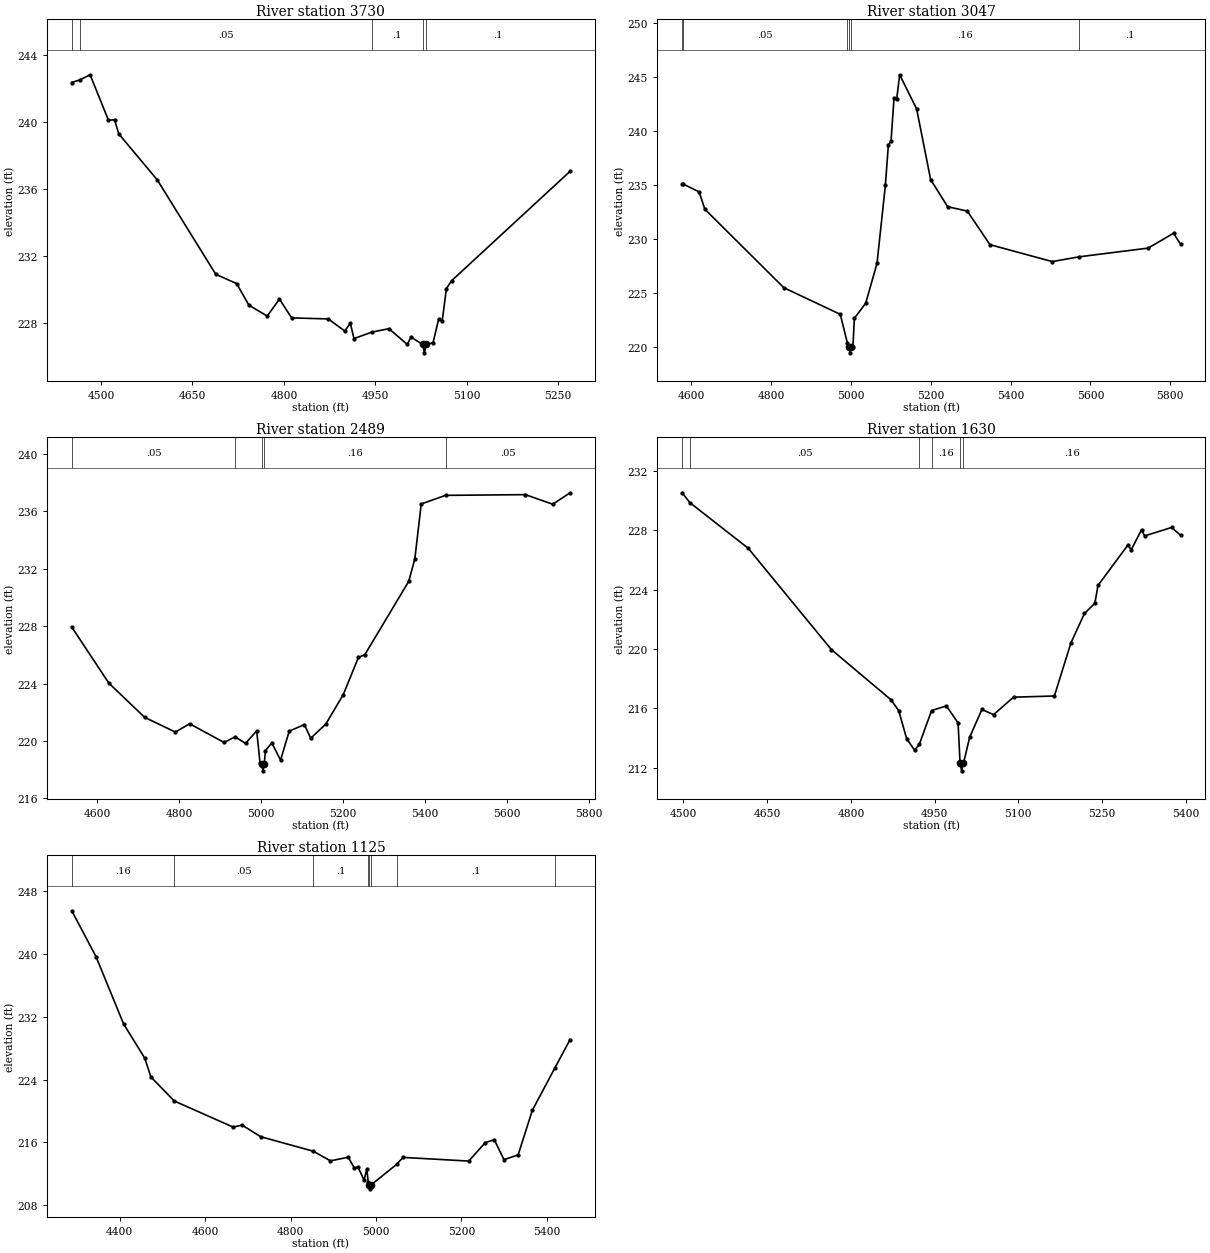
Type RM Length L Ch R = 1,3730,683,683,683
BEGIN DESCRIPTION:
UNT119 IN GIBB 6.0
END DESCRIPTION:
XS GIS Cut Line= 3
      3611542.06     10203991.64      3611948.46     10204017.42
      3612292.07     10204241.62
#Sta/Elev= 30
  4452.0  242.34  4465.6  242.50  4482.1  242.80  4512.2  240.09  4522.2  240.12
  4529.1  239.28  4592.3  236.54  4688.2  230.92  4722.6  230.36  4742.6  229.08
  4772.7  228.43  4792.7  229.44  4812.8  228.32  4872.8  228.26  4899.9  227.54
  4909.0  228.01  4915.0  227.09  4944.1  227.47  4972.3  227.68  5002.5  226.74
  5008.5  227.18  5027.7  226.74  5030.5  226.24  5033.7  226.74  5044.7  226.84
  5053.9  228.25  5059.8  228.14  5066.6  230.06  5075.0  230.53  5269.5  237.05
#Mann=5,-1,0
  4452.0    0.16       0  4465.6    0.05       0  4944.1     0.1       0
  5027.7    0.07       0  5033.7     0.1       0
Bank Sta=5027.7,5033.7
Exp/Cntr=0.3,0.1

Type RM Length L Ch R = 1,3047,558,558,558
BEGIN DESCRIPTION:
UNT119 IN GIBB 5.0
END DESCRIPTION:
XS GIS Cut Line= 3
      3611442.12     10204191.65      3611742.11     10204491.64
      3612300.48     10205097.81
#Sta/Elev= 30
  4577.1  235.09  4580.0  235.09  4619.5  234.37  4633.7  232.77  4831.6  225.49
  4973.1  223.02  4990.8  220.38  4994.8  219.95  4997.6  219.45  5000.8  219.95
  5004.7  219.95  5008.4  222.65  5036.8  224.05  5065.1  227.74  5086.1  234.98
  5093.5  238.69  5100.3  239.09  5107.7  243.05  5114.5  242.98  5121.9  245.23
  5164.4  242.07  5199.5  235.51  5242.1  233.00  5291.4  232.59  5348.1  229.48
  5504.1  227.91  5570.9  228.35  5744.5  229.16  5808.0  230.54  5825.5  229.53
#Mann=6,-1,0
  4577.1    0.16       0  4580.0    0.05       0  4990.8    0.16       0
  4994.8    0.07       0  5000.8    0.16       0  5570.9     0.1       0
Bank Sta=4994.8,5000.8
Exp/Cntr=0.3,0.1

Type RM Length L Ch R = 1,2489,859,859,859
BEGIN DESCRIPTION:
UNT119 IN GIBB 4.0
END DESCRIPTION:
XS GIS Cut Line= 3
      3611221.89     10204449.70      3611365.13     10204767.42
      3611814.85     10205507.71
#Sta/Elev= 30
  4538.7  227.94  4629.2  224.03  4716.3  221.65  4791.2  220.62  4826.0  221.20
  4910.0  219.90  4937.0  220.29  4962.3  219.83  4989.5  220.71  4997.5  218.50
  5002.0  218.42  5004.7  217.92  5008.0  218.42  5010.8  219.33  5026.3  219.87
  5047.6  218.67  5068.9  220.69  5105.8  221.14  5121.2  220.19  5158.0  221.18
  5200.7  223.24  5237.5  225.83  5253.0  226.01  5360.2  231.13  5375.1  232.71
  5390.6  236.52  5449.9  237.12  5644.5  237.17  5711.2  236.50  5753.4  237.30
#Mann=5,-1,0
  4538.7    0.05       0  4937.0    0.16       0  5002.0    0.07       0
  5008.0    0.16       0  5449.9    0.05       0
Bank Sta=5002,5008
Exp/Cntr=0.3,0.1

Type RM Length L Ch R = 1,1630,505,505,505
BEGIN DESCRIPTION:
UNT119 IN GIBB 2.0
END DESCRIPTION:
XS GIS Cut Line= 3
      3610552.62     10204684.07      3610961.90     10205154.14
      3611061.88     10205404.11
#Sta/Elev= 30
  4497.9  230.54  4511.4  229.88  4616.0  226.80  4765.1  219.96  4871.4  216.59
  4885.6  215.85  4899.9  213.95  4914.1  213.17  4922.5  213.56  4944.6  215.85
  4971.1  216.16  4992.0  215.01  4995.6  212.28  4998.4  211.78  5001.6  212.28
  5012.8  214.05  5034.7  215.92  5055.6  215.57  5091.3  216.75  5164.5  216.83
  5194.2  220.42  5218.4  222.40  5237.0  223.08  5242.6  224.29  5296.5  227.03
  5301.9  226.68  5320.7  228.05  5326.1  227.63  5374.6  228.20  5390.4  227.67
#Mann=6,-1,0
  4497.9     0.1       0  4511.4    0.05       0  4922.5     0.1       0
  4944.6    0.16       0  4995.6    0.07       0  5001.6    0.16       0
Bank Sta=4995.6,5001.6
Exp/Cntr=0.3,0.1

Type RM Length L Ch R = 1,1125,0,0,0
BEGIN DESCRIPTION:
UNT119 IN GIBB 1.0
END DESCRIPTION:
XS GIS Cut Line= 3
      3610092.08     10204641.61      3610664.61     10205374.19
      3610892.15     10205441.65
#Sta/Elev= 30
  4287.5  245.54  4344.5  239.67  4408.7  231.13  4458.5  226.74  4472.9  224.34
  4527.7  221.28  4665.6  217.95  4686.4  218.21  4729.8  216.73  4853.1  214.88
  4893.5  213.65  4935.1  214.11  4949.6  212.71  4957.7  212.91  4972.1  211.17
  4978.5  212.61  4981.8  210.98  4982.6  210.58  4985.3  210.08  4988.6  210.58
  5048.1  213.19  5063.5  214.09  5217.3  213.62  5256.1  215.98  5277.2  216.34
  5299.8  213.80  5333.0  214.41  5366.3  220.10  5418.8  225.47  5454.6  229.11
#Mann=8,-1,0
  4287.5    0.16       0  4527.7    0.05       0  4853.1     0.1       0
  4981.8    0.16       0  4982.6    0.07       0  4988.6    0.16       0
  5048.1     0.1       0  5418.8    0.16       0
Bank Sta=4982.6,4988.6
Exp/Cntr=0.3,0.1

Chan Stop Cuts=-1