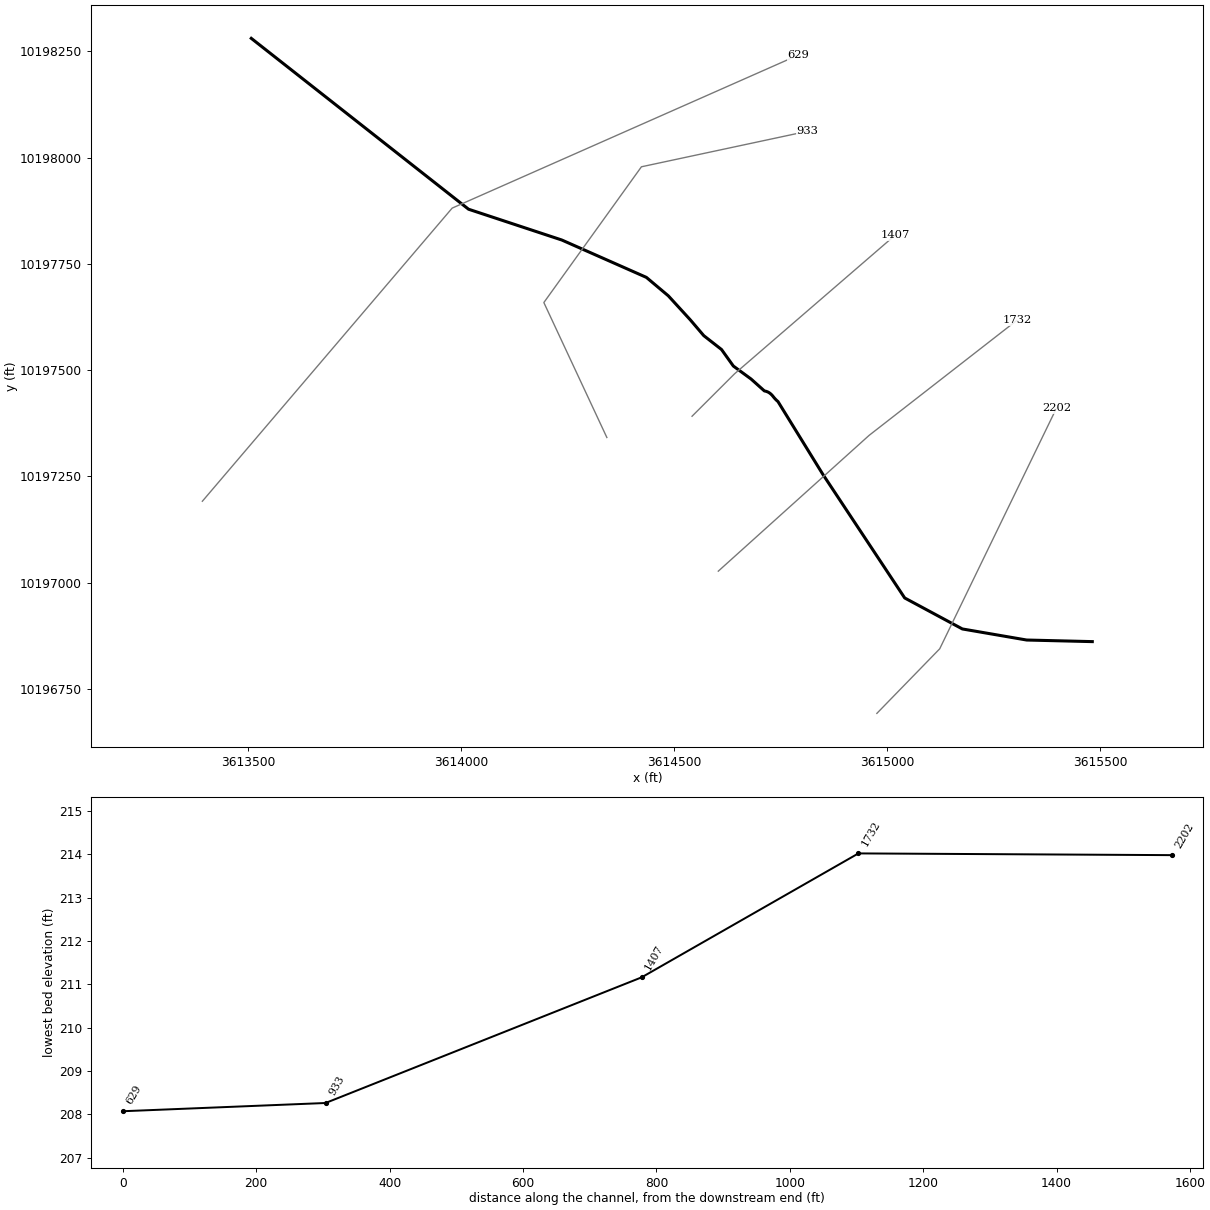
--- UNT140 IN GIBB.prj (project) ---

Proj Title=UNT140 IN GIBB Base Level Engineering
Current Plan=p01
Default Exp/Contr=0.3,0.1
English Units
Geom File=g01
Flow File=f01
Plan File=p01
BEGIN DESCRIPTION:
UNT140 IN GIBB
END DESCRIPTION:

--- UNT140 IN GIBB.p01 (plan) ---

Plan Title=Multiple Run
Short Identifier=Multiple
Geom File=g01
Flow File=f01
Subcritical Flow
K Sum by GR= 0
Std Step Tol= 0.01
Critical Tol= 0.01
Num of Std Step Trials= 20
Max Error Tol= 0.3
Flow Tol Ratio= 0.001
Split Flow NTrial= 30
Split Flow Tol= 0.02
Split Flow Ratio= 0.02
Log Output Level= 0
Friction Slope Method= 1
Unsteady Friction Slope Method= 2
Unsteady Bridges Friction Slope Method= 1
Parabolic Critical Depth
Global Vel Dist=  1 , 1 , 1
Global Log Level= 0
CheckData=True
Encroach Param= -1, 0, 0, 0
BEGIN DESCRIPTION:
Multiple Run
END DESCRIPTION:

--- UNT140 IN GIBB.f01 (steady flow) ---

Flow Title=Multiple
Number of Profiles=7
Profile Names=10-year,25-year,50-year,1pct_min,100-year,1pct_plu,500-year
River Rch & RM= UNT140 IN GIBB,Reach-1,2202
     488     649     779     686     928    1255    1318
Boundary for River Rch & Prof#=UNT140 IN GIBB,Reach-1,1
Up Type=0
Dn Type=3
Dn Slope=0.005
Boundary for River Rch & Prof#=UNT140 IN GIBB,Reach-1,2
Up Type=0
Dn Type=3
Dn Slope=0.005
Boundary for River Rch & Prof#=UNT140 IN GIBB,Reach-1,3
Up Type=0
Dn Type=3
Dn Slope=0.005
Boundary for River Rch & Prof#=UNT140 IN GIBB,Reach-1,4
Up Type=0
Dn Type=3
Dn Slope=0.005
Boundary for River Rch & Prof#=UNT140 IN GIBB,Reach-1,5
Up Type=0
Dn Type=3
Dn Slope=0.005
Boundary for River Rch & Prof#=UNT140 IN GIBB,Reach-1,6
Up Type=0
Dn Type=3
Dn Slope=0.005
Boundary for River Rch & Prof#=UNT140 IN GIBB,Reach-1,7
Up Type=0
Dn Type=3
Dn Slope=0.005

--- UNT140 IN GIBB.g01 (geometry) ---

Geom Title=Existing Conditions

River Reach=UNT140 IN GIBB,Reach-1
Reach XY= 26
      3615482.10     10196861.41      3615328.00     10196865.16
      3615176.96     10196891.21      3615041.54     10196964.12
      3614848.83     10197255.79      3614743.94     10197426.24
      3614740.87     10197428.93      3614737.91     10197431.87
      3614735.15     10197434.96      3614731.52     10197439.45
      3614729.65     10197441.61      3614726.73     10197444.43
      3614723.49     10197446.89      3614719.93     10197448.88
      3614716.08     10197450.32      3614711.98     10197451.31
      3614680.81     10197479.23      3614639.15     10197509.79
      3614611.37     10197548.68      3614569.70     10197581.31
      3614537.76     10197618.81      3614486.37     10197675.06
      3614434.89     10197718.42      3614236.33     10197806.31
      3614017.30     10197878.78      3613506.99     10198280.85

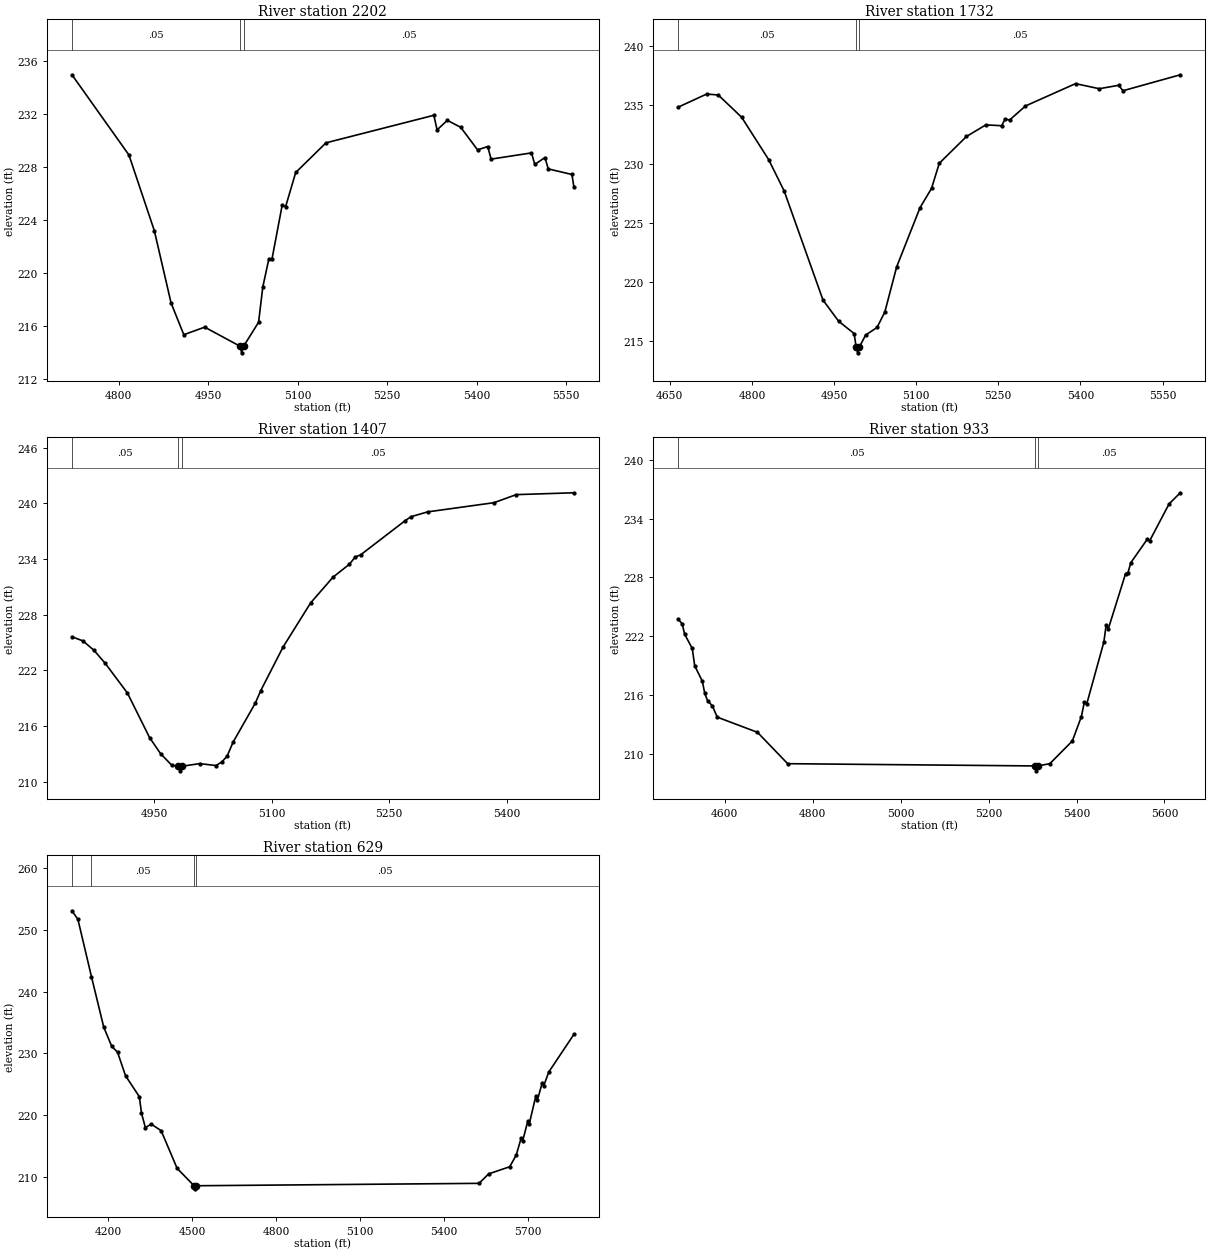
Type RM Length L Ch R = 1,2202,470,470,470
BEGIN DESCRIPTION:
UNT140 IN GIBB 5.0
END DESCRIPTION:
XS GIS Cut Line= 3
      3614976.20     10196692.58      3615123.79     10196844.52
      3615397.97     10197410.70
#Sta/Elev= 30
  4721.8  234.98  4817.3  228.92  4859.8  223.21  4887.9  217.74  4909.2  215.35
  4944.2  215.92  5003.4  214.48  5006.1  213.98  5009.4  214.48  5034.5  216.29
  5041.5  218.94  5051.5  221.03  5057.1  221.10  5074.1  225.15  5079.7  225.01
  5096.7  227.60  5147.4  229.84  5328.1  231.92  5333.6  230.82  5350.7  231.54
  5373.2  231.01  5401.4  229.31  5418.4  229.56  5424.0  228.61  5491.7  229.08
  5497.3  228.21  5514.3  228.73  5519.8  227.87  5559.5  227.45  5562.7  226.52
#Mann=3,-1,0
  4721.8    0.05       0  5003.4   0.033       0  5009.4    0.05       0
Bank Sta=5003.4,5009.4
Exp/Cntr=0.3,0.1

Type RM Length L Ch R = 1,1732,325,325,325
BEGIN DESCRIPTION:
UNT140 IN GIBB 4.0
END DESCRIPTION:
XS GIS Cut Line= 3
      3614603.80     10197027.21      3614957.99     10197346.69
      3615304.63     10197617.06
#Sta/Elev= 30
  4665.8  234.82  4717.4  235.92  4738.6  235.84  4781.2  233.96  4830.5  230.38
  4858.9  227.72  4929.9  218.48  4958.3  216.70  4986.7  215.65  4990.4  214.52
  4993.2  214.02  4996.4  214.52  5007.6  215.52  5028.6  216.17  5042.8  217.48
  5064.4  221.30  5107.0  226.30  5128.0  227.93  5142.2  230.06  5191.9  232.33
  5227.2  233.31  5256.2  233.24  5262.5  233.81  5270.6  233.72  5299.6  234.91
  5391.0  236.80  5434.4  236.37  5469.7  236.66  5477.7  236.20  5582.4  237.55
#Mann=3,-1,0
  4665.8    0.05       0  4990.4   0.035       0  4996.4    0.05       0
Bank Sta=4990.4,4996.4
Exp/Cntr=0.3,0.1

Type RM Length L Ch R = 1,1407,474,474,474
BEGIN DESCRIPTION:
UNT140 IN GIBB 3.0
END DESCRIPTION:
XS GIS Cut Line= 3
      3614542.13     10197391.67      3614642.11     10197491.64
      3615019.16     10197817.75
#Sta/Elev= 30
  4845.4  225.61  4859.5  225.16  4873.6  224.14  4887.8  222.75  4916.1  219.55
  4944.4  214.74  4958.5  213.00  4972.6  211.77  4980.2  211.66  4983.0  211.16
  4986.2  211.66  5008.2  211.94  5029.0  211.73  5036.7  212.13  5043.3  212.76
  5050.9  214.26  5079.3  218.48  5086.0  219.79  5114.6  224.51  5149.7  229.26
  5178.2  232.03  5199.0  233.42  5206.7  234.22  5213.3  234.43  5270.3  238.13
  5277.7  238.55  5298.8  239.07  5383.4  240.06  5411.8  240.93  5485.3  241.13
#Mann=3,-1,0
  4845.4    0.05       0  4980.2   0.035       0  4986.2    0.05       0
Bank Sta=4980.2,4986.2
Exp/Cntr=0.3,0.1

Type RM Length L Ch R = 1,933,304,304,304
BEGIN DESCRIPTION:
UNT140 IN GIBB 2.0
END DESCRIPTION:
XS GIS Cut Line= 4
      3614342.09     10197341.67      3614194.11     10197659.19
      3614423.27     10197978.63      3614812.19     10198061.97
#Sta/Elev= 30
  4494.8  223.71  4503.4  223.26  4509.0  222.20  4526.3  220.75  4531.8  218.99
  4549.2  217.40  4554.7  216.17  4561.0  215.43  4572.0  214.89  4583.1  213.74
  4674.6  212.19  4743.2  208.99  5305.7  208.76  5308.4  208.26  5311.7  208.76
  5339.3  208.99  5390.5  211.31  5410.9  213.78  5417.9  215.29  5423.0  215.05
  5462.1  221.40  5467.3  223.12  5472.4  222.77  5511.6  228.40  5516.7  228.44
  5523.4  229.50  5561.0  231.91  5566.1  231.72  5610.5  235.51  5636.0  236.64
#Mann=3,-1,0
  4494.8    0.05       0  5305.7   0.033       0  5311.7    0.05       0
Bank Sta=5305.7,5311.7
Exp/Cntr=0.3,0.1

Type RM Length L Ch R = 1,629,0,0,0
BEGIN DESCRIPTION:
UNT140 IN GIBB 1.0
END DESCRIPTION:
XS GIS Cut Line= 3
      3613392.14     10197191.68      3613978.83     10197881.41
      3614792.12     10198241.65
#Sta/Elev= 30
  4069.9  253.11  4091.3  251.71  4139.8  242.41  4183.5  234.28  4212.1  231.16
  4232.9  230.21  4261.5  226.39  4310.9  223.00  4318.6  220.33  4332.4  218.00
  4353.7  218.55  4388.9  217.49  4446.0  211.39  4506.7  208.57  4509.4  208.07
  4512.7  208.57  5525.8  208.96  5560.2  210.49  5635.5  211.65  5658.8  213.53
  5676.6  216.32  5682.1  215.86  5699.9  219.01  5705.3  218.57  5728.6  223.04
  5734.1  222.38  5751.9  225.26  5757.4  224.79  5775.2  226.99  5864.9  233.08
#Mann=4,-1,0
  4069.9    0.16       0  4139.8    0.05       0  4506.7   0.033       0
  4512.7    0.05       0
Bank Sta=4506.7,4512.7
Exp/Cntr=0.3,0.1

Chan Stop Cuts=-1