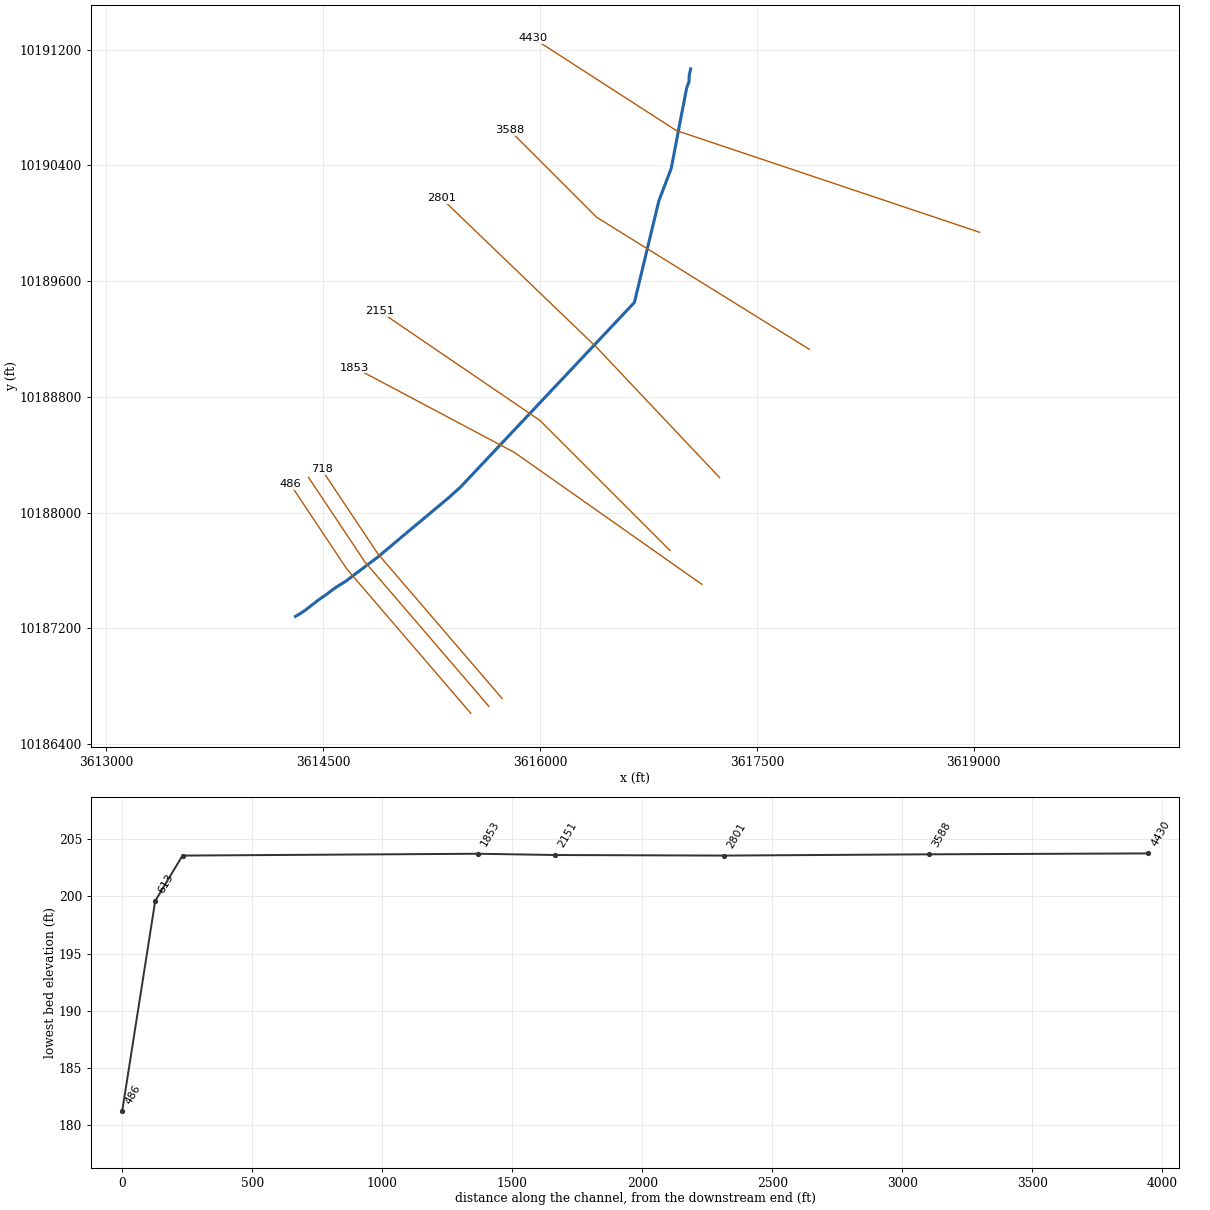
--- UNT141 IN GIBB.prj (project) ---

Proj Title=UNT141 IN GIBB Base Level Engineering
Current Plan=p01
Default Exp/Contr=0.3,0.1
English Units
Geom File=g01
Flow File=f01
Plan File=p01
BEGIN DESCRIPTION:
UNT141 IN GIBB
END DESCRIPTION:

--- UNT141 IN GIBB.p01 (plan) ---

Plan Title=Multiple Run
Short Identifier=Multiple
Geom File=g01
Flow File=f01
Subcritical Flow
K Sum by GR= 0
Std Step Tol= 0.01
Critical Tol= 0.01
Num of Std Step Trials= 20
Max Error Tol= 0.3
Flow Tol Ratio= 0.001
Split Flow NTrial= 30
Split Flow Tol= 0.02
Split Flow Ratio= 0.02
Log Output Level= 0
Friction Slope Method= 1
Unsteady Friction Slope Method= 2
Unsteady Bridges Friction Slope Method= 1
Parabolic Critical Depth
Global Vel Dist=  1 , 1 , 1
Global Log Level= 0
CheckData=True
Encroach Param= -1, 0, 0, 0
BEGIN DESCRIPTION:
Multiple Run
END DESCRIPTION:

--- UNT141 IN GIBB.f01 (steady flow) ---

Flow Title=Multiple
Number of Profiles=7
Profile Names=10-year,25-year,50-year,1pct_min,100-year,1pct_plu,500-year
River Rch & RM= UNT141 IN GIBB,Reach-1,4430
     574     773     935     831    1123    1519    1621
Boundary for River Rch & Prof#=UNT141 IN GIBB,Reach-1,1
Up Type=0
Dn Type=3
Dn Slope=0.005
Boundary for River Rch & Prof#=UNT141 IN GIBB,Reach-1,2
Up Type=0
Dn Type=3
Dn Slope=0.005
Boundary for River Rch & Prof#=UNT141 IN GIBB,Reach-1,3
Up Type=0
Dn Type=3
Dn Slope=0.005
Boundary for River Rch & Prof#=UNT141 IN GIBB,Reach-1,4
Up Type=0
Dn Type=3
Dn Slope=0.005
Boundary for River Rch & Prof#=UNT141 IN GIBB,Reach-1,5
Up Type=0
Dn Type=3
Dn Slope=0.005
Boundary for River Rch & Prof#=UNT141 IN GIBB,Reach-1,6
Up Type=0
Dn Type=3
Dn Slope=0.005
Boundary for River Rch & Prof#=UNT141 IN GIBB,Reach-1,7
Up Type=0
Dn Type=3
Dn Slope=0.005

--- UNT141 IN GIBB.g01 (geometry) ---

Geom Title=Existing Conditions

River Reach=UNT141 IN GIBB,Reach-1
Reach XY= 21
      3617042.11     10191067.82      3617031.85     10191023.22
      3617030.97     10190980.50      3617015.31     10190938.62
      3616977.95     10190747.41      3616907.81     10190380.05
      3616822.19     10190155.07      3616652.92     10189452.56
      3615451.55     10188176.88      3615366.97     10188100.84
      3615050.30     10187836.26      3614884.16     10187696.16
      3614741.45     10187588.86      3614660.20     10187526.89
      3614586.76     10187481.05      3614519.05     10187430.53
      3614470.09     10187396.68      3614424.26     10187361.26
      3614374.78     10187322.72      3614339.89     10187299.80
      3614308.86     10187281.66

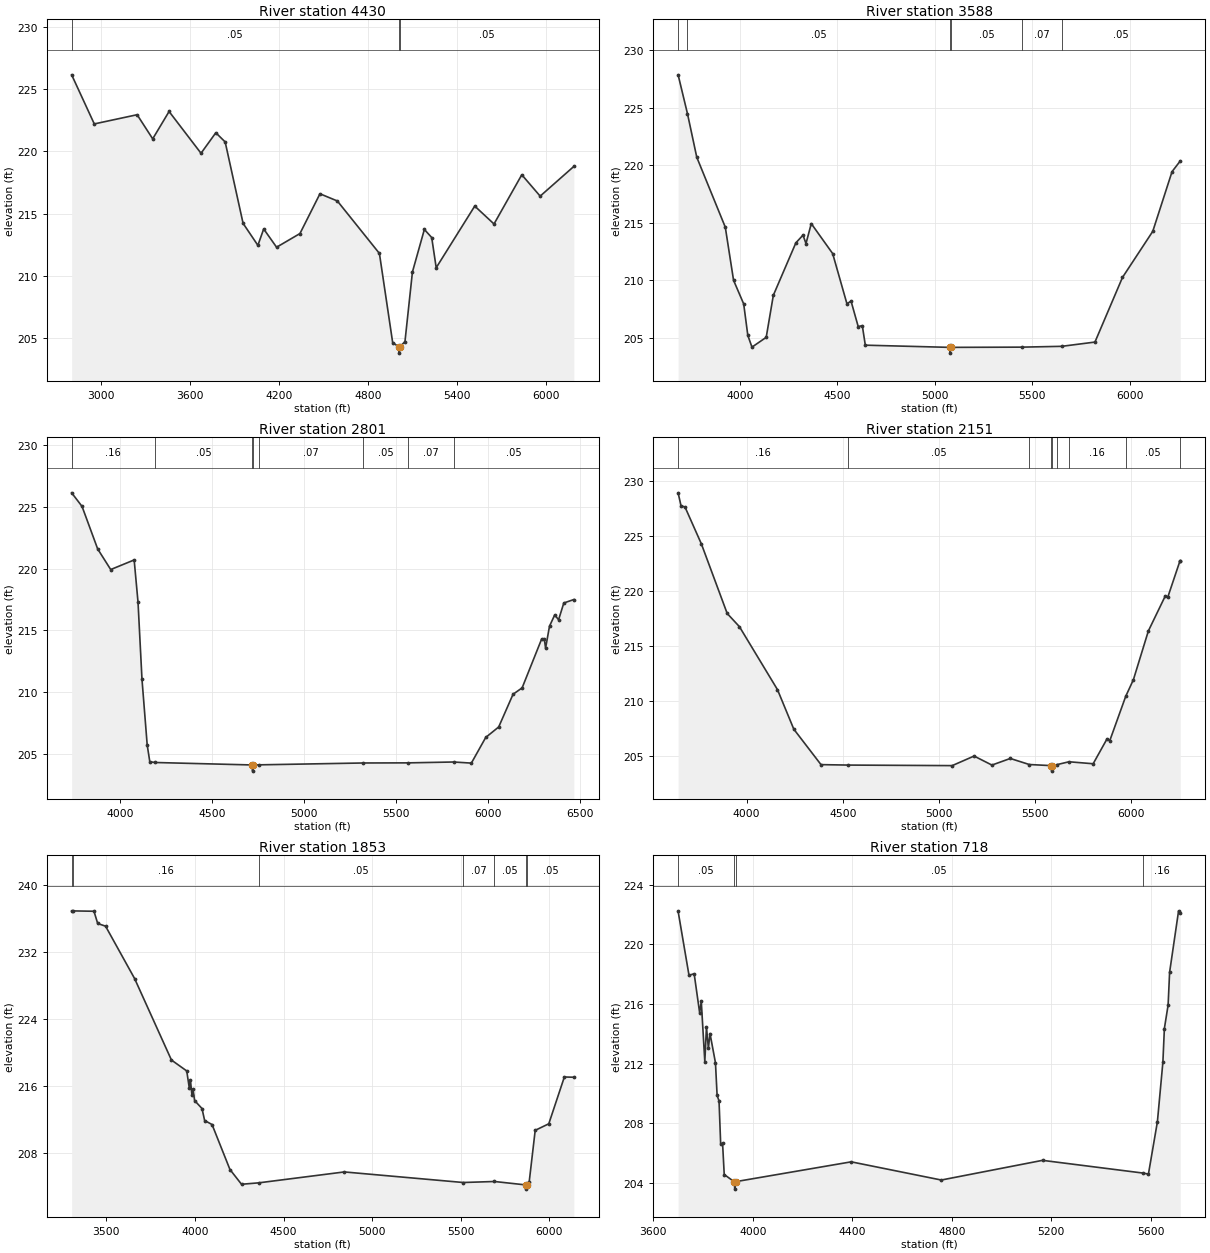
Type RM Length L Ch R = 1,4430,842,842,842
BEGIN DESCRIPTION:
UNT141 IN GIBB 10.0
END DESCRIPTION:
XS GIS Cut Line= 3
      3619040.57     10189937.65      3616942.11     10190641.64
      3615954.63     10191278.80
#Sta/Elev= 30
  2802.1  226.16  2954.8  222.21  3243.9  222.95  3349.0  221.01  3459.5  223.21
  3675.0  219.85  3774.9  221.50  3838.0  220.76  3958.9  214.21  4058.8  212.44
  4097.9  213.76  4184.9  212.29  4342.6  213.39  4477.6  216.59  4595.0  216.01
  4878.8  211.79  4968.2  204.62  5009.9  204.27  5012.6  203.77  5015.9  204.27
  5051.2  204.70  5101.6  210.30  5182.1  213.72  5231.6  213.07  5262.0  210.64
  5522.0  215.60  5652.0  214.16  5839.5  218.12  5963.5  216.40  6190.7  218.79
#Mann=3,-1,0
  2802.1    0.05       0  5009.9    0.03       0  5015.9    0.05       0
Bank Sta=5009.9,5015.9
Exp/Cntr=0.3,0.1

Type RM Length L Ch R = 1,3588,787,787,787
BEGIN DESCRIPTION:
UNT141 IN GIBB 8.0
END DESCRIPTION:
XS GIS Cut Line= 3
      3617862.60     10189128.64      3616392.11     10190041.64
      3615792.11     10190641.64
#Sta/Elev= 30
  3681.5  227.84  3729.5  224.47  3777.3  220.69  3923.8  214.62  3966.3  210.01
  4018.3  207.96  4039.5  205.23  4060.8  204.21  4134.0  205.06  4170.6  208.71
  4286.3  213.26  4322.9  213.93  4338.3  213.20  4365.4  214.93  4475.3  212.33
  4548.5  207.98  4569.8  208.20  4606.4  206.00  4627.6  206.07  4643.0  204.38
  5075.8  204.19  5078.5  203.69  5081.8  204.19  5448.2  204.21  5651.9  204.28
  5822.5  204.65  5963.9  210.26  6119.5  214.26  6218.5  219.44  6260.9  220.37
#Mann=6,-1,0
  3681.5    0.16       0  3729.5    0.05       0  5075.8   0.033       0
  5081.8    0.05       0  5448.2    0.07       0  5651.9    0.05       0
Bank Sta=5075.8,5081.8
Exp/Cntr=0.3,0.1

Type RM Length L Ch R = 1,2801,650,650,650
BEGIN DESCRIPTION:
UNT141 IN GIBB 6.0
END DESCRIPTION:
XS GIS Cut Line= 3
      3617242.08     10188241.66      3616392.11     10189141.64
      3615317.65     10190174.22
#Sta/Elev= 30
  3738.8  226.14  3795.2  225.04  3880.2  221.59  3951.0  219.92  4078.4  220.70
  4099.4  217.27  4120.9  211.02  4149.2  205.70  4163.4  204.34  4191.4  204.28
  4719.0  204.08  4721.8  203.58  4725.0  204.08  4758.4  204.09  5322.3  204.24
  5567.3  204.25  5814.5  204.32  5910.2  204.23  5988.2  206.31  6058.7  207.16
  6136.6  209.81  6186.0  210.33  6292.3  214.30  6306.4  214.29  6313.4  213.55
  6334.7  215.33  6363.0  216.24  6384.1  215.85  6412.4  217.21  6466.9  217.49
#Mann=8,-1,0
  3738.8    0.16       0  4191.4    0.05       0  4719.0    0.07       0
  4725.0    0.05       0  4758.4    0.07       0  5322.3    0.05       0
  5567.3    0.07       0  5814.5    0.05       0
Bank Sta=4719,4725
Exp/Cntr=0.3,0.1

Type RM Length L Ch R = 1,2151,298,298,298
BEGIN DESCRIPTION:
UNT141 IN GIBB 4.0
END DESCRIPTION:
XS GIS Cut Line= 3
      3616899.03     10187737.49      3615999.05     10188637.48
      3614892.11     10189391.64
#Sta/Elev= 30
  3643.4  228.91  3658.3  227.75  3679.5  227.61  3764.4  224.27  3898.7  217.95
  3962.4  216.75  4160.3  211.03  4245.2  207.44  4386.6  204.22  4529.5  204.18
  5069.1  204.13  5182.9  205.00  5275.7  204.18  5371.3  204.78  5470.2  204.23
  5583.8  204.13  5586.6  203.63  5589.8  204.13  5616.5  204.23  5676.6  204.48
  5802.3  204.30  5874.1  206.55  5889.0  206.41  5971.6  210.42  6011.7  211.94
  6089.6  216.37  6176.3  219.50  6191.2  219.47  6254.1  222.74  6255.6  222.74
#Mann=9,-1,0
  3643.4    0.16       0  4529.5    0.05       0  5470.2    0.07       0
  5583.8   0.033       0  5589.8    0.07       0  5616.5    0.05       0
  5676.6    0.16       0  5971.6    0.05       0  6254.1    0.16       0
Bank Sta=5583.8,5589.8
Exp/Cntr=0.3,0.1

Type RM Length L Ch R = 1,1853,1135,1135,1135
BEGIN DESCRIPTION:
UNT141 IN GIBB 3.0
END DESCRIPTION:
XS GIS Cut Line= 3
      3617119.54     10187503.64      3615824.21     10188415.24
      3614719.49     10189001.53
#Sta/Elev= 30
  3304.2  236.92  3311.8  236.91  3430.2  236.87  3451.2  235.41  3495.6  235.09
  3659.4  228.85  3867.5  219.13  3953.8  217.83  3968.6  215.75  3974.7  216.73
  3983.4  214.91  3989.5  215.65  3998.1  214.30  4040.0  213.35  4054.8  211.92
  4096.7  211.44  4197.7  206.08  4263.0  204.32  4360.5  204.49  4843.2  205.79
  5514.5  204.53  5690.7  204.65  5868.1  204.24  5870.8  203.74  5874.1  204.24
  5886.8  204.60  5920.7  210.75  5997.4  211.53  6085.3  217.11  6138.8  217.08
#Mann=7,-1,0
  3304.2    0.05       0  3311.8    0.16       0  4360.5    0.05       0
  5514.5    0.07       0  5690.7    0.05       0  5868.1   0.033       0
  5874.1    0.05       0
Bank Sta=5868.1,5874.1
Exp/Cntr=0.3,0.1

Type RM Length L Ch R = 1,718,105,105,105
BEGIN DESCRIPTION:
UNT141 IN GIBB 1.2
END DESCRIPTION:
XS GIS Cut Line= 3
      3615737.32     10186715.54      3614880.09     10187713.84
      3614490.49     10188298.23
#Sta/Elev= 30
  3700.3  222.21  3744.0  217.92  3764.8  218.02  3786.8  215.41  3793.4  216.17
  3807.6  212.12  3814.2  214.46  3821.9  213.03  3828.5  214.01  3850.4  212.05
  3857.0  209.86  3864.7  209.50  3871.3  206.61  3879.0  206.65  3885.6  204.56
  3925.3  204.08  3928.1  203.58  3931.3  204.08  4395.9  205.41  4758.0  204.19
  5164.7  205.51  5567.2  204.66  5590.4  204.59  5626.4  208.09  5648.5  212.09
  5654.5  214.35  5669.5  215.92  5675.5  218.12  5711.6  222.24  5718.5  222.11
#Mann=4,-1,0
  3700.3    0.05       0  3925.3   0.033       0  3931.3    0.05       0
  5567.2    0.16       0
Bank Sta=3925.3,3931.3
Exp/Cntr=0.3,0.1

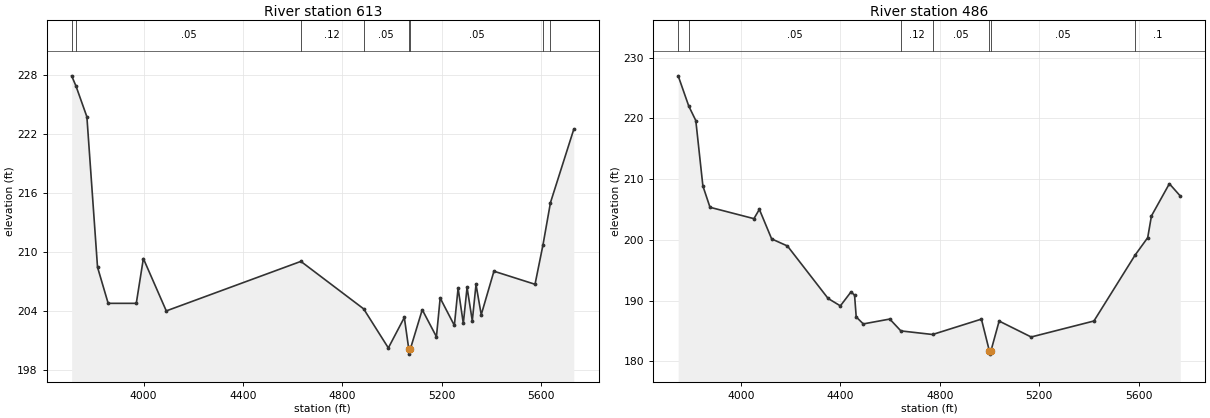
Type RM Length L Ch R = 1,613,127,127,127
BEGIN DESCRIPTION:
UNT141 IN GIBB 1.1
END DESCRIPTION:
XS GIS Cut Line= 3
      3615647.00     10186660.03      3614789.81     10187658.28
      3614399.18     10188244.23
#Sta/Elev= 30
  3710.7  227.94  3728.1  226.90  3772.0  223.77  3814.8  208.46  3857.6  204.78
  3970.7  204.78  3999.2  209.34  4091.4  204.01  4632.9  209.05  4885.3  204.22
  4984.7  200.24  5049.0  203.34  5067.0  200.11  5069.7  199.61  5073.0  200.11
  5121.1  204.13  5178.2  201.38  5193.2  205.32  5250.3  202.53  5265.3  206.33
  5286.3  202.74  5301.4  206.40  5322.4  203.00  5337.4  206.70  5358.4  203.62
  5409.5  208.05  5574.8  206.72  5606.5  210.69  5637.0  215.04  5730.7  222.50
#Mann=8,-1,0
  3710.7    0.16       0  3728.1    0.05       0  4632.9    0.12       0
  4885.3    0.05       0  5067.0    0.03       0  5073.0    0.05       0
  5606.5     0.1       0  5637.0    0.16       0
Bank Sta=5067,5073
Exp/Cntr=0.3,0.1

Type RM Length L Ch R = 1,486,0,0,0
BEGIN DESCRIPTION:
UNT141 IN GIBB 1.0
END DESCRIPTION:
XS GIS Cut Line= 3
      3615522.03     10186611.38      3614664.81     10187609.67
      3614274.21     10188195.57
#Sta/Elev= 30
  3747.3  227.00  3789.8  222.03  3818.2  219.64  3846.7  208.88  3875.3  205.37
  4052.0  203.50  4073.9  205.03  4123.3  200.17  4186.9  199.00  4350.4  190.37
  4399.8  189.15  4442.6  191.45  4456.9  190.91  4463.5  187.33  4492.0  186.18
  4598.5  186.98  4643.2  185.03  4770.8  184.44  4967.2  186.97  4999.3  181.71
  5002.1  181.21  5005.3  181.71  5038.5  186.65  5167.4  184.03  5419.8  186.66
  5585.0  197.48  5636.1  200.37  5651.2  203.95  5723.3  209.25  5767.3  207.22
#Mann=7,-1,0
  3747.3    0.16       0  3789.8    0.05       0  4643.2    0.12       0
  4770.8    0.05       0  4999.3    0.03       0  5005.3    0.05       0
  5585.0     0.1       0
Bank Sta=4999.3,5005.3
Exp/Cntr=0.3,0.1

Chan Stop Cuts=-1