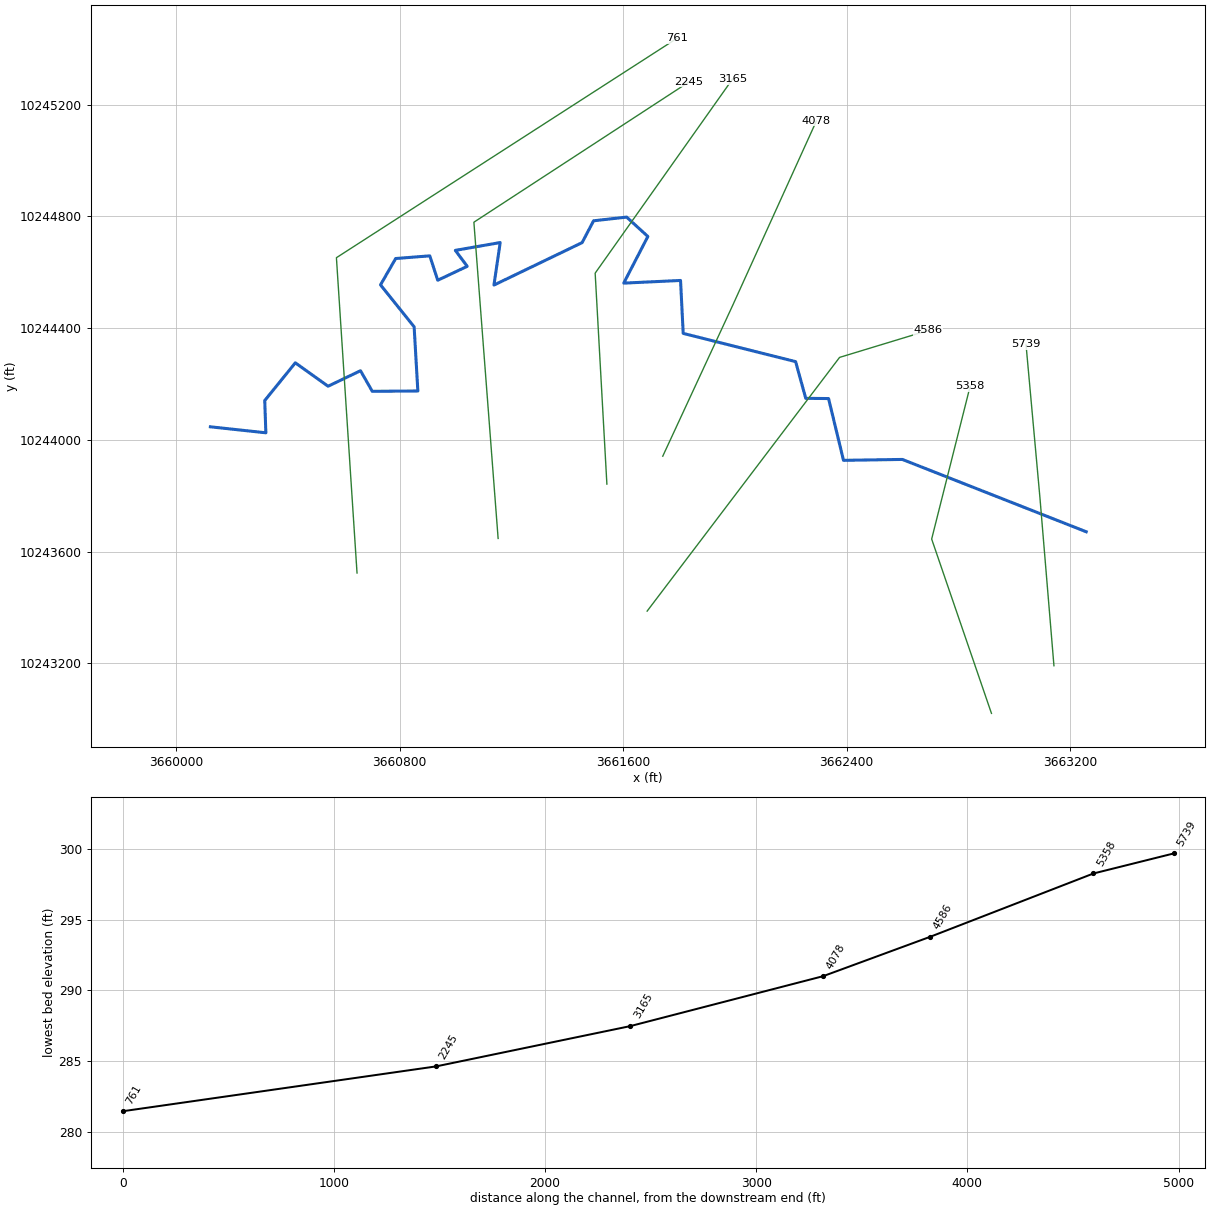
--- UNT142 IN GIBB.prj (project) ---

Proj Title=UNT142 IN GIBB Base Level Engineering
Current Plan=p01
Default Exp/Contr=0.3,0.1
English Units
Geom File=g01
Flow File=f01
Plan File=p01
BEGIN DESCRIPTION:
UNT142 IN GIBB
END DESCRIPTION:

--- UNT142 IN GIBB.p01 (plan) ---

Plan Title=Multiple Run
Short Identifier=Multiple
Geom File=g01
Flow File=f01
Subcritical Flow
K Sum by GR= 0
Std Step Tol= 0.01
Critical Tol= 0.01
Num of Std Step Trials= 20
Max Error Tol= 0.3
Flow Tol Ratio= 0.001
Split Flow NTrial= 30
Split Flow Tol= 0.02
Split Flow Ratio= 0.02
Log Output Level= 0
Friction Slope Method= 1
Unsteady Friction Slope Method= 2
Unsteady Bridges Friction Slope Method= 1
Parabolic Critical Depth
Global Vel Dist=  1 , 1 , 1
Global Log Level= 0
CheckData=True
Encroach Param= -1, 0, 0, 0
BEGIN DESCRIPTION:
Multiple Run
END DESCRIPTION:

--- UNT142 IN GIBB.f01 (steady flow) ---

Flow Title=Multiple
Number of Profiles=7
Profile Names=10-year,25-year,50-year,1pct_min,100-year,1pct_plu,500-year
River Rch & RM= UNT142 IN GIBB,Reach-1,5739
     359     460     538     462     624     844     839
Boundary for River Rch & Prof#=UNT142 IN GIBB,Reach-1,1
Up Type=0
Dn Type=3
Dn Slope=0.005
Boundary for River Rch & Prof#=UNT142 IN GIBB,Reach-1,2
Up Type=0
Dn Type=3
Dn Slope=0.005
Boundary for River Rch & Prof#=UNT142 IN GIBB,Reach-1,3
Up Type=0
Dn Type=3
Dn Slope=0.005
Boundary for River Rch & Prof#=UNT142 IN GIBB,Reach-1,4
Up Type=0
Dn Type=3
Dn Slope=0.005
Boundary for River Rch & Prof#=UNT142 IN GIBB,Reach-1,5
Up Type=0
Dn Type=3
Dn Slope=0.005
Boundary for River Rch & Prof#=UNT142 IN GIBB,Reach-1,6
Up Type=0
Dn Type=3
Dn Slope=0.005
Boundary for River Rch & Prof#=UNT142 IN GIBB,Reach-1,7
Up Type=0
Dn Type=3
Dn Slope=0.005

--- UNT142 IN GIBB.g01 (geometry) ---

Geom Title=Existing Conditions

River Reach=UNT142 IN GIBB,Reach-1
Reach XY= 30
      3663257.56     10243671.15      3662599.55     10243929.99
      3662388.97     10243926.73      3662335.47     10244147.87
      3662253.83     10244148.66      3662217.59     10244279.95
      3661815.25     10244381.08      3661805.70     10244570.53
      3661602.36     10244560.98      3661688.73     10244727.87
      3661612.77     10244797.31      3661494.50     10244784.07
      3661453.49     10244705.95      3661137.95     10244554.04
      3661160.30     10244706.17      3660999.71     10244678.17
      3661042.25     10244621.10      3660936.78     10244571.27
      3660908.30     10244658.60      3660786.26     10244649.05
      3660731.92     10244554.78      3660852.23     10244404.60
      3660865.56     10244174.98      3660702.48     10244173.72
      3660660.30     10244247.44      3660544.24     10244191.97
      3660427.05     10244275.74      3660317.58     10244140.76
      3660321.59     10244025.31      3660123.04     10244046.75

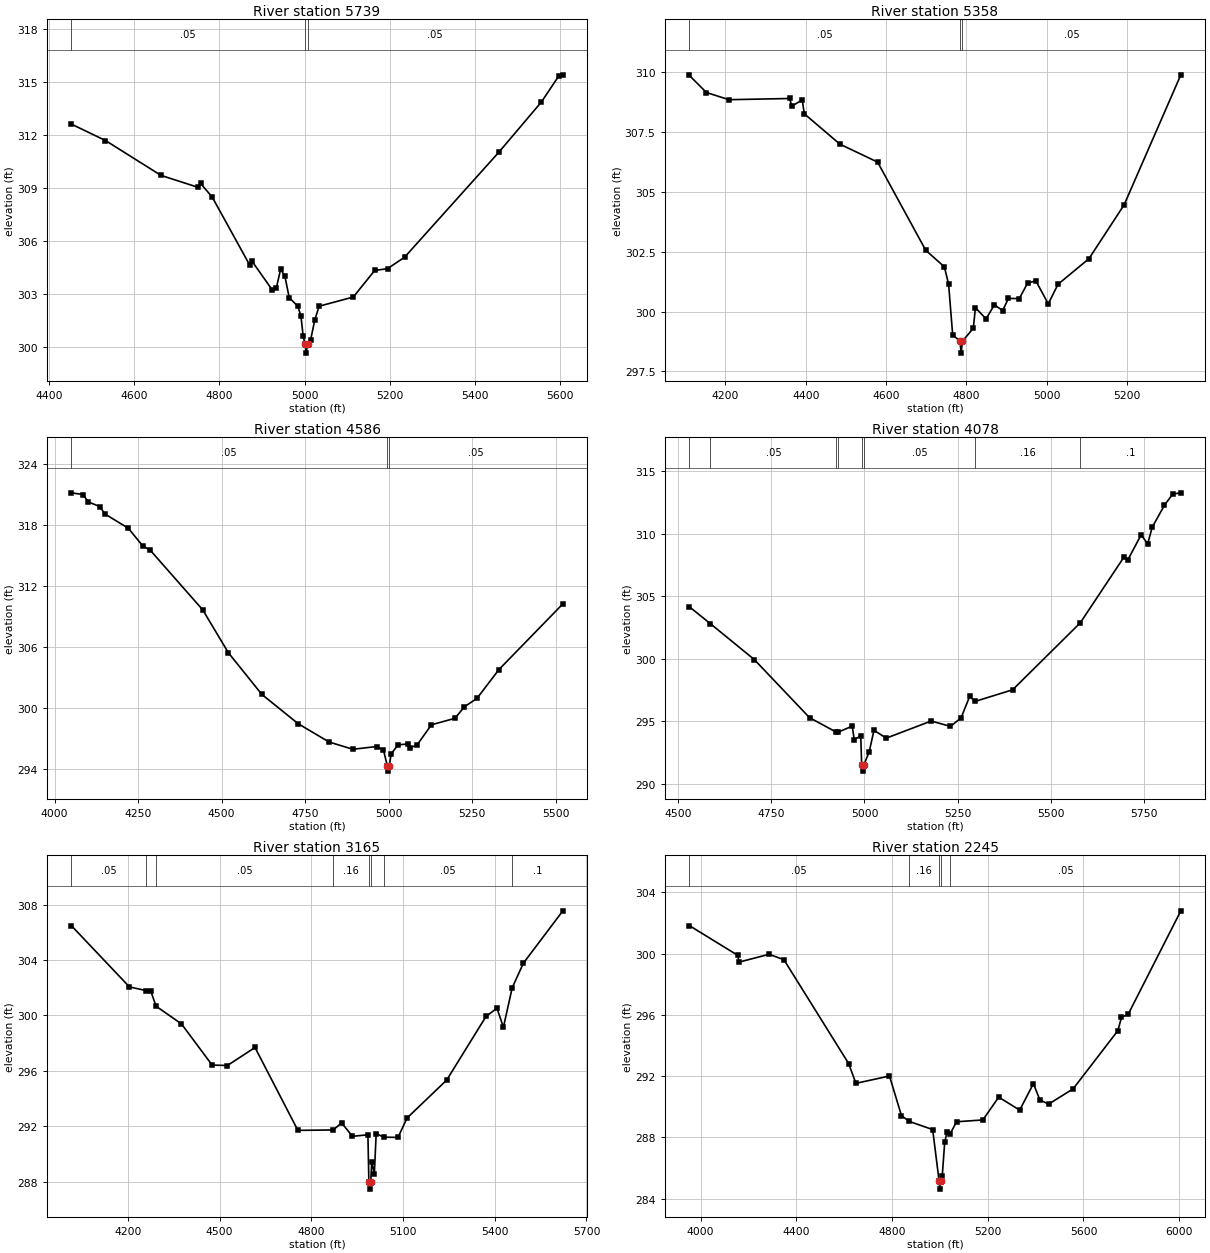
Type RM Length L Ch R = 1,5739,381,381,381
BEGIN DESCRIPTION:
UNT142 IN GIBB 7.0
END DESCRIPTION:
XS GIS Cut Line= 3
      3663142.10     10243191.67      3663092.11     10243791.64
      3663042.11     10244341.62
#Sta/Elev= 30
  4452.2  312.62  4532.5  311.69  4662.9  309.72  4750.7  309.04  4755.7  309.27
  4783.3  308.49  4871.1  304.66  4876.1  304.89  4923.8  303.26  4933.8  303.37
  4943.9  304.42  4953.9  304.02  4963.9  302.82  4984.0  302.33  4991.5  301.79
  4996.6  300.66  5001.1  300.18  5003.8  299.68  5007.1  300.18  5014.1  300.41
  5024.2  301.57  5034.2  302.33  5114.5  302.85  5164.7  304.35  5194.8  304.45
  5235.0  305.10  5455.9  311.02  5556.3  313.87  5596.5  315.32  5606.5  315.40
#Mann=3,-1,0
  4452.2    0.05       0  5001.1    0.03       0  5007.1    0.05       0
Bank Sta=5001.1,5007.1
Exp/Cntr=0.3,0.1

Type RM Length L Ch R = 1,5358,772,772,772
BEGIN DESCRIPTION:
UNT142 IN GIBB 6.0
END DESCRIPTION:
XS GIS Cut Line= 3
      3662918.47     10243021.14      3662704.47     10243645.03
      3662842.09     10244191.60
#Sta/Elev= 30
  4110.2  309.88  4153.0  309.16  4209.0  308.86  4360.1  308.91  4365.4  308.59
  4391.3  308.85  4396.6  308.27  4485.1  307.00  4578.9  306.25  4698.7  302.56
  4745.0  301.87  4755.6  301.14  4765.7  299.02  4783.9  298.76  4786.7  298.26
  4789.9  298.76  4817.1  299.30  4822.3  300.16  4848.8  299.69  4869.4  300.28
  4890.0  300.04  4904.5  300.55  4931.3  300.54  4951.9  301.18  4972.5  301.29
  5003.5  300.32  5027.8  301.14  5104.8  302.21  5192.2  304.46  5333.4  309.90
#Mann=3,-1,0
  4110.2    0.05       0  4783.9    0.03       0  4789.9    0.05       0
Bank Sta=4783.9,4789.9
Exp/Cntr=0.3,0.1

Type RM Length L Ch R = 1,4586,508,508,508
BEGIN DESCRIPTION:
UNT142 IN GIBB 4.0
END DESCRIPTION:
XS GIS Cut Line= 3
      3661686.22     10243387.20      3662374.89     10244295.18
      3662692.14     10244391.65
#Sta/Elev= 30
  4050.1  321.18  4085.9  321.01  4100.4  320.29  4135.8  319.83  4150.3  319.11
  4221.1  317.69  4264.7  315.93  4285.5  315.57  4443.6  309.66  4520.6  305.43
  4620.5  301.34  4728.6  298.47  4821.3  296.66  4892.9  295.94  4963.7  296.21
  4984.5  295.87  4996.0  294.29  4998.8  293.79  5002.0  294.29  5007.3  295.47
  5028.1  296.38  5057.2  296.46  5063.5  296.08  5084.9  296.36  5128.0  298.35
  5198.6  298.99  5226.2  300.11  5264.3  300.95  5330.1  303.79  5521.3  310.25
#Mann=3,-1,0
  4050.1    0.05       0  4996.0   0.035       0  5002.0    0.05       0
Bank Sta=4996,5002
Exp/Cntr=0.3,0.1

Type RM Length L Ch R = 1,4078,913,913,913
BEGIN DESCRIPTION:
UNT142 IN GIBB 3.0
END DESCRIPTION:
XS GIS Cut Line= 3
      3661742.11     10243941.66      3661992.94     10244482.68
      3662292.09     10245141.61
#Sta/Elev= 30
  4529.5  304.16  4586.3  302.80  4704.1  299.93  4852.5  295.28  4924.3  294.12
  4928.8  294.11  4967.1  294.60  4972.6  293.52  4990.0  293.82  4992.5  291.50
  4995.3  291.00  4998.5  291.50  5012.9  292.56  5025.5  294.27  5058.6  293.64
  5179.2  295.01  5230.9  294.58  5259.4  295.26  5282.5  296.98  5297.2  296.58
  5397.9  297.51  5579.6  302.87  5696.8  308.13  5706.8  307.88  5742.9  309.91
  5760.5  309.19  5772.7  310.52  5805.6  312.28  5827.6  313.17  5849.5  313.27
#Mann=8,-1,0
  4529.5    0.16       0  4586.3    0.05       0  4924.3    0.16       0
  4928.8    0.05       0  4992.5    0.03       0  4998.5    0.05       0
  5297.2    0.16       0  5579.6     0.1       0
Bank Sta=4992.5,4998.5
Exp/Cntr=0.3,0.1

Type RM Length L Ch R = 1,3165,920,920,920
BEGIN DESCRIPTION:
UNT142 IN GIBB 2.0
END DESCRIPTION:
XS GIS Cut Line= 3
      3661542.10     10243841.68      3661500.16     10244596.70
      3661992.09     10245291.62
#Sta/Elev= 30
  4015.2  306.49  4205.5  302.06  4261.1  301.79  4275.6  301.74  4292.5  300.67
  4375.7  299.39  4475.9  296.42  4525.9  296.39  4616.1  297.69  4756.3  291.71
  4871.9  291.74  4899.2  292.25  4934.9  291.28  4985.3  291.39  4988.5  287.97
  4991.2  287.47  4994.5  287.97  4998.0  289.46  5006.3  288.56  5012.4  291.48
  5036.3  291.22  5083.7  291.20  5113.3  292.60  5243.0  295.34  5371.8  299.94
  5407.4  300.52  5428.4  299.15  5457.2  302.00  5493.6  303.77  5622.8  307.55
#Mann=8,-1,0
  4015.2    0.05       0  4261.1    0.16       0  4292.5    0.05       0
  4871.9    0.16       0  4988.5    0.07       0  4994.5    0.16       0
  5036.3    0.05       0  5457.2     0.1       0
Bank Sta=4988.5,4994.5
Exp/Cntr=0.3,0.1

Type RM Length L Ch R = 1,2245,1484,1484,1484
BEGIN DESCRIPTION:
UNT142 IN GIBB 1.1
END DESCRIPTION:
XS GIS Cut Line= 3
      3661152.86     10243647.20      3661066.13     10244778.99
      3661836.19     10245281.27
#Sta/Elev= 30
  3952.5  301.84  4155.6  299.89  4160.6  299.45  4286.2  299.96  4348.1  299.61
  4618.9  292.82  4649.0  291.53  4789.4  292.01  4839.5  289.42  4872.5  289.04
  4969.9  288.51  4997.0  285.12  4999.8  284.62  5003.0  285.12  5010.0  285.50
  5020.1  287.67  5030.1  288.37  5043.2  288.25  5070.0  289.02  5179.6  289.14
  5246.0  290.63  5333.5  289.78  5390.9  291.51  5417.9  290.45  5454.1  290.17
  5556.8  291.17  5743.8  294.97  5759.0  295.84  5787.2  296.05  6007.0  302.80
#Mann=5,-1,0
  3952.5    0.05       0  4872.5    0.16       0  4997.0    0.07       0
  5003.0    0.16       0  5043.2    0.05       0
Bank Sta=4997,5003
Exp/Cntr=0.3,0.1

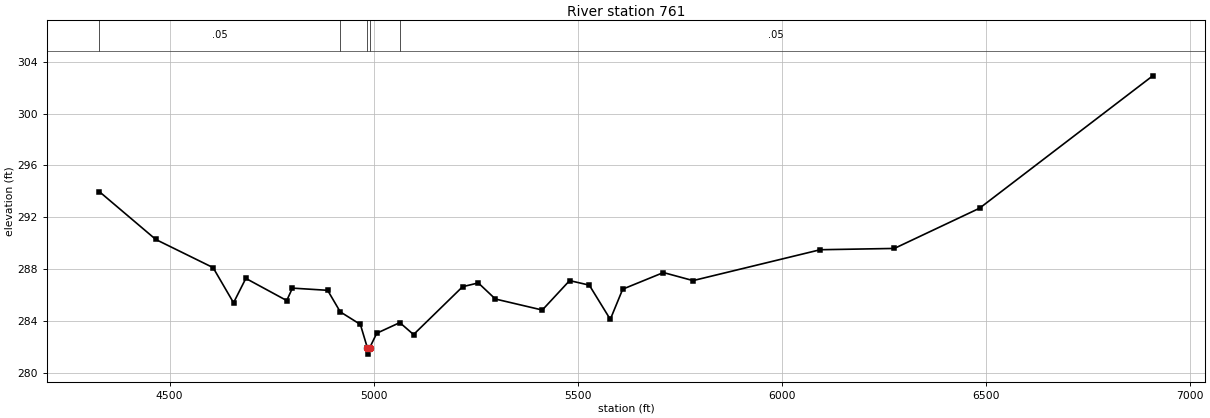
Type RM Length L Ch R = 1,761,0,0,0
BEGIN DESCRIPTION:
UNT142 IN GIBB 1.0
END DESCRIPTION:
XS GIS Cut Line= 3
      3660647.89     10243523.52      3660574.11     10244651.95
      3661792.99     10245437.07
#Sta/Elev= 30
  4328.1  293.98  4466.5  290.29  4606.8  288.12  4656.9  285.41  4687.0  287.29
  4787.2  285.58  4801.1  286.54  4887.4  286.37  4918.3  284.71  4967.6  283.74
  4984.6  281.95  4987.4  281.45  4990.6  281.95  5007.7  283.06  5064.2  283.88
  5097.9  282.96  5218.1  286.65  5256.5  286.94  5298.3  285.70  5413.3  284.85
  5480.2  287.12  5528.4  286.77  5579.9  284.13  5610.3  286.46  5710.0  287.74
  5782.6  287.12  6094.2  289.50  6275.8  289.60  6484.4  292.70  6908.8  302.91
#Mann=5,-1,0
  4328.1    0.05       0  4918.3    0.12       0  4984.6    0.07       0
  4990.6    0.12       0  5064.2    0.05       0
Bank Sta=4984.6,4990.6
Exp/Cntr=0.3,0.1

Chan Stop Cuts=-1