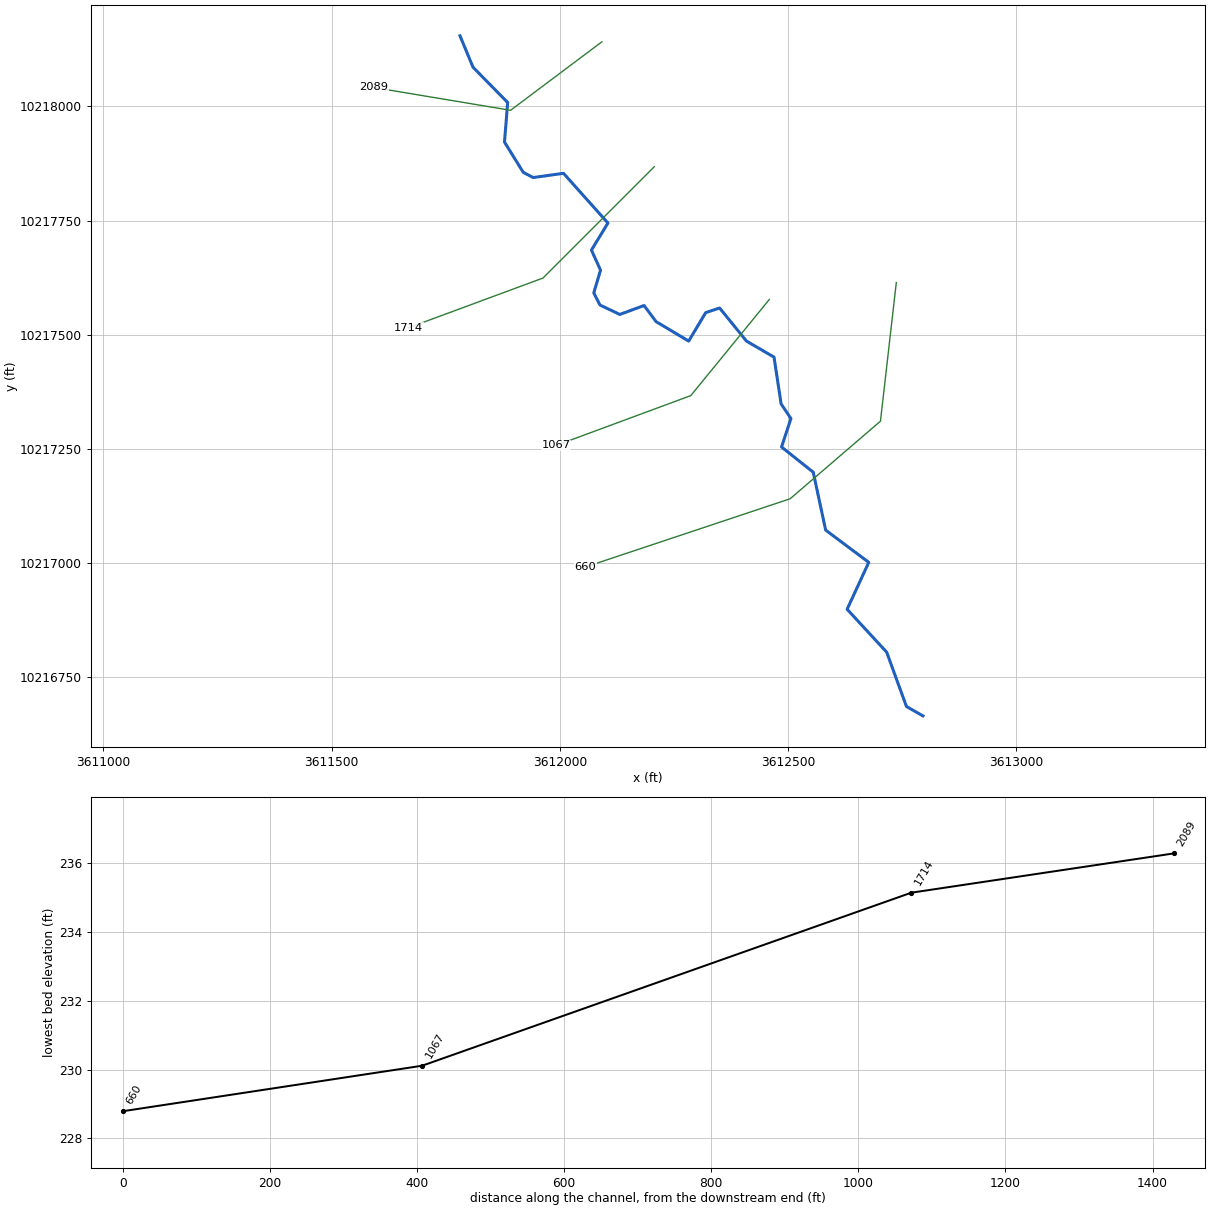
--- UNT147 IN GIBB.prj (project) ---

Proj Title=UNT147 IN GIBB Base Level Engineering
Current Plan=p01
Default Exp/Contr=0.3,0.1
English Units
Geom File=g01
Flow File=f01
Plan File=p01
Y Axis Title=Elevation
X Axis Title(PF)=Main Channel Distance
X Axis Title(XS)=Station
BEGIN DESCRIPTION:
UNT147 IN GIBB
END DESCRIPTION:
DSS Export Rating Curves= 0
DSS Export Rating Curve Sorted= 0
DSS Export Volume Flow Curves= 0
DXF OffsetX= 0
DXF OffsetY= 0
DXF ScaleX= 1
DXF ScaleY= 10

--- UNT147 IN GIBB.p01 (plan) ---

Plan Title=Multiple Run
Short Identifier=Multiple
Geom File=g01
Flow File=f01
Subcritical Flow
K Sum by GR= 0
Std Step Tol= 0.01
Critical Tol= 0.01
Num of Std Step Trials= 20
Max Error Tol= 0.3
Flow Tol Ratio= 0.001
Split Flow NTrial= 30
Split Flow Tol= 0.02
Split Flow Ratio= 0.02
Log Output Level= 0
Friction Slope Method= 1
Unsteady Friction Slope Method= 2
Unsteady Bridges Friction Slope Method= 1
Parabolic Critical Depth
Global Vel Dist=  1 , 1 , 1
Global Log Level= 0
CheckData=True
Encroach Param= -1, 0, 0, 0
BEGIN DESCRIPTION:
Multiple Run
END DESCRIPTION:

--- UNT147 IN GIBB.f01 (steady flow) ---

Flow Title=Multiple
Program Version=4.10
Number of Profiles= 7
Profile Names=10-year,25-year,50-year,1pct_min,100-year,1pct_plu,500-year
River Rch & RM=UNT147 IN GIBB,Reach-1         ,2089
     306     393     459     394     533     721     720
Boundary for River Rch & Prof#=UNT147 IN GIBB,Reach-1         , 1
Up Type= 0
Dn Type= 3
Dn Slope=0.007
Boundary for River Rch & Prof#=UNT147 IN GIBB,Reach-1         , 2
Up Type= 0
Dn Type= 3
Dn Slope=0.007
Boundary for River Rch & Prof#=UNT147 IN GIBB,Reach-1         , 3
Up Type= 0
Dn Type= 3
Dn Slope=0.007
Boundary for River Rch & Prof#=UNT147 IN GIBB,Reach-1         , 4
Up Type= 0
Dn Type= 3
Dn Slope=0.007
Boundary for River Rch & Prof#=UNT147 IN GIBB,Reach-1         , 5
Up Type= 0
Dn Type= 3
Dn Slope=0.007
Boundary for River Rch & Prof#=UNT147 IN GIBB,Reach-1         , 6
Up Type= 0
Dn Type= 3
Dn Slope=0.007
Boundary for River Rch & Prof#=UNT147 IN GIBB,Reach-1         , 7
Up Type= 0
Dn Type= 3
Dn Slope=0.007
DSS Import GetInterval= 0
DSS Import GetPeak= 0
DSS Import FillOption= 0

--- UNT147 IN GIBB.g01 (geometry) ---

Geom Title=Existing Conditions
Program Version=4.10

River Reach=UNT147 IN GIBB  ,Reach-1
Reach XY= 30
      3611781.33     10218154.82      3611809.95     10218085.89
      3611885.77     10218008.69      3611878.85     10217921.98
      3611919.89     10217855.74       3611941.6     10217844.27
      3612008.11     10217853.58      3612105.48      10217744.6
      3612069.33     10217685.32      3612089.27     10217641.45
      3612074.44     10217591.38      3612088.08     10217564.97
      3612131.44     10217544.35      3612184.65     10217563.85
      3612211.01     10217528.54      3612282.42     10217485.93
      3612319.71     10217548.29      3612350.19     10217558.44
      3612409.01     10217485.92      3612469.44     10217450.82
      3612484.92      10217348.3      3612506.38     10217316.27
      3612485.93     10217253.89      3612555.35     10217198.62
      3612582.55     10217071.78      3612676.99     10217001.12
      3612629.59     10216898.35      3612716.21     10216804.33
      3612759.55     10216685.29      3612795.68     10216664.72

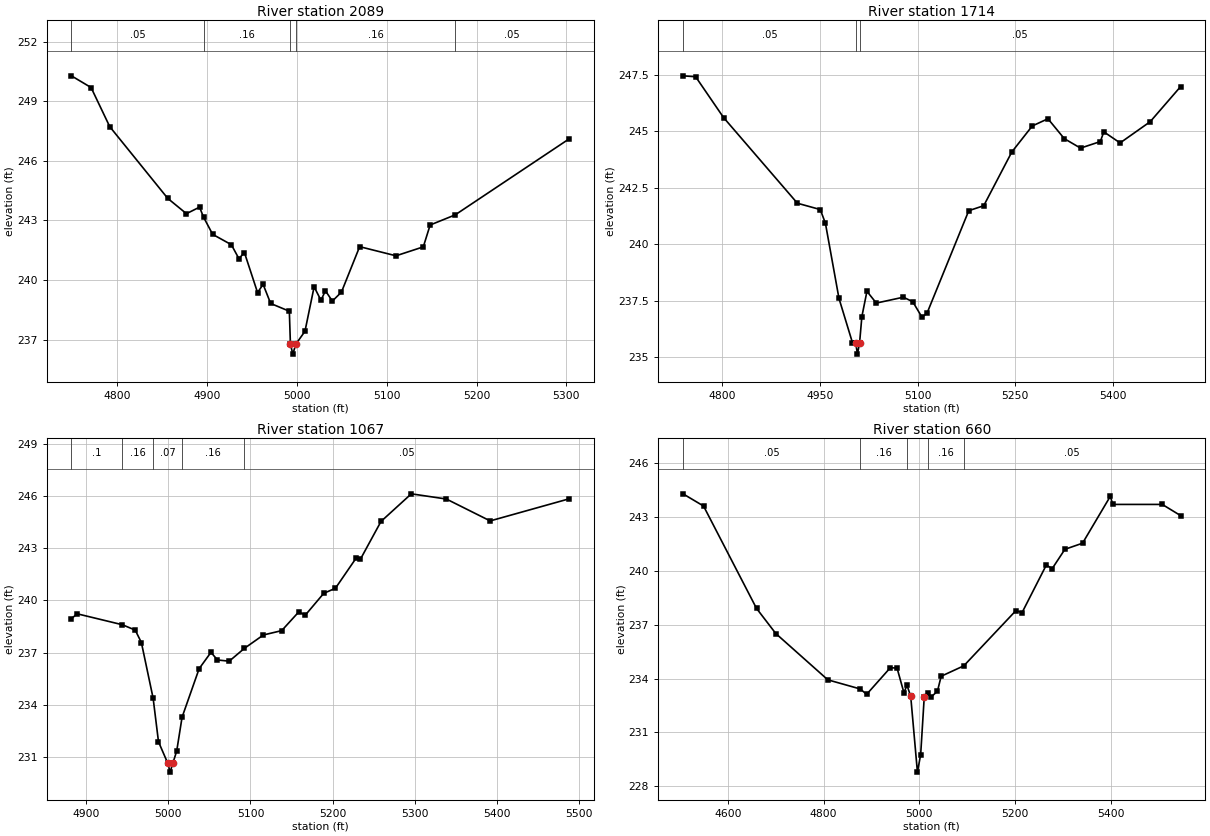
Type RM Length L Ch R = 1 ,2089    ,357,357,357
BEGIN DESCRIPTION:
UNT147 IN GIBB 3.0
END DESCRIPTION:
XS GIS Cut Line= 3
      3612092.11     10218141.64      3611892.11     10217991.64
      3611592.14     10218041.64
#Sta/Elev= 30
  4748.8  250.28  4770.7  249.69  4791.5  247.72  4856.1  244.11  4876.9  243.34
  4891.5  243.67  4895.9  243.17  4906.1   242.3  4926.9  241.78  4935.3  241.08
  4941.5  241.38  4956.1  239.37  4962.3  239.78  4970.7  238.82  4991.5  238.43
  4992.7  236.77  4995.4  236.27  4998.7  236.77  5008.9  237.42  5019.1  239.66
  5026.7  238.98  5031.7  239.46  5039.4  238.94  5049.5  239.39  5069.8  241.68
  5110.3  241.22  5140.7  241.67  5148.3  242.77  5176.2  243.28  5302.9   247.1
#Mann= 5 ,-1 , 0
  4748.8     .05       0  4895.9     .16       0  4992.7     .07       0
  4998.7     .16       0  5176.2     .05       0
Bank Sta=4992.7,4998.7
XS Rating Curve= 0 ,0
Exp/Cntr=0.3,0.1

Type RM Length L Ch R = 1 ,1714    ,665,665,665
BEGIN DESCRIPTION:
UNT147 IN GIBB 2.0
END DESCRIPTION:
XS GIS Cut Line= 3
        3612207.       10217868.      3611963.21     10217624.11
       3611668.4     10217515.02
#Sta/Elev= 30
  4739.4  247.45  4758.8  247.41  4801.8   245.6  4915.2  241.81  4950.4  241.53
  4958.3  240.92  4979.1   237.6  4999.9  235.63  5004.8  235.63  5007.5  235.13
  5010.8  235.63  5014.3  236.79  5022.1  237.91  5036.5  237.39  5078.1  237.65
  5092.5  237.45  5106.8  236.76  5114.7  236.96  5178.6  241.48  5201.6   241.7
  5244.8  244.08  5276.2  245.23  5300.3  245.55  5325.4  244.67  5350.4  244.25
  5380.8  244.54  5386.2  244.97  5411.2  244.48  5457.5  245.42  5504.1  246.97
#Mann= 3 ,-1 , 0
  4739.4     .05       0  5004.8     .03       0  5010.8     .05       0
Bank Sta=5004.8,5010.8
XS Rating Curve= 0 ,0
Exp/Cntr=0.3,0.1

Type RM Length L Ch R = 1 ,1067    ,407,407,407
BEGIN DESCRIPTION:
UNT147 IN GIBB 2.1
END DESCRIPTION:
XS GIS Cut Line= 3
        3612459.       10217577.      3612286.96     10217366.45
      3611992.17     10217257.37
#Sta/Elev= 30
    4882  238.95    4889  239.23    4944   238.6  4959.7  238.29  4967.2  237.57
  4981.5  234.36    4988  231.86  4999.4  230.61  5002.1  230.11  5005.4  230.61
  5010.2  231.33  5016.7  233.27  5037.5  236.07  5051.9  237.01  5059.8  236.57
  5074.1   236.5  5092.6  237.24  5115.7  238.01    5138  238.26  5158.8  239.34
  5166.7  239.15  5189.2  240.41  5203.4   240.7  5228.5  242.43  5233.8  242.37
  5258.9  244.55  5295.8  246.14  5338.5  245.84  5391.8  244.58  5487.7  245.85
#Mann= 5 ,-1 , 0
    4882      .1       0    4944     .16       0  4981.5     .07       0
  5016.7     .16       0  5092.6     .05       0
Bank Sta=4999.4,5005.4
XS Rating Curve= 0 ,0
Exp/Cntr=0.3,0.1

Type RM Length L Ch R = 1 ,660     ,0,0,0
BEGIN DESCRIPTION:
UNT147 IN GIBB 1.0
END DESCRIPTION:
XS GIS Cut Line= 4
      3612737.33     10217614.29      3612702.61     10217310.51
       3612504.7     10217140.46      3612055.86     10216990.85
#Sta/Elev= 30
    4506  244.29  4548.9  243.61  4659.6  237.91  4699.9  236.51  4808.7  233.93
  4876.6  233.42  4889.7  233.12  4939.1   234.6  4953.3  234.59  4967.6  233.22
  4974.2  233.62  4981.9  233.01  4995.9  228.79  5002.7  229.77  5010.2     233
    5017  233.22  5023.6  232.95  5037.8   233.3  5045.5  234.13  5092.8  234.71
  5201.9  237.79  5214.5  237.67  5265.2  240.32  5277.7  240.13  5304.1   241.2
    5341  241.54    5399  244.15  5404.2   243.7  5507.6   243.7  5545.8  243.08
#Mann= 5 ,-1 , 0
    4506     .05       0  4876.6     .16       0  4974.2     .07       0
    5017     .16       0  5092.8     .05       0
Bank Sta=4981.9,5010.2
XS Rating Curve= 0 ,0
Exp/Cntr=0.3,0.1

Chan Stop Cuts=-1
Use User Specified Reach Order=0
Composite Channel Slope=5