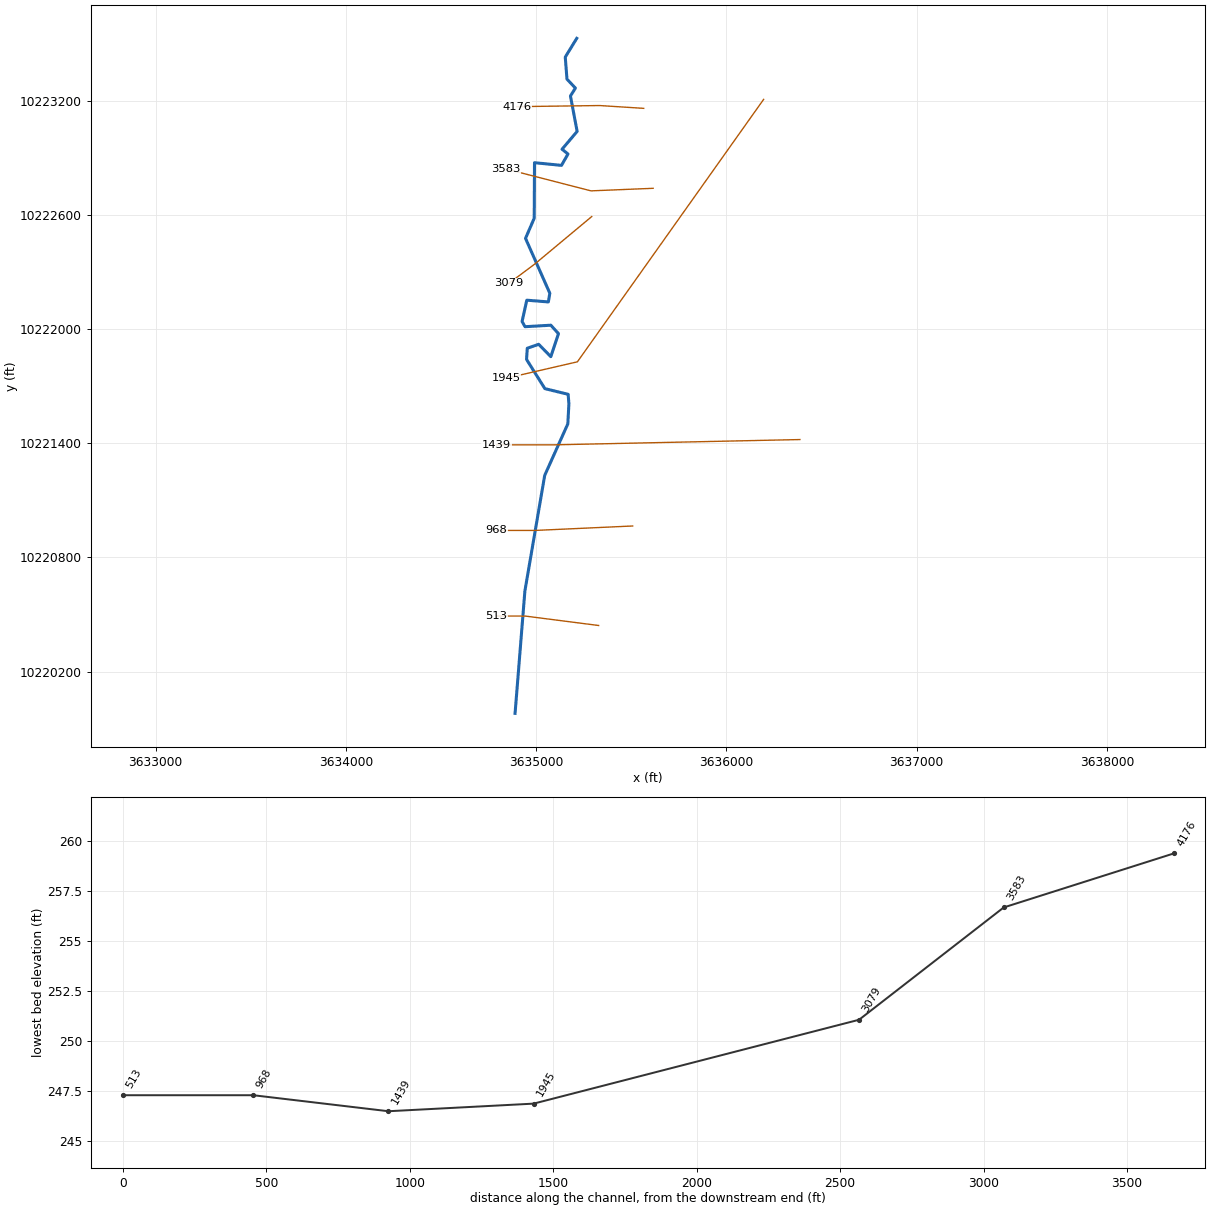
--- UNT148 IN GIBB.prj (project) ---

Proj Title=UNT148 IN GIBB Base Level Engineering
Current Plan=p01
Default Exp/Contr=0.3,0.1
English Units
Geom File=g01
Flow File=f01
Plan File=p01
BEGIN DESCRIPTION:
UNT148 IN GIBB
END DESCRIPTION:

--- UNT148 IN GIBB.p01 (plan) ---

Plan Title=Multiple Run
Short Identifier=Multiple
Geom File=g01
Flow File=f01
Subcritical Flow
K Sum by GR= 0
Std Step Tol= 0.01
Critical Tol= 0.01
Num of Std Step Trials= 20
Max Error Tol= 0.3
Flow Tol Ratio= 0.001
Split Flow NTrial= 30
Split Flow Tol= 0.02
Split Flow Ratio= 0.02
Log Output Level= 0
Friction Slope Method= 1
Unsteady Friction Slope Method= 2
Unsteady Bridges Friction Slope Method= 1
Parabolic Critical Depth
Global Vel Dist=  1 , 1 , 1
Global Log Level= 0
CheckData=True
Encroach Param= -1, 0, 0, 0
BEGIN DESCRIPTION:
Multiple Run
END DESCRIPTION:

--- UNT148 IN GIBB.f01 (steady flow) ---

Flow Title=Multiple
Number of Profiles=7
Profile Names=10-year,25-year,50-year,1pct_min,100-year,1pct_plu,500-year
River Rch & RM= UNT148 IN GIBB,Reach-1,4176
     254     322     375     321     434     587     581
Boundary for River Rch & Prof#=UNT148 IN GIBB,Reach-1,1
Up Type=0
Dn Type=3
Dn Slope=0.005
Boundary for River Rch & Prof#=UNT148 IN GIBB,Reach-1,2
Up Type=0
Dn Type=3
Dn Slope=0.005
Boundary for River Rch & Prof#=UNT148 IN GIBB,Reach-1,3
Up Type=0
Dn Type=3
Dn Slope=0.005
Boundary for River Rch & Prof#=UNT148 IN GIBB,Reach-1,4
Up Type=0
Dn Type=3
Dn Slope=0.005
Boundary for River Rch & Prof#=UNT148 IN GIBB,Reach-1,5
Up Type=0
Dn Type=3
Dn Slope=0.005
Boundary for River Rch & Prof#=UNT148 IN GIBB,Reach-1,6
Up Type=0
Dn Type=3
Dn Slope=0.005
Boundary for River Rch & Prof#=UNT148 IN GIBB,Reach-1,7
Up Type=0
Dn Type=3
Dn Slope=0.005

--- UNT148 IN GIBB.g01 (geometry) ---

Geom Title=Existing Conditions

River Reach=UNT148 IN GIBB,Reach-1
Reach XY= 30
      3635213.33     10223528.50      3635152.87     10223429.79
      3635161.99     10223313.91      3635206.26     10223267.03
      3635180.22     10223225.37      3635215.37     10223039.17
      3635135.95     10222945.42      3635167.20     10222920.68
      3635133.34     10222860.78      3634991.27     10222874.78
      3634989.78     10222582.97      3634944.07     10222476.91
      3635071.78     10222188.47      3635063.97     10222142.89
      3634950.69     10222152.01      3634925.95     10222040.03
      3634941.57     10222012.69      3635076.99     10222020.50
      3635117.35     10221976.23      3635076.99     10221855.13
      3635013.19     10221920.24      3634953.29     10221899.40
      3634949.38     10221840.81      3635045.74     10221687.17
      3635168.13     10221657.22      3635172.04     10221607.74
      3635166.40     10221501.84      3635044.87     10221231.00
      3634940.70     10220623.36      3634889.10     10219980.09

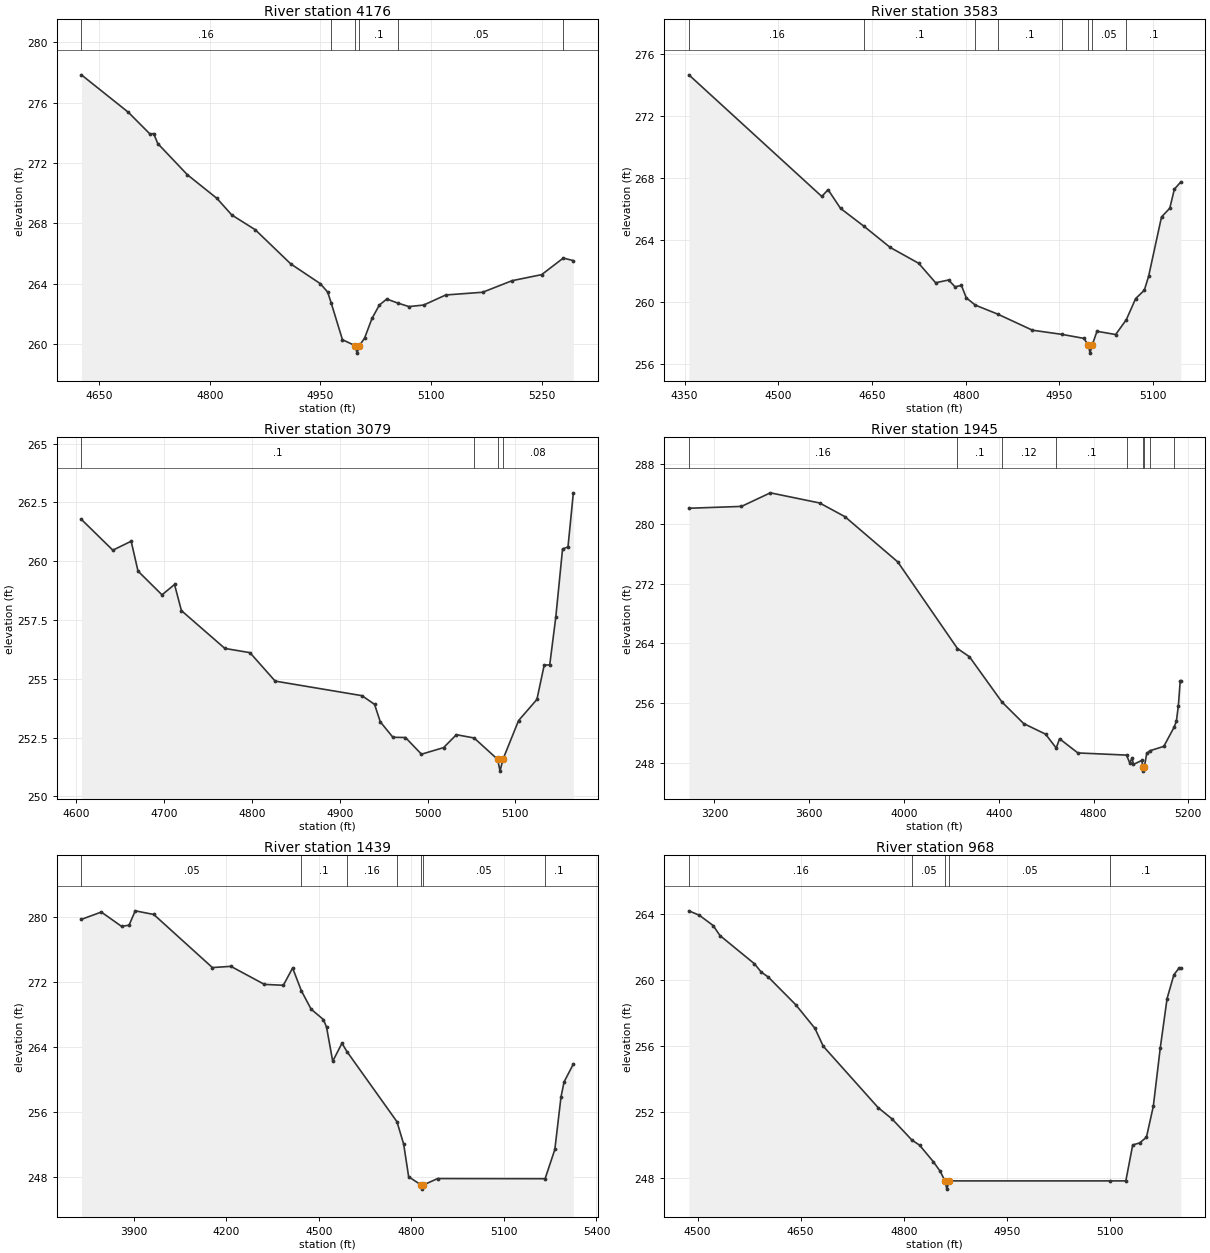
Type RM Length L Ch R = 1,4176,593,593,593
BEGIN DESCRIPTION:
UNT148 IN GIBB 8.0
END DESCRIPTION:
XS GIS Cut Line= 3
      3635565.44     10223160.45      3635333.50     10223175.23
      3634899.25     10223169.39
#Sta/Elev= 30
  4626.0  277.85  4689.5  275.37  4719.0  273.92  4724.0  273.95  4729.5  273.29
  4769.6  271.22  4809.7  269.65  4829.8  268.55  4861.6  267.57  4909.8  265.30
  4949.8  263.99  4959.8  263.43  4964.4  262.73  4979.8  260.27  4996.8  259.88
  4999.6  259.38  5002.8  259.88  5009.8  260.38  5019.8  261.68  5029.8  262.57
  5039.8  262.97  5054.4  262.71  5069.8  262.47  5089.8  262.57  5119.8  263.24
  5169.8  263.42  5209.8  264.19  5249.8  264.59  5279.1  265.69  5292.7  265.52
#Mann=6,-1,0
  4626.0    0.16       0  4964.4     0.1       0  4996.8    0.07       0
  5002.8     0.1       0  5054.4    0.05       0  5279.1    0.08       0
Bank Sta=4996.8,5002.8
Exp/Cntr=0.3,0.1

Type RM Length L Ch R = 1,3583,504,504,504
BEGIN DESCRIPTION:
UNT148 IN GIBB 7.0
END DESCRIPTION:
XS GIS Cut Line= 3
      3635614.71     10222740.17      3635288.27     10222726.75
      3634842.14     10222841.63
#Sta/Elev= 30
  4356.9  274.64  4569.7  266.79  4579.7  267.23  4599.7  266.02  4637.1  264.87
  4679.2  263.50  4724.7  262.48  4751.9  261.22  4772.6  261.40  4782.9  260.96
  4793.2  261.05  4800.9  260.25  4815.3  259.78  4851.1  259.20  4906.8  258.16
  4954.1  257.89  4989.4  257.63  4996.3  257.18  4999.0  256.68  5002.3  257.18
  5010.1  258.09  5040.0  257.88  5057.1  258.84  5072.0  260.20  5085.9  260.74
  5092.7  261.63  5113.4  265.47  5126.6  266.03  5134.0  267.26  5144.3  267.73
#Mann=8,-1,0
  4356.9    0.16       0  4637.1     0.1       0  4815.3    0.16       0
  4851.1     0.1       0  4954.1    0.05       0  4996.3   0.035       0
  5002.3    0.05       0  5057.1     0.1       0
Bank Sta=4996.3,5002.3
Exp/Cntr=0.3,0.1

Type RM Length L Ch R = 1,3079,1134,1134,1134
BEGIN DESCRIPTION:
UNT148 IN GIBB 6.0
END DESCRIPTION:
XS GIS Cut Line= 3
      3635292.14     10222591.67      3634992.11     10222341.64
      3634856.04     10222240.16
#Sta/Elev= 30
  4605.7  261.78  4641.5  260.47  4662.4  260.85  4670.2  259.58  4697.5  258.57
  4711.8  259.01  4719.6  257.90  4769.1  256.29  4797.7  256.11  4826.4  254.90
  4925.3  254.28  4939.6  253.91  4946.1  253.17  4960.5  252.51  4974.8  252.50
  4993.0  251.79  5018.2  252.07  5032.8  252.62  5053.0  252.48  5079.8  251.57
  5082.5  251.07  5085.8  251.57  5103.6  253.22  5124.5  254.12  5132.8  255.58
  5139.1  255.59  5146.0  257.62  5153.7  260.52  5159.9  260.61  5166.0  262.91
#Mann=4,-1,0
  4605.7     0.1       0  5053.0    0.08       0  5079.8    0.07       0
  5085.8    0.08       0
Bank Sta=5079.8,5085.8
Exp/Cntr=0.3,0.1

Type RM Length L Ch R = 1,1945,506,506,506
BEGIN DESCRIPTION:
UNT148 IN GIBB 4.0
END DESCRIPTION:
XS GIS Cut Line= 3
      3636195.69     10223207.66      3635216.73     10221828.07
      3634842.11     10221741.64
#Sta/Elev= 30
  3092.1  282.13  3314.2  282.38  3436.0  284.20  3643.9  282.84  3750.9  281.00
  3973.6  274.94  4225.6  263.32  4276.2  262.22  4413.1  256.16  4505.0  253.26
  4597.3  251.84  4642.4  249.98  4656.4  251.22  4733.8  249.32  4939.0  249.03
  4952.7  247.98  4962.9  248.68  4968.0  247.78  5004.0  248.32  5007.8  247.38
  5010.6  246.88  5013.8  247.38  5024.5  249.29  5039.4  249.63  5096.4  250.20
  5139.8  252.77  5149.4  253.56  5157.9  255.67  5165.6  258.93  5168.2  258.93
#Mann=9,-1,0
  3092.1    0.16       0  4225.6     0.1       0  4413.1    0.12       0
  4642.4     0.1       0  4939.0    0.12       0  5007.8    0.07       0
  5013.8    0.12       0  5039.4    0.05       0  5139.8     0.1       0
Bank Sta=5007.8,5013.8
Exp/Cntr=0.3,0.1

Type RM Length L Ch R = 1,1439,471,471,471
BEGIN DESCRIPTION:
UNT148 IN GIBB 3.0
END DESCRIPTION:
XS GIS Cut Line= 3
      3636386.70     10221419.47      3635092.11     10221391.64
      3634792.10     10221391.64
#Sta/Elev= 30
  3730.2  279.69  3794.8  280.59  3860.8  278.82  3884.8  278.98  3904.8  280.74
  3964.9  280.29  4154.9  273.76  4214.9  273.91  4323.5  271.69  4384.9  271.58
  4415.0  273.71  4443.4  270.90  4475.0  268.64  4515.0  267.36  4525.0  266.42
  4545.0  262.23  4575.0  264.45  4591.0  263.43  4753.2  254.80  4775.0  252.04
  4791.2  248.02  4832.1  247.00  4834.8  246.50  4838.1  247.00  4885.1  247.80
  5233.5  247.78  5265.1  251.38  5285.1  257.85  5295.1  259.70  5325.1  261.89
#Mann=7,-1,0
  3730.2    0.05       0  4443.4     0.1       0  4591.0    0.16       0
  4753.2    0.05       0  4832.1   0.033       0  4838.1    0.05       0
  5233.5     0.1       0
Bank Sta=4832.1,4838.1
Exp/Cntr=0.3,0.1

Type RM Length L Ch R = 1,968,455,455,455
BEGIN DESCRIPTION:
UNT148 IN GIBB 2.0
END DESCRIPTION:
XS GIS Cut Line= 3
      3635507.36     10220965.15      3634992.11     10220941.64
      3634792.09     10220941.64
#Sta/Elev= 30
  4487.4  264.18  4502.7  263.91  4522.7  263.29  4532.7  262.68  4582.8  260.97
  4592.8  260.46  4602.8  260.17  4642.8  258.49  4670.9  257.05  4682.9  255.97
  4762.9  252.24  4783.0  251.56  4812.1  250.27  4823.0  249.97  4843.0  248.97
  4853.0  248.39  4860.0  247.80  4862.8  247.30  4866.0  247.80  5099.9  247.80
  5123.2  247.80  5133.2  249.98  5143.2  250.10  5153.2  250.45  5163.2  252.33
  5173.2  255.83  5183.2  258.86  5193.2  260.31  5200.7  260.71  5203.2  260.71
#Mann=5,-1,0
  4487.4    0.16       0  4812.1    0.05       0  4860.0   0.033       0
  4866.0    0.05       0  5099.9     0.1       0
Bank Sta=4860,4866
Exp/Cntr=0.3,0.1

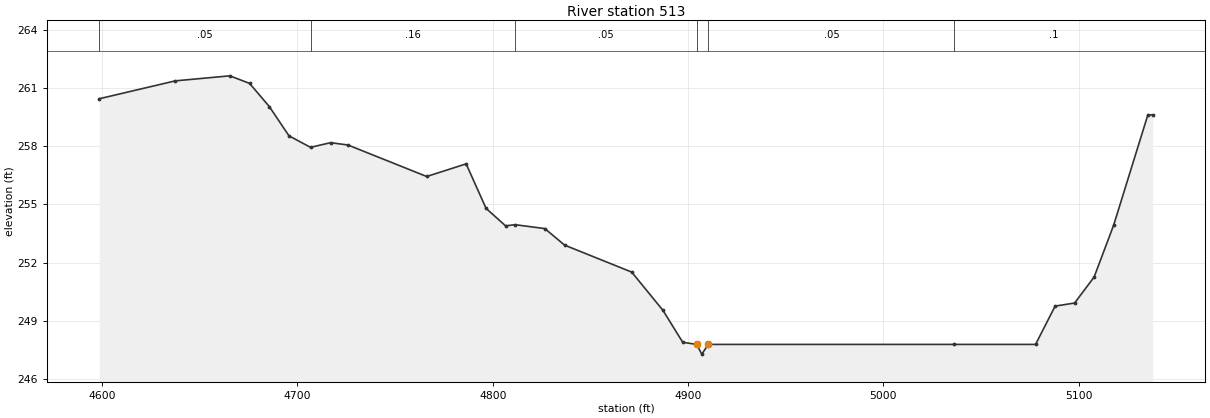
Type RM Length L Ch R = 1,513,0,0,0
BEGIN DESCRIPTION:
UNT148 IN GIBB 1.0
END DESCRIPTION:
XS GIS Cut Line= 3
      3635328.47     10220442.04      3634942.11     10220491.64
      3634792.14     10220491.64
#Sta/Elev= 30
  4598.5  260.44  4637.4  261.36  4665.4  261.62  4675.5  261.23  4685.6  260.04
  4695.7  258.53  4706.7  257.94  4717.0  258.18  4725.9  258.06  4766.2  256.44
  4786.4  257.09  4796.6  254.80  4806.6  253.90  4811.5  253.96  4826.7  253.76
  4836.8  252.91  4871.2  251.52  4887.2  249.55  4897.3  247.91  4904.4  247.80
  4907.1  247.30  4910.4  247.80  5036.4  247.80  5078.0  247.80  5088.0  249.77
  5098.0  249.93  5108.0  251.27  5118.0  253.94  5135.5  259.61  5138.0  259.61
#Mann=6,-1,0
  4598.5    0.05       0  4706.7    0.16       0  4811.5    0.05       0
  4904.4   0.033       0  4910.4    0.05       0  5036.4     0.1       0
Bank Sta=4904.4,4910.4
Exp/Cntr=0.3,0.1

Chan Stop Cuts=-1