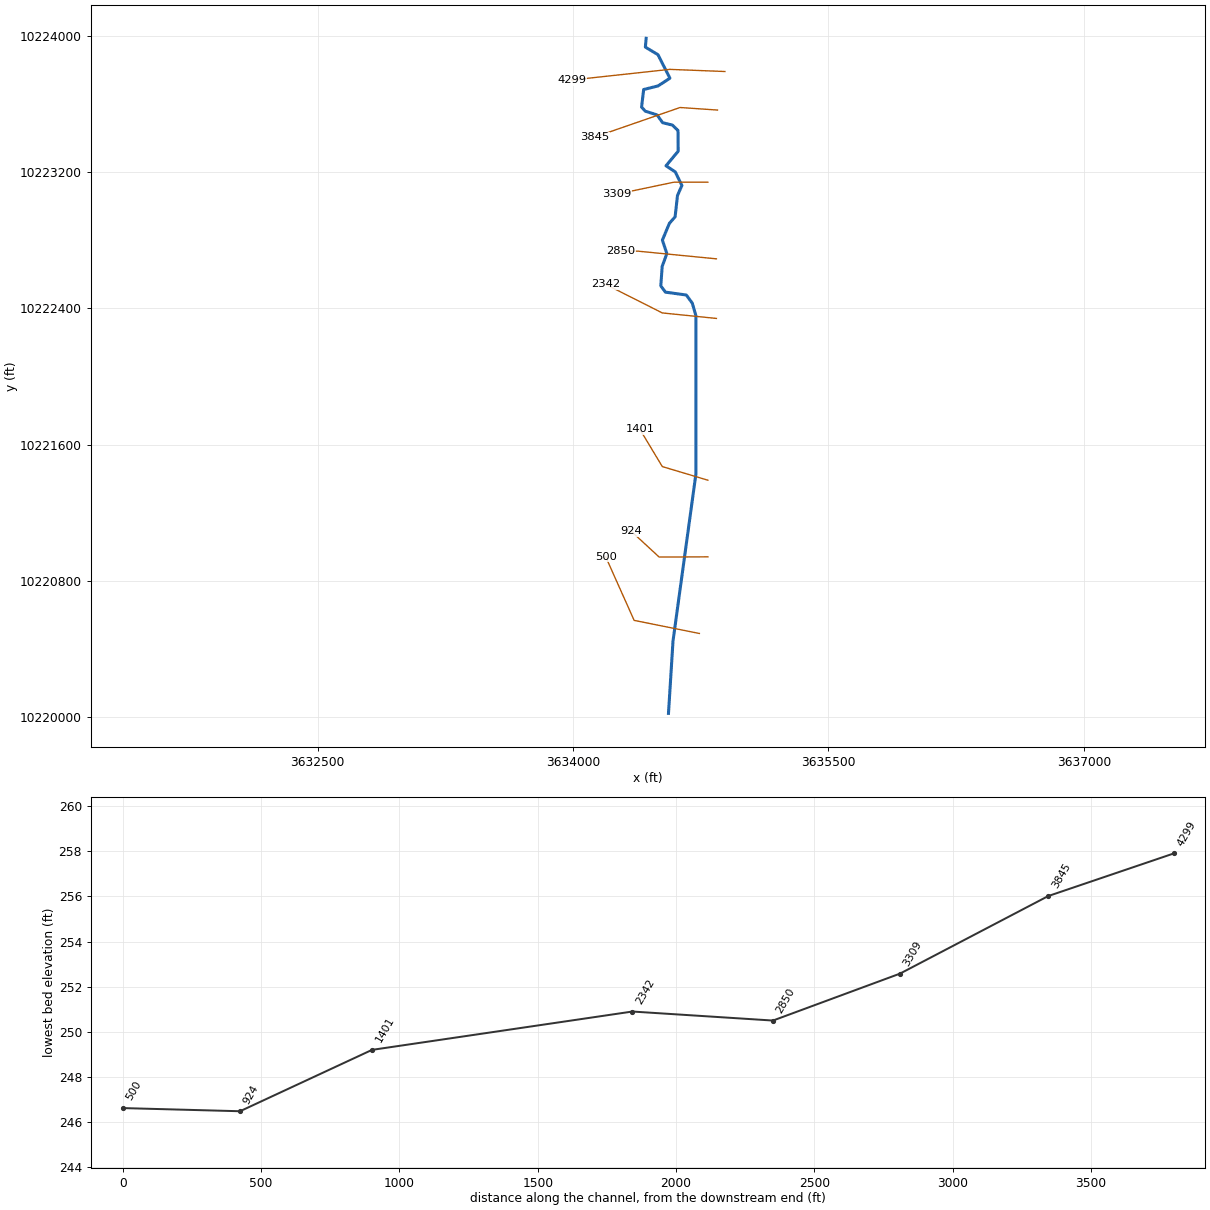
--- UNT149 IN GIBB.prj (project) ---

Proj Title=UNT149 IN GIBB Base Level Engineering
Current Plan=p01
Default Exp/Contr=0.3,0.1
English Units
Geom File=g01
Flow File=f01
Plan File=p01
BEGIN DESCRIPTION:
UNT149 IN GIBB
END DESCRIPTION:

--- UNT149 IN GIBB.p01 (plan) ---

Plan Title=Multiple Run
Short Identifier=Multiple
Geom File=g01
Flow File=f01
Subcritical Flow
K Sum by GR= 0
Std Step Tol= 0.01
Critical Tol= 0.01
Num of Std Step Trials= 20
Max Error Tol= 0.3
Flow Tol Ratio= 0.001
Split Flow NTrial= 30
Split Flow Tol= 0.02
Split Flow Ratio= 0.02
Log Output Level= 0
Friction Slope Method= 1
Unsteady Friction Slope Method= 2
Unsteady Bridges Friction Slope Method= 1
Parabolic Critical Depth
Global Vel Dist=  1 , 1 , 1
Global Log Level= 0
CheckData=True
Encroach Param= -1, 0, 0, 0
BEGIN DESCRIPTION:
Multiple Run
END DESCRIPTION:

--- UNT149 IN GIBB.f01 (steady flow) ---

Flow Title=Multiple
Number of Profiles=7
Profile Names=10-year,25-year,50-year,1pct_min,100-year,1pct_plu,500-year
River Rch & RM= UNT149 IN GIBB,Reach-1,4299
     343     441     516     444     600     812     812
Boundary for River Rch & Prof#=UNT149 IN GIBB,Reach-1,1
Up Type=0
Dn Type=3
Dn Slope=0.005
Boundary for River Rch & Prof#=UNT149 IN GIBB,Reach-1,2
Up Type=0
Dn Type=3
Dn Slope=0.005
Boundary for River Rch & Prof#=UNT149 IN GIBB,Reach-1,3
Up Type=0
Dn Type=3
Dn Slope=0.005
Boundary for River Rch & Prof#=UNT149 IN GIBB,Reach-1,4
Up Type=0
Dn Type=3
Dn Slope=0.005
Boundary for River Rch & Prof#=UNT149 IN GIBB,Reach-1,5
Up Type=0
Dn Type=3
Dn Slope=0.005
Boundary for River Rch & Prof#=UNT149 IN GIBB,Reach-1,6
Up Type=0
Dn Type=3
Dn Slope=0.005
Boundary for River Rch & Prof#=UNT149 IN GIBB,Reach-1,7
Up Type=0
Dn Type=3
Dn Slope=0.005

--- UNT149 IN GIBB.g01 (geometry) ---

Geom Title=Existing Conditions

River Reach=UNT149 IN GIBB,Reach-1
Reach XY= 30
      3634429.58     10223986.48      3634424.93     10223934.86
      3634498.72     10223890.62      3634569.19     10223752.29
      3634499.39     10223707.06      3634415.01     10223685.94
      3634402.59     10223582.91      3634424.54     10223558.77
      3634493.77     10223536.73      3634526.32     10223491.11
      3634584.38     10223476.79      3634616.48     10223445.24
      3634617.67     10223323.73      3634546.21     10223238.02
      3634600.54     10223202.18      3634639.26     10223122.46
      3634613.41     10223062.40      3634599.58     10222938.40
      3634566.09     10222900.07      3634524.79     10222801.47
      3634551.14     10222722.59      3634523.57     10222646.74
      3634515.63     10222532.72      3634542.76     10222496.02
      3634665.25     10222479.22      3634700.17     10222432.01
      3634721.75     10222357.61      3634721.71     10221428.23
      3634587.25     10220447.55      3634560.65     10220022.45

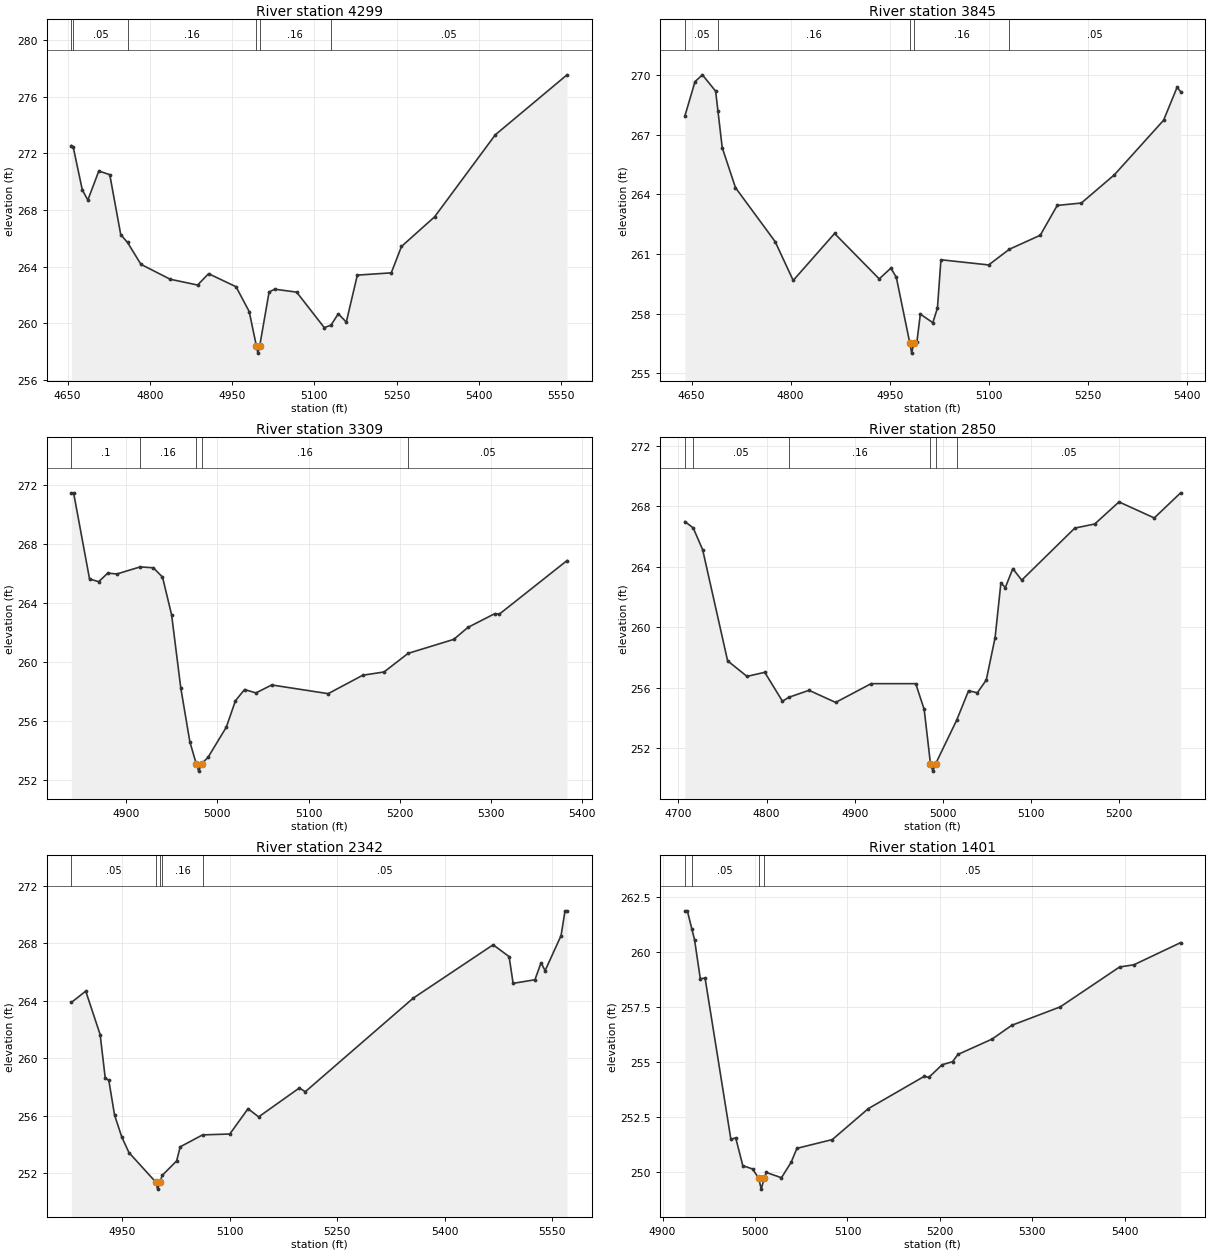
Type RM Length L Ch R = 1,4299,454,454,454
BEGIN DESCRIPTION:
UNT149 IN GIBB 8.0
END DESCRIPTION:
XS GIS Cut Line= 3
      3634892.13     10223791.64      3634568.12     10223804.25
      3633992.07     10223741.64
#Sta/Elev= 30
  4656.9  272.54  4660.5  272.41  4676.9  269.42  4687.0  268.70  4707.0  270.75
  4727.0  270.49  4747.0  266.26  4759.4  265.71  4783.8  264.17  4837.1  263.12
  4887.1  262.71  4907.1  263.51  4957.2  262.59  4981.2  260.84  4994.3  258.41
  4997.0  257.91  5000.3  258.41  5017.4  262.21  5027.4  262.42  5067.7  262.21
  5118.0  259.71  5130.2  259.88  5143.6  260.68  5158.2  260.10  5178.3  263.41
  5240.2  263.57  5258.8  265.43  5319.2  267.52  5429.8  273.30  5560.6  277.53
#Mann=6,-1,0
  4656.9    0.08       0  4660.5    0.05       0  4759.4    0.16       0
  4994.3    0.07       0  5000.3    0.16       0  5130.2    0.05       0
Bank Sta=4994.3,5000.3
Exp/Cntr=0.3,0.1

Type RM Length L Ch R = 1,3845,536,536,536
BEGIN DESCRIPTION:
UNT149 IN GIBB 7.0
END DESCRIPTION:
XS GIS Cut Line= 3
      3634848.51     10223565.33      3634628.77     10223580.31
      3634127.37     10223406.56
#Sta/Elev= 30
  4639.9  267.94  4655.2  269.66  4666.4  270.00  4686.4  269.18  4690.0  268.16
  4696.4  266.34  4716.5  264.33  4776.6  261.62  4803.9  259.67  4866.6  262.03
  4934.2  259.75  4951.9  260.29  4960.1  259.83  4980.6  256.52  4983.4  256.02
  4986.6  256.52  4991.2  256.56  4996.5  257.98  5015.4  257.55  5022.4  258.28
  5027.7  260.71  5100.0  260.45  5131.4  261.24  5178.1  261.94  5203.9  263.44
  5240.4  263.56  5290.5  264.98  5365.0  267.72  5385.5  269.38  5390.8  269.15
#Mann=5,-1,0
  4639.9    0.05       0  4690.0    0.16       0  4980.6    0.07       0
  4986.6    0.16       0  5131.4    0.05       0
Bank Sta=4980.6,4986.6
Exp/Cntr=0.3,0.1

Type RM Length L Ch R = 1,3309,459,459,459
BEGIN DESCRIPTION:
UNT149 IN GIBB 6.0
END DESCRIPTION:
XS GIS Cut Line= 3
      3634792.07     10223141.64      3634592.11     10223141.64
      3634255.67     10223071.16
#Sta/Elev= 30
  4839.8  271.44  4842.3  271.44  4859.8  265.60  4869.8  265.42  4879.8  266.00
  4889.8  265.94  4915.3  266.42  4929.8  266.36  4939.8  265.73  4949.8  263.17
  4959.8  258.24  4969.8  254.57  4976.8  253.08  4979.5  252.58  4982.8  253.08
  4989.8  253.52  5009.8  255.56  5019.8  257.35  5029.8  258.11  5042.3  257.88
  5059.6  258.42  5121.5  257.83  5159.5  259.08  5182.8  259.30  5209.2  260.56
  5259.3  261.51  5274.8  262.32  5304.2  263.25  5309.3  263.22  5383.5  266.85
#Mann=5,-1,0
  4839.8     0.1       0  4915.3    0.16       0  4976.8    0.07       0
  4982.8    0.16       0  5209.2    0.05       0
Bank Sta=4976.8,4982.8
Exp/Cntr=0.3,0.1

Type RM Length L Ch R = 1,2850,508,508,508
BEGIN DESCRIPTION:
UNT149 IN GIBB 5.0
END DESCRIPTION:
XS GIS Cut Line= 3
      3634842.16     10222691.64      3634382.27     10222736.60
      3634282.25     10222736.60
#Sta/Elev= 30
  4707.5  266.99  4716.9  266.57  4727.6  265.13  4755.9  257.79  4777.9  256.76
  4798.0  257.03  4818.1  255.12  4825.4  255.38  4848.2  255.84  4878.4  255.04
  4918.6  256.28  4969.2  256.28  4978.8  254.58  4985.9  251.00  4988.6  250.50
  4991.9  251.00  5015.6  253.86  5029.1  255.81  5039.1  255.68  5049.2  256.52
  5059.2  259.32  5065.8  262.94  5070.8  262.63  5079.3  263.88  5089.4  263.12
  5149.6  266.56  5172.2  266.83  5199.7  268.29  5239.7  267.23  5269.6  268.89
#Mann=6,-1,0
  4707.5     0.1       0  4716.9    0.05       0  4825.4    0.16       0
  4985.9    0.07       0  4991.9    0.16       0  5015.6    0.05       0
Bank Sta=4985.9,4991.9
Exp/Cntr=0.3,0.1

Type RM Length L Ch R = 1,2342,941,941,941
BEGIN DESCRIPTION:
UNT149 IN GIBB 4.0
END DESCRIPTION:
XS GIS Cut Line= 3
      3634842.10     10222341.64      3634524.27     10222374.02
      3634192.14     10222541.63
#Sta/Elev= 30
  4879.1  263.87  4899.2  264.66  4919.3  261.64  4926.4  258.62  4931.4  258.46
  4939.4  256.05  4949.5  254.52  4959.5  253.44  4996.7  251.40  4999.5  250.90
  5002.7  251.40  5006.0  251.86  5026.0  252.86  5031.0  253.84  5062.2  254.67
  5100.2  254.73  5125.6  256.49  5140.4  255.92  5197.2  257.93  5205.5  257.67
  5356.0  264.17  5467.5  267.88  5489.8  267.06  5495.4  265.20  5525.8  265.45
  5534.4  266.63  5540.0  266.08  5562.3  268.52  5567.8  270.24  5570.6  270.24
#Mann=5,-1,0
  4879.1    0.05       0  4996.7    0.03       0  5002.7    0.05       0
  5006.0    0.16       0  5062.2    0.05       0
Bank Sta=4996.7,5002.7
Exp/Cntr=0.3,0.1

Type RM Length L Ch R = 1,1401,477,477,477
BEGIN DESCRIPTION:
UNT149 IN GIBB 3.0
END DESCRIPTION:
XS GIS Cut Line= 3
      3634792.11     10221391.64      3634524.25     10221471.76
      3634392.11     10221691.63
#Sta/Elev= 30
  4924.2  261.89  4926.8  261.89  4931.7  261.06  4934.6  260.57  4940.8  258.80
  4946.0  258.82  4973.9  251.47  4979.1  251.54  4986.8  250.27  4997.3  250.12
  5004.0  249.70  5006.7  249.20  5010.0  249.70  5012.2  249.96  5028.6  249.72
  5039.0  250.42  5045.3  251.06  5083.6  251.46  5122.5  252.87  5182.9  254.34
  5188.1  254.30  5202.3  254.87  5213.6  255.01  5219.4  255.34  5256.3  256.04
  5277.7  256.67  5330.1  257.51  5394.3  259.33  5409.8  259.43  5460.3  260.44
#Mann=4,-1,0
  4924.2     0.1       0  4931.7    0.05       0  5004.0    0.03       0
  5010.0    0.05       0
Bank Sta=5004,5010
Exp/Cntr=0.3,0.1

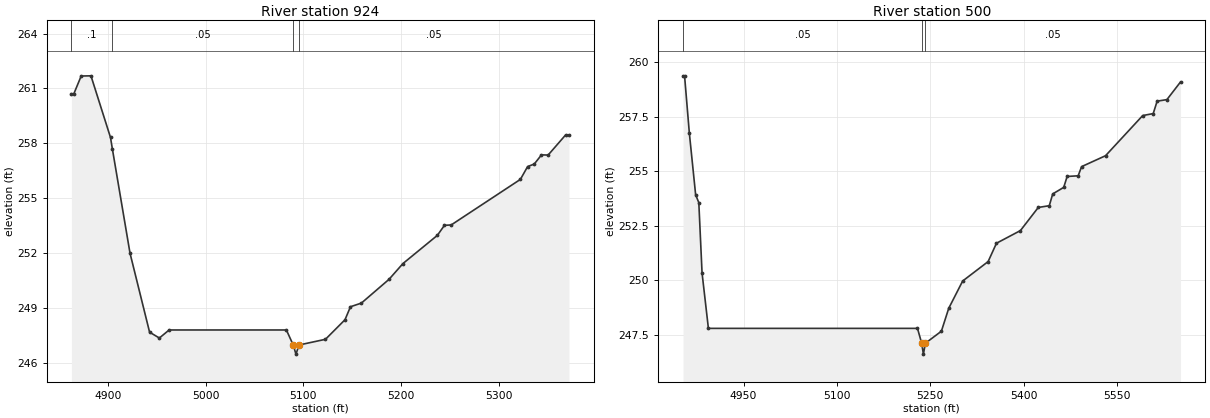
Type RM Length L Ch R = 1,924,424,424,424
BEGIN DESCRIPTION:
UNT149 IN GIBB 2.0
END DESCRIPTION:
XS GIS Cut Line= 3
      3634792.15     10220941.64      3634505.96     10220940.44
      3634342.07     10221091.67
#Sta/Elev= 30
  4862.7  260.71  4865.2  260.71  4872.7  261.68  4882.7  261.69  4902.7  258.32
  4904.6  257.70  4922.7  251.99  4942.7  247.68  4952.7  247.36  4962.7  247.80
  5082.7  247.80  5089.7  246.98  5092.5  246.48  5095.7  246.98  5122.7  247.29
  5142.7  248.36  5148.3  249.07  5159.5  249.27  5187.8  250.57  5202.0  251.43
  5237.2  252.97  5244.5  253.52  5251.4  253.54  5322.2  256.03  5329.6  256.73
  5336.4  256.87  5343.8  257.37  5350.6  257.36  5368.5  258.46  5371.9  258.46
#Mann=4,-1,0
  4862.7     0.1       0  4904.6    0.05       0  5089.7   0.033       0
  5095.7    0.05       0
Bank Sta=5089.7,5095.7
Exp/Cntr=0.3,0.1

Type RM Length L Ch R = 1,500,0,0,0
BEGIN DESCRIPTION:
UNT149 IN GIBB 1.0
END DESCRIPTION:
XS GIS Cut Line= 3
      3634742.07     10220491.65      3634359.05     10220568.47
      3634192.09     10220941.67
#Sta/Elev= 30
  4852.7  259.37  4855.2  259.37  4862.9  256.74  4873.0  253.92  4878.1  253.56
  4883.3  250.34  4893.5  247.80  5229.5  247.80  5236.2  247.12  5239.0  246.62
  5242.2  247.12  5267.9  247.67  5279.7  248.72  5302.1  249.97  5343.0  250.86
  5356.4  251.70  5394.9  252.28  5423.6  253.34  5441.3  253.42  5446.8  253.96
  5464.5  254.26  5470.0  254.76  5487.7  254.79  5493.2  255.21  5531.7  255.71
  5591.4  257.55  5608.3  257.64  5614.6  258.21  5630.3  258.28  5652.2  259.09
#Mann=3,-1,0
  4852.7    0.05       0  5236.2   0.033       0  5242.2    0.05       0
Bank Sta=5236.2,5242.2
Exp/Cntr=0.3,0.1

Chan Stop Cuts=-1