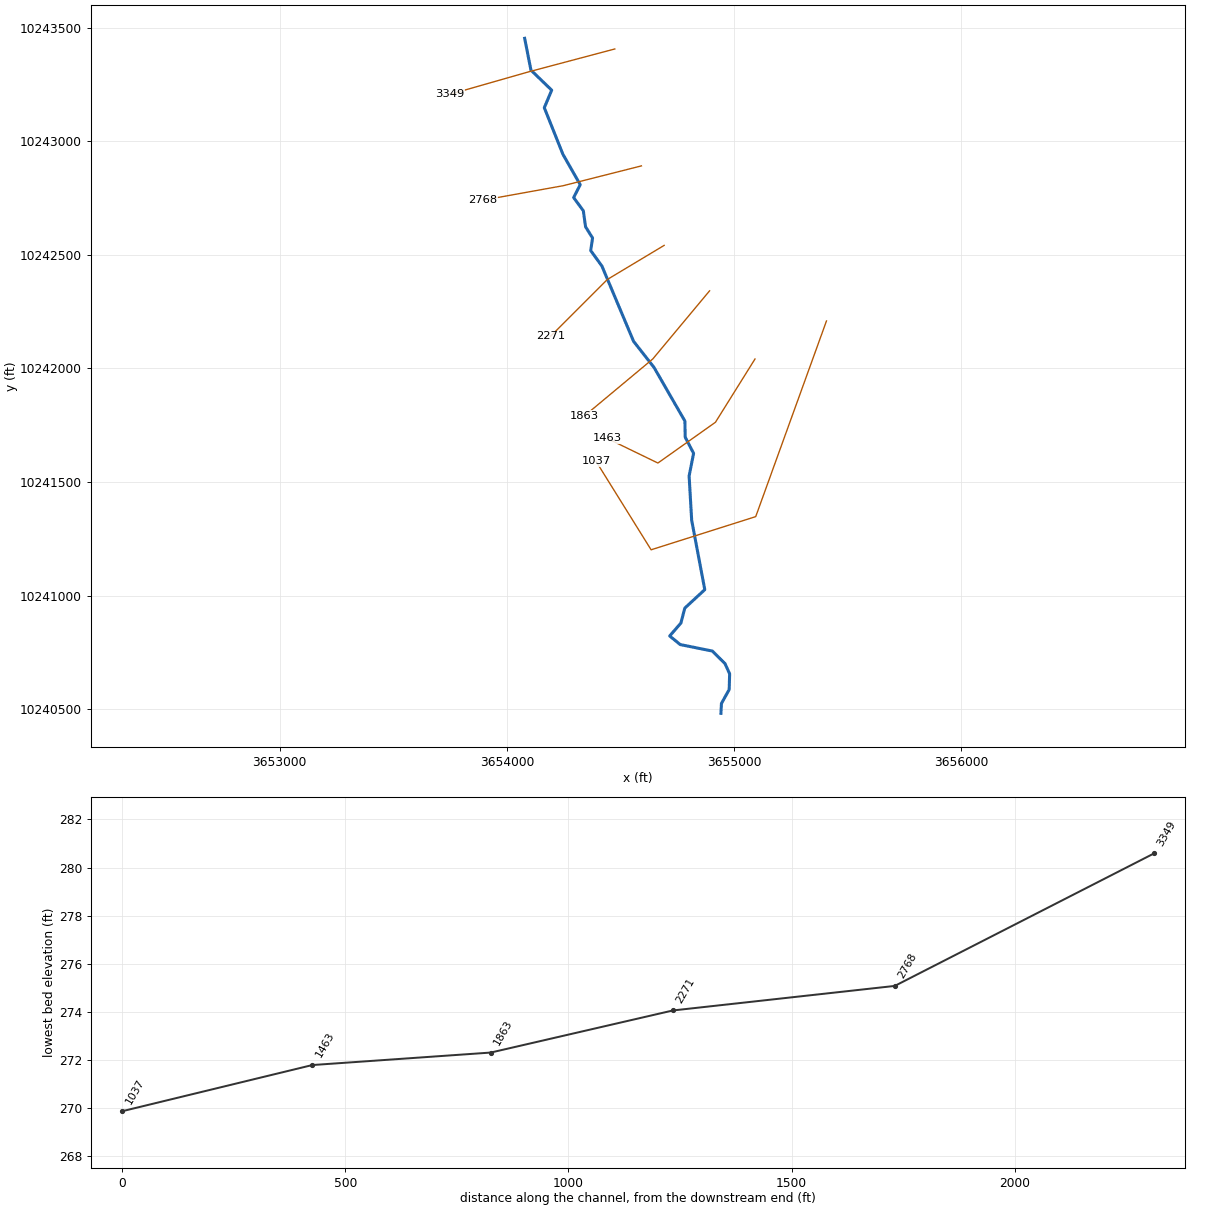
--- WILSON BRANCH.prj (project) ---

Proj Title=WILSON BRANCH Base Level Engineering
Current Plan=p01
Default Exp/Contr=0.3,0.1
English Units
Geom File=g01
Flow File=f01
Plan File=p01
BEGIN DESCRIPTION:
WILSON BRANCH
END DESCRIPTION:

--- WILSON BRANCH.p01 (plan) ---

Plan Title=Multiple Run
Short Identifier=Multiple
Geom File=g01
Flow File=f01
Subcritical Flow
K Sum by GR= 0
Std Step Tol= 0.01
Critical Tol= 0.01
Num of Std Step Trials= 20
Max Error Tol= 0.3
Flow Tol Ratio= 0.001
Split Flow NTrial= 30
Split Flow Tol= 0.02
Split Flow Ratio= 0.02
Log Output Level= 0
Friction Slope Method= 1
Unsteady Friction Slope Method= 2
Unsteady Bridges Friction Slope Method= 1
Parabolic Critical Depth
Global Vel Dist=  1 , 1 , 1
Global Log Level= 0
CheckData=True
Encroach Param= -1, 0, 0, 0
BEGIN DESCRIPTION:
Multiple Run
END DESCRIPTION:

--- WILSON BRANCH.f01 (steady flow) ---

Flow Title=Multiple
Number of Profiles=7
Profile Names=10-year,25-year,50-year,1pct_min,100-year,1pct_plu,500-year
River Rch & RM= WILSON BRANCH,Reach-1,3349
     444     579     686     596     806    1091    1114
Boundary for River Rch & Prof#=WILSON BRANCH,Reach-1,1
Up Type=0
Dn Type=3
Dn Slope=0.005
Boundary for River Rch & Prof#=WILSON BRANCH,Reach-1,2
Up Type=0
Dn Type=3
Dn Slope=0.005
Boundary for River Rch & Prof#=WILSON BRANCH,Reach-1,3
Up Type=0
Dn Type=3
Dn Slope=0.005
Boundary for River Rch & Prof#=WILSON BRANCH,Reach-1,4
Up Type=0
Dn Type=3
Dn Slope=0.005
Boundary for River Rch & Prof#=WILSON BRANCH,Reach-1,5
Up Type=0
Dn Type=3
Dn Slope=0.005
Boundary for River Rch & Prof#=WILSON BRANCH,Reach-1,6
Up Type=0
Dn Type=3
Dn Slope=0.005
Boundary for River Rch & Prof#=WILSON BRANCH,Reach-1,7
Up Type=0
Dn Type=3
Dn Slope=0.005

--- WILSON BRANCH.g01 (geometry) ---

Geom Title=Existing Conditions

River Reach=WILSON BRANCH,Reach-1
Reach XY= 30
      3654078.16     10243453.12      3654105.77     10243313.27
      3654197.12     10243224.93      3654164.63     10243147.69
      3654246.22     10242943.35      3654322.78     10242808.70
      3654293.69     10242752.21      3654336.40     10242694.05
      3654346.29     10242623.31      3654377.06     10242574.37
      3654368.90     10242518.99      3654418.44     10242450.16
      3654557.67     10242119.23      3654647.44     10242004.71
      3654783.50     10241768.26      3654784.89     10241697.33
      3654821.80     10241626.39      3654802.08     10241526.57
      3654813.34     10241331.83      3654871.02     10241026.32
      3654783.04     10240944.97      3654765.97     10240879.36
      3654716.63     10240822.33      3654762.83     10240784.56
      3654904.78     10240755.84      3654959.95     10240700.80
      3654980.44     10240655.83      3654978.49     10240586.55
      3654944.38     10240525.34      3654942.11     10240481.64

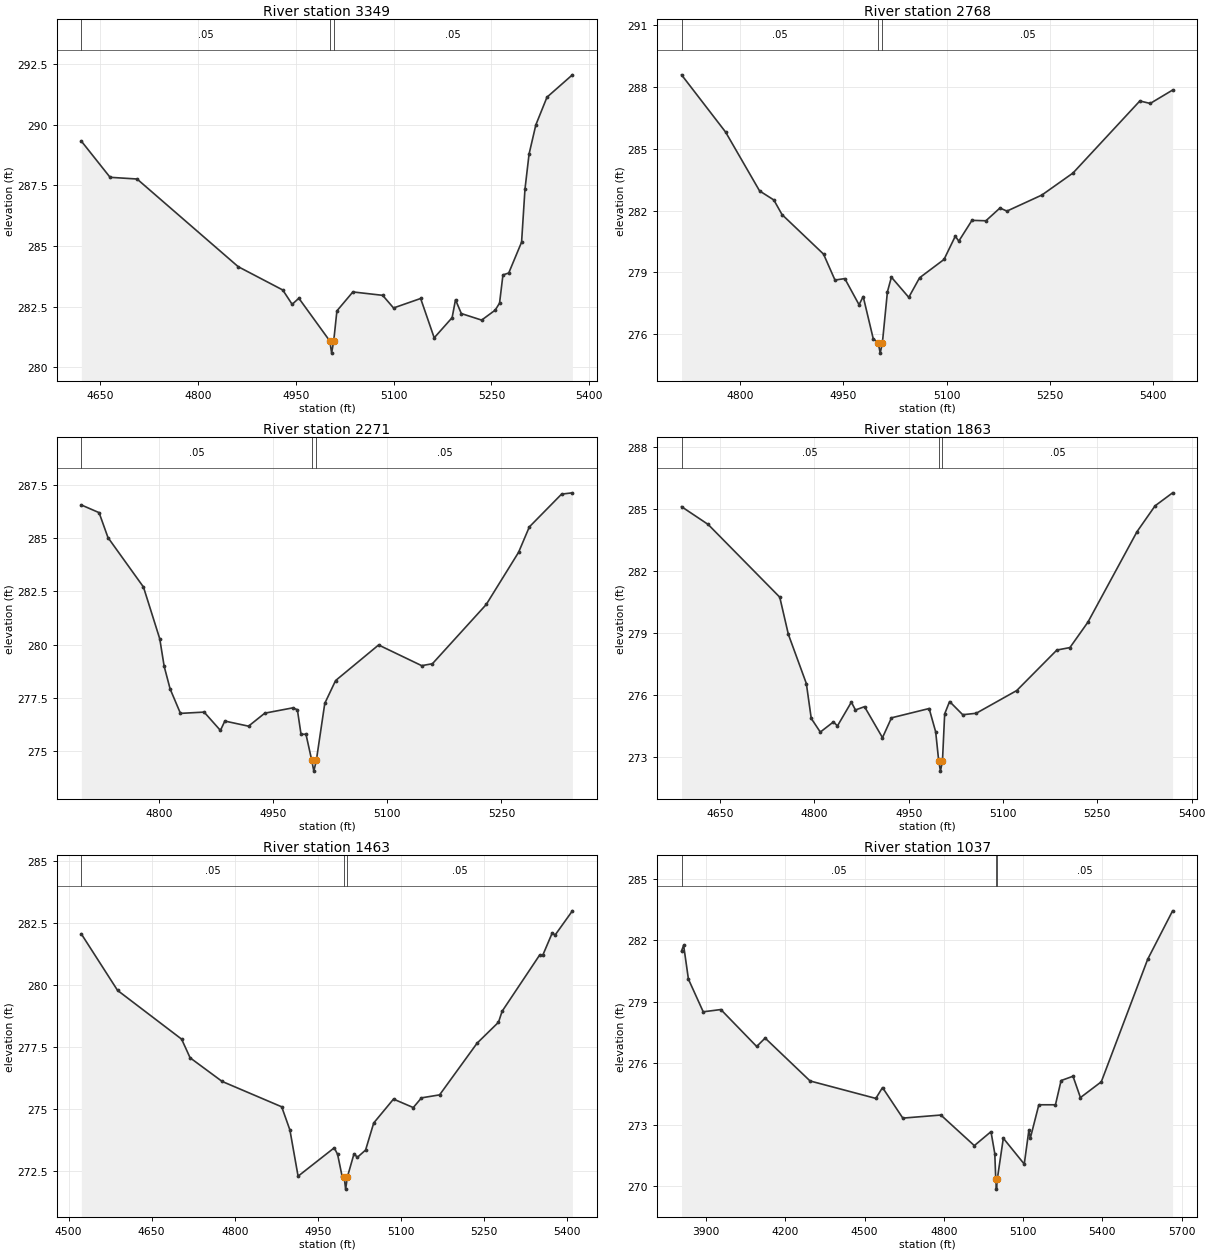
Type RM Length L Ch R = 1,3349,581,581,581
BEGIN DESCRIPTION:
WILSON BRANCH 6.0
END DESCRIPTION:
XS GIS Cut Line= 3
      3654474.77     10243406.26      3654095.73     10243305.63
      3653748.20     10243206.34
#Sta/Elev= 30
  4620.7  289.32  4664.8  287.83  4706.2  287.76  4861.4  284.15  4929.8  283.19
  4944.2  282.60  4954.5  282.85  5002.0  281.09  5004.8  280.59  5008.0  281.09
  5012.9  282.33  5037.4  283.11  5083.1  282.97  5099.8  282.45  5141.4  282.84
  5162.2  281.22  5189.7  282.05  5194.9  282.79  5203.8  282.22  5235.0  281.95
  5255.8  282.36  5262.5  282.65  5267.7  283.81  5276.6  283.89  5296.3  285.16
  5301.5  287.34  5307.8  288.79  5318.2  289.99  5335.3  291.13  5374.3  292.05
#Mann=3,-1,0
  4620.7    0.05       0  5002.0    0.03       0  5008.0    0.05       0
Bank Sta=5002,5008
Exp/Cntr=0.3,0.1

Type RM Length L Ch R = 1,2768,497,497,497
BEGIN DESCRIPTION:
WILSON BRANCH 5.0
END DESCRIPTION:
XS GIS Cut Line= 3
      3654592.08     10242891.64      3654247.56     10242804.37
      3653895.24     10242740.87
#Sta/Elev= 30
  4715.0  288.60  4779.0  285.82  4828.4  282.96  4849.1  282.52  4861.0  281.81
  4921.3  279.89  4937.9  278.63  4952.2  278.70  4972.9  277.43  4978.9  277.83
  4993.5  275.78  5000.8  275.58  5003.6  275.08  5006.8  275.58  5014.1  278.06
  5019.9  278.77  5045.1  277.79  5060.8  278.74  5096.3  279.63  5112.7  280.76
  5117.8  280.52  5136.9  281.53  5157.2  281.51  5177.6  282.13  5187.7  281.98
  5238.5  282.76  5283.7  283.83  5380.8  287.33  5395.9  287.21  5428.4  287.86
#Mann=3,-1,0
  4715.0    0.05       0  5000.8    0.03       0  5006.8    0.05       0
Bank Sta=5000.8,5006.8
Exp/Cntr=0.3,0.1

Type RM Length L Ch R = 1,2271,408,408,408
BEGIN DESCRIPTION:
WILSON BRANCH 4.0
END DESCRIPTION:
XS GIS Cut Line= 3
      3654692.09     10242541.63      3654442.11     10242391.64
      3654192.09     10242141.63
#Sta/Elev= 30
  4698.2  286.55  4721.5  286.19  4733.2  285.02  4779.8  282.70  4801.2  280.27
  4807.0  278.98  4814.8  277.92  4828.4  276.77  4859.5  276.83  4880.9  275.97
  4886.7  276.41  4917.8  276.17  4939.2  276.78  4976.1  277.03  4982.0  276.94
  4986.8  275.79  4993.3  275.79  5000.9  274.56  5003.6  274.06  5006.9  274.56
  5018.0  277.24  5032.2  278.31  5088.7  279.98  5145.3  279.01  5159.4  279.10
  5230.1  281.88  5272.6  284.33  5286.7  285.52  5329.1  287.06  5343.3  287.12
#Mann=3,-1,0
  4698.2    0.05       0  5000.9    0.03       0  5006.9    0.05       0
Bank Sta=5000.9,5006.9
Exp/Cntr=0.3,0.1

Type RM Length L Ch R = 1,1863,400,400,400
BEGIN DESCRIPTION:
WILSON BRANCH 3.0
END DESCRIPTION:
XS GIS Cut Line= 3
      3654892.12     10242341.66      3654642.11     10242041.64
      3654342.14     10241791.67
#Sta/Elev= 30
  4588.7  285.11  4631.0  284.25  4744.9  280.73  4758.6  278.93  4787.2  276.55
  4795.0  274.86  4809.4  274.20  4830.2  274.69  4836.7  274.50  4858.8  275.65
  4865.3  275.27  4879.7  275.43  4908.3  273.93  4922.6  274.89  4982.5  275.34
  4992.9  274.21  4997.7  272.81  5000.5  272.31  5003.7  272.81  5007.2  275.08
  5015.0  275.68  5035.9  275.04  5057.3  275.11  5121.8  276.21  5185.6  278.17
  5206.4  278.29  5235.0  279.52  5313.1  283.90  5341.8  285.15  5369.7  285.78
#Mann=3,-1,0
  4588.7    0.05       0  4997.7    0.03       0  5003.7    0.05       0
Bank Sta=4997.7,5003.7
Exp/Cntr=0.3,0.1

Type RM Length L Ch R = 1,1463,426,426,426
BEGIN DESCRIPTION:
WILSON BRANCH 2.0
END DESCRIPTION:
XS GIS Cut Line= 4
      3655092.08     10242041.61      3654918.06     10241763.17
      3654664.72     10241583.61      3654442.12     10241691.64
#Sta/Elev= 30
  4523.1  282.05  4588.5  279.78  4704.1  277.82  4719.4  277.07  4777.2  276.12
  4884.7  275.10  4899.5  274.17  4914.3  272.31  4979.5  273.45  4985.6  273.19
  4993.6  272.32  4997.4  272.29  5000.1  271.79  5003.4  272.29  5015.2  273.21
  5021.3  273.07  5036.1  273.36  5050.8  274.45  5086.5  275.41  5122.2  275.07
  5137.0  275.46  5169.7  275.58  5237.4  277.66  5276.0  278.50  5282.5  278.94
  5350.2  281.20  5355.8  281.19  5372.8  282.08  5378.3  282.01  5409.4  282.98
#Mann=3,-1,0
  4523.1    0.05       0  4997.4    0.03       0  5003.4    0.05       0
Bank Sta=4997.4,5003.4
Exp/Cntr=0.3,0.1

Type RM Length L Ch R = 1,1037,0,0,0
BEGIN DESCRIPTION:
WILSON BRANCH 1.0
END DESCRIPTION:
XS GIS Cut Line= 4
      3655406.75     10242209.12      3655095.29     10241347.73
      3654634.76     10241201.71      3654392.09     10241591.67
#Sta/Elev= 30
  3807.3  281.47  3815.2  281.75  3833.4  280.10  3889.4  278.51  3956.1  278.62
  4091.7  276.82  4123.6  277.23  4293.8  275.14  4542.6  274.29  4567.9  274.82
  4644.7  273.33  4788.7  273.48  4915.4  271.99  4978.4  272.67  4992.8  271.60
  4996.4  270.37  4999.1  269.87  5002.4  270.37  5025.1  272.35  5104.3  271.09
  5122.0  272.76  5127.2  272.35  5159.5  273.98  5222.4  273.98  5243.7  275.16
  5288.8  275.37  5316.9  274.33  5395.9  275.10  5571.4  281.07  5665.7  283.43
#Mann=3,-1,0
  3807.3    0.05       0  4996.4    0.03       0  5002.4    0.05       0
Bank Sta=4996.4,5002.4
Exp/Cntr=0.3,0.1

Chan Stop Cuts=-1