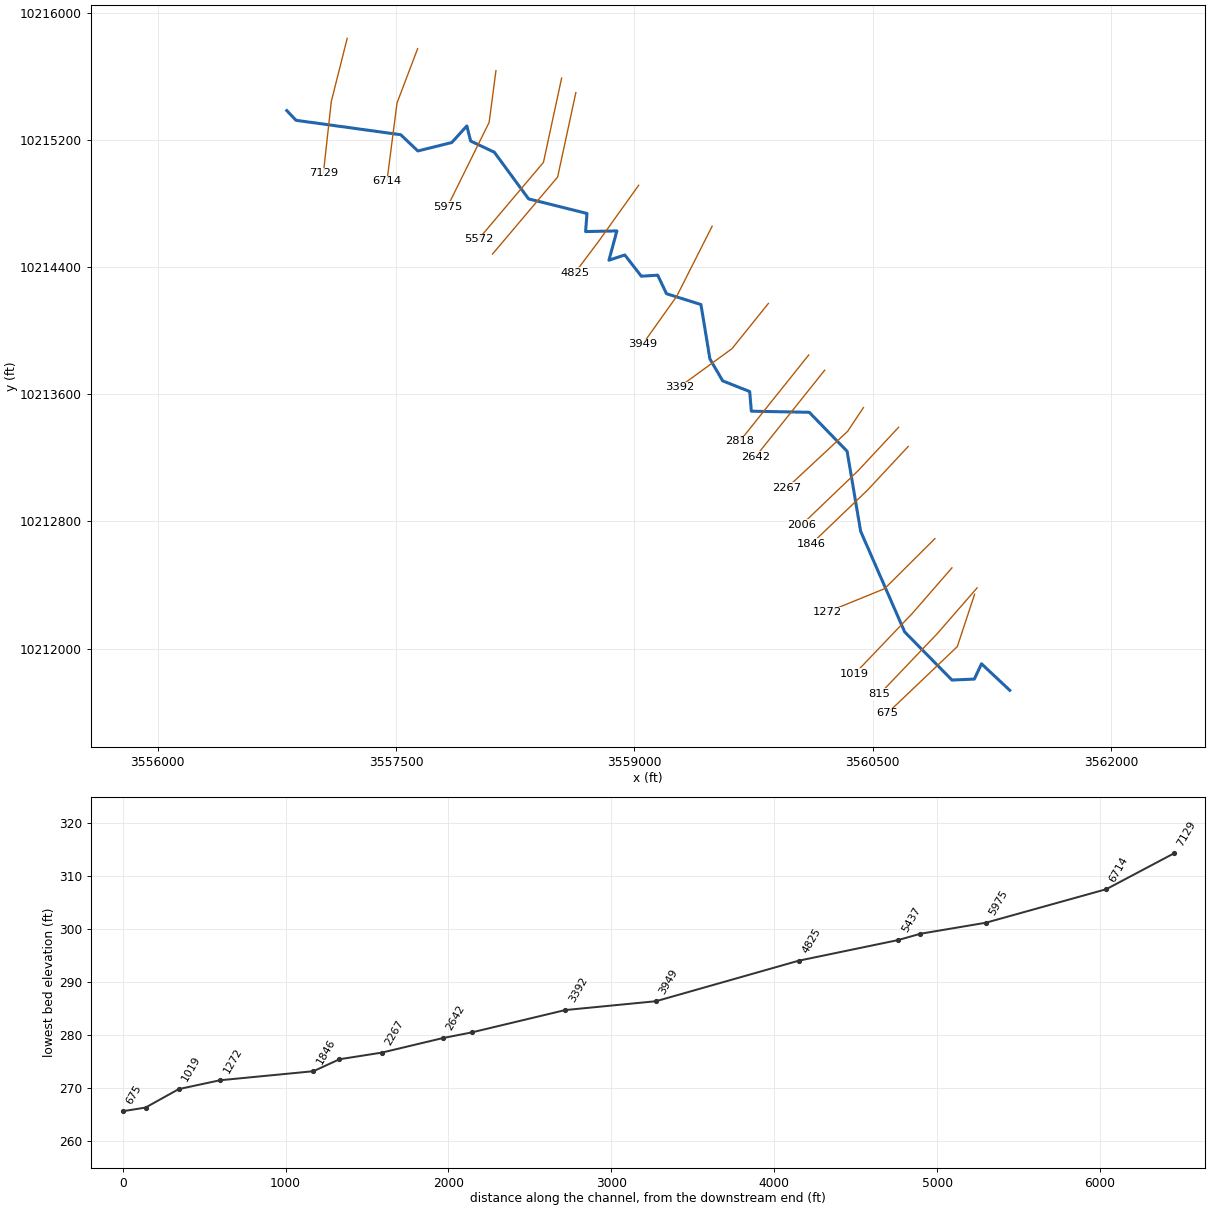
--- WOLF PEN CREEK TRIB A.prj (project) ---

Proj Title=WOLF PEN CREEK TRIB A Base Level Engineering
Current Plan=p01
Default Exp/Contr=0.3,0.1
English Units
Geom File=g01
Flow File=f01
Plan File=p01
Y Axis Title=Elevation
X Axis Title(PF)=Main Channel Distance
X Axis Title(XS)=Station
BEGIN DESCRIPTION:
WOLF PEN CREEK TRIB A
END DESCRIPTION:
DSS Export Rating Curves= 0
DSS Export Rating Curve Sorted= 0
DSS Export Volume Flow Curves= 0
DXF OffsetX= 0
DXF OffsetY= 0
DXF ScaleX= 1
DXF ScaleY= 10

--- WOLF PEN CREEK TRIB A.p01 (plan) ---

Plan Title=Multiple Run
Short Identifier=Multiple
Geom File=g01
Flow File=f01
Subcritical Flow
K Sum by GR= 0
Std Step Tol= 0.01
Critical Tol= 0.01
Num of Std Step Trials= 20
Max Error Tol= 0.3
Flow Tol Ratio= 0.001
Split Flow NTrial= 30
Split Flow Tol= 0.02
Split Flow Ratio= 0.02
Log Output Level= 0
Friction Slope Method= 1
Unsteady Friction Slope Method= 2
Unsteady Bridges Friction Slope Method= 1
Parabolic Critical Depth
Global Vel Dist=  1 , 1 , 1
Global Log Level= 0
CheckData=True
Encroach Param= -1, 0, 0, 0
BEGIN DESCRIPTION:
Multiple Run
END DESCRIPTION:

--- WOLF PEN CREEK TRIB A.f01 (steady flow) ---

Flow Title=Multiple
Program Version=4.10
Number of Profiles= 7
Profile Names=10-year,25-year,50-year,1pct_min,100-year,1pct_plu,500-year
River Rch & RM=WOLF PEN CREEK T,Reach-1         ,7129
     325     424     502     436     590     798     816
Boundary for River Rch & Prof#=WOLF PEN CREEK T,Reach-1         , 1
Up Type= 0
Dn Type= 3
Dn Slope=0.007
Boundary for River Rch & Prof#=WOLF PEN CREEK T,Reach-1         , 2
Up Type= 0
Dn Type= 3
Dn Slope=0.007
Boundary for River Rch & Prof#=WOLF PEN CREEK T,Reach-1         , 3
Up Type= 0
Dn Type= 3
Dn Slope=0.007
Boundary for River Rch & Prof#=WOLF PEN CREEK T,Reach-1         , 4
Up Type= 0
Dn Type= 3
Dn Slope=0.007
Boundary for River Rch & Prof#=WOLF PEN CREEK T,Reach-1         , 5
Up Type= 0
Dn Type= 3
Dn Slope=0.007
Boundary for River Rch & Prof#=WOLF PEN CREEK T,Reach-1         , 6
Up Type= 0
Dn Type= 3
Dn Slope=0.007
Boundary for River Rch & Prof#=WOLF PEN CREEK T,Reach-1         , 7
Up Type= 0
Dn Type= 3
Dn Slope=0.007
DSS Import GetInterval= 0
DSS Import GetPeak= 0
DSS Import FillOption= 0

--- WOLF PEN CREEK TRIB A.g01 (geometry) ---

Geom Title=Existing Conditions
Program Version=4.10

River Reach=WOLF PEN CREEK T,Reach-1
Reach XY= 30
      3556811.87     10215386.72      3556869.51     10215325.61
      3557528.96     10215234.79        3557637.     10215132.46
      3557850.14     10215185.55      3557945.37     10215289.99
      3557969.32     10215194.99      3558118.35      10215124.7
      3558333.78     10214830.96      3558701.84     10214739.08
      3558692.98     10214625.06      3558889.97     10214629.15
        3558840.     10214444.55      3558939.84     10214477.79
      3559043.76     10214343.98      3559146.98      10214350.4
      3559202.53     10214233.74       3559419.2     10214165.68
      3559475.63     10213823.07      3559556.01     10213685.13
      3559726.15     10213617.77      3559736.56     10213494.15
      3560101.15     10213487.21      3560339.34     10213242.07
      3560424.76      10212737.9      3560701.84     10212104.57
      3560999.76     10211801.39      3561140.38     10211807.46
      3561185.52     10211903.82       3561363.6     10211736.82

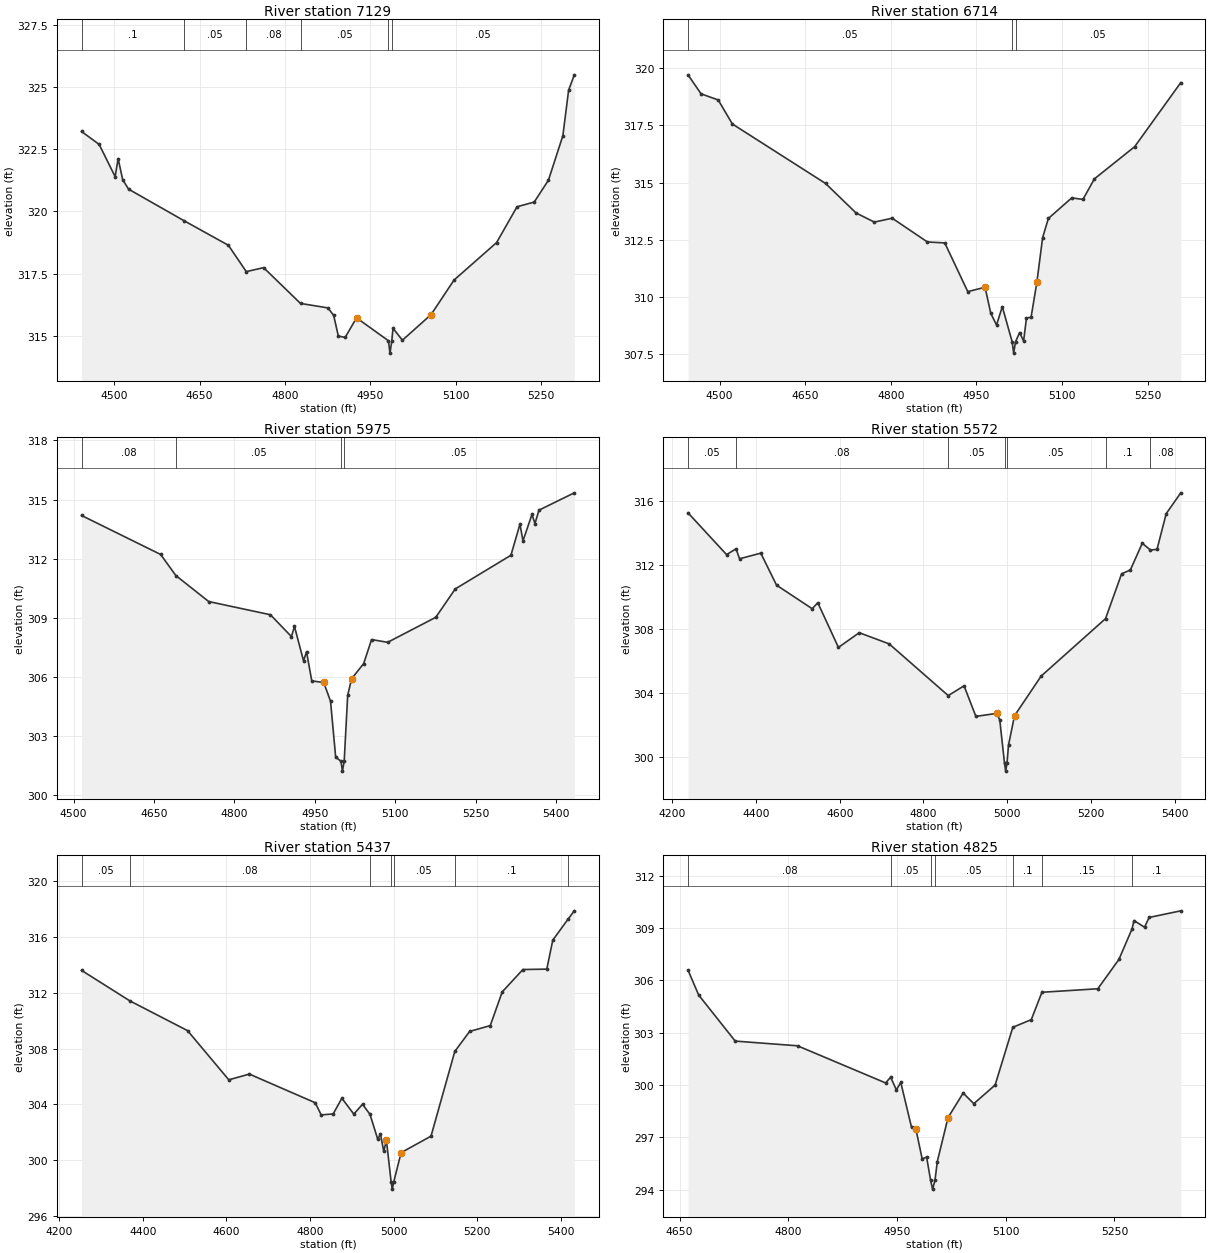
Type RM Length L Ch R = 1 ,7129    ,415,415,415
BEGIN DESCRIPTION:
WOLF PEN CREEK TRIB A 16.0
END DESCRIPTION:
XS GIS Cut Line= 3
       3557192.1     10215841.61      3557091.86     10215443.54
      3557042.11     10214991.67
#Sta/Elev= 30
  4442.9  323.22  4473.8   322.7  4501.9   321.4  4507.1  322.13  4515.1  321.28
  4525.4   320.9  4622.7  319.63  4700.7  318.64  4732.1  317.58  4762.5  317.74
  4827.3   316.3  4875.4  316.12  4885.5  315.82  4893.7  314.99  4905.6  314.93
  4925.7  315.72  4981.6   314.8  4984.4   314.3  4987.6   314.8  4989.7   315.3
  5006.2  314.82  5056.5  315.85  5096.8  317.24  5171.6  318.75  5207.4  320.19
  5237.6  320.38  5262.6  321.26  5287.9  323.05    5298  324.88    5308   325.5
#Mann= 6 ,-1 , 0
  4442.9      .1       0  4622.7     .05       0  4732.1     .08       0
  4827.3     .05       0  4981.6     .04       0  4987.6     .05       0
Bank Sta=4925.7,5056.5
XS Rating Curve= 0 ,0
Exp/Cntr=0.3,0.1

Type RM Length L Ch R = 1 ,6714    ,739,739,739
BEGIN DESCRIPTION:
WOLF PEN CREEK TRIB A 15.0
END DESCRIPTION:
XS GIS Cut Line= 3
      3557635.61     10215776.82      3557505.82     10215435.01
       3557442.1     10214941.63
#Sta/Elev= 30
  4444.8  319.71  4467.6  318.88  4497.7  318.61  4522.5  317.56  4685.7  314.96
  4739.1  313.67  4771.2  313.27  4802.4  313.44  4864.2   312.4  4894.5  312.36
  4934.8  310.23  4965.1  310.42  4975.1  309.28  4985.2  308.77  4995.3  309.57
  5012.5  308.04  5015.2  307.54  5018.5  308.04  5025.6  308.44  5032.6  308.07
  5037.6  309.07  5045.7  309.11  5055.8  310.63  5065.9  312.59    5076  313.43
    5117  314.33  5136.5  314.26  5156.6  315.16  5227.2  316.57  5307.9  319.37
#Mann= 3 ,-1 , 0
  4444.8     .05       0  5012.5     .04       0  5018.5     .05       0
Bank Sta=4965.1,5055.8
XS Rating Curve= 0 ,0
Exp/Cntr=0.3,0.1

Type RM Length L Ch R = 1 ,5975    ,403,403,403
BEGIN DESCRIPTION:
WOLF PEN CREEK TRIB A 14.0
END DESCRIPTION:
XS GIS Cut Line= 3
      3558128.67     10215637.96       3558085.7     10215312.43
      3557823.77     10214782.48
#Sta/Elev= 30
  4514.7  314.19  4662.3  312.21  4690.7  311.14    4752  309.82  4867.1  309.15
  4906.4  308.04    4912  308.56  4928.9  306.81  4934.5  307.27  4944.3  305.79
  4966.6  305.71  4979.3  304.76  4988.9  301.92  4998.8  301.71  5001.5  301.21
  5004.8  301.71  5011.3  305.06  5018.6   305.9  5041.1  306.67  5055.9  307.89
  5085.9  307.75  5175.7  309.02    5212  310.46  5315.9  312.17  5332.8  313.75
  5338.4   312.9  5355.2  314.24  5360.8  313.78  5368.2  314.46  5434.2  315.34
#Mann= 4 ,-1 , 0
  4514.7     .08       0  4690.7     .05       0  4998.8     .04       0
  5004.8     .05       0
Bank Sta=4966.6,5018.6
XS Rating Curve= 0 ,0
Exp/Cntr=0.3,0.1

Type RM Length L Ch R = 1 ,5572    ,135,135,135
BEGIN DESCRIPTION:
WOLF PEN CREEK TRIB A 13.0
END DESCRIPTION:
XS GIS Cut Line= 3
      3558542.11     10215591.64      3558427.58     10215060.52
      3558018.07     10214576.04
#Sta/Elev= 30
  4237.3  315.26  4329.4  312.65    4352  313.01  4360.5  312.39  4411.2  312.74
  4448.9  310.74    4534  309.27  4547.5  309.64  4596.8  306.85  4646.5  307.77
  4718.1  307.07  4859.2  303.84    4897  304.45  4925.3  302.54  4975.6  302.73
  4982.4  302.31  4993.7  299.62  4996.5  299.12  4999.7  299.62  5003.3  300.75
  5017.6  302.58  5081.3  305.06  5235.2  308.65  5273.6  311.45  5294.5  311.69
    5323  313.36  5342.6  312.93  5358.2  312.98  5380.2  315.21    5415  316.51
#Mann= 7 ,-1 , 0
  4237.3     .05       0    4352     .08       0  4859.2     .05       0
  4993.7     .04       0  4999.7     .05       0  5235.2      .1       0
  5342.6     .08       0
Bank Sta=4975.6,5017.6
XS Rating Curve= 0 ,0
Exp/Cntr=0.3,0.1

Type RM Length L Ch R = 1 ,5437    ,612,612,612
BEGIN DESCRIPTION:
WOLF PEN CREEK TRIB A 13.1
END DESCRIPTION:
XS GIS Cut Line= 3
      3558631.56     10215499.64      3558517.04     10214968.54
      3558107.06     10214483.51
#Sta/Elev= 30
  4253.6  313.59    4369  311.41  4507.1  309.28  4605.7  305.76  4654.9  306.17
  4812.4  304.12  4826.7  303.25  4855.3  303.32  4876.1  304.44  4904.7  303.31
  4925.5  304.01  4943.4  303.29  4961.9  301.51  4968.4  301.89  4976.2  300.65
  4982.7  301.43    4994  298.44  4996.7  297.94    5000  298.44  5017.8  300.55
  5089.3  301.73  5146.2  307.79  5181.6  309.22    5231  309.64  5259.6  312.05
    5309  313.65  5366.2  313.68  5380.5  315.75  5416.4  317.23    5432  317.85
#Mann= 7 ,-1 , 0
  4253.6     .05       0    4369     .08       0  4943.4     .05       0
    4994     .04       0    5000     .05       0  5146.2      .1       0
  5416.4     .08       0
Bank Sta=4982.7,5017.8
XS Rating Curve= 0 ,0
Exp/Cntr=0.3,0.1

Type RM Length L Ch R = 1 ,4825    ,876,876,876
BEGIN DESCRIPTION:
WOLF PEN CREEK TRIB A 11.0
END DESCRIPTION:
XS GIS Cut Line= 3
      3559027.13     10214916.49      3558777.14      10214566.5
       3558627.2     10214366.58
#Sta/Elev= 30
  4661.6  306.59  4676.3  305.16  4726.7  302.52  4812.7  302.25  4934.3  300.12
  4941.2  300.45  4949.1  299.72  4955.2  300.15    4970  297.58  4976.1  297.46
  4984.7  295.77  4990.9  295.86  4996.4  294.53  4999.1  294.03  5002.4  294.53
  5005.6  295.61  5020.4  298.13  5041.3  299.54    5056  298.93  5085.4     300
  5109.8  303.31  5135.3  303.75    5150  305.32  5227.1  305.52  5256.2   307.2
  5274.3  308.95  5277.1  309.43  5291.6  309.05  5297.9  309.61  5341.6  309.99
#Mann= 7 ,-1 , 0
  4661.6     .08       0  4941.2     .05       0  4996.4     .04       0
  5002.4     .05       0  5109.8      .1       0    5150     .15       0
  5274.3      .1       0
Bank Sta=4976.1,5020.4
XS Rating Curve= 0 ,0
Exp/Cntr=0.3,0.1

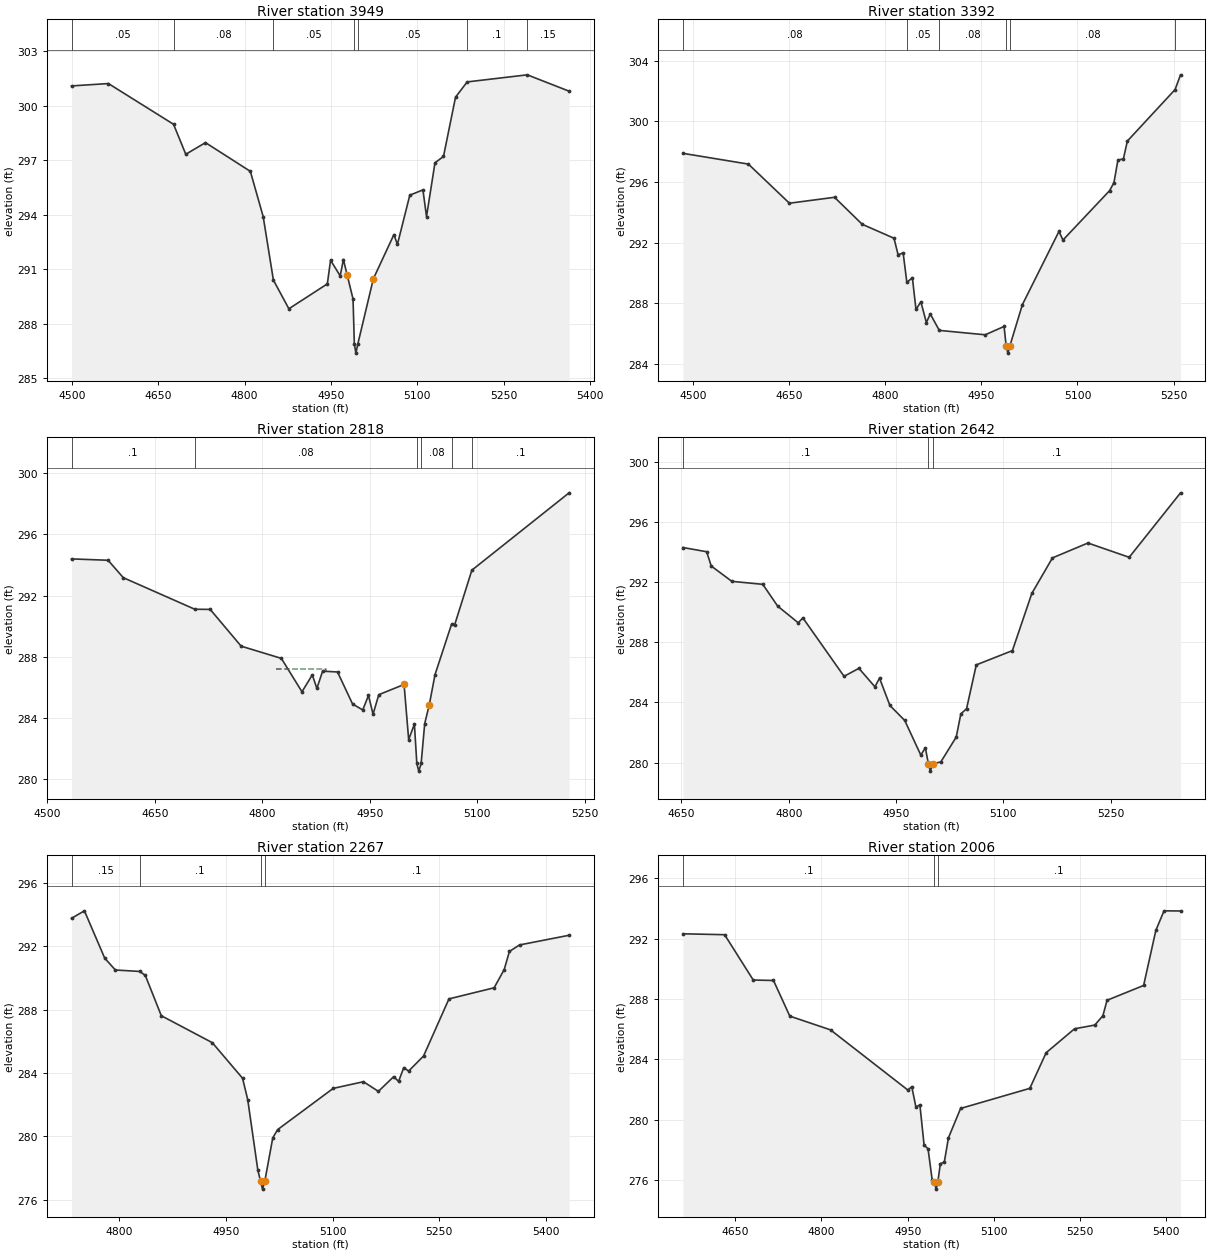
Type RM Length L Ch R = 1 ,3949    ,557,557,557
BEGIN DESCRIPTION:
WOLF PEN CREEK TRIB A 9.0
END DESCRIPTION:
XS GIS Cut Line= 3
      3559489.76     10214658.73      3559266.53     10214217.22
      3559052.63     10213916.21
#Sta/Elev= 30
  4499.4  301.08  4563.4  301.21  4676.5  298.97  4697.8  297.32    4732  297.96
  4809.9  296.38  4832.2  293.89  4849.9   290.4  4876.8  288.82  4943.6  290.19
  4949.2  291.49  4965.9  290.63  4971.5  291.53    4978  290.68  4988.2  289.36
  4990.5  286.88  4993.2  286.38  4996.5  286.88  5023.5  290.47  5059.2   292.9
  5065.3  292.36  5086.8  295.07  5109.6  295.36  5115.8  293.89  5130.5  296.85
  5145.3   297.2  5166.2  300.46  5186.4   301.3  5290.8  301.69  5363.4  300.79
#Mann= 7 ,-1 , 0
  4499.4     .05       0  4676.5     .08       0  4849.9     .05       0
  4990.5     .04       0  4996.5     .05       0  5186.4      .1       0
  5290.8     .15       0
Bank Sta=4978,5023.5
XS Rating Curve= 0 ,0
Exp/Cntr=0.3,0.1

Type RM Length L Ch R = 1 ,3392    ,574,574,574
BEGIN DESCRIPTION:
WOLF PEN CREEK TRIB A 8.0
END DESCRIPTION:
XS GIS Cut Line= 3
      3559843.94     10214172.65      3559614.78     10213887.93
      3559282.67     10213645.77
#Sta/Elev= 30
  4484.4  297.89  4586.5  297.18  4650.5   294.6  4720.9  294.99  4764.1  293.21
  4813.7  292.29  4820.1   291.2    4828  291.32  4833.8  289.37  4842.4  289.69
    4848   287.6  4855.7  288.09  4864.2  286.73  4870.4  287.29  4884.4  286.21
  4956.1  285.92  4985.5  286.47  4988.7  285.21  4991.4  284.71  4994.7  285.21
  5014.1  287.91  5071.2  292.74  5077.4  292.17  5150.2  295.43    5157  295.96
  5163.2  297.45  5171.7  297.52  5177.9   298.7  5252.4   302.1  5260.9  303.07
#Mann= 6 ,-1 , 0
  4484.4     .08       0  4833.8     .05       0  4884.4     .08       0
  4988.7     .07       0  4994.7     .08       0  5252.4     .05       0
Bank Sta=4988.7,4994.7
XS Rating Curve= 0 ,0
Exp/Cntr=0.3,0.1

Type RM Length L Ch R = 1 ,2818    ,176,176,176
BEGIN DESCRIPTION:
WOLF PEN CREEK TRIB A 7.0
END DESCRIPTION:
XS GIS Cut Line= 3
      3560097.76       10213848.      3559875.62     10213570.16
      3559664.18     10213305.59
#Sta/Elev= 30
  4533.8   294.4  4584.8  294.31    4606  293.17  4705.8   291.1  4727.3  291.09
  4770.5  288.68  4826.6  287.88  4855.4  285.69  4869.8   286.8  4876.2  285.91
  4884.2  287.04    4905  286.99    4926  284.89  4940.2   284.5  4948.2  285.45
  4954.6  284.22  4962.6   285.5  4997.9  286.17  5004.3  282.56  5012.3  283.57
  5015.7  280.99  5018.4  280.49  5021.7  280.99  5026.7  283.61  5033.1  284.84
  5041.1  286.82  5064.1  290.11  5068.3  290.05  5092.5  293.66  5228.2  298.73
#Mann= 6 ,-1 , 0
  4533.8      .1       0  4705.8     .08       0  5015.7     .07       0
  5021.7     .08       0  5064.1     .05       0  5092.5      .1       0
#XS Ineff= 1 ,-1
 4819.55 4889.09  287.16
Permanent Ineff=
       F
Bank Sta=4997.9,5033.1
XS Rating Curve= 0 ,0
Exp/Cntr=0.3,0.1

Type RM Length L Ch R = 1 ,2642    ,375,375,375
BEGIN DESCRIPTION:
WOLF PEN CREEK TRIB A 7.1
END DESCRIPTION:
XS GIS Cut Line= 3
       3560198.2     10213751.98      3559976.05     10213474.12
      3559763.82     10213208.56
#Sta/Elev= 30
  4652.1  294.31  4685.2  294.03  4691.6  293.08  4720.4  292.06  4763.7  291.86
  4784.5  290.41  4813.3   289.3  4819.7  289.63  4877.3  285.74  4898.1  286.27
  4920.5  285.04  4926.9  285.62  4941.4   283.8  4962.2   282.8  4984.6   280.5
    4991  280.98  4995.2  279.93    4998  279.43  5001.2  279.93  5012.6  280.04
  5034.2   281.7  5040.6  283.24  5048.6  283.58  5062.2   286.5  5112.7  287.45
  5139.9  291.26  5168.7  293.62  5218.3  294.61    5276  293.66  5347.8  297.95
#Mann= 3 ,-1 , 0
  4652.1      .1       0  4995.2     .07       0  5001.2      .1       0
Bank Sta=4995.2,5001.2
XS Rating Curve= 0 ,0
Exp/Cntr=0.3,0.1

Type RM Length L Ch R = 1 ,2267    ,261,261,261
BEGIN DESCRIPTION:
WOLF PEN CREEK TRIB A 5.0
END DESCRIPTION:
XS GIS Cut Line= 3
      3560442.12     10213516.67      3560342.11     10213366.64
      3559962.02     10213012.95
#Sta/Elev= 30
    4733  293.75  4751.1  294.22  4779.6  291.24  4794.6  290.49  4828.9   290.4
  4836.7  290.15  4859.2  287.61  4930.9  285.91  4973.4  283.67  4980.7  282.32
  4994.9  277.88  4998.7  277.18  5001.5  276.68  5004.7  277.18  5015.9  279.91
  5022.7  280.43  5100.9  283.03  5143.4  283.45  5164.4  282.84  5185.9  283.77
  5192.8  283.47  5200.1  284.34  5206.9  284.12  5227.9  285.07  5263.6  288.67
  5327.1  289.37  5341.3  290.52  5348.6  291.66  5362.8  292.07  5432.5  292.68
#Mann= 4 ,-1 , 0
    4733     .15       0  4828.9      .1       0  4998.7     .07       0
  5004.7      .1       0
Bank Sta=4998.7,5004.7
XS Rating Curve= 0 ,0
Exp/Cntr=0.3,0.1

Type RM Length L Ch R = 1 ,2006    ,160,160,160
BEGIN DESCRIPTION:
WOLF PEN CREEK TRIB A 4.1
END DESCRIPTION:
XS GIS Cut Line= 3
      3560663.54     10213392.76       3560407.1     10213117.67
      3560053.85     10212779.21
#Sta/Elev= 30
  4559.3  292.32  4631.7  292.26  4681.5  289.26  4716.7  289.23  4745.1  286.87
  4815.9  285.96  4950.3  281.98  4957.2   282.2  4964.4  280.85  4971.3     281
  4978.6  278.34  4985.5  278.09  4992.7  276.02  4996.6  275.92  4999.4  275.42
  5002.6  275.92  5006.9   277.1  5013.8  277.22    5021  278.82  5042.1  280.76
  5162.5  282.09  5190.9  284.45  5240.2  286.03  5275.5  286.28  5289.6   286.9
  5296.8  287.92  5360.4   288.9  5381.7  292.55  5395.9  293.84  5424.6  293.83
#Mann= 3 ,-1 , 0
  4559.3      .1       0  4996.6     .07       0  5002.6      .1       0
Bank Sta=4996.6,5002.6
XS Rating Curve= 0 ,0
Exp/Cntr=0.3,0.1

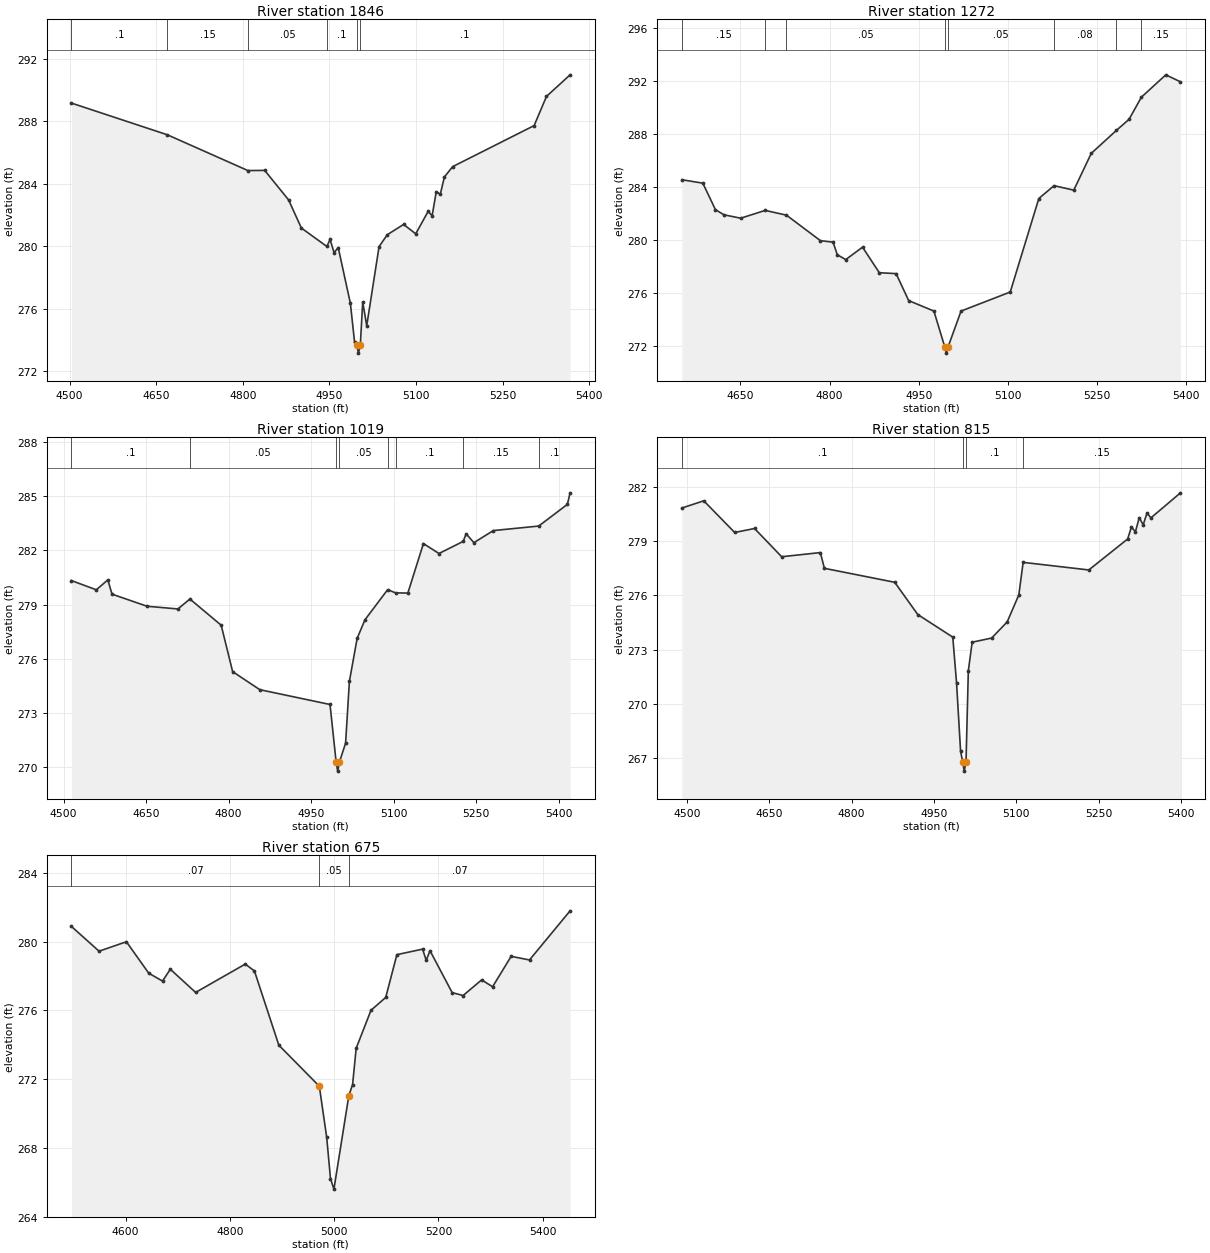
Type RM Length L Ch R = 1 ,1846    ,574,574,574
BEGIN DESCRIPTION:
WOLF PEN CREEK TRIB A 4.0
END DESCRIPTION:
XS GIS Cut Line= 3
      3560724.47     10213272.32      3560468.02     10212997.22
      3560115.94     10212659.88
#Sta/Elev= 30
  4503.4  289.17  4669.5  287.14    4809  284.85  4838.1  284.86  4879.5  282.97
  4901.6  281.17  4945.8  279.99  4951.3  280.44  4958.2   279.6  4965.5  279.91
  4986.5  276.35  4993.8  273.85  4997.7  273.66  5000.4  273.16  5003.7  273.66
  5007.9  276.45  5014.8  274.91  5036.2  279.98  5050.4  280.74  5078.7   281.4
  5099.7   280.8  5121.1  282.23  5128.1  281.96  5135.3   283.5  5142.2  283.33
  5149.4  284.44  5163.6   285.1  5304.8  287.73  5326.2   289.6  5367.1  290.98
#Mann= 6 ,-1 , 0
  4503.4      .1       0  4669.5     .15       0    4809     .05       0
  4945.8      .1       0  4997.7     .07       0  5003.7      .1       0
Bank Sta=4997.7,5003.7
XS Rating Curve= 0 ,0
Exp/Cntr=0.3,0.1

Type RM Length L Ch R = 1 ,1272    ,253,253,253
BEGIN DESCRIPTION:
WOLF PEN CREEK TRIB A 3.0
END DESCRIPTION:
XS GIS Cut Line= 3
       3560892.1     10212691.64      3560575.83      10212376.9
      3560212.03     10212228.22
#Sta/Elev= 30
  4551.5  284.56  4586.8   284.3    4608   282.3  4622.2  281.91  4650.5  281.65
  4691.8  282.24  4727.6  281.88  4784.8  279.95    4806  279.84  4813.1  278.89
  4827.3  278.52  4855.6  279.46  4883.8  277.53  4912.1  277.46  4933.3  275.42
  4975.7  274.63  4993.8  271.95  4996.5  271.45  4999.8  271.95  5021.4  274.63
  5104.2  276.07  5152.3  283.14  5177.9  284.11  5211.1  283.77  5240.5  286.55
  5282.9  288.29  5304.2  289.13  5324.9   290.8    5366  292.49  5390.7  291.96
#Mann= 8 ,-1 , 0
  4551.5     .15       0  4691.8      .1       0  4727.6     .05       0
  4993.8     .04       0  4999.8     .05       0  5177.9     .08       0
  5282.9      .1       0  5324.9     .15       0
Bank Sta=4993.8,4999.8
XS Rating Curve= 0 ,0
Exp/Cntr=0.3,0.1

Type RM Length L Ch R = 1 ,1019    ,204,204,204
BEGIN DESCRIPTION:
WOLF PEN CREEK TRIB A 2.0
END DESCRIPTION:
XS GIS Cut Line= 3
      3560999.52     10212507.65      3560747.77     10212218.59
      3560386.39     10211840.14
#Sta/Elev= 30
  4514.2  280.33  4559.4  279.82  4580.3  280.37  4587.9  279.58  4651.5  278.91
  4707.8  278.76  4729.5  279.31  4786.4  277.86  4807.2  275.29  4856.6  274.29
  4984.3  273.47  4995.4  270.28  4998.2  269.78  5001.4  270.28  5012.6  271.33
  5019.5  274.75  5033.6  277.13  5047.8  278.16  5089.1  279.83  5103.4  279.65
  5125.8  279.64  5154.1  282.38  5182.4  281.83  5226.4   282.5  5231.8  282.92
  5245.9  282.43  5281.2   283.1  5363.7  283.35  5415.8  284.55  5420.8  285.19
#Mann= 8 ,-1 , 0
  4514.2      .1       0  4729.5     .05       0  4995.4     .04       0
  5001.4     .05       0  5089.1     .08       0  5103.4      .1       0
  5226.4     .15       0  5363.7      .1       0
Bank Sta=4995.4,5001.4
XS Rating Curve= 0 ,0
Exp/Cntr=0.3,0.1

Type RM Length L Ch R = 1 ,815     ,140,140,140
BEGIN DESCRIPTION:
WOLF PEN CREEK TRIB A 2.1
END DESCRIPTION:
XS GIS Cut Line= 3
      3561158.04     10212381.76      3560906.29     10212092.71
      3560544.15     10211713.45
#Sta/Elev= 30
    4491  280.82  4530.9  281.22  4587.2  279.47  4623.3  279.69  4672.7  278.13
  4743.1  278.36  4750.5  277.49  4878.5  276.72  4920.4  274.94  4984.2  273.69
  4991.1  271.15  4998.4  267.39  5002.3  266.79    5005  266.29  5008.3  266.79
  5012.5  271.83  5019.5  273.41    5055  273.64  5083.2  274.53  5104.4  276.02
  5112.3  277.82  5231.8   277.4  5302.5  279.11  5309.4  279.77  5316.7  279.51
  5323.6  280.29  5330.8  279.89  5337.7  280.54    5345  280.28  5398.7  281.66
#Mann= 4 ,-1 , 0
    4491      .1       0  5002.3     .07       0  5008.3      .1       0
  5112.3     .15       0
Bank Sta=5002.3,5008.3
XS Rating Curve= 0 ,0
Exp/Cntr=0.3,0.1

Type RM Length L Ch R = 1 ,675     ,0,0,0
BEGIN DESCRIPTION:
WOLF PEN CREEK TRIB A 1.0
END DESCRIPTION:
XS GIS Cut Line= 3
      3561142.12     10212341.69      3561033.34     10212012.13
      3560592.07     10211591.61
#Sta/Elev= 30
  4496.1  280.89    4549  279.45  4601.5     280  4644.3  278.17  4670.8  277.71
  4685.7   278.4  4734.3  277.05  4829.5   278.7  4847.1   278.3  4893.9  273.98
  4971.6  271.59  4985.7  268.62    4993  266.21  4999.6   265.6  5028.2  271.04
  5035.4  271.69  5042.3   273.8  5070.7  276.01    5099  276.76  5120.4  279.25
  5169.7  279.57  5176.6  278.92  5183.9  279.48  5226.4  277.04  5247.4  276.87
    5283  277.78    5304  277.38  5339.6  279.15  5374.8  278.94  5452.7   281.8
#Mann= 3 , 0 , 0
  4496.1     .07       0  4971.6     .05       0  5028.2     .07       0
Bank Sta=4971.6,5028.2
XS Rating Curve= 0 ,0
Exp/Cntr=0.3,0.1

Chan Stop Cuts=-1
Use User Specified Reach Order=0
Composite Channel Slope=5