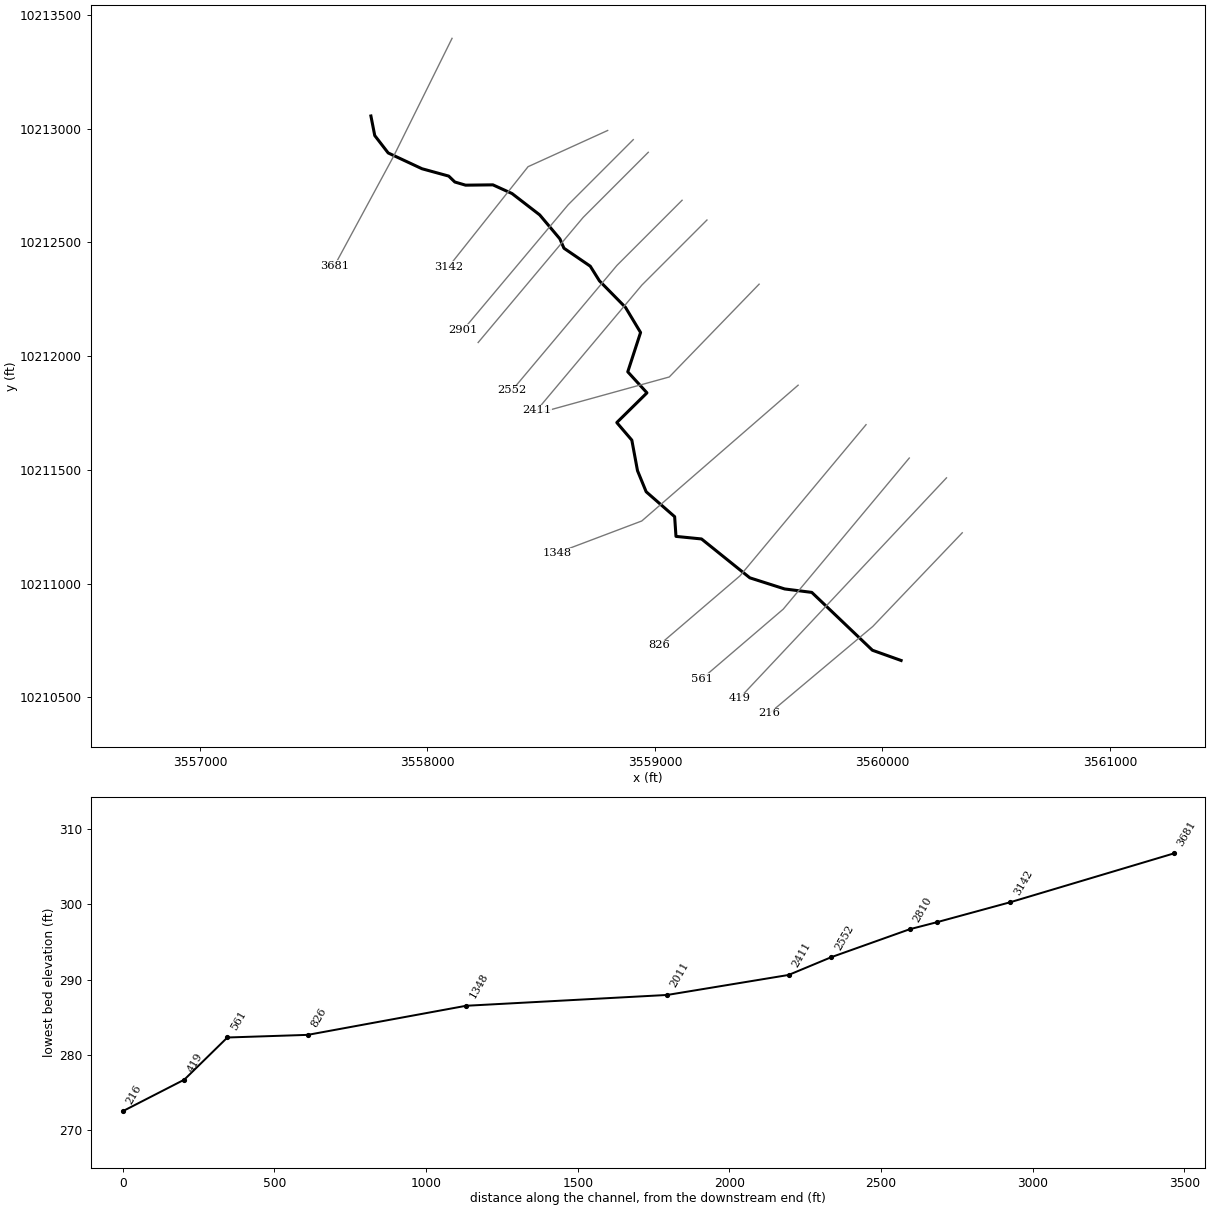
--- WOLF PEN CREEK TRIB B.prj (project) ---

Proj Title=WOLF PEN CREEK TRIB B Base Level Engineering
Current Plan=p01
Default Exp/Contr=0.3,0.1
English Units
Geom File=g01
Flow File=f01
Plan File=p01
Y Axis Title=Elevation
X Axis Title(PF)=Main Channel Distance
X Axis Title(XS)=Station
BEGIN DESCRIPTION:
WOLF PEN CREEK TRIB B
END DESCRIPTION:
DSS Export Rating Curves= 0
DSS Export Rating Curve Sorted= 0
DSS Export Volume Flow Curves= 0
DXF OffsetX= 0
DXF OffsetY= 0
DXF ScaleX= 1
DXF ScaleY= 10

--- WOLF PEN CREEK TRIB B.p01 (plan) ---

Plan Title=Multiple Run
Short Identifier=Multiple
Geom File=g01
Flow File=f01
Subcritical Flow
K Sum by GR= 0
Std Step Tol= 0.01
Critical Tol= 0.01
Num of Std Step Trials= 20
Max Error Tol= 0.3
Flow Tol Ratio= 0.001
Split Flow NTrial= 30
Split Flow Tol= 0.02
Split Flow Ratio= 0.02
Log Output Level= 0
Friction Slope Method= 1
Unsteady Friction Slope Method= 2
Unsteady Bridges Friction Slope Method= 1
Parabolic Critical Depth
Global Vel Dist=  1 , 1 , 1
Global Log Level= 0
CheckData=True
Encroach Param= -1, 0, 0, 0
BEGIN DESCRIPTION:
Multiple Run
END DESCRIPTION:

--- WOLF PEN CREEK TRIB B.f01 (steady flow) ---

Flow Title=Multiple
Number of Profiles=7
Profile Names=10-year,25-year,50-year,1pct_min,100-year,1pct_plu,500-year
River Rch & RM= WOLF PEN CREEK T,Reach-1,3681
     274     353     415     358     484     654     659
Boundary for River Rch & Prof#=WOLF PEN CREEK T,Reach-1,1
Up Type=0
Dn Type=3
Dn Slope=0.005
Boundary for River Rch & Prof#=WOLF PEN CREEK T,Reach-1,2
Up Type=0
Dn Type=3
Dn Slope=0.005
Boundary for River Rch & Prof#=WOLF PEN CREEK T,Reach-1,3
Up Type=0
Dn Type=3
Dn Slope=0.005
Boundary for River Rch & Prof#=WOLF PEN CREEK T,Reach-1,4
Up Type=0
Dn Type=3
Dn Slope=0.005
Boundary for River Rch & Prof#=WOLF PEN CREEK T,Reach-1,5
Up Type=0
Dn Type=3
Dn Slope=0.005
Boundary for River Rch & Prof#=WOLF PEN CREEK T,Reach-1,6
Up Type=0
Dn Type=3
Dn Slope=0.005
Boundary for River Rch & Prof#=WOLF PEN CREEK T,Reach-1,7
Up Type=0
Dn Type=3
Dn Slope=0.005

--- WOLF PEN CREEK TRIB B.g01 (geometry) ---

Geom Title=Existing Conditions
Program Version=4.10

River Reach=WOLF PEN CREEK T,Reach-1
Reach XY= 30
      3557751.25     10213055.31      3557768.15     10212969.24
      3557827.17     10212892.85      3557975.78      10212823.4
      3558093.36     10212791.08      3558120.23     10212765.07
      3558167.45     10212751.18      3558287.59     10212752.57
      3558371.62     10212714.38      3558493.15     10212620.63
      3558582.03     10212515.07       3558599.9     10212473.97
      3558715.59     10212394.99      3558755.79     10212330.66
      3558870.37     10212214.07      3558936.71     10212103.52
      3558880.42     10211930.64      3558964.85     10211838.18
      3558832.18     10211707.52      3558898.27     10211630.28
      3558923.27     10211495.91      3558961.34     10211403.33
      3559086.52     10211293.79      3559092.38     10211207.14
      3559204.66      10211195.9      3559417.11     10211024.96
       3559570.1     10210976.13      3559689.46     10210960.94
      3559955.95     10210706.63      3560082.11     10210661.64

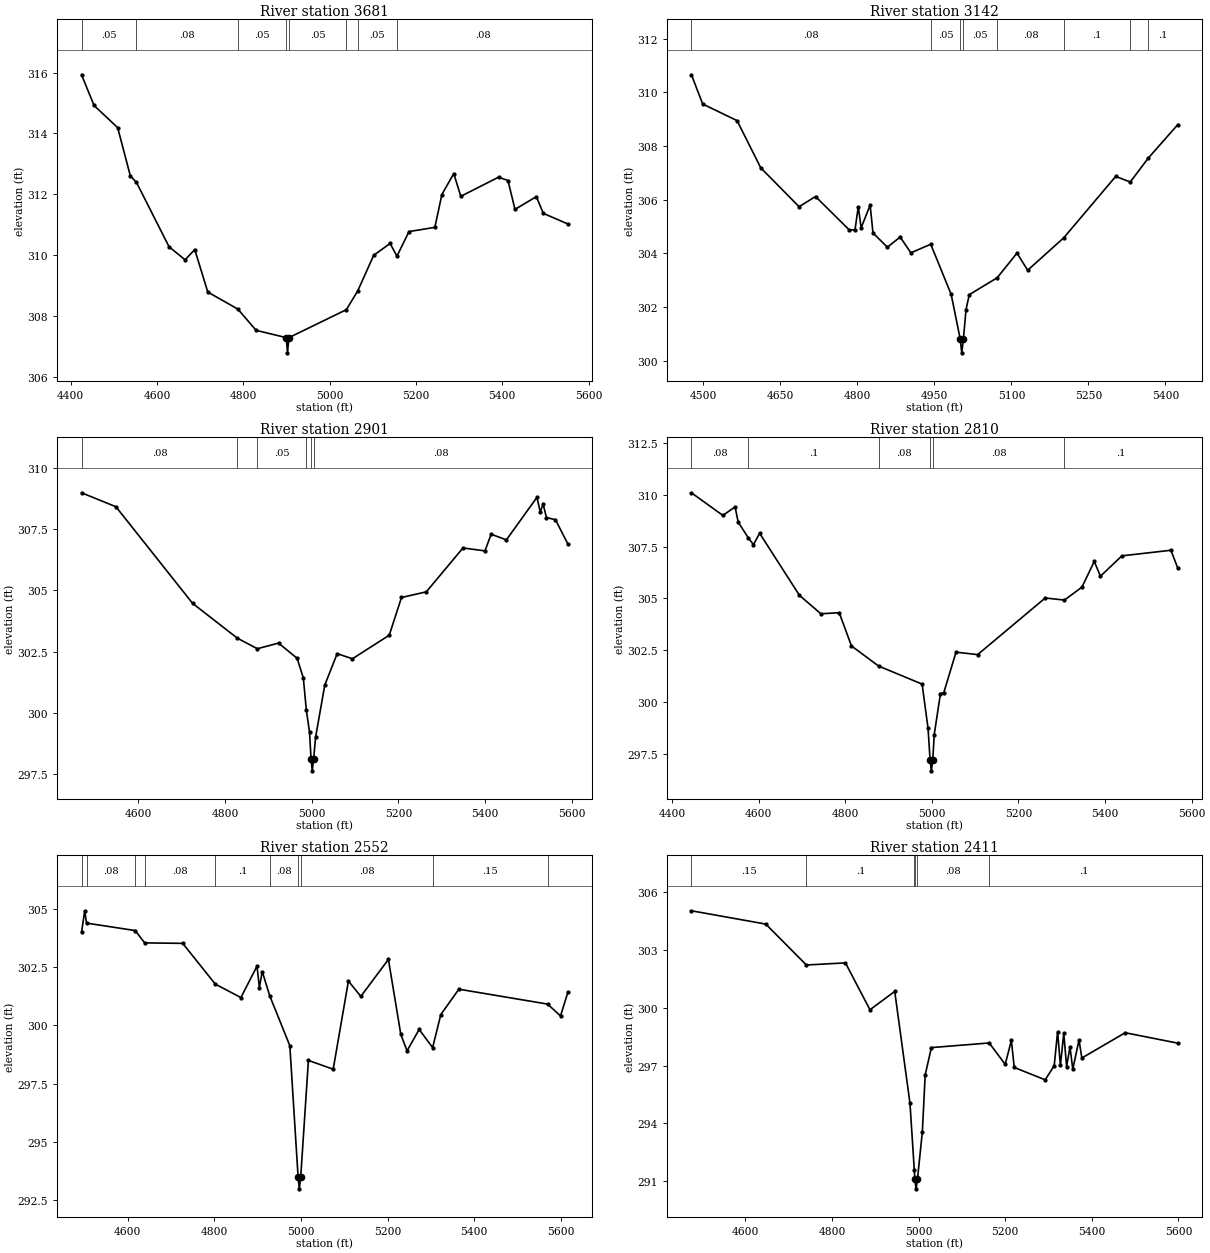
Type RM Length L Ch R = 1 ,3681    ,539,539,539
BEGIN DESCRIPTION:
WOLF PEN CREEK TRIB B 8.0
END DESCRIPTION:
XS GIS Cut Line= 3
      3558107.96     10213396.68      3557851.86     10212879.79
      3557590.45     10212395.84
#Sta/Elev= 30
  4425.1  315.93  4454.1  314.92  4508.8  314.19  4538.2   312.6  4552.3  312.39
  4627.9  310.27  4665.1  309.84  4687.4  310.18  4717.6  308.78  4787.2  308.22
  4829.7  307.52  4899.5  307.28  4902.3  306.78  4905.5  307.28  5038.7   308.2
  5065.1  308.82  5102.1  309.99  5140.1  310.38  5155.9  309.96  5183.8  310.77
  5243.8  310.91    5260  311.99  5287.6  312.68  5303.8  311.93  5391.3  312.56
  5413.2  312.45  5429.4   311.5  5478.9  311.92  5495.1  311.37    5552  311.02
#Mann= 8 ,-1 , 0
  4425.1     .05       0  4552.3     .08       0  4787.2     .05       0
  4899.5     .04       0  4905.5     .05       0  5038.7     .08       0
  5065.1     .05       0  5155.9     .08       0
Bank Sta=4899.5,4905.5
XS Rating Curve= 0 ,0
Exp/Cntr=0.3,0.1

Type RM Length L Ch R = 1 ,3142    ,241,241,241
BEGIN DESCRIPTION:
WOLF PEN CREEK TRIB B 6.0
END DESCRIPTION:
XS GIS Cut Line= 3
      3558792.08     10212991.63      3558442.14     10212832.42
      3558092.11     10212391.65
#Sta/Elev= 30
  4476.7  310.66  4498.6  309.57  4565.6  308.95  4611.7  307.19  4686.4  305.74
  4718.4  306.12  4784.3  304.87  4795.3  304.88  4801.7  305.74  4807.2  304.95
  4824.8   305.8  4830.3  304.76  4858.4  304.23  4883.3  304.61  4904.1  304.02
  4942.8  304.34  4982.6  302.47  5000.4  300.79  5003.2  300.29  5006.4  300.79
  5011.5   301.9  5017.9  302.46  5072.3  303.09  5110.8  304.01  5131.6  303.37
  5201.9  304.58  5303.1  306.87  5331.4  306.66  5366.4  307.55    5424   308.8
#Mann= 8 ,-1 , 0
  4476.7     .08       0  4942.8     .05       0  5000.4     .04       0
  5006.4     .05       0  5072.3     .08       0  5201.9      .1       0
  5331.4     .08       0  5366.4      .1       0
Bank Sta=5000.4,5006.4
XS Rating Curve= 0 ,0
Exp/Cntr=0.3,0.1

Type RM Length L Ch R = 1 ,2901    ,91,91,91
BEGIN DESCRIPTION:
WOLF PEN CREEK TRIB B 5.3
END DESCRIPTION:
XS GIS Cut Line= 3
      3558904.63     10212951.28      3558618.19     10212664.84
      3558157.59     10212116.11
#Sta/Elev= 30
  4469.4  308.98  4548.7  308.41  4725.5  304.47  4828.7  303.05  4874.8  302.62
  4923.6  302.85  4966.5  302.23  4980.8  301.43  4987.8  300.11  4995.1  299.22
  4998.6  298.14  5001.4  297.64  5004.6  298.14  5009.2  299.02  5030.3  301.14
  5058.9  302.42    5094  302.21  5178.9  303.17  5207.2  304.71  5264.4  304.94
    5349  306.73  5399.7  306.61  5413.9  307.29  5449.1  307.06  5519.4  308.79
  5527.2   308.2  5533.7  308.52  5541.5  307.97  5562.3  307.88  5590.9  306.89
#Mann= 6 ,-1 , 0
  4469.4     .08       0  4828.7      .1       0  4874.8     .05       0
  4987.8     .08       0  4998.6     .07       0  5004.6     .08       0
Bank Sta=4998.6,5004.6
XS Rating Curve= 0 ,0
Exp/Cntr=0.3,0.1

Type RM Length L Ch R = 1 ,2810    ,258,258,258
BEGIN DESCRIPTION:
WOLF PEN CREEK TRIB B 5.2
END DESCRIPTION:
XS GIS Cut Line= 3
      3558970.61     10212895.73      3558684.16     10212609.28
      3558222.68     10212059.49
#Sta/Elev= 30
  4445.1  310.09  4517.6     309  4545.9  309.41    4553  308.68  4576.6  307.91
  4588.4  307.59  4602.5  308.14  4694.4  305.15  4743.9  304.26  4786.3  304.31
  4814.6  302.71  4877.2  301.74  4977.7  300.87  4991.4  298.74  4996.2  297.19
    4999  296.69  5002.2  297.19  5005.7  298.44    5020  300.41  5027.8  300.46
    5056  302.41  5105.9  302.29    5262  305.02  5306.3  304.92  5346.6  305.54
  5375.2  306.78  5389.5  306.07  5438.9  307.05  5552.1  307.32    5568  306.46
#Mann= 6 ,-1 , 0
  4445.1     .08       0  4576.6      .1       0  4877.2     .08       0
  4996.2     .07       0  5002.2     .08       0  5306.3      .1       0
Bank Sta=4996.2,5002.2
XS Rating Curve= 0 ,0
Exp/Cntr=0.3,0.1

Type RM Length L Ch R = 1 ,2552    ,141,141,141
BEGIN DESCRIPTION:
WOLF PEN CREEK TRIB B 5.1
END DESCRIPTION:
XS GIS Cut Line= 3
      3559119.21     10212684.83      3558832.77     10212398.39
      3558371.28     10211848.59
#Sta/Elev= 30
  4493.2  304.01  4500.5  304.93  4504.7   304.4  4617.1  304.08    4639  303.55
  4726.8  303.53  4801.9  301.78  4861.1   301.2  4898.3  302.55  4903.8  301.63
  4910.4  302.32  4927.6  301.28  4974.1  299.13  4993.2  293.48  4995.9  292.98
  4999.2  293.48    5017   298.5  5074.2  298.12  5109.4  301.91    5138  301.25
  5201.7  302.84  5230.3  299.62  5244.7  298.91  5272.7  299.83  5303.8  299.05
  5322.7  300.47  5364.4  301.56  5569.2  300.92  5599.1  300.41  5616.1  301.43
#Mann= 10 ,-1 , 0
  4493.2      .1       0  4504.7     .08       0  4617.1      .1       0
    4639     .08       0  4801.9      .1       0  4927.6     .08       0
  4993.2     .07       0  4999.2     .08       0  5303.8     .15       0
  5569.2      .1       0
Bank Sta=4993.2,4999.2
XS Rating Curve= 0 ,0
Exp/Cntr=0.3,0.1

Type RM Length L Ch R = 1 ,2411    ,400,400,400
BEGIN DESCRIPTION:
WOLF PEN CREEK TRIB B 5.0
END DESCRIPTION:
XS GIS Cut Line= 3
      3559228.58     10212598.02      3558942.14     10212311.58
      3558480.65     10211761.78
#Sta/Elev= 30
  4475.5  305.02  4647.2  304.33  4740.9  302.21  4831.1  302.32  4887.7  299.89
  4944.9  300.84  4980.1  295.04  4990.1  291.57  4991.4  291.11  4994.1  290.61
  4997.4  291.11  5008.7  293.58  5015.2  296.51  5029.5  297.93  5163.1  298.17
  5199.9  297.06  5214.2   298.3  5220.8   296.9  5292.3  296.26  5313.1  296.99
  5320.9  298.75  5327.4  297.01  5335.2  298.67  5341.7  296.95  5349.5  297.96
    5356  296.81  5370.4  298.33  5376.9  297.39    5477   298.7  5598.4  298.16
#Mann= 6 ,-1 , 0
  4475.5     .15       0  4740.9      .1       0  4990.1     .08       0
  4991.4     .07       0  4997.4     .08       0  5163.1      .1       0
Bank Sta=4991.4,4997.4
XS Rating Curve= 0 ,0
Exp/Cntr=0.3,0.1

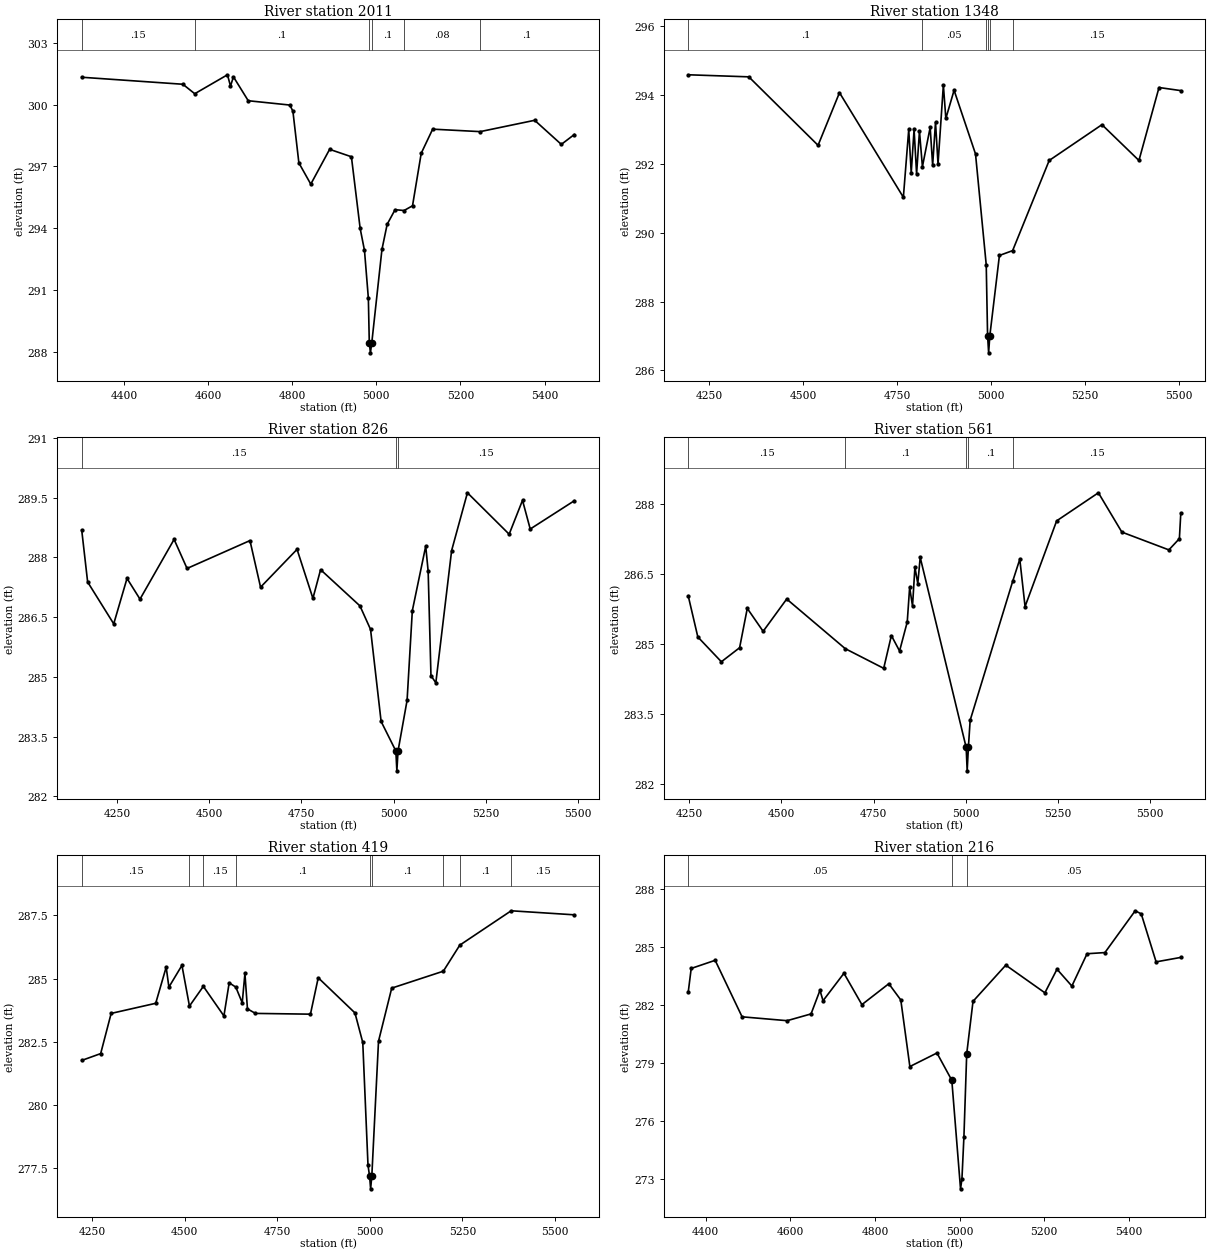
Type RM Length L Ch R = 1 ,2011    ,663,663,663
BEGIN DESCRIPTION:
WOLF PEN CREEK TRIB B 4.0
END DESCRIPTION:
XS GIS Cut Line= 3
      3559457.79     10212315.95       3559062.8     10211907.94
      3558481.25     10211747.36
#Sta/Elev= 30
  4299.6  301.33  4540.1  300.99  4568.3  300.53  4646.1  301.45  4653.3   300.9
  4660.3  301.35  4695.5  300.19  4794.5  299.98  4801.7  299.68  4815.9  297.17
  4844.2  296.14    4889  297.83  4940.8  297.47  4961.6  293.99  4971.9  292.92
  4981.1   290.6  4983.3  288.45    4986  287.95  4989.3  288.45  5013.4  292.97
  5025.8  294.19  5044.6   294.9    5066  294.86  5086.1  295.09  5106.8  297.64
    5134  298.81    5247  298.69  5376.5  299.24  5439.9  298.07  5470.8  298.55
#Mann= 6 ,-1 , 0
  4299.6     .15       0  4568.3      .1       0  4983.3     .07       0
  4989.3      .1       0    5066     .08       0    5247      .1       0
Bank Sta=4983.3,4989.3
XS Rating Curve= 0 ,0
Exp/Cntr=0.3,0.1

Type RM Length L Ch R = 1 ,1348    ,522,522,522
BEGIN DESCRIPTION:
WOLF PEN CREEK TRIB B 3.0
END DESCRIPTION:
XS GIS Cut Line= 3
      3559629.34     10211871.85      3558942.11     10211274.98
      3558567.96     10211133.61
#Sta/Elev= 30
  4194.3  294.59  4355.5  294.53  4539.7  292.54  4596.7  294.07  4766.6  291.03
  4780.9     293  4787.5  291.74  4795.1     293  4801.8  291.71  4809.4  292.95
  4817.3  291.92  4837.9  293.06  4844.5  291.96  4852.1  293.21  4858.8     292
    4873  294.29  4879.6  293.32  4901.5  294.14  4958.5  292.29    4987  289.07
  4990.6  287.01  4993.4  286.51  4996.6  287.01  5022.1  289.34  5057.2  289.48
  5154.5   292.1  5294.8  293.14  5393.2   292.1  5446.6  294.22  5504.5  294.13
#Mann= 6 ,-1 , 0
  4194.3      .1       0  4817.3     .05       0    4987      .1       0
  4990.6     .07       0  4996.6      .1       0  5057.2     .15       0
Bank Sta=4990.6,4996.6
XS Rating Curve= 0 ,0
Exp/Cntr=0.3,0.1

Type RM Length L Ch R = 1 ,826     ,265,265,265
BEGIN DESCRIPTION:
WOLF PEN CREEK TRIB B 2.2
END DESCRIPTION:
XS GIS Cut Line= 3
      3559927.93     10211698.23      3559374.05       10211034.
      3559016.94     10210728.37
#Sta/Elev= 30
  4154.9  288.68  4170.9  287.38  4241.6  286.33  4277.6  287.47  4312.8  286.95
  4405.2  288.45  4440.3  287.72  4610.8  288.42  4639.5  287.25  4738.4   288.2
  4781.4  286.97  4802.2  287.69  4908.9  286.78  4937.6  286.19  4966.2  283.88
  5006.1  283.14  5008.9  282.64  5012.1  283.14  5036.6  284.41  5050.8  286.66
  5087.1  288.28  5093.7  287.65  5101.3  285.03  5114.5  284.85  5157.3  288.17
  5200.1  289.62  5313.2  288.58  5349.4  289.43  5370.3  288.71  5489.8  289.42
#Mann= 3 ,-1 , 0
  4154.9     .15       0  5006.1     .07       0  5012.1     .15       0
Bank Sta=5006.1,5012.1
XS Rating Curve= 0 ,0
Exp/Cntr=0.3,0.1

Type RM Length L Ch R = 1 ,561     ,142,142,142
BEGIN DESCRIPTION:
WOLF PEN CREEK TRIB B 2.1
END DESCRIPTION:
XS GIS Cut Line= 3
      3560117.98     10211551.67      3559564.14      10210887.5
      3559206.97     10210581.82
#Sta/Elev= 30
  4247.8  286.03  4273.9  285.15  4337.7  284.62  4387.1  284.92  4407.9  285.76
  4450.9  285.27  4514.7  285.96  4673.4   284.9  4777.6  284.48  4798.4  285.18
  4820.6  284.85  4841.4  285.47  4847.9  286.21  4855.7  285.81  4862.2  286.64
    4870  286.29  4876.5  286.85  5001.1  282.79  5003.8  282.29  5007.1  282.79
  5011.9  283.37  5127.2  286.34  5146.4  286.81  5160.7   285.8  5246.3  287.63
  5359.4  288.23    5423  287.39  5550.4  287.01  5578.9  287.25  5582.7  287.79
#Mann= 5 ,-1 , 0
  4247.8     .15       0  4673.4      .1       0  5001.1     .07       0
  5007.1      .1       0  5127.2     .15       0
Bank Sta=5001.1,5007.1
XS Rating Curve= 0 ,0
Exp/Cntr=0.3,0.1

Type RM Length L Ch R = 1 ,419     ,203,203,203
BEGIN DESCRIPTION:
WOLF PEN CREEK TRIB B 2.0
END DESCRIPTION:
XS GIS Cut Line= 3
      3560281.55     10211464.47      3559678.39     10210822.12
      3559371.44     10210495.58
#Sta/Elev= 30
  4222.6  281.76  4273.7  282.03    4302  283.62  4422.2  284.02  4450.5  285.45
  4457.8  284.66    4493  285.52  4513.3  283.91  4550.8  284.69  4606.3  283.52
  4620.5  284.83  4638.4  284.66  4655.7  284.04    4663   285.2  4669.8   283.8
  4691.3  283.62  4839.8  283.59  4860.8  285.03  4959.9  283.64    4981  282.47
  4995.1  277.62  4999.4  277.18  5002.2  276.68  5005.4  277.18  5023.5  282.52
  5059.1  284.62  5198.4  285.29  5242.8  286.32  5381.5  287.68  5551.9  287.52
#Mann= 9 ,-1 , 0
  4222.6     .15       0  4513.3      .1       0  4550.8     .15       0
  4638.4      .1       0  4999.4     .07       0  5005.4      .1       0
  5198.4     .15       0  5242.8      .1       0  5381.5     .15       0
Bank Sta=4999.4,5005.4
XS Rating Curve= 0 ,0
Exp/Cntr=0.3,0.1

Type RM Length L Ch R = 1 ,216     ,0,0,0
BEGIN DESCRIPTION:
WOLF PEN CREEK TRIB B 1.0
END DESCRIPTION:
XS GIS Cut Line= 3
      3560350.87     10211223.01      3559957.43     10210811.05
      3559502.57     10210429.11
#Sta/Elev= 30
    4359  282.63  4366.1  283.87  4422.7  284.29  4486.3  281.37  4592.6  281.17
  4649.2  281.52  4670.3  282.74  4677.5   282.2  4726.9  283.62  4769.3     282
  4832.9  283.08  4861.2  282.24  4882.6   278.8  4946.6   279.5  4981.7  278.09
  5002.3  272.48  5005.6  272.98  5010.3  275.16  5016.9  279.46  5031.8  282.17
  5109.2  284.04  5201.6  282.61  5230.2  283.83  5265.3  282.96  5301.2  284.63
  5343.4  284.69  5414.9  286.85  5429.2  286.69  5464.3  284.21  5522.6  284.44
#Mann= 3 , 0 , 0
    4359     .05       0  4981.7     .03       0  5016.9     .05       0
Bank Sta=4981.7,5016.9
XS Rating Curve= 0 ,0
Exp/Cntr=0.3,0.1

Chan Stop Cuts=-1
Use User Specified Reach Order=0
Composite Channel Slope=5