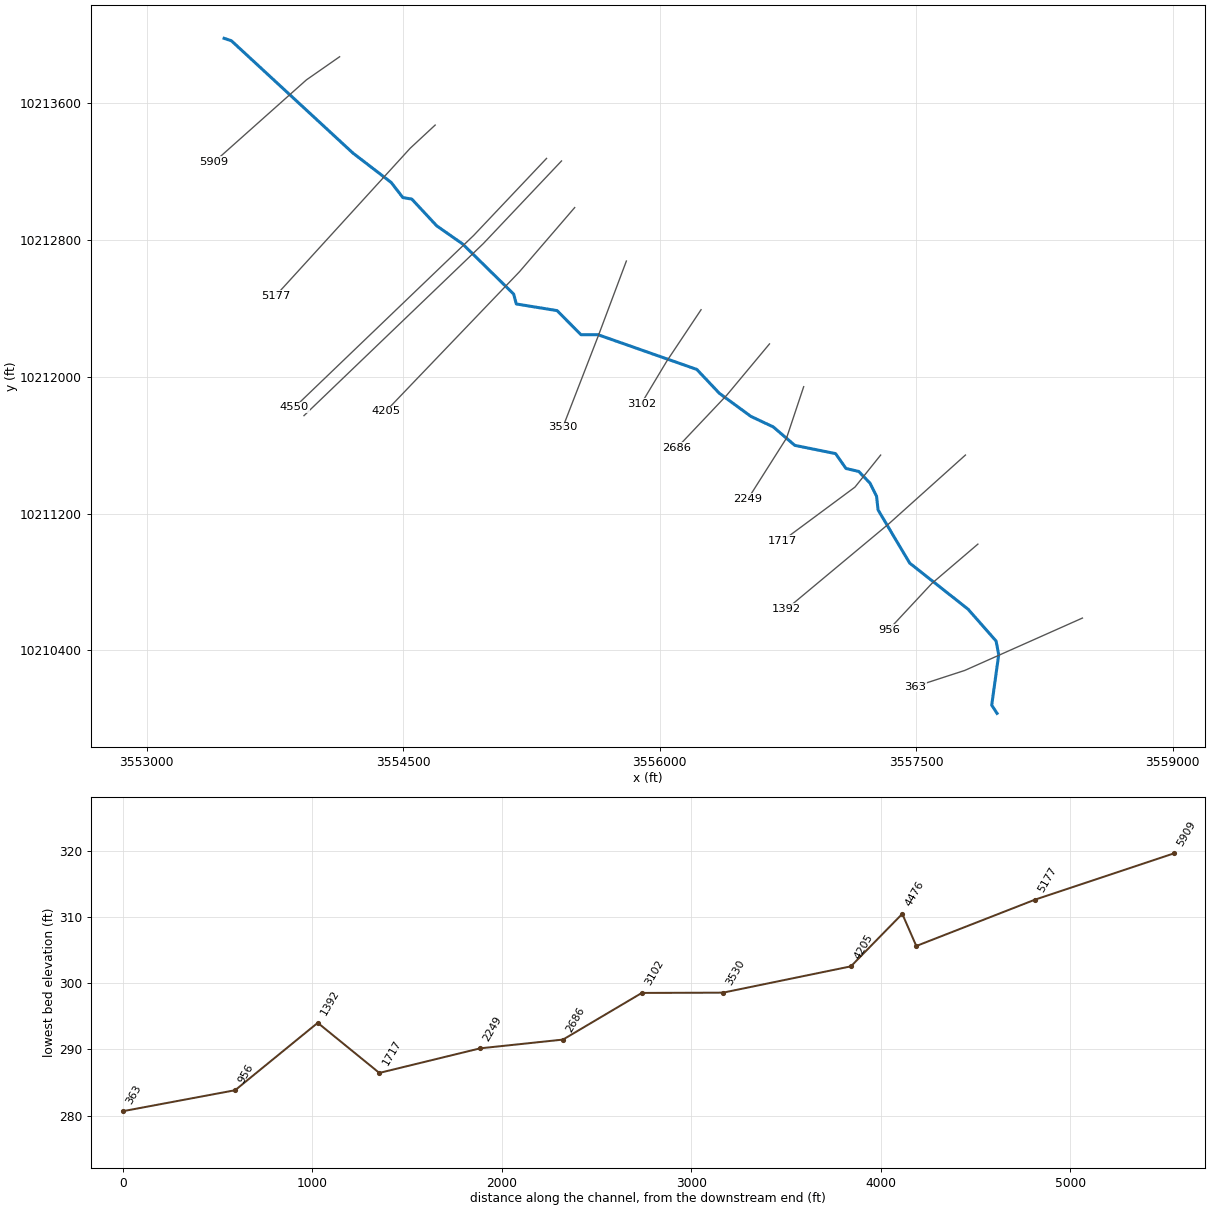
--- WOLF PEN CREEK TRIB C.prj (project) ---

Proj Title=WOLF PEN CREEK TRIB C Base Level Engineering
Current Plan=p01
Default Exp/Contr=0.3,0.1
English Units
Geom File=g01
Flow File=f01
Plan File=p01
Y Axis Title=Elevation
X Axis Title(PF)=Main Channel Distance
X Axis Title(XS)=Station
BEGIN DESCRIPTION:
WOLF PEN CREEK TRIB C
END DESCRIPTION:
DSS Export Rating Curves= 0
DSS Export Rating Curve Sorted= 0
DSS Export Volume Flow Curves= 0
DXF OffsetX= 0
DXF OffsetY= 0
DXF ScaleX= 1
DXF ScaleY= 10

--- WOLF PEN CREEK TRIB C.p01 (plan) ---

Plan Title=Multiple Run
Short Identifier=Multiple
Geom File=g01
Flow File=f01
Subcritical Flow
K Sum by GR= 0
Std Step Tol= 0.01
Critical Tol= 0.01
Num of Std Step Trials= 20
Max Error Tol= 0.3
Flow Tol Ratio= 0.001
Split Flow NTrial= 30
Split Flow Tol= 0.02
Split Flow Ratio= 0.02
Log Output Level= 0
Friction Slope Method= 1
Unsteady Friction Slope Method= 2
Unsteady Bridges Friction Slope Method= 1
Parabolic Critical Depth
Global Vel Dist=  1 , 1 , 1
Global Log Level= 0
CheckData=True
Encroach Param= -1, 0, 0, 0
BEGIN DESCRIPTION:
Multiple Run
END DESCRIPTION:

--- WOLF PEN CREEK TRIB C.f01 (steady flow) ---

Flow Title=Multiple
Number of Profiles=7
Profile Names=10-year,25-year,50-year,1pct_min,100-year,1pct_plu,500-year
River Rch & RM= WOLF PEN CREEK T,Reach-1,5909
     404     534     637     557     754    1019    1059
Boundary for River Rch & Prof#=WOLF PEN CREEK T,Reach-1,1
Up Type=0
Dn Type=3
Dn Slope=0.005
Boundary for River Rch & Prof#=WOLF PEN CREEK T,Reach-1,2
Up Type=0
Dn Type=3
Dn Slope=0.005
Boundary for River Rch & Prof#=WOLF PEN CREEK T,Reach-1,3
Up Type=0
Dn Type=3
Dn Slope=0.005
Boundary for River Rch & Prof#=WOLF PEN CREEK T,Reach-1,4
Up Type=0
Dn Type=3
Dn Slope=0.005
Boundary for River Rch & Prof#=WOLF PEN CREEK T,Reach-1,5
Up Type=0
Dn Type=3
Dn Slope=0.005
Boundary for River Rch & Prof#=WOLF PEN CREEK T,Reach-1,6
Up Type=0
Dn Type=3
Dn Slope=0.005
Boundary for River Rch & Prof#=WOLF PEN CREEK T,Reach-1,7
Up Type=0
Dn Type=3
Dn Slope=0.005

--- WOLF PEN CREEK TRIB C.g01 (geometry) ---

Geom Title=Existing Conditions
Program Version=4.10

River Reach=WOLF PEN CREEK T,Reach-1
Reach XY= 30
      3553453.13     10213978.48      3553495.91     10213964.13
      3554205.98     10213307.88      3554430.16     10213135.58
      3554498.52     10213047.23       3554550.6     10213038.54
        3554696.     10212882.29      3554847.91     10212775.96
      3555146.21     10212483.01      3555161.65     10212425.32
      3555400.37     10212386.26      3555539.65     10212245.56
      3555639.14     10212245.56      3556217.26     10212042.43
      3556348.77     10211903.11      3556533.67     10211767.69
      3556663.88      10211706.5      3556790.18     10211598.42
      3557028.46     10211550.25      3557089.66     10211463.01
      3557163.88     10211446.08      3557230.28     10211377.07
      3557268.04     10211301.55      3557277.16     10211220.82
      3557461.81     10210910.16      3557803.26     10210640.54
       3557967.1     10210454.28      3557982.43     10210374.48
       3557941.6     10210079.38      3557972.73     10210031.26

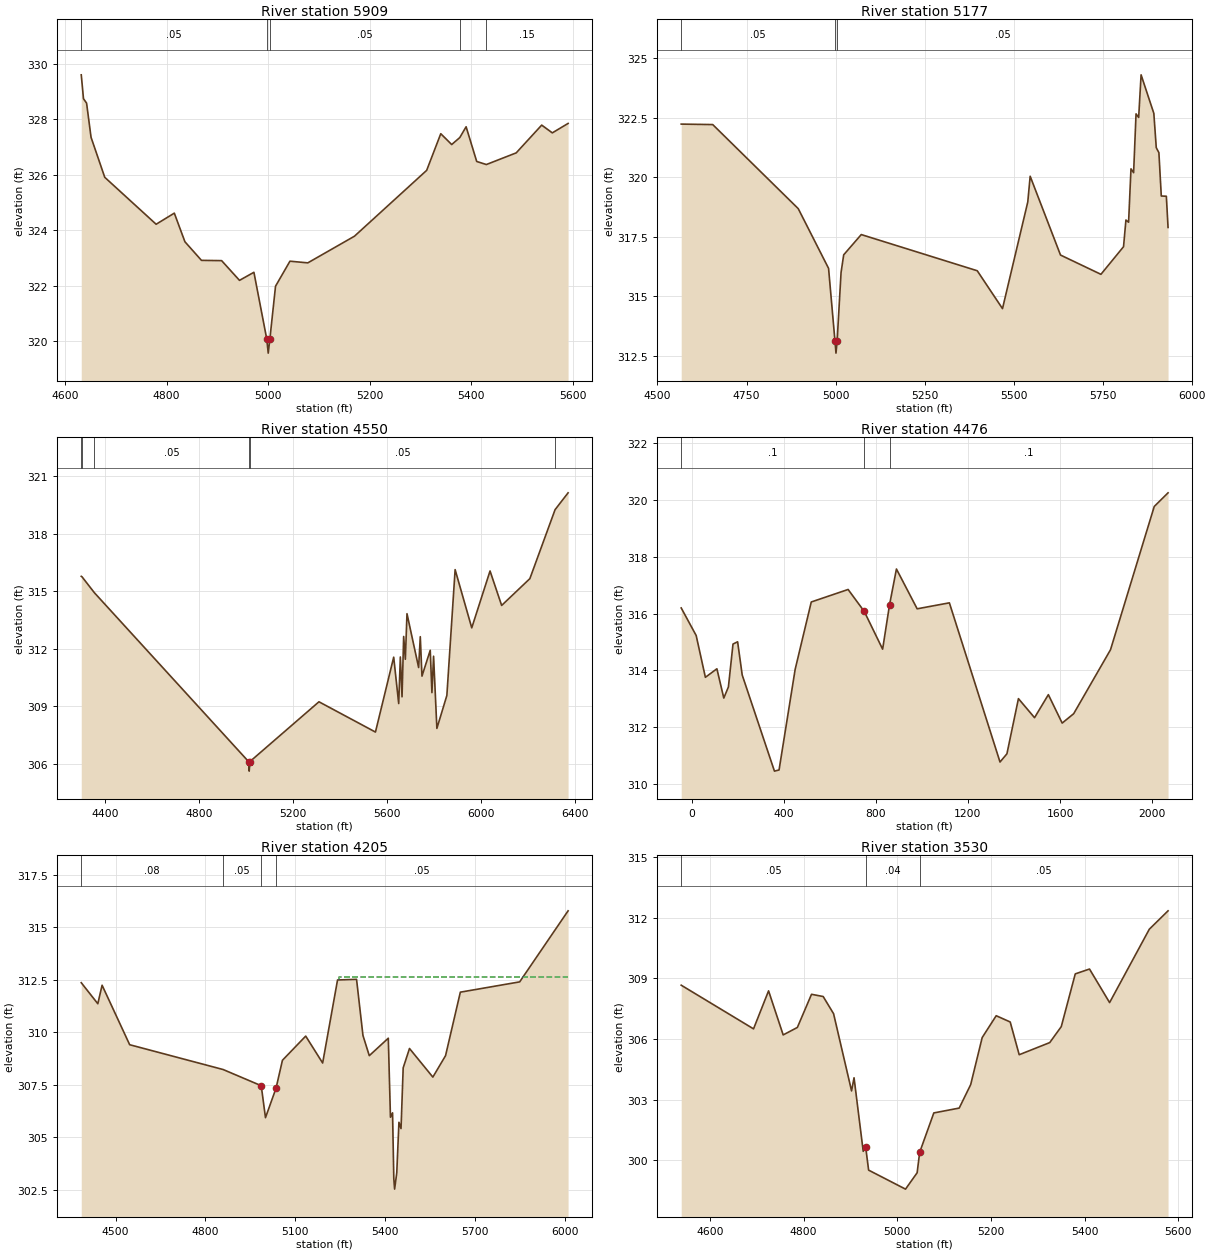
Type RM Length L Ch R = 1 ,5909    ,732,732,732
BEGIN DESCRIPTION:
WOLF PEN CREEK TRIB C 12.0
END DESCRIPTION:
XS GIS Cut Line= 3
      3554128.44     10213870.77      3553934.13     10213735.41
      3553394.84     10213255.07
#Sta/Elev= 30
  4631.9   329.6  4636.3  328.74  4642.4  328.58  4651.2  327.35  4678.2  325.91
  4779.4  324.22  4815.2  324.62  4836.1  323.59  4868.7  322.92  4908.4  322.91
  4943.6   322.2    4972  322.49  4997.4  320.08  5000.2  319.58  5003.4  320.08
  5014.6  321.99    5043  322.89  5078.2  322.83  5170.1  323.79  5312.3  326.16
  5340.1  327.48  5361.6  327.09  5377.5  327.34    5390  327.73  5410.9  326.48
  5429.9  326.37  5488.7  326.79  5538.9  327.79  5559.8  327.51  5590.9  327.85
#Mann= 5 ,-1 , 0
  4631.9     .05       0  4997.4     .04       0  5003.4     .05       0
  5377.5      .1       0  5429.9     .15       0
Bank Sta=4997.4,5003.4
XS Rating Curve= 0 ,0
Exp/Cntr=0.3,0.1

Type RM Length L Ch R = 1 ,5177    ,627,627,627
BEGIN DESCRIPTION:
WOLF PEN CREEK TRIB C 11.0
END DESCRIPTION:
XS GIS Cut Line= 3
      3554687.12      10213471.3      3554541.31     10213335.91
      3553754.17     10212472.82
#Sta/Elev= 30
  4566.6  322.23  4655.1  322.21  4895.2  318.68  4980.4  316.17  4998.4  313.11
  5001.2  312.61  5004.4  313.11  5015.5     316  5022.9  316.74  5072.2  317.59
  5397.9  316.07  5468.8  314.48  5539.8  318.96  5546.5  320.04  5631.7  316.73
  5745.2  315.92  5808.7  317.08  5815.4   318.2  5822.9  318.11  5829.6  320.35
    5837  320.19  5843.8  322.66  5851.2  322.51    5858   324.3  5893.8  322.68
  5900.6  321.24    5908  321.03  5914.7  319.21  5928.9   319.2  5933.7  317.89
#Mann= 3 ,-1 , 0
  4566.6     .05       0  4998.4     .04       0  5004.4     .05       0
Bank Sta=4998.4,5004.4
XS Rating Curve= 0 ,0
Exp/Cntr=0.3,0.1

Type RM Length L Ch R = 1 ,4550    ,74,74,74
BEGIN DESCRIPTION:
WOLF PEN CREEK TRIB C 10.0
END DESCRIPTION:
XS GIS Cut Line= 3
      3555338.57     10213276.43      3554911.85     10212825.52
      3553863.78     10211819.91
#Sta/Elev= 30
  4297.9  315.78  4301.5  315.75  4353.4  314.93  5010.3  306.11  5013.1  305.61
  5016.3  306.11  5310.2  309.23  5550.8  307.65  5628.5  311.56  5649.8  309.14
  5656.8  311.57    5664  309.49  5670.9  312.64  5678.1  311.45  5685.1  313.83
  5734.7  311.02  5741.7  312.63  5748.9  310.57  5784.1  311.92  5791.3  309.71
  5798.3  311.61  5812.4  307.84  5854.9  309.56  5890.1  316.13  5960.9  313.09
  6038.8  316.06  6088.2  314.26  6208.4  315.66  6315.7  319.26  6371.2  320.14
#Mann= 6 ,-1 , 0
  4297.9     .15       0  4301.5      .1       0  4353.4     .05       0
  5010.3     .04       0  5016.3     .05       0  6315.7     .08       0
Bank Sta=5010.3,5016.3
XS Rating Curve= 0 ,0
Exp/Cntr=0.3,0.1

Type RM Length L Ch R = 1 ,4476    ,271,271,271
BEGIN DESCRIPTION:
WOLF PEN CREEK TRIB C 10.1
END DESCRIPTION:
XS GIS Cut Line= 4
3555425.9603508110213261.4150639      3555395.03     10213228.73
      3554968.28     10212777.77      3553920.17     10211772.13
#Sta/Elev= 30
     -45   316.2   19.99  315.23   59.97  313.76  109.94  314.06  139.92  313.03
  159.91  313.42   179.9  314.93  199.89  315.01  219.88  313.84   359.8  310.46
  379.79   310.5  449.76  314.04  519.72  316.41  679.63  316.85  749.59  316.08
  829.55  314.75  859.53  316.31  889.52  317.57  979.47  316.17 1119.39  316.38
 1339.27  310.78 1369.26  311.07 1419.23  313.01 1489.19  312.34 1549.16  313.15
 1609.12  312.15  1659.1  312.48 1819.01  314.73 2008.91  319.77 2068.87  320.25
#Mann= 3 , 0 , 0
     -45      .1       0  749.59     .03       0  859.53      .1       0
Bank Sta=749.59,859.53
XS Rating Curve= 0 ,0
Exp/Cntr=0.3,0.1

Type RM Length L Ch R = 1 ,4205    ,675,675,675
BEGIN DESCRIPTION:
WOLF PEN CREEK TRIB C 9.0
END DESCRIPTION:
XS GIS Cut Line= 3
      3555502.97     10212988.81       3555180.2     10212613.69
      3554397.97     10211797.05
#Sta/Elev= 30
  4385.4  312.36  4440.7  311.36    4455  312.24  4547.1  309.41  4859.1  308.23
  4986.4  307.46  5000.6  305.94  5035.8  307.34  5057.2  308.67  5134.9  309.82
  5191.5  308.54  5241.2  312.49  5304.7  312.52  5326.1  309.85  5347.2  308.89
  5410.7  309.72  5417.9  305.96  5424.9  306.17  5429.1  303.04  5431.8  302.54
    5439  303.32  5446.2  305.72  5453.2  305.42  5460.4  308.31  5481.5  309.23
  5559.5  307.87  5601.9  308.89  5651.3  311.91  5849.4   312.4  6011.1  315.78
#Mann= 4 ,-1 , 0
  4385.4     .08       0  4859.1     .05       0  4986.4     .04       0
  5035.8     .05       0
#XS Ineff= 2 , 0
                         5247.18          312.63
Permanent Ineff=
       F       F
Bank Sta=4986.4,5035.8
XS Rating Curve= 0 ,0
Exp/Cntr=0.3,0.1

Type RM Length L Ch R = 1 ,3530    ,428,428,428
BEGIN DESCRIPTION:
WOLF PEN CREEK TRIB C 8.0
END DESCRIPTION:
XS GIS Cut Line= 3
      3555805.22     10212676.23      3555642.11     10212241.64
       3555434.2     10211705.32
#Sta/Elev= 30
  4538.6  308.66    4693   306.5  4725.1  308.38  4756.3   306.2  4786.6  306.57
  4816.8  308.21  4841.7   308.1  4863.9  307.25  4902.3  303.43  4907.6  304.08
  4927.2  300.44  4932.5  300.64  4938.7  299.51  5017.5  298.57  5042.3  299.38
  5047.7  300.39  5077.9  302.34  5132.1  302.58  5156.6  303.74  5181.2  306.07
  5211.1  307.15    5241  306.84  5260.2  305.22  5325.4  305.82    5350  306.61
  5379.9  309.22  5410.3  309.46  5453.2   307.8    5538  311.43    5578  312.34
#Mann= 3 , 0 , 0
  4538.6     .05       0  4932.5     .04       0  5047.7     .05       0
Bank Sta=4932.5,5047.7
XS Rating Curve= 0 ,0
Exp/Cntr=0.3,0.1

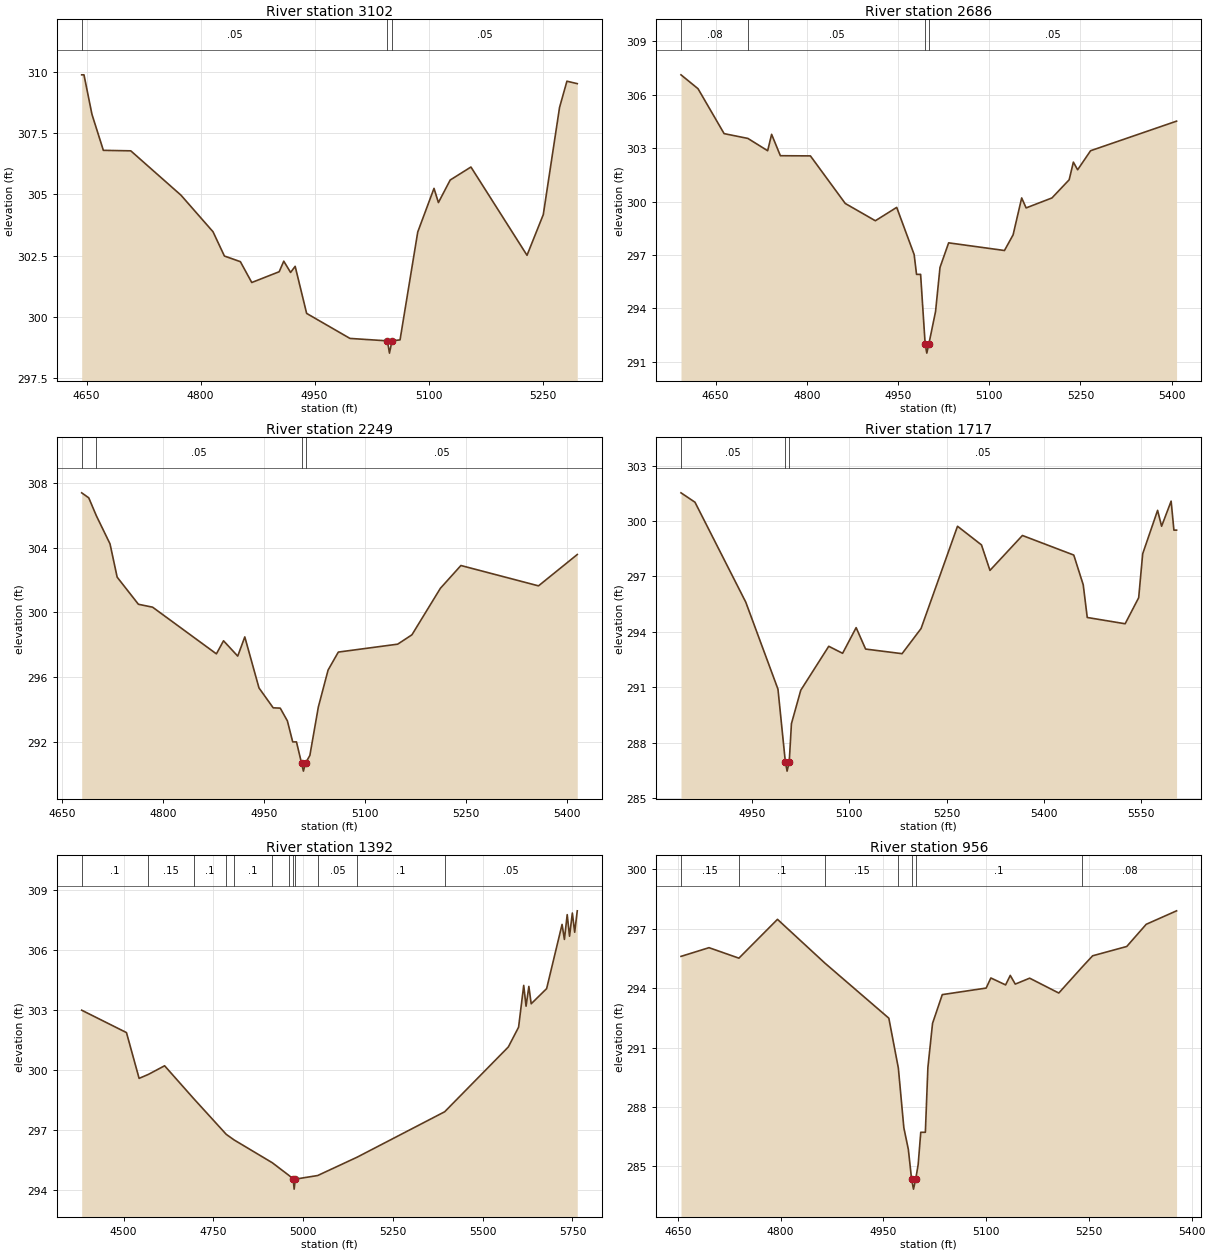
Type RM Length L Ch R = 1 ,3102    ,416,416,416
BEGIN DESCRIPTION:
WOLF PEN CREEK TRIB C 7.0
END DESCRIPTION:
XS GIS Cut Line= 3
       3556242.1     10212391.64      3556042.11     10212091.64
      3555892.11     10211841.64
#Sta/Elev= 30
  4643.5  309.88  4646.5  309.88    4657  308.27    4672   306.8  4708.1  306.78
  4774.2  304.97  4816.3  303.48  4831.3  302.49  4852.3  302.26  4867.3  301.41
  4903.4  301.85  4909.4  302.28  4918.4  301.82  4924.4  302.07  4939.5  300.15
  4996.5  299.13  5045.8  299.03  5048.5  298.53  5051.8  299.03  5062.4  299.07
  5085.7  303.47  5107.1  305.25  5112.9  304.67  5128.4  305.59  5155.7  306.12
  5229.5  302.52  5250.9  304.18  5272.3  308.55    5282  309.62  5295.6  309.52
#Mann= 3 ,-1 , 0
  4643.5     .05       0  5045.8     .04       0  5051.8     .05       0
Bank Sta=5045.8,5051.8
XS Rating Curve= 0 ,0
Exp/Cntr=0.3,0.1

Type RM Length L Ch R = 1 ,2686    ,437,437,437
BEGIN DESCRIPTION:
WOLF PEN CREEK TRIB C 6.0
END DESCRIPTION:
XS GIS Cut Line= 3
       3556642.1     10212191.64      3556392.11     10211891.64
      3556100.33     10211583.47
#Sta/Elev= 30
  4593.2  307.11  4621.2  306.33  4664.1  303.81  4703.2  303.54  4735.7  302.85
  4742.2  303.77  4756.6  302.57    4806  302.56  4863.3  299.89  4912.8  298.92
  4947.9  299.67  4976.6  297.02  4980.5  295.91  4987.2  295.91  4994.7  291.99
  4997.4  291.49  5000.7  291.99  5011.8  293.83  5019.1   296.3  5033.3  297.68
  5125.1  297.25  5139.3  298.13  5153.4   300.2  5160.7  299.64  5203.2   300.2
  5231.5  301.22  5238.4  302.21  5245.4  301.78  5266.7  302.85  5408.1  304.51
#Mann= 4 ,-1 , 0
  4593.2     .08       0  4703.2     .05       0  4994.7     .04       0
  5000.7     .05       0
Bank Sta=4994.7,5000.7
XS Rating Curve= 0 ,0
Exp/Cntr=0.3,0.1

Type RM Length L Ch R = 1 ,2249    ,532,532,532
BEGIN DESCRIPTION:
WOLF PEN CREEK TRIB C 5.0
END DESCRIPTION:
XS GIS Cut Line= 3
       3556842.1     10211941.61      3556742.11     10211641.64
      3556517.05     10211286.67
#Sta/Elev= 30
  4678.9   307.4  4689.4  307.09  4700.7  305.98    4721  304.24  4731.6  302.18
  4763.2   300.5  4784.3  300.32  4879.1  297.43  4889.7  298.24  4910.8  297.29
  4921.3  298.48  4942.4  295.32  4963.5  294.09    4974  294.07  4984.6  293.28
  4992.5  291.98  4998.1  291.98  5005.6  290.67  5008.4  290.17  5011.6  290.67
    5018  291.14  5030.6  294.14  5045.1  296.43  5060.3  297.54  5148.5  298.03
  5169.7  298.61    5212  301.49  5242.5   302.9  5357.8  301.64  5415.4  303.58
#Mann= 4 ,-1 , 0
  4678.9     .08       0  4700.7     .05       0  5005.6     .04       0
  5011.6     .05       0
Bank Sta=5005.6,5011.6
XS Rating Curve= 0 ,0
Exp/Cntr=0.3,0.1

Type RM Length L Ch R = 1 ,1717    ,325,325,325
BEGIN DESCRIPTION:
WOLF PEN CREEK TRIB C 4.0
END DESCRIPTION:
XS GIS Cut Line= 3
      3557292.11     10211541.65      3557142.01     10211354.32
       3556720.1     10211041.79
#Sta/Elev= 30
    4840  301.53  4861.6  301.02    4940  295.61  4989.7   290.9  5001.1  286.96
  5003.8  286.46  5007.1  286.96  5010.5  289.03  5024.9  290.84  5068.1  293.22
  5089.5  292.84  5110.4  294.23    5125  293.07  5181.3  292.82  5210.6  294.18
  5266.9  299.72  5303.9  298.71    5317  297.33  5367.1  299.22  5446.4  298.16
    5461  296.55  5467.2  294.78  5525.7  294.44  5546.6  295.85  5552.8  298.23
  5575.8  300.58    5582  299.72  5596.7  301.08    5601  299.51  5605.1  299.51
#Mann= 3 ,-1 , 0
    4840     .05       0  5001.1     .04       0  5007.1     .05       0
Bank Sta=5001.1,5007.1
XS Rating Curve= 0 ,0
Exp/Cntr=0.3,0.1

Type RM Length L Ch R = 1 ,1392    ,436,436,436
BEGIN DESCRIPTION:
WOLF PEN CREEK TRIB C 3.0
END DESCRIPTION:
XS GIS Cut Line= 3
      3557787.85     10211541.83      3557342.11     10211141.64
      3556742.07     10210641.61
#Sta/Elev= 30
  4383.3  302.97    4508  301.85  4543.2  299.56  4569.2  299.76  4614.2  300.19
  4696.1  298.53  4785.9  296.76  4807.8  296.48  4914.1  295.34  4961.6  294.69
  4972.2  294.52    4975  294.02  4978.2  294.52  5040.5   294.7  5150.6  295.62
  5394.2  297.89  5571.4  301.13    5600  302.12  5614.3  304.21  5620.8  303.17
  5628.6  304.16  5635.1  303.29  5678.1  304.05  5721.1  307.26  5727.6  306.51
  5735.4  307.75  5741.9  306.67  5749.7  307.83  5756.2  306.87  5763.4  307.94
#Mann= 12 ,-1 , 0
  4383.3      .1       0  4569.2     .15       0  4696.1      .1       0
  4785.9     .05       0  4807.8      .1       0  4914.1     .05       0
  4961.6      .1       0  4972.2     .07       0  4978.2      .1       0
  5040.5     .05       0  5150.6      .1       0  5394.2     .05       0
Bank Sta=4972.2,4978.2
XS Rating Curve= 0 ,0
Exp/Cntr=0.3,0.1

Type RM Length L Ch R = 1 ,956     ,593,593,593
BEGIN DESCRIPTION:
WOLF PEN CREEK TRIB C 2.0
END DESCRIPTION:
XS GIS Cut Line= 3
      3557860.75     10211020.98      3557592.11     10210791.64
      3557339.89     10210520.95
#Sta/Elev= 30
  4654.8   295.6  4695.7  296.04  4739.3  295.51  4795.6  297.47  4864.8  295.26
  4958.1  292.48    4972  289.96    4980  286.95  4986.6  285.85  4991.3  284.35
  4994.1  283.85  4997.3  284.35  5000.9  285.09  5004.7  286.72  5011.4  286.72
  5015.1  289.99  5021.9  292.22  5036.1  293.67  5100.1     294    5107  294.51
  5128.5  294.16  5135.3  294.64  5142.6   294.2  5163.6   294.5  5206.1  293.75
  5240.7  295.08  5255.5  295.63  5305.3   296.1  5333.7  297.22    5378   297.9
#Mann= 7 ,-1 , 0
  4654.8     .15       0  4739.3      .1       0  4864.8     .15       0
    4972      .1       0  4991.3     .07       0  4997.3      .1       0
  5240.7     .08       0
Bank Sta=4991.3,4997.3
XS Rating Curve= 0 ,0
Exp/Cntr=0.3,0.1

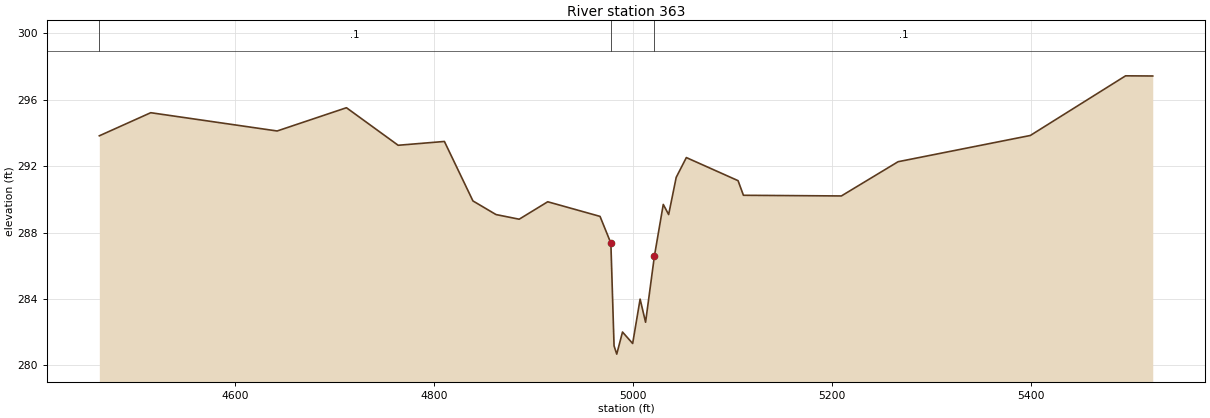
Type RM Length L Ch R = 1 ,363     ,0,0,0
BEGIN DESCRIPTION:
WOLF PEN CREEK TRIB C 1.0
END DESCRIPTION:
XS GIS Cut Line= 3
      3558472.04     10210588.66      3557784.05     10210282.37
      3557492.87     10210187.61
#Sta/Elev= 30
  4463.3  293.82    4515  295.21  4642.1  294.11  4711.8  295.51  4763.8  293.25
  4810.3  293.48    4839   289.9  4862.2  289.08  4885.5   288.8  4914.2  289.85
  4966.8  288.97  4977.7  287.36  4980.9  281.18  4983.6  280.68  4989.4  282.01
  4999.6  281.32  5007.1  283.99  5012.6   282.6  5021.5  286.59  5030.4  289.69
  5035.8  289.08  5043.4  291.32  5053.6  292.51  5105.6  291.12    5111  290.24
  5209.5   290.2  5266.5  292.26  5399.5  293.84  5495.3  297.43  5522.6  297.42
#Mann= 3 , 0 , 0
  4463.3      .1       0  4977.7     .05       0  5021.5      .1       0
Bank Sta=4977.7,5021.5
XS Rating Curve= 0 ,0
Exp/Cntr=0.3,0.1

Chan Stop Cuts=-1
Use User Specified Reach Order=0
Composite Channel Slope=5