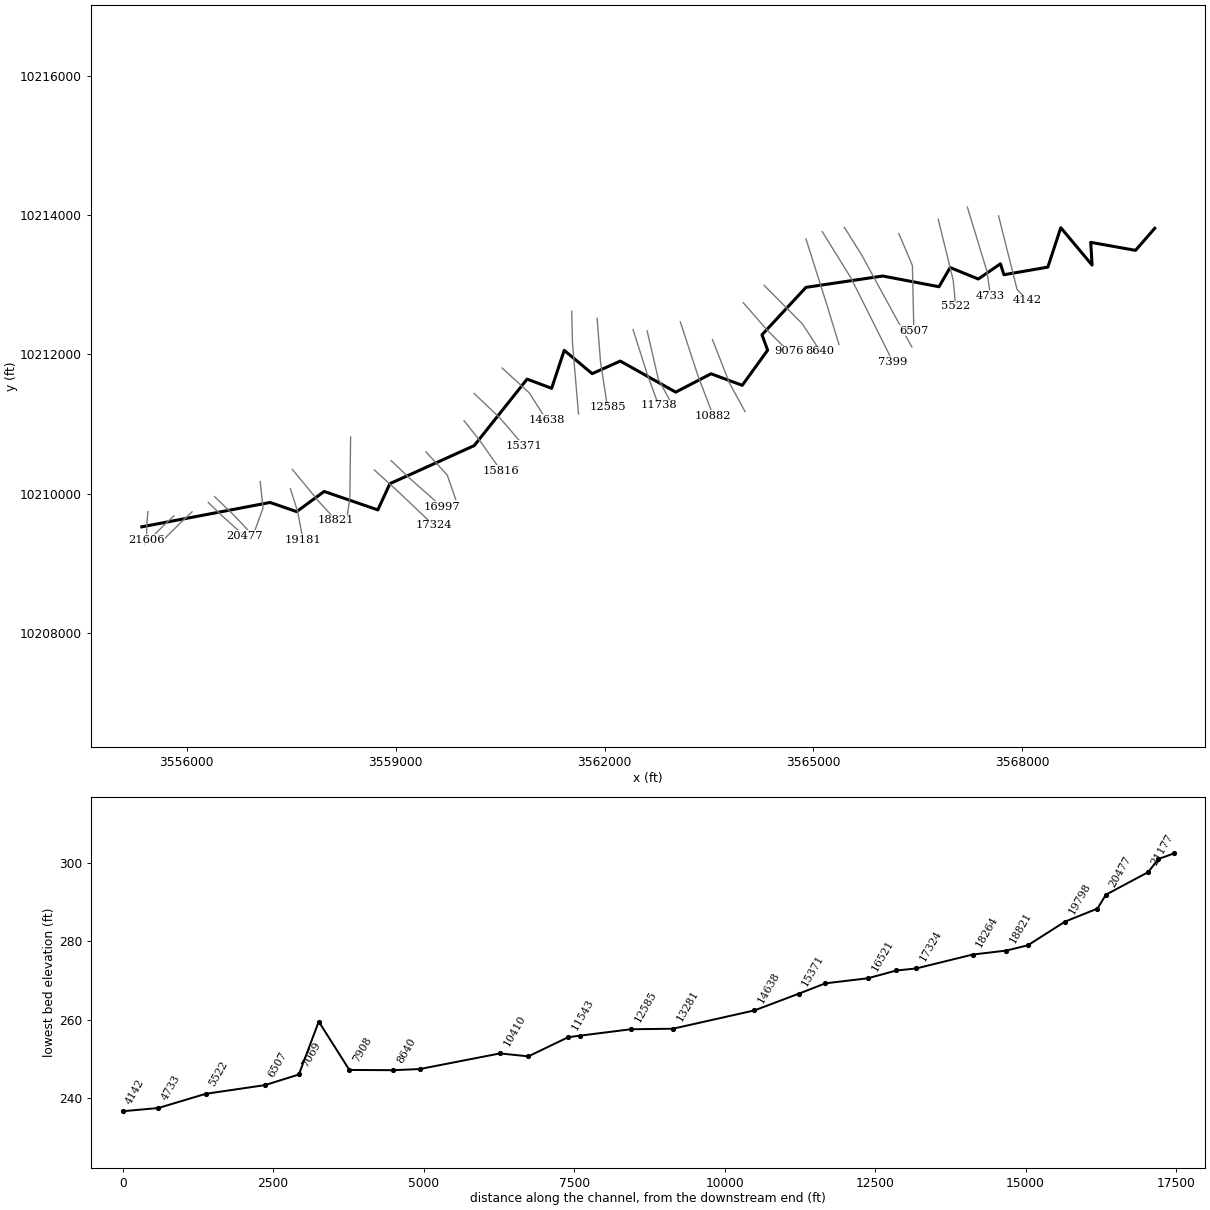
--- WOLF PEN CREEK.prj (project) ---

Proj Title=WOLF PEN CREEK Base Level Engineering
Current Plan=p01
Default Exp/Contr=0.3,0.1
English Units
Geom File=g01
Flow File=f01
Plan File=p01
BEGIN DESCRIPTION:
WOLF PEN CREEK
END DESCRIPTION:

--- WOLF PEN CREEK.p01 (plan) ---

Plan Title=Multiple Run
Short Identifier=Multiple
Geom File=g01
Flow File=f01
Subcritical Flow
K Sum by GR= 0
Std Step Tol= 0.01
Critical Tol= 0.01
Num of Std Step Trials= 20
Max Error Tol= 0.3
Flow Tol Ratio= 0.001
Split Flow NTrial= 30
Split Flow Tol= 0.02
Split Flow Ratio= 0.02
Log Output Level= 0
Friction Slope Method= 1
Unsteady Friction Slope Method= 2
Unsteady Bridges Friction Slope Method= 1
Parabolic Critical Depth
Global Vel Dist=  1 , 1 , 1
Global Log Level= 0
CheckData=True
Encroach Param= -1, 0, 0, 0
BEGIN DESCRIPTION:
Multiple Run
END DESCRIPTION:

--- WOLF PEN CREEK.f01 (steady flow) ---

Flow Title=Multiple
Number of Profiles=7
Profile Names=10-year,25-year,50-year,1pct_min,100-year,1pct_plu,500-year
River Rch & RM= WOLF PEN CREEK,Reach-1,21606
     301     393     465     405     548     741     761
River Rch & RM= WOLF PEN CREEK,Reach-1,18264
     591     797     964     855    1156    1563    1666
River Rch & RM= WOLF PEN CREEK,Reach-1,15816
     770    1053    1286    1151    1556    2104    2283
River Rch & RM= WOLF PEN CREEK,Reach-1,13281
    1030    1421    1745    1566    2118    2865    3131
River Rch & RM= WOLF PEN CREEK,Reach-1,7069
    1138    1579    1948    1755    2374    3210    3538
Boundary for River Rch & Prof#=WOLF PEN CREEK,Reach-1,1
Up Type=0
Dn Type=3
Dn Slope=0.005
Boundary for River Rch & Prof#=WOLF PEN CREEK,Reach-1,2
Up Type=0
Dn Type=3
Dn Slope=0.005
Boundary for River Rch & Prof#=WOLF PEN CREEK,Reach-1,3
Up Type=0
Dn Type=3
Dn Slope=0.005
Boundary for River Rch & Prof#=WOLF PEN CREEK,Reach-1,4
Up Type=0
Dn Type=3
Dn Slope=0.005
Boundary for River Rch & Prof#=WOLF PEN CREEK,Reach-1,5
Up Type=0
Dn Type=3
Dn Slope=0.005
Boundary for River Rch & Prof#=WOLF PEN CREEK,Reach-1,6
Up Type=0
Dn Type=3
Dn Slope=0.005
Boundary for River Rch & Prof#=WOLF PEN CREEK,Reach-1,7
Up Type=0
Dn Type=3
Dn Slope=0.005

--- WOLF PEN CREEK.g01 (geometry) ---

Geom Title=Existing Conditions

River Reach=WOLF PEN CREEK,Reach-1
Reach XY= 30
      3555354.18     10209523.03      3557196.45     10209872.99
      3557578.45     10209741.37      3557972.73     10210031.26
      3558744.19     10209766.22      3558916.94     10210142.96
      3560127.95     10210689.50      3560887.50     10211644.73
      3561239.93     10211512.78      3561420.92     10212057.92
      3561822.23     10211723.25      3562225.88     10211903.81
      3563021.75     10211457.76      3563529.57     10211721.43
      3563977.70     10211555.42      3564342.28     10212059.97
      3564260.90     10212281.33      3564893.14     10212962.87
      3565995.57     10213125.63      3566803.20     10212971.53
      3566963.19     10213247.15      3567367.45     10213082.49
      3567685.63     10213301.10      3567735.63     10213144.15
      3568366.53     10213253.33      3568552.35     10213819.84
      3569001.61     10213282.83      3568982.55     10213609.26
      3569626.21     10213494.20      3569902.11     10213811.64

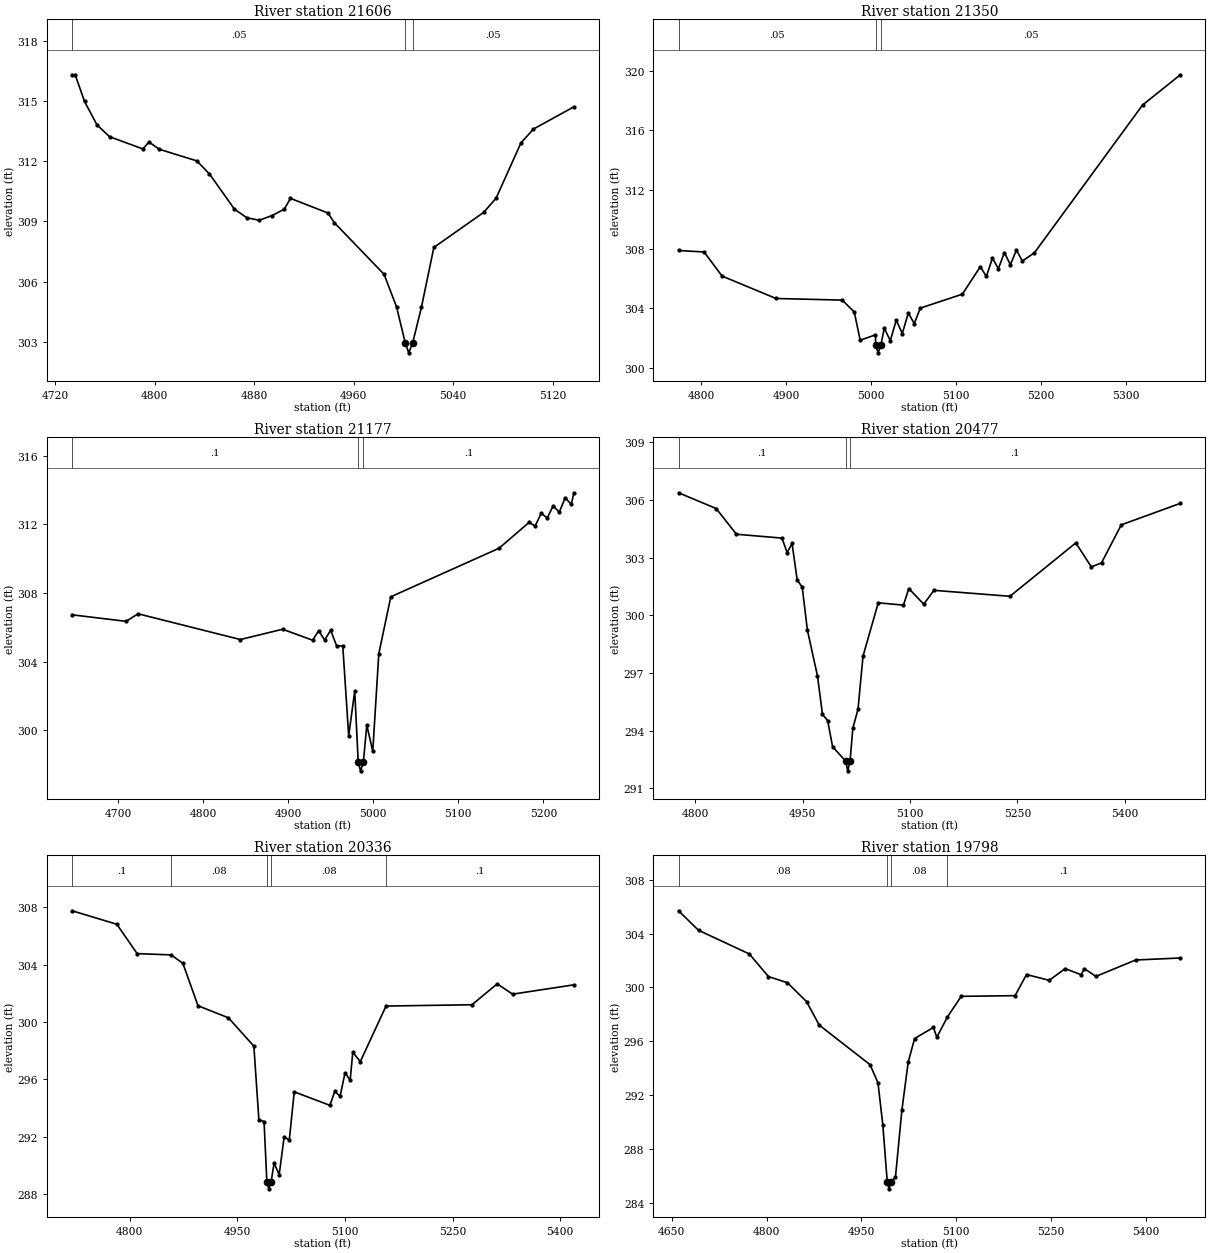
Type RM Length L Ch R = 1,21606,256,256,256
BEGIN DESCRIPTION:
WOLF PEN CREEK 44.0
END DESCRIPTION:
XS GIS Cut Line= 3
      3555442.10     10209741.62      3555424.51     10209536.73
      3555423.65     10209339.17
#Sta/Elev= 30
  4733.7  316.32  4736.2  316.32  4743.7  314.99  4753.7  313.82  4763.8  313.23
  4790.5  312.62  4795.5  312.96  4803.9  312.60  4834.0  312.02  4844.1  311.37
  4864.2  309.61  4874.2  309.18  4884.2  309.06  4894.3  309.29  4904.2  309.61
  4909.2  310.15  4939.3  309.42  4944.4  308.94  4984.4  306.36  4994.4  304.74
  5001.4  302.94  5004.2  302.44  5007.4  302.94  5014.4  304.71  5024.4  307.70
  5064.4  309.45  5074.4  310.16  5094.4  312.92  5104.4  313.61  5136.9  314.72
#Mann=3,-1,0
  4733.7    0.05       0  5001.4    0.04       0  5007.4    0.05       0
Bank Sta=5001.4,5007.4
Exp/Cntr=0.3,0.1

Type RM Length L Ch R = 1,21350,173,173,173
BEGIN DESCRIPTION:
WOLF PEN CREEK 43.1
END DESCRIPTION:
XS GIS Cut Line= 3
      3555815.30     10209680.84      3555647.20     10209521.23
      3555392.78     10209268.09
#Sta/Elev= 30
  4773.1  307.90  4803.2  307.80  4824.3  306.18  4887.8  304.67  4965.8  304.56
  4980.0  303.76  4986.9  301.86  5004.9  302.22  5005.2  301.51  5008.0  301.01
  5011.2  301.51  5015.3  302.67  5022.4  301.83  5029.4  303.21  5036.5  302.31
  5043.6  303.69  5050.6  302.98  5057.7  304.02  5107.2  304.96  5128.4  306.81
  5135.5  306.15  5142.6  307.39  5149.6  306.68  5156.7  307.76  5163.8  306.94
  5170.8  307.93  5177.9  307.19  5192.1  307.75  5319.3  317.69  5363.8  319.73
#Mann=3,-1,0
  4773.1    0.05       0  5005.2    0.04       0  5011.2    0.05       0
Bank Sta=5005.2,5011.2
Exp/Cntr=0.3,0.1

Type RM Length L Ch R = 1,21177,700,700,700
BEGIN DESCRIPTION:
WOLF PEN CREEK 43.0
END DESCRIPTION:
XS GIS Cut Line= 3
      3556075.38     10209738.21      3555907.31     10209578.62
      3555653.43     10209326.02
#Sta/Elev= 30
  4646.0  306.73  4709.5  306.35  4723.6  306.79  4843.8  305.29  4893.5  305.89
  4928.8  305.25  4935.9  305.81  4942.9  305.26  4950.0  305.83  4957.1  304.91
  4964.2  304.93  4971.2  299.68  4978.3  302.29  4982.4  298.14  4985.1  297.64
  4988.4  298.14  4992.5  300.30  4999.5  298.78  5006.6  304.47  5020.7  307.78
  5148.0  310.61  5183.4  312.12  5190.4  311.90  5197.5  312.65  5204.6  312.37
  5211.6  313.08  5218.7  312.71  5225.8  313.55  5232.9  313.16  5235.9  313.84
#Mann=3,-1,0
  4646.0     0.1       0  4982.4    0.07       0  4988.4     0.1       0
Bank Sta=4982.4,4988.4
Exp/Cntr=0.3,0.1

Type RM Length L Ch R = 1,20477,141,141,141
BEGIN DESCRIPTION:
WOLF PEN CREEK 42.0
END DESCRIPTION:
XS GIS Cut Line= 3
      3556308.63     10209872.58      3556526.02     10209663.73
      3556823.97     10209397.54
#Sta/Elev= 30
  4776.6  306.38  4829.2  305.56  4857.5  304.22  4921.1  304.02  4928.3  303.26
  4935.2  303.74  4942.4  301.83  4949.4  301.47  4956.6  299.23  4970.7  296.84
  4977.7  294.84  4984.9  294.52  4991.8  293.16  5010.2  292.40  5012.9  291.90
  5016.2  292.40  5020.1  294.12  5027.3  295.10  5034.3  297.87  5055.6  300.65
  5090.8  300.53  5098.3  301.39  5119.2  300.58  5133.4  301.30  5239.6  300.99
  5331.6  303.77  5353.3  302.52  5367.5  302.73  5395.1  304.71  5477.6  305.83
#Mann=3,-1,0
  4776.6     0.1       0  5010.2    0.07       0  5016.2     0.1       0
Bank Sta=5010.2,5016.2
Exp/Cntr=0.3,0.1

Type RM Length L Ch R = 1,20336,538,538,538
BEGIN DESCRIPTION:
WOLF PEN CREEK 41.0
END DESCRIPTION:
XS GIS Cut Line= 3
      3556399.01     10209956.83      3556682.33     10209684.49
      3556892.39     10209461.00
#Sta/Elev= 30
  4719.4  307.76  4781.8  306.82  4810.1  304.77  4857.6  304.68  4873.9  304.09
  4895.0  301.13  4937.4  300.29  4972.9  298.31  4979.9  293.17  4987.1  293.05
  4991.0  288.85  4993.8  288.35  4997.0  288.85  5001.1  290.15  5008.2  289.34
  5015.1  291.97  5022.3  291.76  5029.2  295.12  5078.9  294.18  5085.8  295.16
  5093.1  294.80  5100.0  296.45  5107.2  295.93  5110.8  297.89  5121.3  297.23
  5157.2  301.11  5277.0  301.20  5312.2  302.66  5333.7  301.94  5419.1  302.59
#Mann=5,-1,0
  4719.4     0.1       0  4857.6    0.08       0  4991.0    0.07       0
  4997.0    0.08       0  5157.2     0.1       0
Bank Sta=4991,4997
Exp/Cntr=0.3,0.1

Type RM Length L Ch R = 1,19798,617,617,617
BEGIN DESCRIPTION:
WOLF PEN CREEK 40.0
END DESCRIPTION:
XS GIS Cut Line= 3
      3557054.72     10210173.03      3557094.60     10209789.71
      3556954.23     10209406.18
#Sta/Elev= 30
  4660.7  305.70  4692.3  304.25  4772.7  302.49  4802.9  300.81  4833.0  300.35
  4863.2  298.95  4883.3  297.20  4963.7  294.26  4976.2  292.91  4983.8  289.81
  4990.9  285.53  4993.6  285.03  4996.9  285.53  5003.9  285.91  5014.0  290.87
  5024.0  294.45  5034.1  296.20  5063.9  297.03  5069.3  296.30  5086.1  297.81
  5107.9  299.34  5193.1  299.39  5211.2  300.96  5247.1  300.53  5272.3  301.40
  5297.5  300.95  5302.8  301.40  5320.9  300.82  5383.7  302.04  5454.5  302.19
#Mann=4,-1,0
  4660.7    0.08       0  4990.9    0.07       0  4996.9    0.08       0
  5086.1     0.1       0
Bank Sta=4990.9,4996.9
Exp/Cntr=0.3,0.1

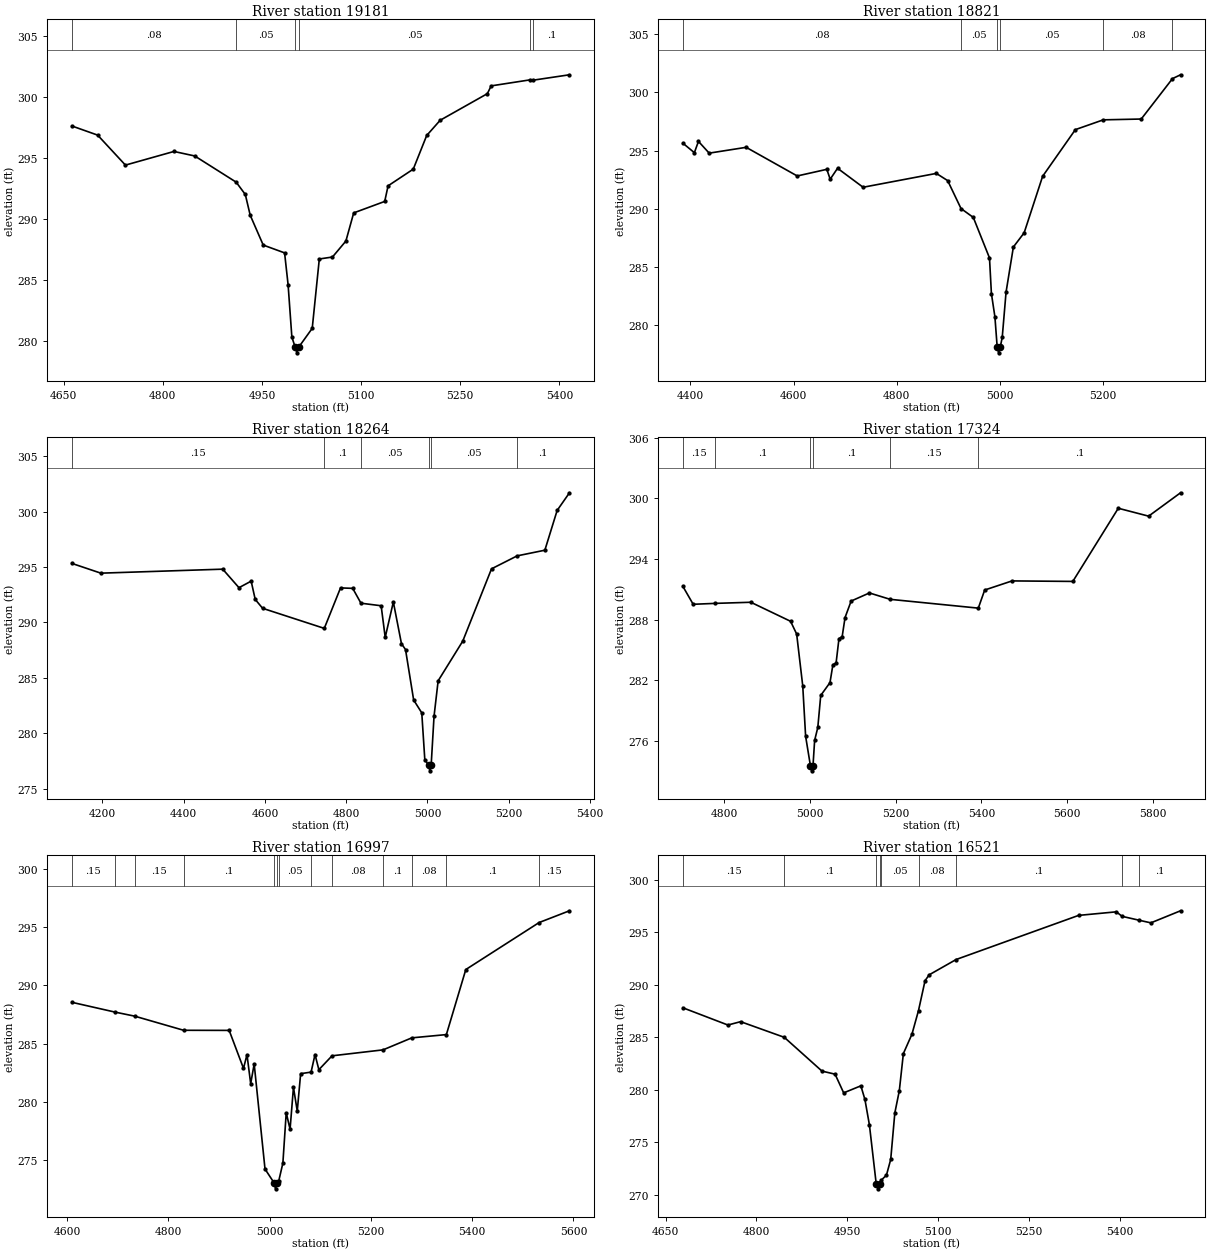
Type RM Length L Ch R = 1,19181,360,360,360
BEGIN DESCRIPTION:
WOLF PEN CREEK 39.0
END DESCRIPTION:
XS GIS Cut Line= 3
      3557488.75     10210068.85      3557592.11     10209741.64
      3557669.31     10209339.63
#Sta/Elev= 30
  4662.6  297.60  4701.6  296.85  4743.6  294.39  4817.0  295.51  4848.4  295.14
  4911.1  292.99  4924.9  291.98  4932.3  290.28  4952.0  287.83  4984.3  287.19
  4989.6  284.58  4995.3  280.28  5000.1  279.49  5002.9  278.99  5006.1  279.49
  5026.1  281.00  5036.8  286.69  5056.7  286.85  5077.0  288.16  5088.8  290.47
  5135.7  291.41  5140.8  292.69  5178.9  294.06  5199.2  296.82  5219.6  298.07
  5290.9  300.25  5296.7  300.89  5355.1  301.38  5360.6  301.36  5415.1  301.80
#Mann=6,-1,0
  4662.6    0.08       0  4911.1    0.05       0  5000.1    0.04       0
  5006.1    0.05       0  5355.1    0.08       0  5360.6     0.1       0
Bank Sta=5000.1,5006.1
Exp/Cntr=0.3,0.1

Type RM Length L Ch R = 1,18821,557,557,557
BEGIN DESCRIPTION:
WOLF PEN CREEK 38.0
END DESCRIPTION:
XS GIS Cut Line= 3
      3557516.22     10210347.72      3557892.11     10209891.64
      3558143.79     10209615.30
#Sta/Elev= 30
  4385.5  295.63  4407.7  294.82  4415.6  295.79  4436.4  294.78  4508.1  295.28
  4607.1  292.82  4664.5  293.39  4671.0  292.54  4685.3  293.48  4734.8  291.85
  4876.8  293.04  4898.8  292.42  4924.7  290.02  4948.5  289.26  4979.9  285.78
  4983.6  282.72  4990.4  280.72  4994.8  278.13  4997.6  277.63  5000.8  278.13
  5004.6  278.96  5012.0  282.84  5026.2  286.72  5047.1  287.94  5082.9  292.79
  5146.4  296.80  5200.5  297.64  5274.1  297.71  5334.7  301.18  5350.3  301.51
#Mann=6,-1,0
  4385.5    0.08       0  4924.7    0.05       0  4994.8    0.04       0
  5000.8    0.05       0  5200.5    0.08       0  5334.7     0.1       0
Bank Sta=4994.8,5000.8
Exp/Cntr=0.3,0.1

Type RM Length L Ch R = 1,18264,940,940,940
BEGIN DESCRIPTION:
WOLF PEN CREEK 37.0
END DESCRIPTION:
XS GIS Cut Line= 3
      3558353.04     10210813.00      3558342.11     10209941.64
      3558292.10     10209591.62
#Sta/Elev= 30
  4124.8  295.33  4196.2  294.45  4496.2  294.81  4536.2  293.14  4566.2  293.73
  4576.2  292.08  4594.4  291.28  4746.2  289.47  4786.2  293.12  4816.2  293.08
  4836.5  291.74  4886.2  291.51  4896.2  288.66  4916.2  291.85  4936.2  288.09
  4946.2  287.56  4966.2  283.01  4986.2  281.85  4993.7  277.62  5003.3  277.12
  5006.1  276.62  5009.3  277.12  5016.4  281.54  5026.5  284.74  5087.1  288.32
  5157.9  294.84  5221.0  296.01  5289.2  296.52  5319.5  300.11  5349.8  301.70
#Mann=6,-1,0
  4124.8    0.15       0  4746.2     0.1       0  4836.5    0.05       0
  5003.3    0.04       0  5009.3    0.05       0  5221.0     0.1       0
Bank Sta=5003.3,5009.3
Exp/Cntr=0.3,0.1

Type RM Length L Ch R = 1,17324,327,327,327
BEGIN DESCRIPTION:
WOLF PEN CREEK 35.0
END DESCRIPTION:
XS GIS Cut Line= 3
      3558695.34     10210338.98      3559055.72     10210010.64
      3559542.73     10209547.06
#Sta/Elev= 30
  4704.1  291.29  4728.0  289.53  4779.6  289.62  4862.4  289.73  4955.0  287.85
  4969.2  286.59  4983.4  281.46  4990.1  276.48  5001.3  273.57  5004.1  273.07
  5007.3  273.57  5011.1  276.08  5018.5  277.36  5025.3  280.52  5046.9  281.79
  5053.7  283.56  5061.1  283.72  5067.8  286.13  5075.3  286.34  5082.0  288.22
  5096.2  289.85  5138.8  290.65  5187.1  290.02  5392.6  289.15  5407.5  290.94
  5471.3  291.84  5612.9  291.79  5718.9  299.02  5789.6  298.24  5864.0  300.55
#Mann=6,-1,0
  4704.1    0.15       0  4779.6     0.1       0  5001.3    0.07       0
  5007.3     0.1       0  5187.1    0.15       0  5392.6     0.1       0
Bank Sta=5001.3,5007.3
Exp/Cntr=0.3,0.1

Type RM Length L Ch R = 1,16997,476,476,476
BEGIN DESCRIPTION:
WOLF PEN CREEK 34.0
END DESCRIPTION:
XS GIS Cut Line= 3
      3558934.96     10210473.71      3559218.31     10210204.43
      3559662.47     10209812.74
#Sta/Elev= 30
  4609.1  288.55  4694.3  287.71  4733.4  287.36  4829.9  286.15  4919.9  286.14
  4948.2  282.88  4955.1  284.06  4962.4  281.57  4969.3  283.26  4990.7  274.25
  5008.8  273.05  5011.5  272.55  5014.8  273.05  5017.7  273.20  5026.0  274.76
  5032.6  279.08  5040.2  277.66  5046.9  281.26  5054.4  279.22  5061.1  282.43
  5081.7  282.56  5089.5  284.07  5097.1  282.77  5123.1  283.96  5223.9  284.47
  5280.7  285.50  5349.0  285.78  5387.4  291.36  5532.2  295.39  5592.2  296.40
#Mann=13,-1,0
  4609.1    0.15       0  4694.3     0.1       0  4733.4    0.15       0
  4829.9     0.1       0  5008.8    0.07       0  5014.8     0.1       0
  5017.7    0.05       0  5081.7     0.1       0  5123.1    0.08       0
  5223.9     0.1       0  5280.7    0.08       0  5349.0     0.1       0
  5532.2    0.15       0
Bank Sta=5008.8,5014.8
Exp/Cntr=0.3,0.1

Type RM Length L Ch R = 1,16521,705,705,705
BEGIN DESCRIPTION:
WOLF PEN CREEK 33.0
END DESCRIPTION:
XS GIS Cut Line= 3
      3559434.95     10210599.37      3559741.37     10210265.47
      3559862.03     10209917.06
#Sta/Elev= 30
  4678.7  287.80  4753.0  286.16  4774.0  286.48  4846.1  284.99  4908.4  281.77
  4930.0  281.48  4944.2  279.70  4972.6  280.37  4979.3  279.07  4986.7  276.66
  4997.9  271.06  5000.7  270.56  5003.9  271.06  5006.1  271.37  5014.9  271.87
  5021.9  273.36  5028.7  277.79  5036.1  279.90  5042.8  283.44  5057.0  285.29
  5067.8  287.54  5078.6  290.38  5085.4  290.94  5130.0  292.40  5332.2  296.60
  5394.5  296.94  5404.1  296.51  5431.4  296.15  5451.6  295.89  5500.6  297.04
#Mann=9,-1,0
  4678.7    0.15       0  4846.1     0.1       0  4997.9    0.07       0
  5003.9     0.1       0  5006.1    0.05       0  5067.8    0.08       0
  5130.0     0.1       0  5404.1    0.15       0  5431.4     0.1       0
Bank Sta=4997.9,5003.9
Exp/Cntr=0.3,0.1

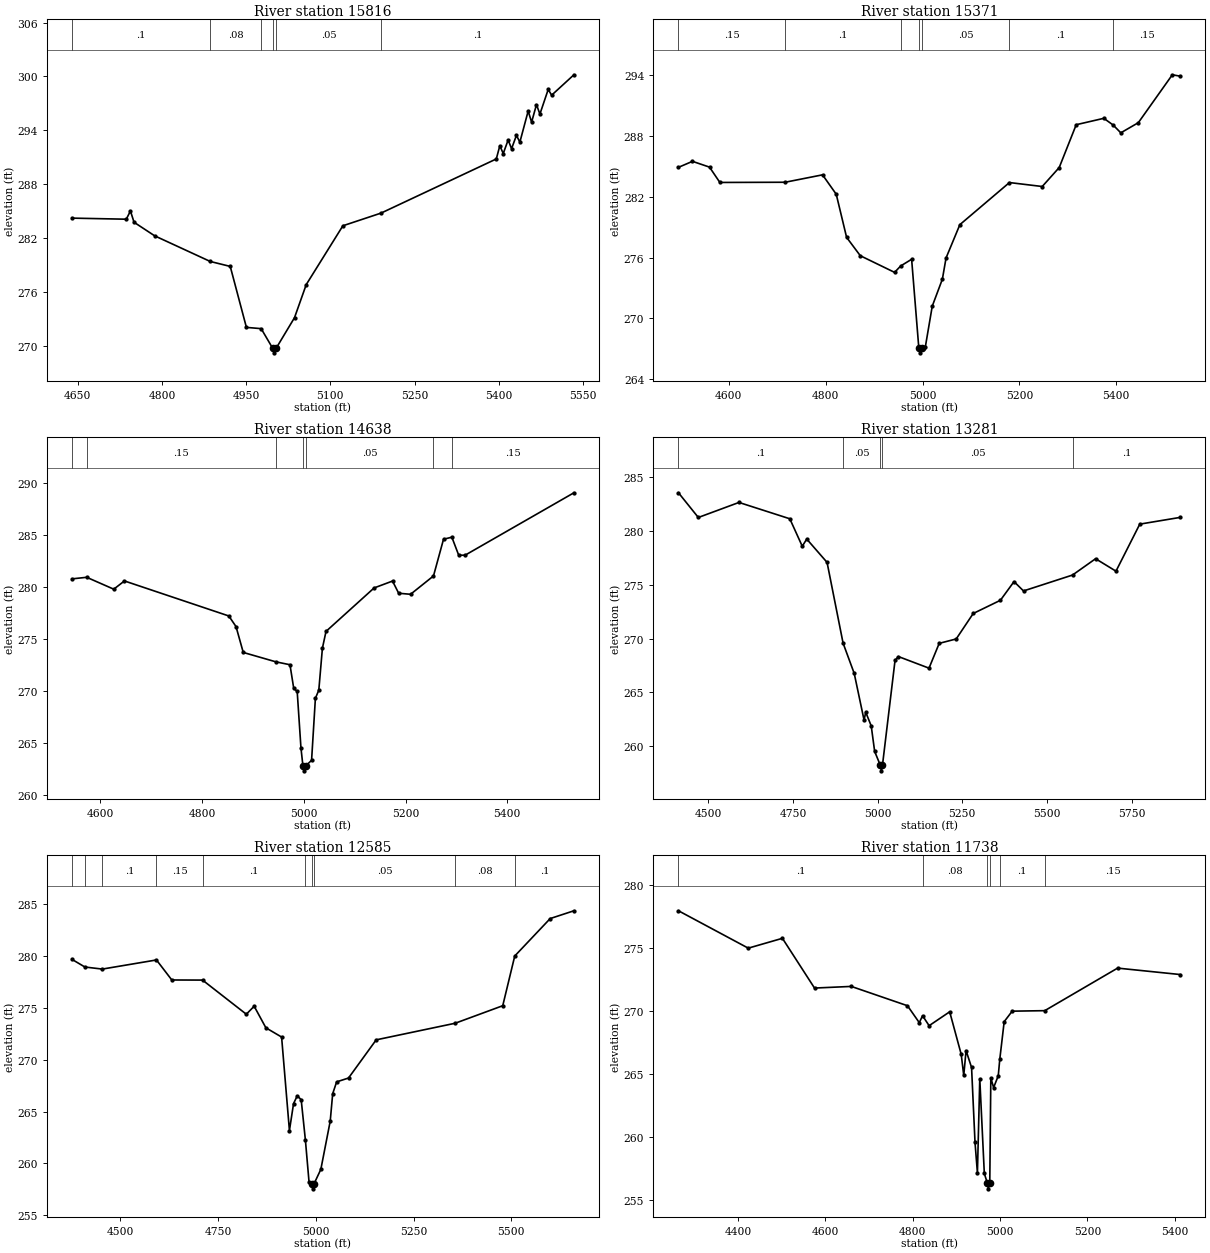
Type RM Length L Ch R = 1,15816,445,445,445
BEGIN DESCRIPTION:
WOLF PEN CREEK 31.0
END DESCRIPTION:
XS GIS Cut Line= 3
      3559981.82     10211047.29      3560201.39     10210771.01
      3560513.05     10210328.57
#Sta/Elev= 30
  4639.9  284.25  4736.5  284.13  4743.9  285.05  4750.3  283.79  4787.1  282.28
  4886.1  279.43  4921.7  278.88  4950.5  272.10  4976.8  271.96  4997.4  269.77
  5000.2  269.27  5003.4  269.77  5036.2  273.18  5057.1  276.86  5122.4  283.40
  5190.4  284.81  5395.7  290.83  5402.0  292.30  5408.1  291.43  5416.8  292.94
  5422.9  291.97  5431.6  293.45  5437.7  292.70  5452.5  296.16  5458.6  294.92
  5467.3  296.87  5473.4  295.82  5488.2  298.56  5494.3  297.92  5534.0  300.19
#Mann=6,-1,0
  4639.9     0.1       0  4886.1    0.08       0  4976.8    0.05       0
  4997.4    0.04       0  5003.4    0.05       0  5190.4     0.1       0
Bank Sta=4997.4,5003.4
Exp/Cntr=0.3,0.1

Type RM Length L Ch R = 1,15371,733,733,733
BEGIN DESCRIPTION:
WOLF PEN CREEK 30.0
END DESCRIPTION:
XS GIS Cut Line= 3
      3560127.64     10211437.93      3560492.11     10211091.64
      3560841.16     10210687.96
#Sta/Elev= 30
  4496.0  284.89  4524.9  285.48  4560.1  284.91  4581.5  283.40  4716.3  283.42
  4793.5  284.15  4821.8  282.24  4843.2  277.99  4871.5  276.18  4942.3  274.54
  4954.9  275.17  4977.5  275.83  4992.3  267.11  4995.0  266.61  4998.3  267.11
  5005.9  267.22  5020.1  271.21  5041.0  273.87  5048.6  275.96  5077.1  279.24
  5179.5  283.39  5247.2  283.00  5282.3  284.87  5317.4  289.09  5374.4  289.72
  5393.6  289.06  5409.5  288.29  5445.7  289.29  5515.9  294.01  5532.4  293.87
#Mann=7,-1,0
  4496.0    0.15       0  4716.3     0.1       0  4954.9    0.05       0
  4992.3    0.04       0  4998.3    0.05       0  5179.5     0.1       0
  5393.6    0.15       0
Bank Sta=4992.3,4998.3
Exp/Cntr=0.3,0.1

Type RM Length L Ch R = 1,14638,1357,1357,1357
BEGIN DESCRIPTION:
WOLF PEN CREEK 29.0
END DESCRIPTION:
XS GIS Cut Line= 3
      3560528.69     10211803.92      3560920.48     10211445.70
      3561164.45     10211060.18
#Sta/Elev= 30
  4544.1  280.78  4572.9  280.93  4626.1  279.79  4647.1  280.58  4852.4  277.22
  4866.6  276.20  4880.8  273.72  4944.9  272.82  4972.7  272.54  4980.1  270.27
  4986.9  269.98  4994.3  264.56  4998.1  262.86  5000.8  262.36  5004.1  262.86
  5015.2  263.37  5022.7  269.32  5029.4  270.10  5036.5  274.13  5043.6  275.74
  5138.2  279.91  5174.4  280.57  5186.5  279.40  5209.9  279.30  5255.0  281.06
  5274.7  284.58  5291.1  284.78  5304.6  283.05  5317.1  283.05  5531.2  289.04
#Mann=7,-1,0
  4544.1     0.1       0  4572.9    0.15       0  4944.9    0.05       0
  4998.1    0.04       0  5004.1    0.05       0  5255.0     0.1       0
  5291.1    0.15       0
Bank Sta=4998.1,5004.1
Exp/Cntr=0.3,0.1

Type RM Length L Ch R = 1,13281,696,696,696
BEGIN DESCRIPTION:
WOLF PEN CREEK 26.0
END DESCRIPTION:
XS GIS Cut Line= 3
      3561528.68     10212620.24      3561539.21     10212161.40
      3561626.25     10211142.38
#Sta/Elev= 30
  4412.2  283.57  4470.8  281.27  4590.8  282.67  4740.9  281.15  4777.7  278.59
  4790.9  279.26  4850.9  277.09  4898.2  269.57  4931.1  266.75  4960.1  262.41
  4965.1  263.14  4981.3  261.86  4991.4  259.49  5008.4  258.18  5011.2  257.68
  5014.4  258.18  5051.6  267.96  5061.6  268.32  5151.9  267.24  5182.0  269.55
  5232.2  269.96  5282.4  272.33  5362.7  273.56  5402.9  275.30  5430.9  274.43
  5575.6  275.91  5643.7  277.43  5703.9  276.27  5774.2  280.65  5893.9  281.28
#Mann=5,-1,0
  4412.2     0.1       0  4898.2    0.05       0  5008.4    0.04       0
  5014.4    0.05       0  5575.6     0.1       0
Bank Sta=5008.4,5014.4
Exp/Cntr=0.3,0.1

Type RM Length L Ch R = 1,12585,847,847,847
BEGIN DESCRIPTION:
WOLF PEN CREEK 24.0
END DESCRIPTION:
XS GIS Cut Line= 3
      3561893.26     10212516.08      3561942.11     10211891.64
      3562042.11     10211241.64
#Sta/Elev= 30
  4376.3  279.66  4409.1  278.93  4453.6  278.73  4592.2  279.61  4631.5  277.68
  4710.1  277.67  4822.1  274.38  4842.2  275.15  4872.2  273.07  4912.4  272.18
  4932.4  263.17  4943.0  265.77  4952.5  266.52  4962.5  266.14  4973.3  262.24
  4982.6  258.21  4989.6  258.05  4992.4  257.55  4995.6  258.05  5012.8  259.43
  5036.8  264.08  5043.1  266.72  5053.2  267.86  5083.6  268.23  5154.4  271.91
  5356.5  273.51  5478.2  275.20  5508.9  279.99  5599.6  283.60  5660.3  284.35
#Mann=10,-1,0
  4376.3     0.1       0  4409.1    0.15       0  4453.6     0.1       0
  4592.2    0.15       0  4710.1     0.1       0  4973.3    0.05       0
  4989.6    0.04       0  4995.6    0.05       0  5356.5    0.08       0
  5508.9     0.1       0
Bank Sta=4989.6,4995.6
Exp/Cntr=0.3,0.1

Type RM Length L Ch R = 1,11738,195,195,195
BEGIN DESCRIPTION:
WOLF PEN CREEK 22.0
END DESCRIPTION:
XS GIS Cut Line= 3
      3562408.39     10212358.42      3562611.59     10211721.53
      3562775.33     10211269.70
#Sta/Elev= 30
  4263.5  277.93  4423.3  274.97  4501.5  275.75  4575.0  271.81  4659.2  271.94
  4787.9  270.41  4814.9  269.07  4822.4  269.62  4837.4  268.83  4884.5  269.93
  4910.9  266.56  4916.7  264.89  4922.0  266.86  4934.6  265.52  4942.5  259.59
  4948.0  257.17  4953.4  264.63  4963.8  257.13  4970.3  256.41  4973.1  255.91
  4976.3  256.41  4978.7  264.69  4985.1  263.93  4995.7  264.86  4999.2  266.17
  5009.3  269.15  5027.6  269.98  5102.2  270.02  5269.0  273.39  5412.6  272.88
#Mann=6,-1,0
  4263.5     0.1       0  4822.4    0.08       0  4970.3    0.07       0
  4976.3    0.08       0  4999.2     0.1       0  5102.2    0.15       0
Bank Sta=4970.3,4976.3
Exp/Cntr=0.3,0.1

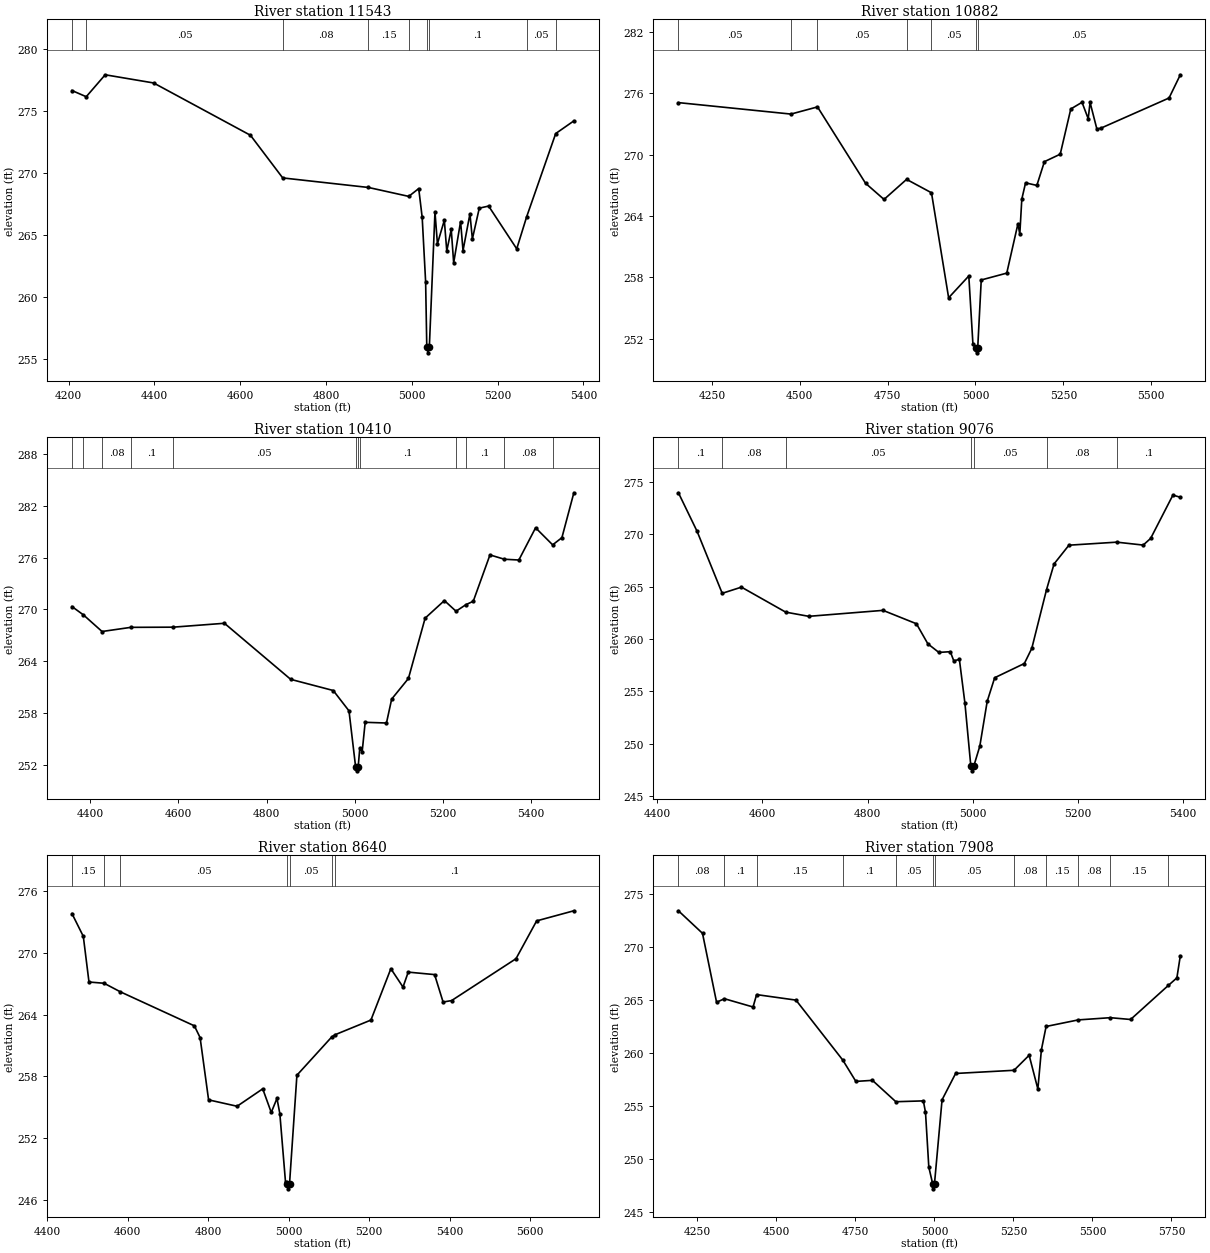
Type RM Length L Ch R = 1,11543,661,661,661
BEGIN DESCRIPTION:
WOLF PEN CREEK 21.0
END DESCRIPTION:
XS GIS Cut Line= 3
      3562611.59     10212337.16      3562772.32     10211642.68
      3562992.13     10211241.60
#Sta/Elev= 30
  4207.6  276.68  4240.9  276.18  4285.1  277.95  4398.0  277.29  4623.8  273.07
  4699.0  269.63  4898.9  268.86  4992.8  268.14  5016.1  268.77  5024.2  266.44
  5032.2  261.25  5034.9  256.02  5037.6  255.52  5040.9  256.02  5054.0  266.89
  5059.7  264.32  5075.8  266.21  5081.5  263.74  5091.9  265.47  5097.6  262.78
  5113.7  266.11  5119.4  263.77  5135.5  266.73  5141.2  264.71  5157.3  267.19
  5179.1  267.36  5244.6  263.91  5267.8  266.50  5335.5  273.21  5377.8  274.23
#Mann=9,-1,0
  4207.6     0.1       0  4240.9    0.05       0  4699.0    0.08       0
  4898.9    0.15       0  4992.8     0.1       0  5034.9    0.07       0
  5040.9     0.1       0  5267.8    0.05       0  5335.5    0.08       0
Bank Sta=5034.9,5040.9
Exp/Cntr=0.3,0.1

Type RM Length L Ch R = 1,10882,472,472,472
BEGIN DESCRIPTION:
WOLF PEN CREEK 20.0
END DESCRIPTION:
XS GIS Cut Line= 3
      3563087.73     10212467.52      3563342.11     10211691.64
      3563559.92     10211120.26
#Sta/Elev= 30
  4154.9  275.08  4475.1  273.96  4550.6  274.66  4687.3  267.20  4739.9  265.62
  4804.1  267.58  4874.9  266.27  4923.7  256.01  4981.1  258.14  4992.8  251.51
  5000.5  251.13  5003.3  250.63  5006.5  251.13  5016.5  257.75  5089.1  258.42
  5120.9  263.24  5126.2  262.22  5131.9  265.65  5142.6  267.24  5174.7  266.99
  5196.2  269.31  5241.2  270.04  5271.3  274.46  5303.2  275.11  5320.8  273.51
  5326.1  275.10  5345.5  272.50  5356.7  272.58  5550.8  275.53  5582.9  277.80
#Mann=7,-1,0
  4154.9    0.05       0  4475.1     0.1       0  4550.6    0.05       0
  4804.1    0.08       0  4874.9    0.05       0  5000.5    0.04       0
  5006.5    0.05       0
Bank Sta=5000.5,5006.5
Exp/Cntr=0.3,0.1

Type RM Length L Ch R = 1,10410,1334,1334,1334
BEGIN DESCRIPTION:
WOLF PEN CREEK 19.0
END DESCRIPTION:
XS GIS Cut Line= 3
      3563549.52     10212213.95      3563792.11     10211591.64
      3564017.70     10211178.55
#Sta/Elev= 30
  4358.3  270.34  4384.5  269.37  4426.6  267.46  4491.9  267.94  4587.8  267.96
  4704.2  268.41  4854.5  261.94  4951.1  260.65  4986.8  258.30  5001.7  251.88
  5004.5  251.38  5007.7  251.88  5011.3  254.02  5016.6  253.55  5023.5  256.98
  5071.8  256.90  5083.6  259.66  5121.6  262.04  5159.5  269.00  5203.2  271.03
  5229.6  269.80  5252.1  270.56  5268.7  270.95  5306.6  276.30  5339.2  275.80
  5372.1  275.71  5410.1  279.43  5448.8  277.46  5469.8  278.29  5496.9  283.47
#Mann=12,-1,0
  4358.3    0.05       0  4384.5     0.1       0  4426.6    0.08       0
  4491.9     0.1       0  4587.8    0.05       0  5001.7    0.04       0
  5007.7    0.05       0  5011.3     0.1       0  5229.6    0.08       0
  5252.1     0.1       0  5339.2    0.08       0  5448.8    0.05       0
Bank Sta=5001.7,5007.7
Exp/Cntr=0.3,0.1

Type RM Length L Ch R = 1,9076,436,436,436
BEGIN DESCRIPTION:
WOLF PEN CREEK 16.0
END DESCRIPTION:
XS GIS Cut Line= 3
      3563992.13     10212741.61      3564342.11     10212341.64
      3564642.08     10212041.66
#Sta/Elev= 30
  4439.9  273.97  4475.5  270.28  4523.3  264.36  4559.9  264.95  4644.2  262.56
  4688.1  262.16  4829.5  262.73  4893.1  261.45  4914.9  259.53  4935.8  258.71
  4957.6  258.78  4964.2  257.91  4974.9  258.04  4985.5  253.84  4996.6  247.89
  4999.4  247.39  5002.6  247.89  5013.8  249.75  5027.9  254.04  5042.1  256.29
  5098.6  257.65  5112.8  259.10  5140.9  264.72  5155.2  267.17  5183.5  268.96
  5274.6  269.25  5324.9  268.97  5339.1  269.61  5381.5  273.75  5395.6  273.54
#Mann=7,-1,0
  4439.9     0.1       0  4523.3    0.08       0  4644.2    0.05       0
  4996.6    0.04       0  5002.6    0.05       0  5140.9    0.08       0
  5274.6     0.1       0
Bank Sta=4996.6,5002.6
Exp/Cntr=0.3,0.1

Type RM Length L Ch R = 1,8640,732,732,732
BEGIN DESCRIPTION:
WOLF PEN CREEK 15.0
END DESCRIPTION:
XS GIS Cut Line= 3
      3564292.14     10212991.61      3564841.18     10212437.93
      3565096.36     10212047.35
#Sta/Elev= 30
  4461.9  273.80  4490.1  271.59  4504.2  267.16  4541.7  267.04  4582.1  266.21
  4765.9  262.91  4780.1  261.77  4801.2  255.73  4872.0  255.11  4935.6  256.80
  4956.8  254.51  4971.0  255.87  4978.1  254.40  4992.2  247.75  4996.2  247.60
  4999.0  247.10  5002.2  247.60  5020.5  258.12  5106.7  261.82  5114.8  262.04
  5204.3  263.47  5253.8  268.45  5284.0  266.67  5296.9  268.12  5362.4  267.88
  5383.5  265.22  5404.6  265.36  5564.5  269.42  5615.8  273.09  5708.2  274.07
#Mann=7,-1,0
  4461.9    0.15       0  4541.7     0.1       0  4582.1    0.05       0
  4996.2    0.04       0  5002.2    0.05       0  5106.7    0.08       0
  5114.8     0.1       0
Bank Sta=4996.2,5002.2
Exp/Cntr=0.3,0.1

Type RM Length L Ch R = 1,7908,509,509,509
BEGIN DESCRIPTION:
WOLF PEN CREEK 13.0
END DESCRIPTION:
XS GIS Cut Line= 3
      3564893.25     10213656.72      3565200.56     10212687.93
      3565367.17     10212141.22
#Sta/Elev= 30
  4190.2  273.43  4266.4  271.30  4310.9  264.79  4335.8  265.12  4426.3  264.34
  4437.6  265.51  4562.1  264.99  4710.3  259.32  4751.6  257.31  4804.0  257.41
  4878.1  255.39  4965.1  255.47  4971.9  254.39  4982.4  249.21  4994.4  247.66
  4997.2  247.16  5000.4  247.66  5024.3  255.57  5067.2  258.06  5252.0  258.36
  5299.8  259.78  5327.4  256.59  5338.6  260.30  5353.5  262.50  5455.0  263.12
  5556.5  263.33  5620.8  263.16  5740.3  266.38  5767.2  267.09  5778.1  269.18
#Mann=12,-1,0
  4190.2    0.08       0  4335.8     0.1       0  4437.6    0.15       0
  4710.3     0.1       0  4878.1    0.05       0  4994.4    0.04       0
  5000.4    0.05       0  5252.0    0.08       0  5353.5    0.15       0
  5455.0    0.08       0  5556.5    0.15       0  5740.3     0.1       0
Bank Sta=4994.4,5000.4
Exp/Cntr=0.3,0.1

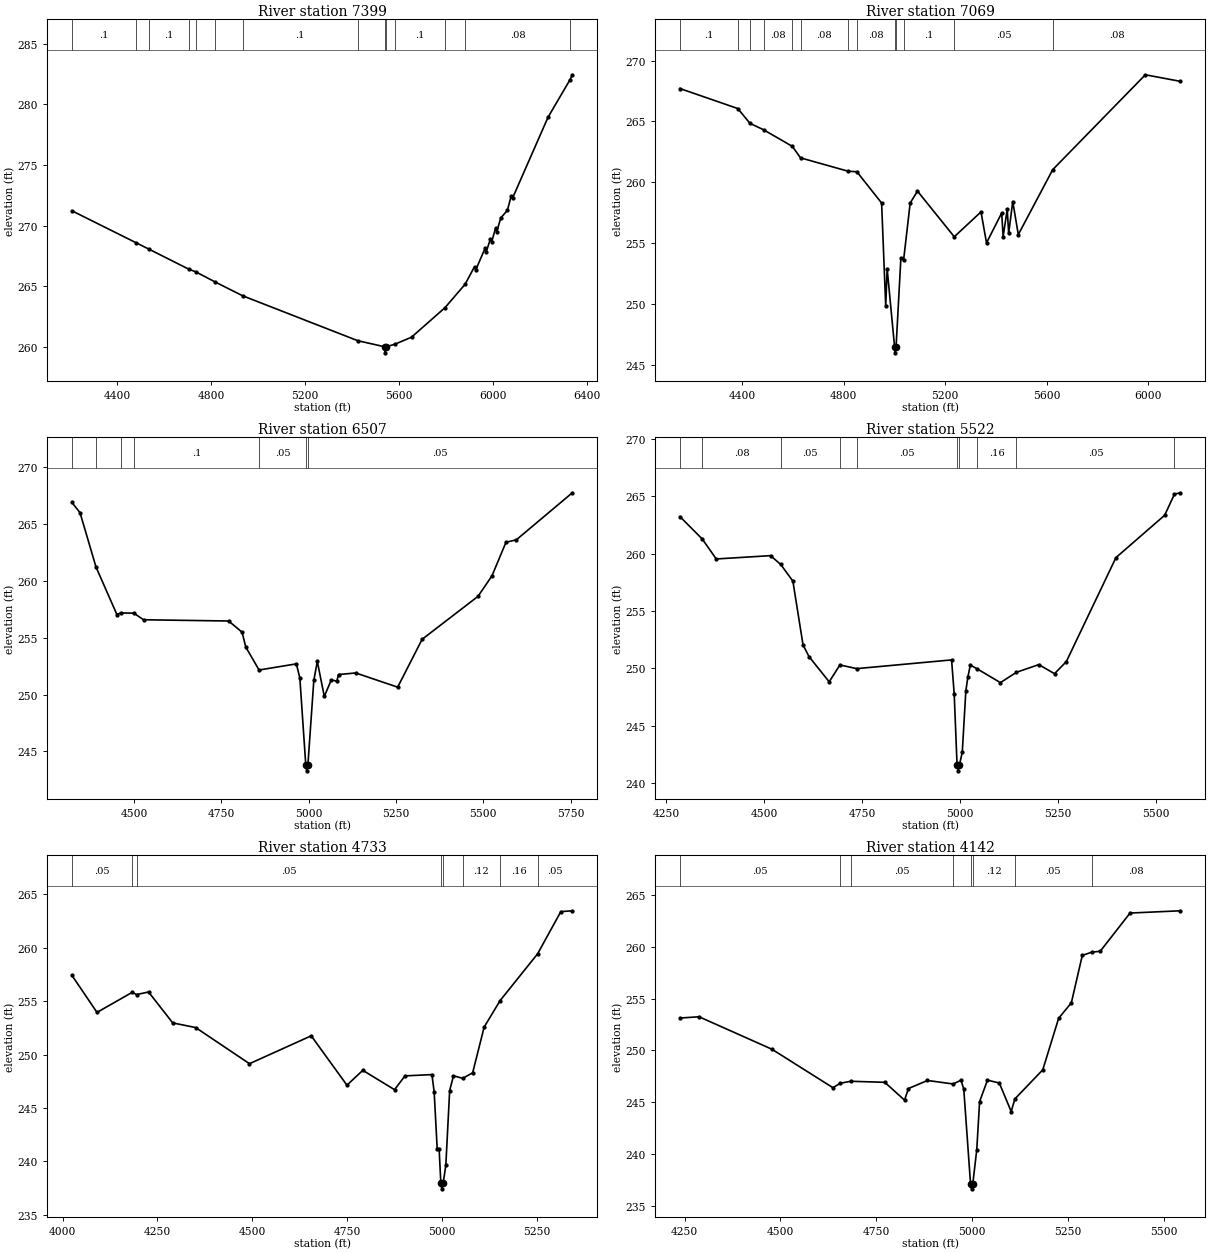
Type RM Length L Ch R = 1,7399,330,330,330
BEGIN DESCRIPTION:
WOLF PEN CREEK 12.0
END DESCRIPTION:
XS GIS Cut Line= 3
      3565126.67     10213763.04      3565542.11     10213091.64
      3566142.12     10211891.62
#Sta/Elev= 30
  4206.9  271.22  4479.7  268.59  4533.8  268.07  4705.3  266.40  4734.1  266.19
  4818.1  265.34  4934.5  264.21  5424.5  260.51  5538.5  260.01  5541.2  259.51
  5544.5  260.01  5581.2  260.21  5653.3  260.80  5795.7  263.23  5881.0  265.15
  5921.6  266.61  5927.2  266.36  5966.3  268.12  5971.9  267.85  5988.7  268.87
  5994.3  268.64  6011.0  269.76  6016.6  269.50  6033.4  270.63  6061.4  271.25
  6078.1  272.45  6083.7  272.27  6234.7  278.93  6328.5  282.03  6338.1  282.43
#Mann=14,-1,0
  4206.9     0.1       0  4479.7    0.05       0  4533.8     0.1       0
  4705.3    0.08       0  4734.1     0.1       0  4818.1    0.08       0
  4934.5     0.1       0  5424.5    0.08       0  5538.5    0.07       0
  5544.5    0.08       0  5581.2     0.1       0  5795.7    0.05       0
  5881.0    0.08       0  6328.5    0.15       0
Bank Sta=5538.5,5544.5
Exp/Cntr=0.3,0.1

Type RM Length L Ch R = 1,7069,562,562,562
BEGIN DESCRIPTION:
WOLF PEN CREEK 11.0
END DESCRIPTION:
XS GIS Cut Line= 3
      3565444.19     10213824.98      3565694.19     10213424.98
      3566413.53     10212105.64
#Sta/Elev= 30
  4153.4  267.70  4381.4  266.06  4429.8  264.84  4483.8  264.31  4596.9  262.95
  4629.0  262.01  4816.9  260.91  4851.3  260.87  4949.0  258.30  4965.2  249.83
  4970.9  252.90  5000.1  246.50  5002.9  246.00  5006.1  246.50  5025.0  253.76
  5036.0  253.66  5061.7  258.30  5090.5  259.28  5235.6  255.53  5341.1  257.57
  5362.9  255.03  5422.8  257.48  5428.4  255.54  5444.6  257.78  5450.3  255.81
  5466.4  258.42  5488.3  255.71  5624.1  261.04  5989.5  268.83  6127.8  268.29
#Mann=13,-1,0
  4153.4     0.1       0  4381.4    0.08       0  4429.8     0.1       0
  4483.8    0.08       0  4596.9     0.1       0  4629.0    0.08       0
  4816.9     0.1       0  4851.3    0.08       0  5000.1    0.07       0
  5006.1    0.08       0  5036.0     0.1       0  5235.6    0.05       0
  5624.1    0.08       0
Bank Sta=5000.1,5006.1
Exp/Cntr=0.3,0.1

Type RM Length L Ch R = 1,6507,985,985,985
BEGIN DESCRIPTION:
WOLF PEN CREEK 10.0
END DESCRIPTION:
XS GIS Cut Line= 3
      3566226.59     10213734.83      3566421.30     10213275.90
      3566442.11     10212341.66
#Sta/Elev= 30
  4322.1  266.90  4345.4  266.00  4391.2  261.22  4451.0  257.04  4461.6  257.18
  4499.5  257.16  4527.4  256.58  4770.9  256.47  4809.4  255.49  4820.2  254.17
  4858.1  252.16  4964.9  252.70  4974.9  251.45  4991.9  243.79  4994.7  243.29
  4997.9  243.79  5014.9  251.25  5024.9  252.91  5044.9  249.84  5065.0  251.29
  5080.7  251.18  5085.7  251.76  5135.0  251.90  5255.0  250.65  5325.0  254.86
  5485.1  258.64  5525.1  260.45  5565.1  263.39  5595.1  263.62  5755.1  267.75
#Mann=7,-1,0
  4322.1    0.15       0  4391.2     0.1       0  4461.6    0.08       0
  4499.5     0.1       0  4858.1    0.05       0  4991.9    0.04       0
  4997.9    0.05       0
Bank Sta=4991.9,4997.9
Exp/Cntr=0.3,0.1

Type RM Length L Ch R = 1,5522,789,789,789
BEGIN DESCRIPTION:
WOLF PEN CREEK 8.0
END DESCRIPTION:
XS GIS Cut Line= 3
      3566792.11     10213941.64      3567007.85     10213062.93
      3567042.11     10212691.61
#Sta/Elev= 30
  4284.7  263.23  4341.6  261.28  4377.4  259.54  4515.9  259.83  4542.0  259.06
  4573.0  257.61  4599.0  252.04  4614.2  251.03  4665.7  248.83  4693.1  250.30
  4736.1  249.98  4978.2  250.74  4984.9  247.78  4992.2  241.57  4994.9  241.07
  4998.2  241.57  5005.5  242.70  5014.6  248.03  5019.8  249.25  5026.1  250.29
  5043.1  249.97  5102.9  248.76  5143.9  249.66  5200.8  250.33  5241.0  249.54
  5271.1  250.59  5397.9  259.66  5522.2  263.35  5547.3  265.19  5562.4  265.31
#Mann=10,-1,0
  4284.7    0.05       0  4341.6    0.08       0  4542.0    0.05       0
  4693.1    0.08       0  4736.1    0.05       0  4992.2    0.04       0
  4998.2    0.05       0  5043.1    0.16       0  5143.9    0.05       0
  5547.3    0.08       0
Bank Sta=4992.2,4998.2
Exp/Cntr=0.3,0.1

Type RM Length L Ch R = 1,4733,591,591,591
BEGIN DESCRIPTION:
WOLF PEN CREEK 7.0
END DESCRIPTION:
XS GIS Cut Line= 3
      3567210.98     10214114.99      3567492.11     10213191.64
      3567542.10     10212841.69
#Sta/Elev= 30
  4024.4  257.42  4090.6  253.95  4183.4  255.83  4194.8  255.62  4226.5  255.86
  4290.1  252.97  4350.6  252.53  4492.4  249.15  4655.1  251.76  4749.2  247.14
  4791.0  248.53  4874.6  246.72  4902.2  248.01  4973.2  248.13  4979.1  246.49
  4987.0  241.20  4992.1  241.20  4996.7  237.94  4999.4  237.44  5002.7  237.94
  5009.8  239.65  5019.9  246.64  5030.0  248.02  5054.2  247.78  5080.5  248.30
  5110.8  252.58  5152.9  255.06  5251.6  259.43  5312.8  263.38  5343.1  263.46
#Mann=8,-1,0
  4024.4    0.05       0  4183.4     0.1       0  4194.8    0.05       0
  4996.7    0.04       0  5002.7    0.05       0  5054.2    0.12       0
  5152.9    0.16       0  5251.6    0.05       0
Bank Sta=4996.7,5002.7
Exp/Cntr=0.3,0.1

Type RM Length L Ch R = 1,4142,1104,1104,1104
BEGIN DESCRIPTION:
WOLF PEN CREEK 6.0
END DESCRIPTION:
XS GIS Cut Line= 3
      3567658.89     10213990.03      3567925.44     10212929.14
      3568075.45     10212779.14
#Sta/Elev= 30
  4237.7  253.12  4287.6  253.24  4477.5  250.11  4636.9  246.39  4656.1  246.82
  4683.4  247.01  4772.2  246.91  4823.8  245.19  4834.1  246.31  4883.7  247.09
  4950.4  246.75  4971.2  247.11  4978.4  246.25  4996.0  237.12  4998.8  236.62
  5002.0  237.12  5012.3  240.41  5019.7  245.05  5040.3  247.12  5071.2  246.84
  5102.1  244.09  5111.8  245.31  5184.6  248.12  5225.9  253.09  5259.1  254.59
  5287.7  259.17  5312.4  259.48  5334.5  259.57  5412.3  263.26  5543.7  263.48
#Mann=8,-1,0
  4237.7    0.05       0  4656.1    0.12       0  4683.4    0.05       0
  4950.4    0.12       0  4996.0    0.07       0  5002.0    0.12       0
  5111.8    0.05       0  5312.4    0.08       0
Bank Sta=4996,5002
Exp/Cntr=0.3,0.1