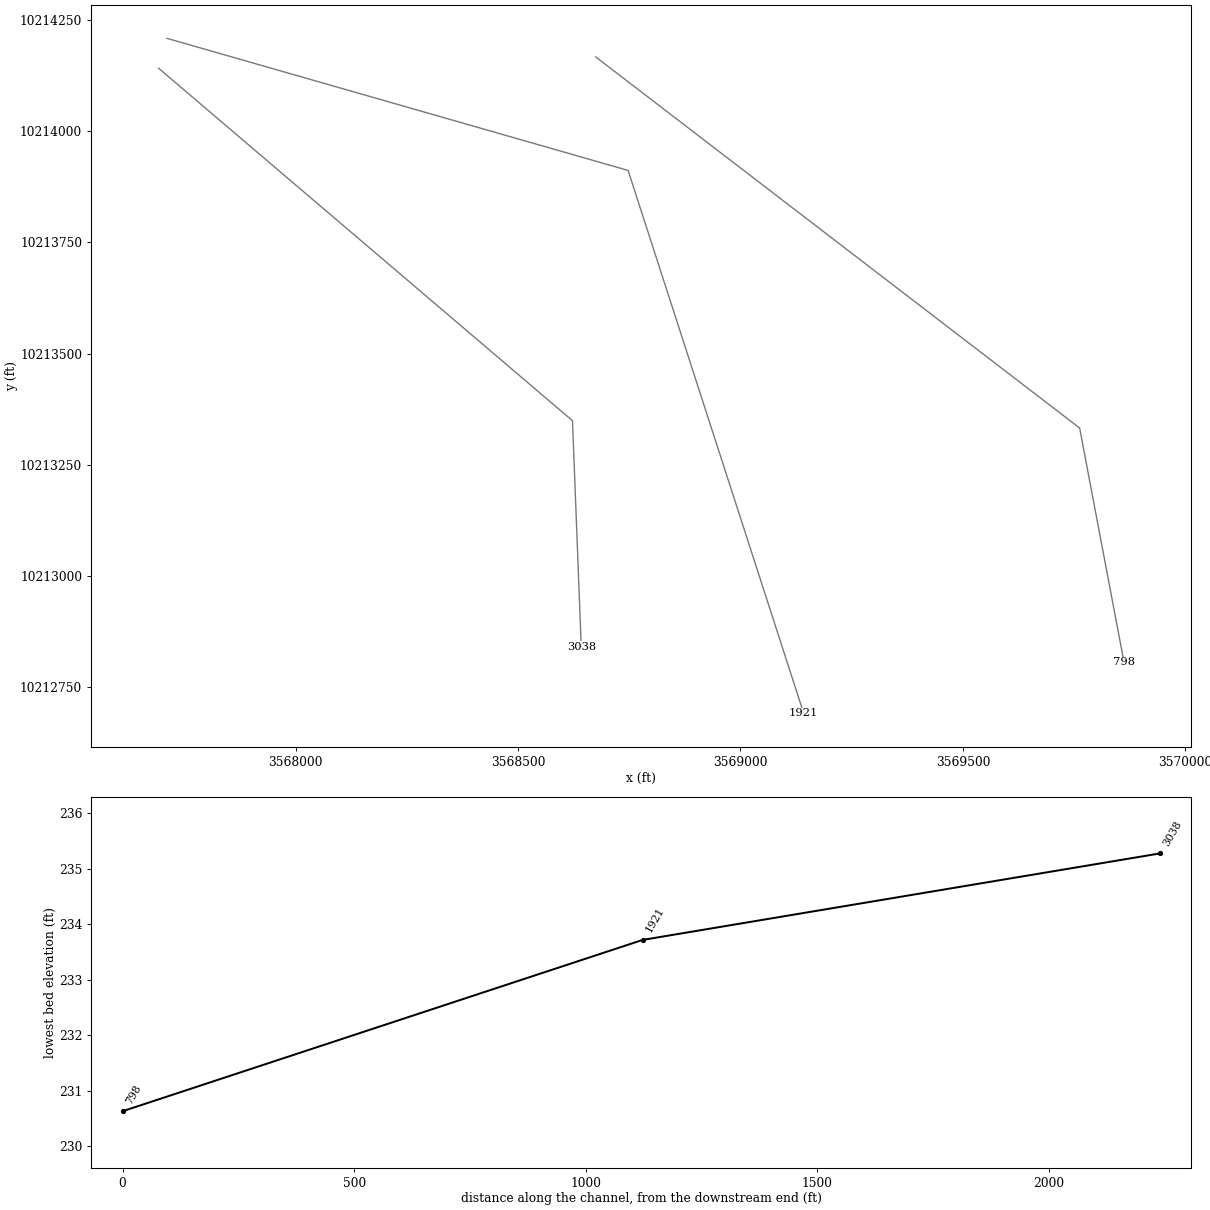
HEC-RAS study WOLF PEN CREEK.prj: WOLF PEN CREEK Base Level Engineering

--- WOLF PEN CREEK.g01 (geometry) --- (continued)

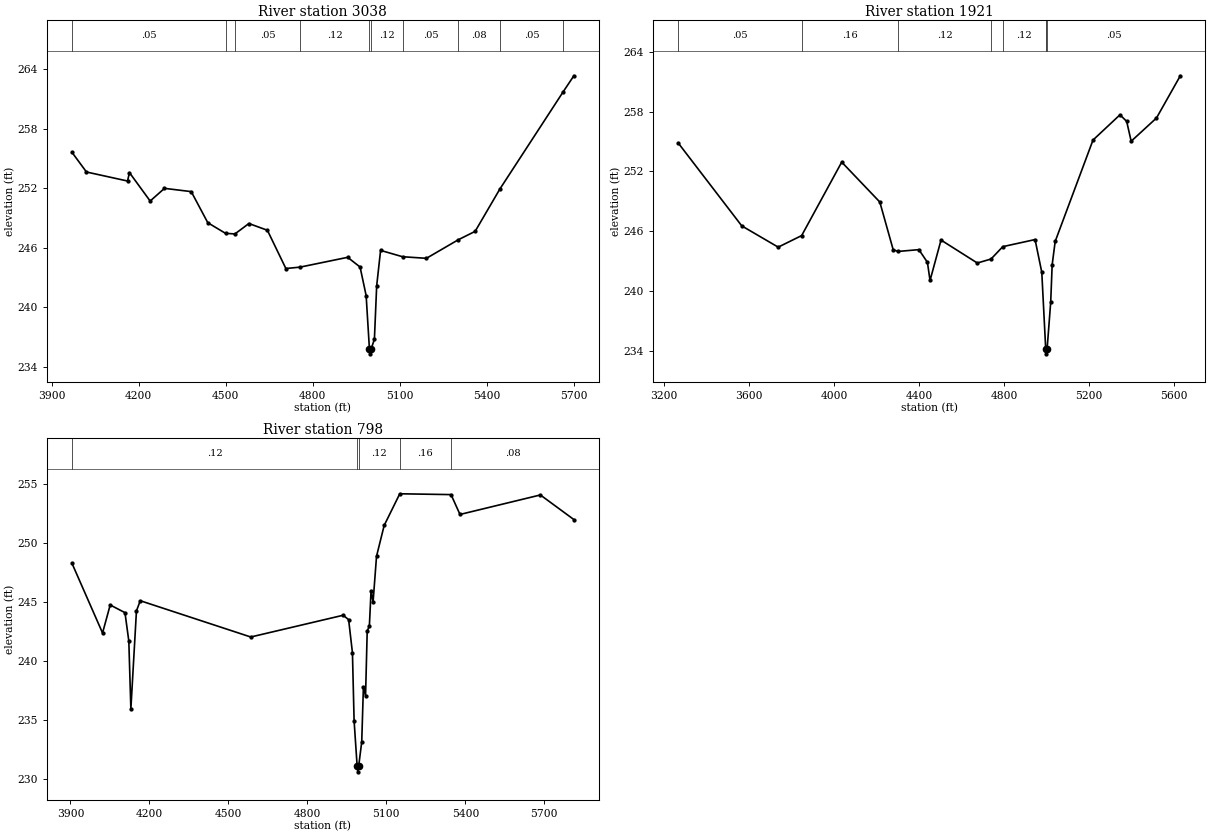
Type RM Length L Ch R = 1,3038,1117,1117,1117
BEGIN DESCRIPTION:
WOLF PEN CREEK 4.0
END DESCRIPTION:
XS GIS Cut Line= 3
      3567692.12     10214141.63      3568622.43     10213349.39
      3568642.11     10212841.61
#Sta/Elev= 30
  3970.3  255.62  4020.3  253.63  4161.9  252.72  4168.5  253.57  4239.9  250.70
  4289.3  251.98  4381.5  251.65  4438.6  248.51  4499.7  247.44  4532.1  247.38
  4580.3  248.43  4644.0  247.75  4707.7  243.89  4756.6  244.03  4920.7  245.02
  4963.5  244.04  4984.4  241.16  4995.7  235.78  4998.4  235.28  5001.7  235.78
  5012.9  236.75  5020.7  242.14  5034.2  245.72  5109.9  245.08  5192.2  244.92
  5301.9  246.79  5360.1  247.64  5445.1  251.90  5664.2  261.75  5700.4  263.34
#Mann=10,-1,0
  3970.3    0.05       0  4499.7    0.16       0  4532.1    0.05       0
  4756.6    0.12       0  4995.7    0.07       0  5001.7    0.12       0
  5109.9    0.05       0  5301.9    0.08       0  5445.1    0.05       0
  5664.2    0.08       0
Bank Sta=4995.7,5001.7
Exp/Cntr=0.3,0.1

Type RM Length L Ch R = 1,1921,1123,1123,1123
BEGIN DESCRIPTION:
WOLF PEN CREEK 3.0
END DESCRIPTION:
XS GIS Cut Line= 3
      3567710.93     10214208.78      3568747.43     10213911.89
      3569142.11     10212691.62
#Sta/Elev= 30
  3268.3  254.82  3566.3  246.54  3737.6  244.41  3848.0  245.57  4036.4  252.93
  4215.6  248.93  4278.5  244.15  4301.5  243.98  4399.3  244.16  4439.5  242.89
  4451.8  241.07  4503.5  245.12  4674.1  242.82  4738.7  243.22  4794.0  244.46
  4945.8  245.17  4977.4  241.89  4995.6  234.31  4996.5  234.22  4999.2  233.72
  5002.5  234.22  5019.4  238.92  5026.2  242.64  5040.4  244.98  5218.3  255.14
  5345.2  257.67  5376.7  257.01  5397.8  255.02  5516.9  257.35  5629.0  261.58
#Mann=8,-1,0
  3268.3    0.05       0  3848.0    0.16       0  4301.5    0.12       0
  4738.7    0.05       0  4794.0    0.12       0  4995.6    0.05       0
  4996.5    0.04       0  5002.5    0.05       0
Bank Sta=4996.5,5002.5
Exp/Cntr=0.3,0.1

Type RM Length L Ch R = 1,798,0,0,0
BEGIN DESCRIPTION:
WOLF PEN CREEK 1.0
END DESCRIPTION:
XS GIS Cut Line= 3
      3568674.50     10214167.11      3569762.25     10213332.96
      3569862.01     10212806.70
#Sta/Elev= 30
  3905.8  248.28  4022.0  242.38  4051.1  244.75  4107.2  244.10  4121.8  241.70
  4129.6  235.95  4150.8  244.25  4165.3  245.11  4585.0  242.04  4935.8  243.88
  4956.7  243.51  4971.2  240.71  4977.5  234.95  4989.0  231.13  4991.7  230.63
  4995.0  231.13  5006.5  233.17  5012.8  237.79  5021.0  237.06  5027.3  242.54
  5035.5  242.97  5041.9  245.96  5049.6  245.01  5062.7  248.87  5091.7  251.48
  5151.0  254.16  5345.7  254.09  5379.7  252.41  5685.0  254.06  5812.2  251.98
#Mann=5,-1,0
  3905.8    0.12       0  4989.0    0.07       0  4995.0    0.12       0
  5151.0    0.16       0  5345.7    0.08       0
Bank Sta=4989,4995
Exp/Cntr=0.3,0.1

Chan Stop Cuts=-1