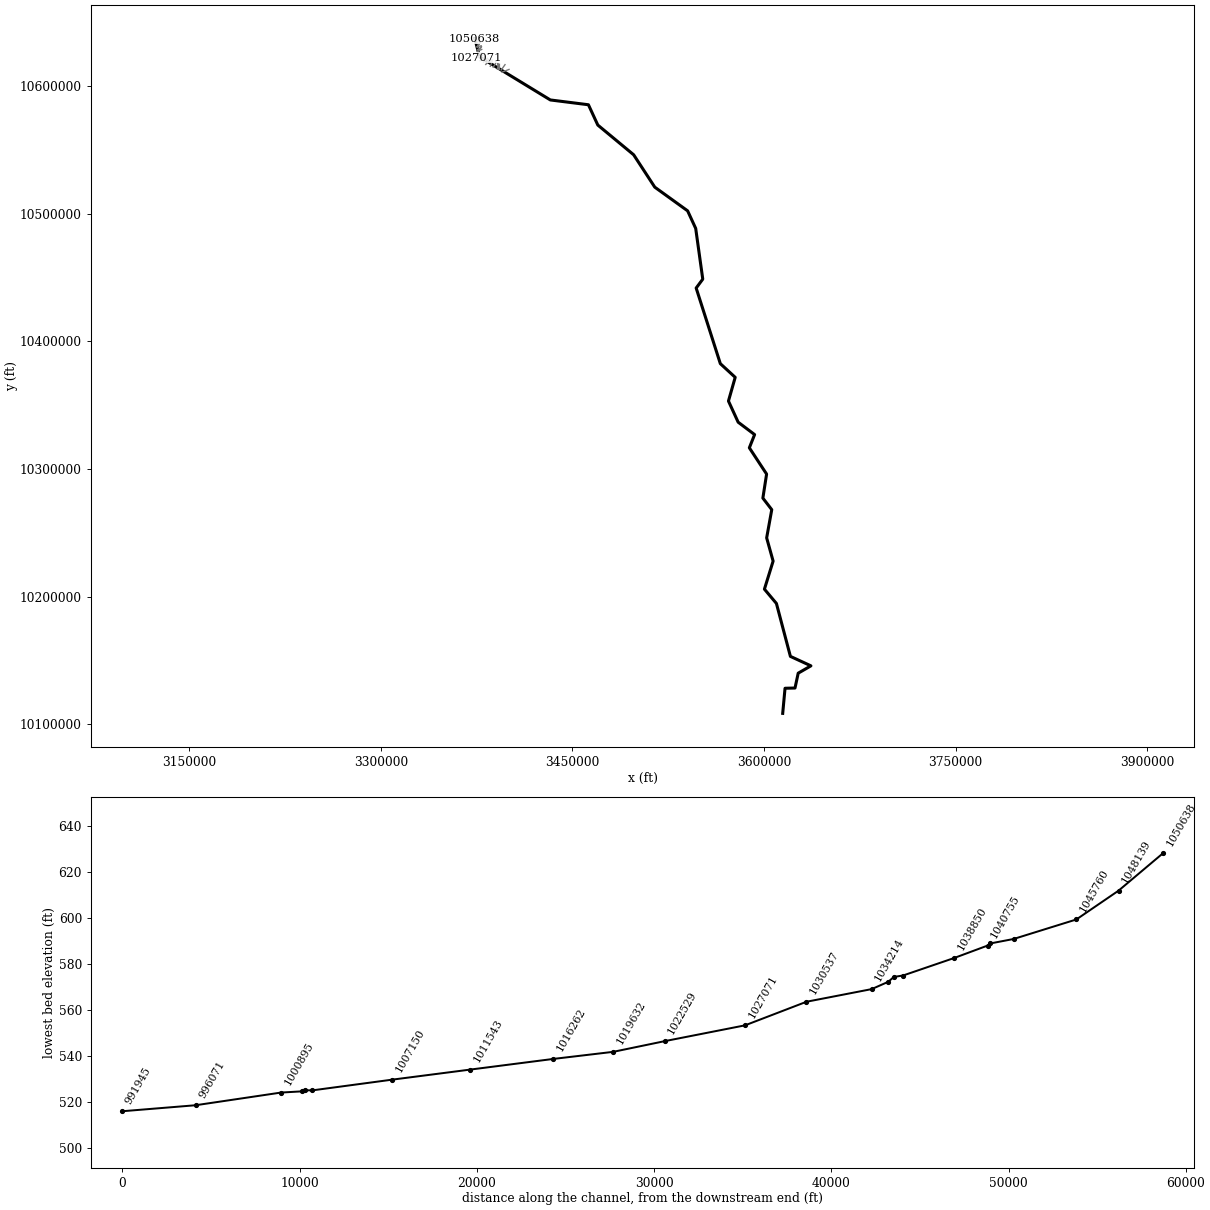
--- NAVASOTA RIVER.prj (project) ---

Proj Title=NAVASOTA RIVER Base Level Engineering
Current Plan=p01
Default Exp/Contr=0.3,0.1
English Units
Geom File=g01
Flow File=f01
Plan File=p01
Y Axis Title=Elevation
X Axis Title(PF)=Main Channel Distance
X Axis Title(XS)=Station
BEGIN DESCRIPTION:
NAVASOTA RIVER
END DESCRIPTION:
DSS File=dss
DSS Export Rating Curves= 0
DSS Export Rating Curve Sorted= 0
DSS Export Volume Flow Curves= 0
DXF OffsetX= 0
DXF OffsetY= 0
DXF ScaleX= 1
DXF ScaleY= 10

--- NAVASOTA RIVER.p01 (plan) ---

Plan Title=Multiple Run
Program Version=4.10
Short Identifier=Multiple Run
Geom File=g01
Flow File=f01
Subcritical Flow
K Sum by GR= 0
Std Step Tol= 0.01
Critical Tol= 0.01
Num of Std Step Trials= 20
Max Error Tol= 0.3
Flow Tol Ratio= 0.001
Split Flow NTrial= 30
Split Flow Tol= 0.02
Split Flow Ratio= 0.02
Log Output Level= 0
Friction Slope Method= 1
Unsteady Friction Slope Method= 2
Unsteady Bridges Friction Slope Method= 1
Parabolic Critical Depth
Global Vel Dist= 1 , 1 , 1
Global Log Level= 0
CheckData=True
Encroach Param=-1 ,0,0, 0
BEGIN DESCRIPTION:
Multiple Run
END DESCRIPTION:
Computation Interval=1HOUR
Output Interval=1HOUR
Run HTab= 0
Run UNet= 0
Run PostProcess= 0
Run WQNet= 0
UNET Theta= 1
UNET Theta Warmup= 1
UNET ZTol= 0.02
UNET ZSATol= 0.05
UNET MxIter= 20
UNET MaxInSteps= 0
UNET DtIC= 0
UNET DtMin= 0
UNET MaxCRTS= 20
UNET WFStab= 2
UNET SFStab= 1
UNET WFX= 1
UNET SFX= 1
UNET DSS MLevel= 4
UNET DZMax Abort= 100
UNET Convert EG Bridges= 0
UNET Use Existing IB Tables=-1
UNET Froude Reduction=False
UNET Froude Limit= 1
UNET Froude Power= 10
UNET Time Slicing=0,0, 5
UNET Junction Losses=0
Instantaneous Interval=1HOUR
DSS File=dss
Write IC File= 0
Write IC File at Sim End=0
Echo Input=False
Echo Parameters=False
Echo Output=False
Write Detailed= 0
WQ AD Non Conservative
WQ ULTIMATE=-1
WQ Max Comp Step=1HOUR
WQ Output Interval=15MIN
WQ Output Selected Increments= 0
WQ Output face flow=0
WQ Output face velocity=0
WQ Output face area=0
WQ Output face dispersion=0
WQ Output cell volume=0
WQ Output cell surface area=0
WQ Output cell continuity=0
WQ Output cumulative cell continuity=0
WQ Output face conc=0
WQ Output face dconc_dx=0
WQ Output face courant=0
WQ Output face peclet=0
WQ Output face adv mass=0
WQ Output face disp mass=0
WQ Output cell mass=0
WQ Output cell source sink temp=0
WQ Output cell source sink nsm=0
WQ Output MaxMinRange=-1
WQ Daily Max Min Mean=-1
WQ Daily Range=0
WQ Daily Time=0
WQ Create Restart=0
WQ Fixed Restart=0
WQ System Summary=0
WQ Use Fixed Temperature=0
Sorting and Armoring Iterations= 10
XS Update Threshold= 0.02
Hydraulics Update Threshold= 0.02
Energy Slope Method= 1
Volume Change Method= 0
XS Weighting Method= 0
Number of US Weighted Cross Sections= 1
Number of DS Weighted Cross Sections= 1
Upstream XS Weight=0.25
Main XS Weight=0.5
Downstream XS Weight=0.25
Number of DS XS's Weighted with US Boundary= 1
Upstream Boundary Weight= 1
Weight of XSs Associated with US Boundary= 0
Number of US XS's Weighted with DS Boundary= 1
Downstream Boundary Weight= 0.5
Weight of XSs Associated with DS Boundary= 0.5
Sediment Output Level= 4
Mass or Volume Output= 0
Output Increment Type= 1
Profile and TS Output Increment= 10
XS Output Flag= 0
XS Output Increment= 10
Disregard all LS=0
Disregard all Conn=0
Disregard all Breaches=0
Disregard all Pumps=0

--- NAVASOTA RIVER.f01 (steady flow) ---

Flow Title=Multiple
Program Version=4.10
Number of Profiles= 7
Profile Names=10-year,25-year,50-year,1pct_min,100-year,1pct_plu,500-year
River Rch & RM=NAVASOTA RIVER,Reach-1         ,1050638
    5528    8142   10433    9688   13101   17718   20649
River Rch & RM=NAVASOTA RIVER,Reach-1         ,1002661
    9518   14092   18125   16869   22813   30852   36091
River Rch & RM=NAVASOTA RIVER,Reach-1         ,959588
   12723   18781   24112   22384   30272   40940   47617
River Rch & RM=NAVASOTA RIVER,Reach-1         ,917458
   13813   20371   26141   24251   32797   44355   51507
River Rch & RM=NAVASOTA RIVER,Reach-1         ,897609
   18214   26912   34593   32136   43460   58775   68399
River Rch & RM=NAVASOTA RIVER,Reach-1         ,881765
   20011   29433   37723   34932   47242   63889   73851
River Rch & RM=NAVASOTA RIVER,Reach-1         ,867178
   23603   34852   44803   41613   56277   76108   88472
River Rch & RM=NAVASOTA RIVER,Reach-1         ,828378
   27152   39922   51188   47413   64121   86716  100197
River Rch & RM=NAVASOTA RIVER,Reach-1         ,765004
   29676   43559   55800   51632   69827   94433  108861
River Rch & RM=NAVASOTA RIVER,Reach-1         ,758530
   30940   45151   57619   53103   71816   97123  111045
River Rch & RM=NAVASOTA RIVER,Reach-1         ,723554
   31368   45724   58306   53694   72616   98204  112099
River Rch & RM=NAVASOTA RIVER,Reach-1         ,711186
   36803   53663   68473   63097   85331  115401  131837
River Rch & RM=NAVASOTA RIVER,Reach-1         ,708504
   38717   56435   72003   66343   89722  121338  138573
River Rch & RM=NAVASOTA RIVER,Reach-1         ,705897
   40558   58913   74997   68944   93238  126094  143315
River Rch & RM=NAVASOTA RIVER,Reach-1         ,674757
   44422   64803   82753   76318  103211  139581  159651
River Rch & RM=NAVASOTA RIVER,Reach-1         ,626468
   51105   74409   94932   87469  118292  159976  182578
River Rch & RM=NAVASOTA RIVER,Reach-1         ,576576
   53415   77708   99098   91269  123431  166926  190323
River Rch & RM=NAVASOTA RIVER,Reach-1         ,567952
   57310   83195  105963   97468  131815  178264  202703
River Rch & RM=NAVASOTA RIVER,Reach-1         ,538096
   59259   85981  109488  100690  136171  184156  209293
River Rch & RM=NAVASOTA RIVER,Reach-1         ,524942
   59962   86886  110545  101573  137366  185772  210751
River Rch & RM=NAVASOTA RIVER,Reach-1         ,500676
   59804   86450  109816  100746  136247  184259  208382
River Rch & RM=NAVASOTA RIVER,Reach-1         ,449579
   58982   84886  107523   98378  133045  179928  202421
River Rch & RM=NAVASOTA RIVER,Reach-1         ,374483
   59405   85205  107712   98398  133072  179964  201894
River Rch & RM=NAVASOTA RIVER,Reach-1         ,333189
   59243   84799  107061   97689  132113  178668  199985
River Rch & RM=NAVASOTA RIVER,Reach-1         ,287020
   58947   84189  106141   96721  130804  176897  197487
River Rch & RM=NAVASOTA RIVER,Reach-1         ,222007
   59601   85030  107139   97594  131985  178494  199145
River Rch & RM=NAVASOTA RIVER,Reach-1         ,205659
   59745   85081  107086   97456  131798  178241  198514
River Rch & RM=NAVASOTA RIVER,Reach-1         ,175379
   59862   85126  107047   97341  131643  178032  197972
River Rch & RM=NAVASOTA RIVER,Reach-1         ,146607
   61272   87030  109379   99425  134461  181843  202065
River Rch & RM=NAVASOTA RIVER,Reach-1         ,140999
   61681   87476  109835   99756  134908  182448  202396
River Rch & RM=NAVASOTA RIVER,Reach-1         ,90862
   61708   87397  109642   99499  134561  181979  201550
River Rch & RM=NAVASOTA RIVER,Reach-1         ,62172
   60964   86187  107992   97884  132377  179024  197802
Boundary for River Rch & Prof#=NAVASOTA RIVER,Reach-1         , 1
Up Type= 0
Dn Type= 3
Dn Slope=0.0002
Boundary for River Rch & Prof#=NAVASOTA RIVER,Reach-1         , 2
Up Type= 0
Dn Type= 3
Dn Slope=0.0002
Boundary for River Rch & Prof#=NAVASOTA RIVER,Reach-1         , 3
Up Type= 0
Dn Type= 3
Dn Slope=0.0002
Boundary for River Rch & Prof#=NAVASOTA RIVER,Reach-1         , 4
Up Type= 0
Dn Type= 3
Dn Slope=0.0002
Boundary for River Rch & Prof#=NAVASOTA RIVER,Reach-1         , 5
Up Type= 0
Dn Type= 3
Dn Slope=0.0002
Boundary for River Rch & Prof#=NAVASOTA RIVER,Reach-1         , 6
Up Type= 0
Dn Type= 3
Dn Slope=0.0002
Boundary for River Rch & Prof#=NAVASOTA RIVER,Reach-1         , 7
Up Type= 0
Dn Type= 3
Dn Slope=0.0002
DSS Import GetInterval= 0
DSS Import GetPeak= 0
DSS Import FillOption= 0

--- NAVASOTA RIVER.g01 (geometry) ---

Geom Title=Existing Conditions
Program Version=4.10

River Reach=NAVASOTA RIVER  ,Reach-1
Reach XY= 30
      3373613.88     10637081.88      3377291.82     10622762.29
      3432735.66     10588968.93      3462547.55      10585216.5
      3469891.27     10569313.84       3497960.1     10546049.67
      3514513.13      10520683.4      3540214.28      10502152.1
      3546540.19     10488396.45      3552071.74     10448671.04
      3546904.09      10441707.3      3565826.63     10382506.84
      3577471.26     10371789.89      3572185.43     10353233.25
      3579791.47     10336664.04      3592664.73     10326964.82
      3588547.16     10316618.68      3602050.56     10296043.66
      3599134.97     10277231.32      3606090.45     10268186.61
      3602096.35     10246095.16      3607158.21     10227902.14
      3600349.03     10205945.66      3609740.18     10194744.97
      3620689.91     10153305.16      3636760.07     10145896.23
      3626796.53     10140154.91      3624293.93     10128523.84
      3616490.97     10128351.09      3614662.11     10108681.64

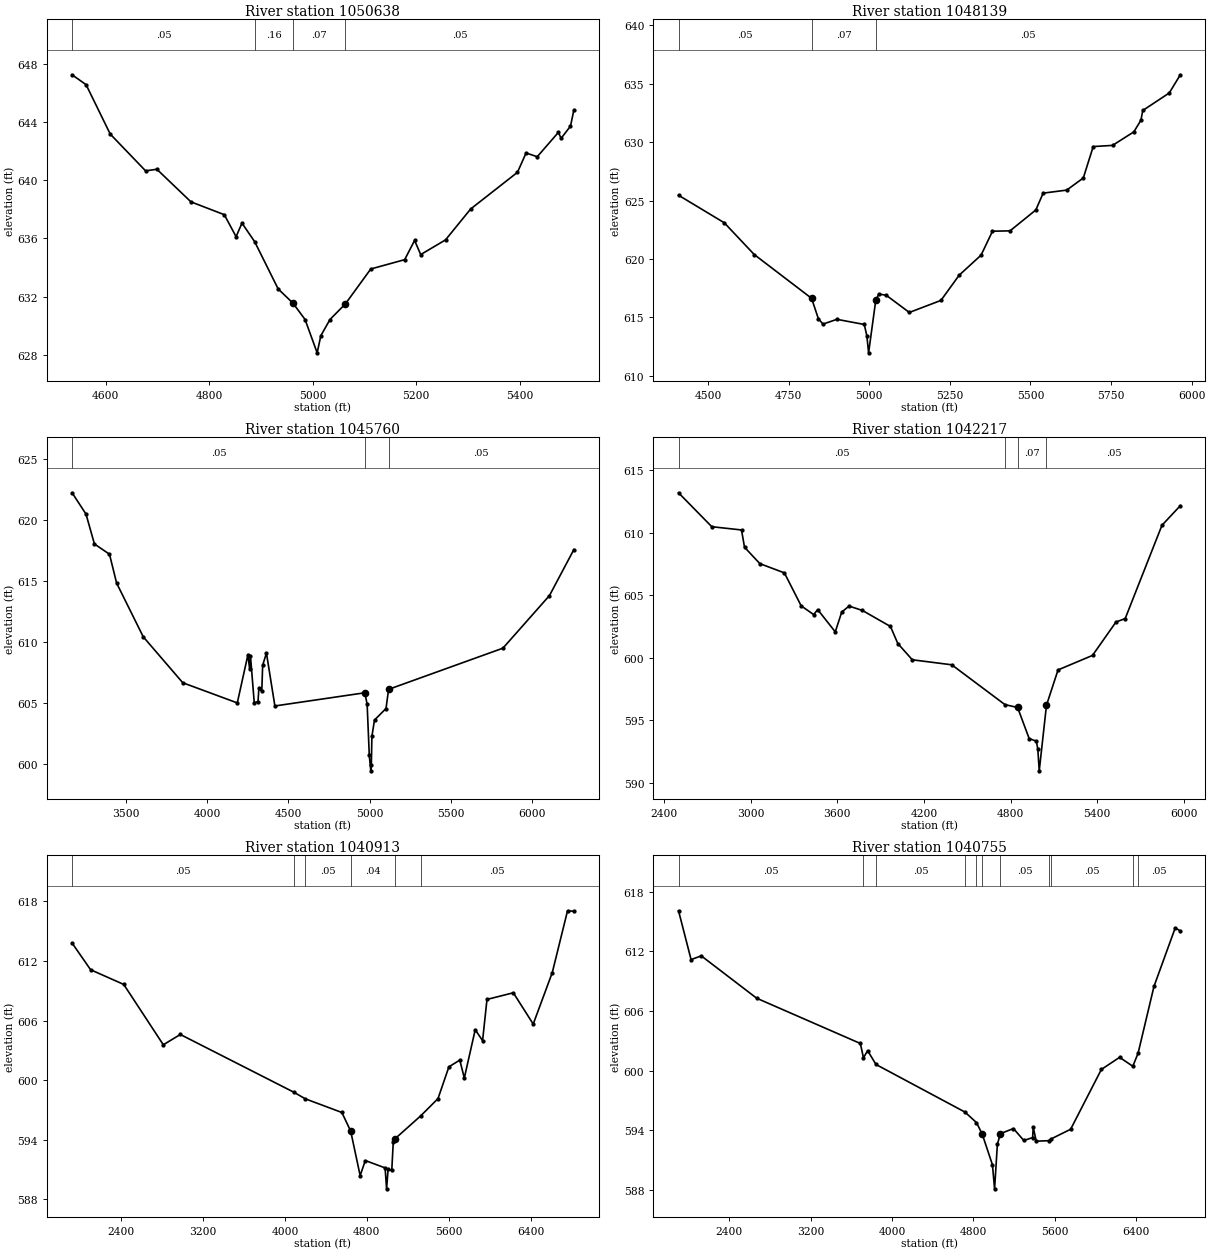
Type RM Length L Ch R = 1 ,1050638 ,2499,2499,2499
BEGIN DESCRIPTION:
NAVASOTA RIVER 001
END DESCRIPTION:
XS GIS Cut Line= 3
      3374052.01     10637217.55       3373626.9     10637029.37
      3373156.08     10636847.01
#Sta/Elev= 30
  4535.1  647.24  4562.2  646.56  4608.8  643.17  4677.2  640.64    4699  640.75
  4764.9  638.51  4829.3  637.63  4852.1  636.12  4863.5  637.05  4888.1  635.77
  4933.4  632.53  4962.1  631.55  4985.4  630.43  5008.8  628.14  5015.9  629.32
  5033.6  630.43  5063.5  631.51  5112.4   633.9  5177.9  634.54  5197.1  635.86
  5208.9  634.89  5256.9   635.9  5305.4  638.02  5395.9  640.54  5412.6  641.87
  5434.1  641.61  5474.9  643.28  5480.3  642.88  5498.4  643.71  5504.9  644.82
#Mann= 4 ,-1 , 0
  4535.1     .05       0  4888.1     .16       0  4962.1     .07       0
  5063.5     .05       0
Bank Sta=4962.1,5063.5
XS Rating Curve= 0 ,0
Exp/Cntr=0.3,0.1

Type RM Length L Ch R = 1 ,1048139 ,2379,2379,2379
BEGIN DESCRIPTION:
NAVASOTA RIVER 002
END DESCRIPTION:
XS GIS Cut Line= 3
      3375352.12     10635911.85      3374888.18     10635544.28
      3374036.46     10635090.64
#Sta/Elev= 30
  4408.1  625.45  4550.1  623.09    4643  620.37  4820.9  616.62  4841.9  614.88
  4856.2  614.41  4899.4  614.82  4984.4  614.38  4992.4  613.41  4997.8  611.95
  5020.1  616.47  5029.5  616.98  5052.2  616.89  5124.2  615.41  5222.2  616.44
  5278.8   618.6  5346.8  620.32  5382.2  622.37  5436.7   622.4  5516.7  624.19
  5539.4  625.63  5612.5  625.89    5664  626.93  5694.7  629.62  5754.7  629.72
  5820.8  630.88  5842.8  631.88  5848.4  632.71  5930.6  634.21    5965  635.77
#Mann= 3 , 0 , 0
  4408.1     .05       0  4820.9     .07       0  5020.1     .05       0
Bank Sta=4820.9,5020.1
XS Rating Curve= 0 ,0
Exp/Cntr=0.3,0.1

Type RM Length L Ch R = 1 ,1045760 ,3543,3543,3543
BEGIN DESCRIPTION:
NAVASOTA RIVER 003
END DESCRIPTION:
XS GIS Cut Line= 3
      3377872.94     10635302.62      3376475.41     10634681.98
      3375108.18     10633922.41
#Sta/Elev= 30
    3166  622.21  3251.8  620.47  3303.8  618.02  3396.7  617.18  3440.5  614.82
  3604.8  610.42  3848.4  606.66  4184.5  605.01  4250.2  608.96  4260.2  607.82
  4265.7  608.86    4289  605.03  4312.2  605.12  4317.7  606.22  4335.5  605.97
  4340.9  608.09  4364.2  609.09  4416.2  604.76  4970.8  605.84  4984.9   604.9
  4998.2  600.71  5007.5  599.45  5010.8  599.95  5014.3  602.28  5030.3  603.61
  5101.2  604.55  5117.2  606.12  5821.9  609.49    6109   613.8  6259.2  617.56
#Mann= 3 , 0 , 0
    3166     .05       0  4970.8     .07       0  5117.2     .05       0
Bank Sta=4970.8,5117.2
XS Rating Curve= 0 ,0
Exp/Cntr=0.3,0.1

Type RM Length L Ch R = 1 ,1042217 ,1304,1304,1304
BEGIN DESCRIPTION:
NAVASOTA RIVER 005
END DESCRIPTION:
XS GIS Cut Line= 5
      3378105.73     10634593.36      3377636.96     10634061.66
       3376861.7     10632932.85      3376132.53     10632928.51
      3375656.45     10633395.94
#Sta/Elev= 30
  2500.3  613.18  2730.5  610.47  2936.3  610.21  2957.2  608.83  3063.4  607.52
  3233.4  606.78  3349.4  604.15    3436  603.45  3463.9  603.85  3585.6  602.07
  3630.2  603.65    3681  604.13  3773.7  603.78  3967.9   602.5  4018.6  601.14
    4119  599.84  4392.2  599.44  4760.5  596.26  4848.1  596.03  4928.1  593.55
  4978.1  593.34  4988.1   592.7  4997.9  590.97  5048.1  596.21  5128.1  599.03
  5366.8  600.19  5529.5  602.86  5593.1  603.13  5847.6  610.58  5974.9  612.15
#Mann= 4 ,-1 , 0
  2500.3     .05       0  4760.5     .16       0  4848.1     .07       0
  5048.1     .05       0
#Block Obstruct= 3 ,-1
 5047.62 5130.84  595.29 5051.26 5115.05  594.75 5119.91 5148.46  594.08
Bank Sta=4848.1,5048.1
XS Rating Curve= 0 ,0
Exp/Cntr=0.3,0.1

Type RM Length L Ch R = 1 ,1040913 ,158,158,158
BEGIN DESCRIPTION:
NAVASOTA RIVER 004
END DESCRIPTION:
XS GIS Cut Line= 3
      3378118.23     10634589.38      3376342.18     10632073.64
        3375266.     10630601.69
#Sta/Elev= 30
  1920.5  613.81  2101.7  611.12  2425.5  609.64  2812.1  603.56  2978.3   604.6
  4088.1  598.78  4198.9  598.12  4556.8  596.74    4643  594.86  4735.3  590.38
  4785.8   591.9  4979.1  591.16  4993.6  589.05  5008.6  591.03  5044.2   590.9
  5058.8  593.78  5073.5  594.07  5327.8  596.41  5495.9  598.14  5602.4  601.34
    5709  602.02    5753  600.21  5859.6  605.08  5931.5  603.98  5974.6  608.13
  6231.8   608.8  6426.3  605.65  6612.4  610.83  6761.5  617.06  6823.4  617.01
#Mann= 6 ,-1 , 0
  1920.5     .05       0  4088.1     .08       0  4198.9     .05       0
    4643     .04       0  5073.5     .05       0  5327.8     .05       0
Bank Sta=4643,5073.5
XS Rating Curve= 0 ,0
Exp/Cntr=0.3,0.1

Type RM Length L Ch R = 1 ,1040755 ,1905,1905,1905
BEGIN DESCRIPTION:
NAVASOTA RIVER 006
END DESCRIPTION:
XS GIS Cut Line= 3
       3378250.5     10634514.26      3376464.38     10631982.24
      3375429.05     10630465.52
#Sta/Elev= 30
  1901.4  616.07  2024.8  611.16  2124.9  611.54    2670  607.28  3689.7  602.73
    3720  601.29  3761.1  602.01  3843.5  600.62  4717.7  595.84  4831.7  594.78
  4887.8  593.63  4988.5  590.54  5009.6  588.12  5037.1  592.59  5066.7  593.67
  5195.4  594.18    5297  592.98  5383.8  593.27  5389.8  594.29  5419.7  592.91
  5540.4  592.96  5566.1  593.14  5757.7  594.11  6059.8  600.12  6239.3  601.34
  6368.9  600.44  6420.7  601.74  6577.3  608.47  6786.6  614.36  6836.4  614.04
#Mann= 11 ,-1 , 0
  1901.4     .05       0    3720     .08       0  3843.5     .05       0
  4717.7     .08       0  4831.7     .16       0  4887.8     .04       0
  5066.7     .05       0  5540.4     .08       0  5566.1     .05       0
  6368.9     .08       0  6420.7     .05       0
Bank Sta=4887.8,5066.7
XS Rating Curve= 0 ,0
Exp/Cntr=0.3,0.1

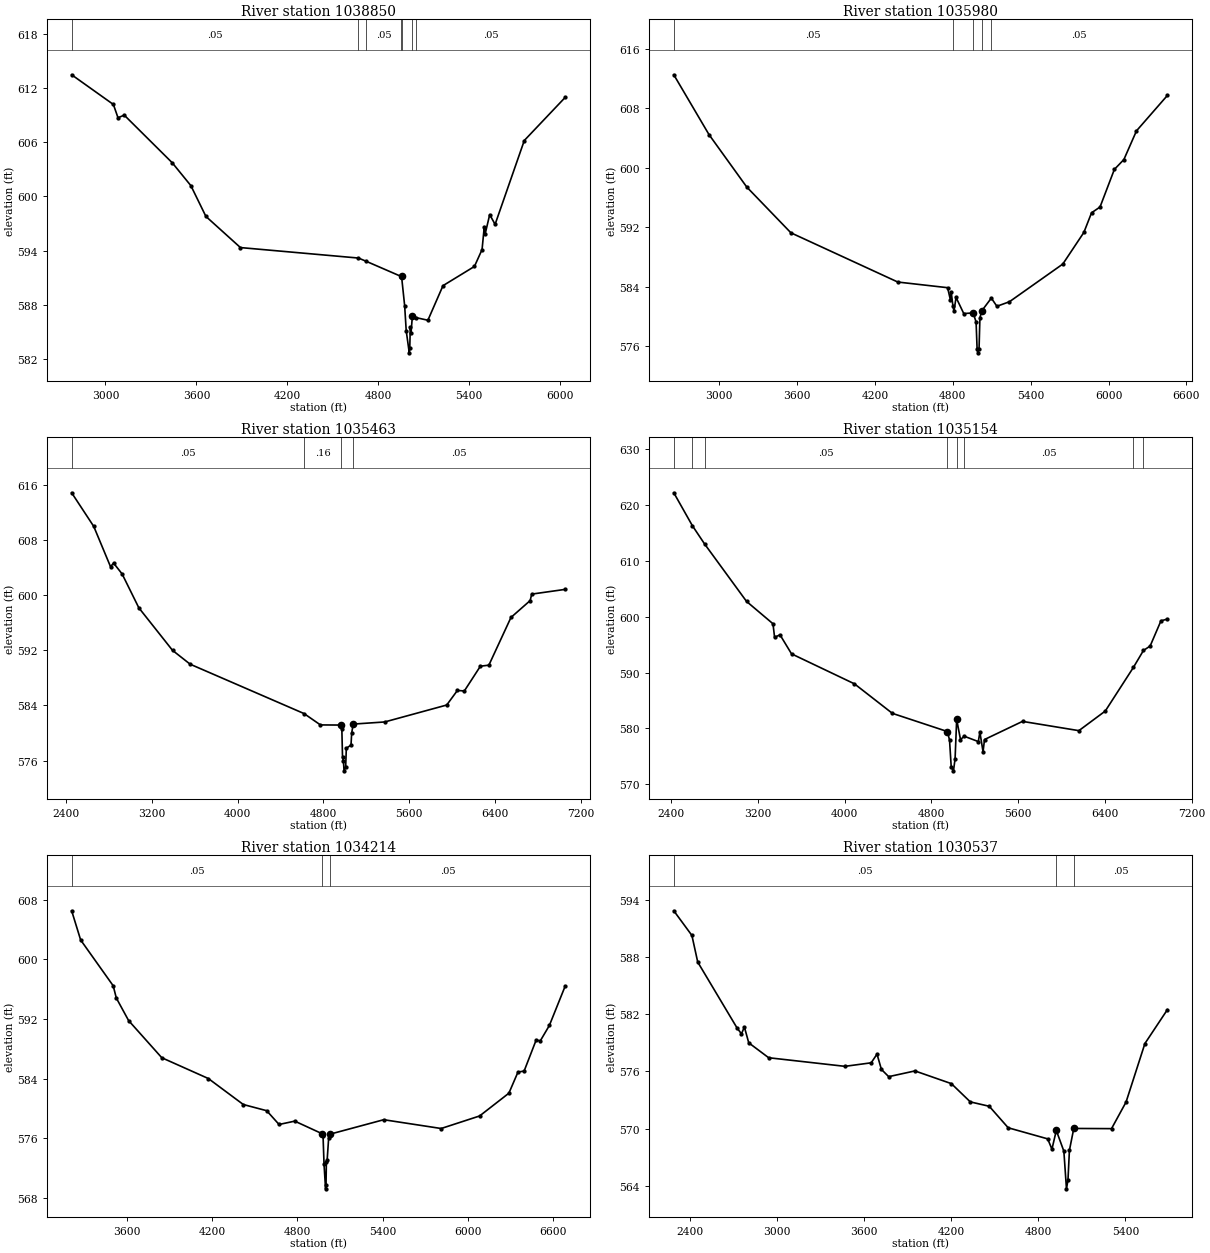
Type RM Length L Ch R = 1 ,1038850 ,2870,2870,2870
BEGIN DESCRIPTION:
NAVASOTA RIVER 007
END DESCRIPTION:
XS GIS Cut Line= 3
       3378601.5     10631361.16      3376218.66     10630855.08
       3375552.1     10630375.75
#Sta/Elev= 30
  2776.8  613.47  3052.2  610.18  3082.6  608.71  3123.8     609  3440.7  603.72
  3563.4  601.19  3662.7  597.78  3890.5  594.33  4669.1  593.17  4717.7  592.83
  4952.5  591.12  4953.7  591.14  4974.1  587.89  4984.4  585.12  5004.6  582.67
  5007.8  583.17  5011.3  585.49  5016.4  584.91  5025.3   586.8  5052.2  586.56
  5127.5  586.28  5227.1  590.11  5434.6  592.24  5484.9  594.11  5499.6  596.65
  5505.8  595.87  5535.3  597.98  5570.9   596.9  5763.6  606.19  6033.8  610.97
#Mann= 7 ,-1 , 0
  2776.8     .05       0  4669.1     .16       0  4717.7     .05       0
  4952.5     .16       0  4953.7     .07       0  5025.3     .16       0
  5052.2     .05       0
Bank Sta=4953.7,5025.3
XS Rating Curve= 0 ,0
Exp/Cntr=0.3,0.1

Type RM Length L Ch R = 1 ,1035980 ,517,517,517
BEGIN DESCRIPTION:
NAVASOTA RIVER 478
END DESCRIPTION:
XS GIS Cut Line= 3
       3378541.4     10630615.15      3377434.62     10629330.42
      3375595.72     10628302.55
#Sta/Elev= 30
  2650.7   612.5  2921.8  604.46  3212.6  597.41  3552.9  591.25  4376.3  584.63
    4760  583.87  4781.7  582.23  4787.5  583.31  4800.7  581.44  4809.2  580.72
  4825.2  582.56  4884.5  580.39  4956.5  580.48  4979.4  579.27  4987.3  575.61
  4992.8  575.11  5002.3  575.68    5009  579.85    5025   580.8  5096.9  582.47
  5139.8  581.37  5236.3  581.98  5647.5  587.05  5809.7   591.3    5869  593.94
  5934.2  594.72  6044.8  599.78    6118   601.1  6215.1  604.96  6453.1  609.72
#Mann= 5 ,-1 , 0
  2650.7     .05       0  4800.7     .16       0  4956.5     .07       0
    5025     .16       0  5096.9     .05       0
Bank Sta=4956.5,5025
XS Rating Curve= 0 ,0
Exp/Cntr=0.3,0.1

Type RM Length L Ch R = 1 ,1035463 ,309,309,309
BEGIN DESCRIPTION:
NAVASOTA RIVER 008
END DESCRIPTION:
XS GIS Cut Line= 2
      3378594.24     10630617.51      3375808.08     10626957.65
#Sta/Elev= 30
  2454.3  614.89  2660.3     610  2816.3  604.16  2845.4  604.67  2924.4   603.1
  3080.3  598.18  3394.3     592  3558.5  589.99  4619.7  582.82  4772.6  581.17
    4964  581.15  4972.2  580.55  4978.5  576.44  4986.8  575.95  4992.8   574.5
  5007.6  575.02  5013.9  577.78  5057.5  578.24  5063.8     580  5078.3  581.29
  5371.4   581.6  5949.4  584.06  6049.2  586.18  6113.6   586.1  6263.3   589.7
  6342.3  589.85  6548.2  596.78    6727  599.23  6741.5  600.17    7054  600.86
#Mann= 4 ,-1 , 0
  2454.3     .05       0  4619.7     .16       0    4964     .07       0
  5078.3     .05       0
Bank Sta=4964,5078.3
XS Rating Curve= 0 ,0
Exp/Cntr=0.3,0.1

Type RM Length L Ch R = 1 ,1035154 ,940,940,940
BEGIN DESCRIPTION:
NAVASOTA RIVER 009
END DESCRIPTION:
XS GIS Cut Line= 3
      3378783.91     10630469.21      3377247.21     10628401.89
      3376051.14     10626829.62
#Sta/Elev= 30
  2424.1  622.22  2595.2  616.33  2708.4  613.04  3094.7  602.76  3338.8  598.75
  3353.4  596.33  3403.5  596.77  3509.8  593.36  4089.7  587.99  4439.6   582.7
  4947.1  579.44  4966.7  577.91  4982.5  573.02  5003.1   572.4  5017.9  574.56
  5032.5   581.6  5067.8  578.01  5102.5   578.6  5232.1  577.64  5246.6  579.34
  5275.7  575.82  5289.3  578.01  5639.6  581.26  6159.4   579.6  6402.7  583.11
  6662.4  590.94  6754.9  593.97  6816.5  594.76  6916.3  599.28  6975.5  599.59
#Mann= 8 ,-1 , 0
  2424.1     .05       0  2595.2     .08       0  2708.4     .05       0
  4947.1     .07       0  5032.5     .16       0  5102.5     .05       0
  6662.4     .08       0  6754.9     .05       0
Bank Sta=4947.1,5032.5
XS Rating Curve= 0 ,0
Exp/Cntr=0.3,0.1

Type RM Length L Ch R = 1 ,1034214 ,3677,3677,3677
BEGIN DESCRIPTION:
NAVASOTA RIVER 479
END DESCRIPTION:
XS GIS Cut Line= 3
      3379010.15     10628527.48      3376822.64     10627581.29
      3376137.01     10626739.44
#Sta/Elev= 30
  3214.4  606.54  3277.6  602.62  3506.4  596.47  3528.2  594.83  3614.7   591.8
  3847.9  586.81  4175.1  584.02  4420.9  580.53  4585.1   579.7  4672.1  577.85
  4782.4   578.3  4975.8   576.6  4981.3  576.28  4988.2  572.51  4998.9  569.21
  5002.1  569.71  5004.7  572.82  5010.2   573.1  5020.9   576.1  5028.2  576.54
  5407.8  578.49  5811.3  577.31  6081.3  578.99  6287.4  582.05  6351.3  584.89
  6394.4  585.02  6479.1  589.19  6507.9  589.07  6571.8  591.14  6683.5  596.45
#Mann= 3 ,-1 , 0
  3214.4     .05       0  4975.8     .07       0  5028.2     .05       0
Bank Sta=4975.8,5028.2
XS Rating Curve= 0 ,0
Exp/Cntr=0.3,0.1

Type RM Length L Ch R = 1 ,1030537 ,3466,3466,3466
BEGIN DESCRIPTION:
NAVASOTA RIVER 010
END DESCRIPTION:
XS GIS Cut Line= 3
      3379826.32      10625594.8      3377127.11      10625354.3
      3376437.42     10625356.95
#Sta/Elev= 30
  2290.1  592.82  2414.8  590.24    2455  587.45    2726  580.55  2756.2  579.94
  2776.2  580.66  2806.4     579  2943.6  577.44    3469  576.54  3649.7  576.91
  3689.8  577.82    3720  576.22  3770.2  575.46  3950.9  576.06  4201.9  574.73
  4332.4  572.82  4462.9  572.36  4593.4  570.11  4865.2  568.95  4894.6  567.87
  4924.7  569.83  4976.7  567.66  4994.7  563.72    5005  564.64    5015  567.75
    5045  570.04    5305  570.02    5405   572.8    5535  578.93  5689.7  582.47
#Mann= 3 , 0 , 0
  2290.1     .05       0  4924.7     .07       0    5045     .05       0
Bank Sta=4924.7,5045
XS Rating Curve= 0 ,0
Exp/Cntr=0.3,0.1

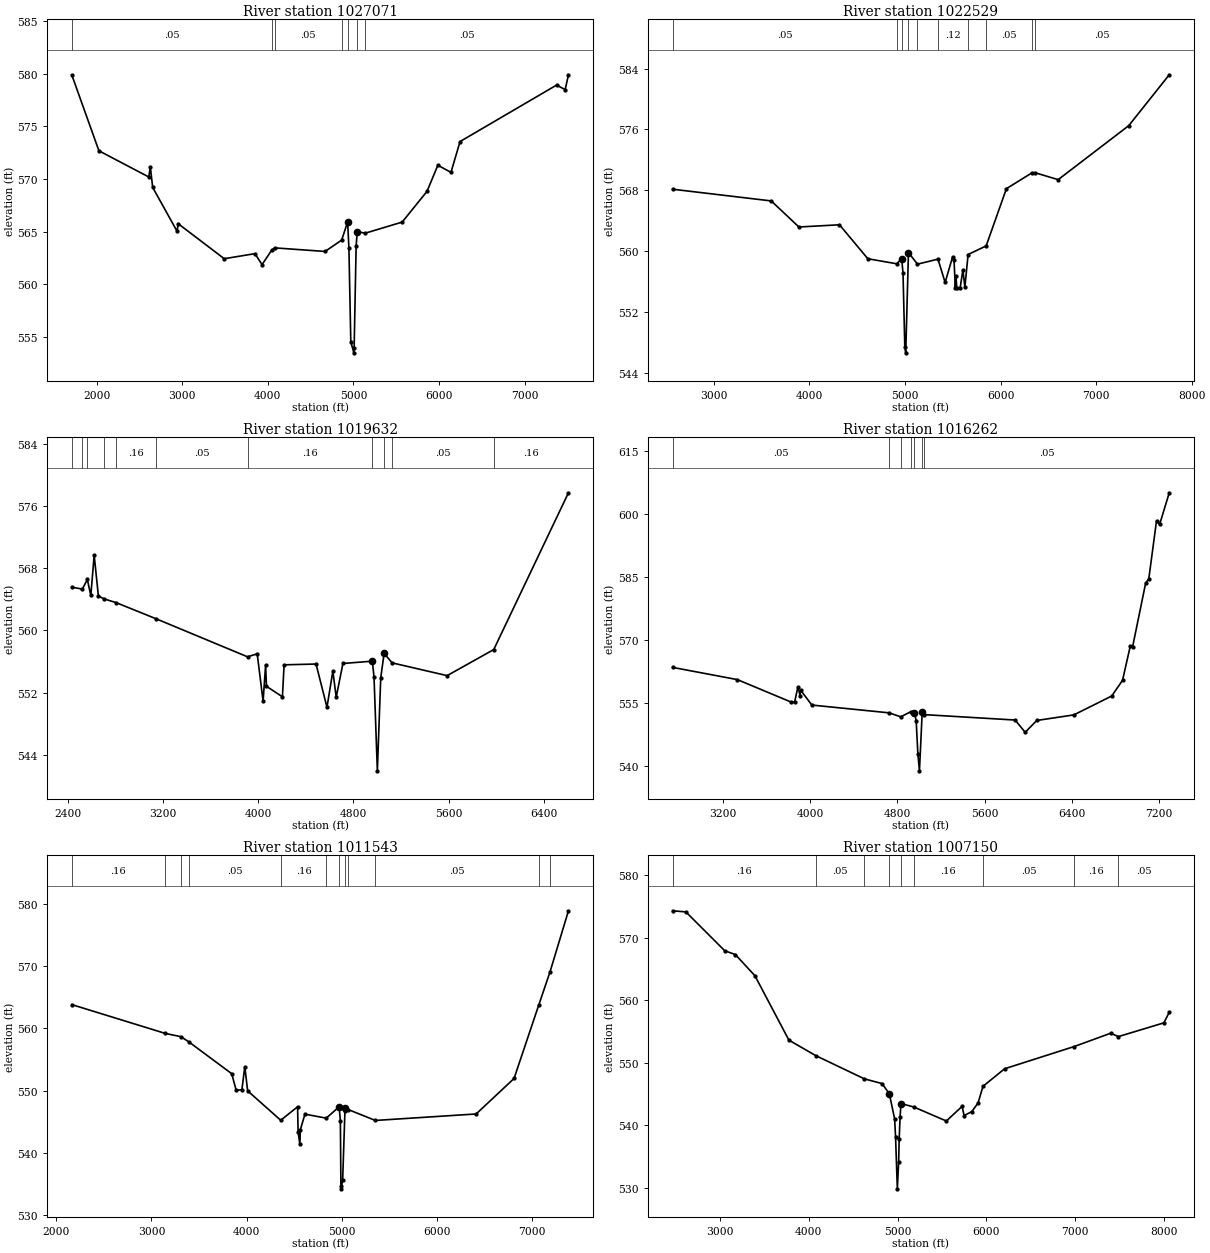
Type RM Length L Ch R = 1 ,1027071 ,4542,4542,4542
BEGIN DESCRIPTION:
NAVASOTA RIVER 011
END DESCRIPTION:
XS GIS Cut Line= 3
       3380165.5      10624314.7      3377214.79     10622857.54
      3374830.12     10622064.75
#Sta/Elev= 30
  1709.1  579.87  2025.8  572.67  2609.4  570.18  2626.3  571.17  2654.3  569.19
  2939.7  565.02  2951.6  565.75  3490.3  562.42  3849.4   562.9  3932.3  561.86
  4046.8  563.25  4079.3  563.45  4668.6  563.11  4862.9  564.19  4932.4  565.92
  4947.2  563.47  4969.5  554.53  5005.2  553.48  5008.5  553.98  5031.9  563.64
    5045     565  5136.4  564.84    5570   565.9  5860.2  568.82  5986.8   571.3
  6139.8  570.62  6246.3  573.55  7373.9  578.91  7474.7  578.48    7513  579.89
#Mann= 7 ,-1 , 0
  1709.1     .05       0  4046.8     .16       0  4079.3     .05       0
  4862.9     .16       0  4932.4     .07       0    5045     .16       0
  5136.4     .05       0
Bank Sta=4932.4,5045
XS Rating Curve= 0 ,0
Exp/Cntr=0.3,0.1

Type RM Length L Ch R = 1 ,1022529 ,2897,2897,2897
BEGIN DESCRIPTION:
NAVASOTA RIVER 012
END DESCRIPTION:
XS GIS Cut Line= 3
      3381686.92     10623055.75      3379920.21     10621383.69
      3377749.41     10619670.33
#Sta/Elev= 30
  2567.5  568.13  3599.5  566.59  3889.5  563.16  4313.9  563.45  4611.2  558.98
  4912.9  558.32  4964.8  558.98  4978.9   557.1  4997.8  547.35  5007.4   546.6
  5035.8   559.8  5130.3  558.27  5344.9  558.93  5419.6  555.86  5498.2  559.24
  5512.6  558.85  5527.1  555.08  5533.4  556.75  5541.5  555.13  5576.8  555.14
  5605.6   557.5  5626.5  555.26  5660.1  559.54  5848.9  560.67  6060.9   568.2
  6327.4  570.28  6358.8  570.31  6602.8  569.39  7341.8   576.5  7765.5  583.19
#Mann= 10 ,-1 , 0
  2567.5     .05       0  4912.9     .16       0  4964.8     .07       0
  5035.8     .12       0  5130.3     .05       0  5344.9     .12       0
  5660.1     .16       0  5848.9     .05       0  6327.4     .16       0
  6358.8     .05       0
Bank Sta=4964.8,5035.8
XS Rating Curve= 0 ,0
Exp/Cntr=0.3,0.1

Type RM Length L Ch R = 1 ,1019632 ,3370,3370,3370
BEGIN DESCRIPTION:
NAVASOTA RIVER 013
END DESCRIPTION:
XS GIS Cut Line= 2
      3383353.87     10621596.03      3380402.49      10618637.7
#Sta/Elev= 30
  2430.5  565.56  2519.3  565.32  2561.1  566.55  2590.4   564.5  2618.7  569.66
  2654.1  564.43  2705.4  564.04  2802.9  563.58  3141.8  561.49  3908.8  556.62
  3990.5     557    4040   550.9  4061.2  555.57  4068.3  552.83  4202.6  551.48
  4216.8  555.59  4485.5  555.69  4577.4  550.14  4626.9  554.77  4655.2  551.43
  4711.7  555.76  4959.2  556.06  4973.4  553.98  5001.4  541.97  5029.9  553.93
  5058.2  557.06  5125.5  555.84  5588.5   554.2  5980.7  557.55  6609.3  577.69
#Mann= 11 ,-1 , 0
  2430.5     .16       0  2519.3     .05       0  2561.1     .16       0
  2705.4     .05       0  2802.9     .16       0  3141.8     .05       0
  3908.8     .16       0  4959.2     .07       0  5058.2     .16       0
  5125.5     .05       0  5980.7     .16       0
Bank Sta=4959.2,5058.2
XS Rating Curve= 0 ,0
Exp/Cntr=0.3,0.1

Type RM Length L Ch R = 1 ,1016262 ,4719,4719,4719
BEGIN DESCRIPTION:
NAVASOTA RIVER 016
END DESCRIPTION:
XS GIS Cut Line= 3
       3384266.2     10620727.09       3383235.4     10617960.19
      3382150.29     10616788.28
#Sta/Elev= 30
  2741.9  563.48  3334.6  560.58    3824  555.28  3859.7  555.24    3890  558.89
  3909.6  556.76    3915  558.05  4017.6  554.53  4725.6  552.68  4831.8  551.73
  4922.3  552.93  4956.7  552.73  4973.1  550.85  4988.7  542.93  5003.2   538.9
  5028.5   552.9  5044.3  552.26    5880  550.97  5971.8  548.05  6077.9  550.87
  6417.5  552.19  6764.5  556.68  6863.7  560.41    6934  568.48  6955.5  568.32
  7075.7  583.53  7104.1   584.5    7175  598.32  7203.3  597.44  7291.7  604.97
#Mann= 7 ,-1 , 0
  2741.9     .05       0  4725.6      .1       0  4831.8     .12       0
  4922.3     .16       0  4956.7     .07       0  5028.5     .16       0
  5044.3     .05       0
Bank Sta=4956.7,5028.5
XS Rating Curve= 0 ,0
Exp/Cntr=0.3,0.1

Type RM Length L Ch R = 1 ,1011543 ,4393,4393,4393
BEGIN DESCRIPTION:
NAVASOTA RIVER 480
END DESCRIPTION:
XS GIS Cut Line= 3
      3387065.69      10620314.8      3386935.48     10618307.42
      3385709.65     10615345.89
#Sta/Elev= 30
  2163.5  563.79  3142.9  559.18  3310.4  558.64    3394   557.8  3843.1  552.71
  3890.3  550.03  3950.4  550.15  3980.5  553.83  4010.5  549.96  4357.9  545.24
    4535   547.4  4540.4  543.41  4558.9  541.36  4564.3  543.72  4612.1  546.22
  4836.2  545.58  4971.4   547.4  4984.5  545.15  4990.1  534.74  4992.8  534.24
  5008.4  535.64  5032.3  546.67  5037.7  547.16  5068.2  546.95  5352.1  545.21
  6410.8  546.25  6808.8  551.94    7067  563.66    7187  569.06  7380.3  578.84
#Mann= 12 ,-1 , 0
  2163.5     .16       0  3142.9     .05       0  3310.4     .16       0
    3394     .05       0  4357.9     .16       0  4836.2     .12       0
  4971.4     .07       0  5037.7     .12       0  5068.2     .16       0
  5352.1     .05       0    7067     .16       0    7187     .05       0
Bank Sta=4971.4,5037.7
XS Rating Curve= 0 ,0
Exp/Cntr=0.3,0.1

Type RM Length L Ch R = 1 ,1007150 ,4489,4489,4489
BEGIN DESCRIPTION:
NAVASOTA RIVER 015
END DESCRIPTION:
XS GIS Cut Line= 3
      3390138.56      10619668.4      3389610.78     10616869.43
      3387962.48     10614676.03
#Sta/Elev= 30
  2467.3  574.27  2616.6  574.09  3054.2  567.89    3174  567.28  3393.9   563.9
  3776.7  553.62  4078.7  551.15  4627.7  547.43  4824.9  546.69  4907.5  545.06
  4967.4  541.03  4977.5  538.21  4997.6  529.88  5012.4  534.18  5018.2  537.79
  5028.4  541.34  5038.6  543.49  5180.1  542.96  5549.5  540.71  5726.5  543.04
  5749.4  541.58  5834.8   542.2  5905.7  543.56  5962.1  546.25  6205.6  549.05
  6989.4   552.6    7399  554.72  7487.7  554.19  7998.8  556.38  8059.3  558.07
#Mann= 9 ,-1 , 0
  2467.3     .16       0  4078.7     .05       0  4627.7     .16       0
  4907.5     .07       0  5038.6     .12       0  5180.1     .16       0
  5962.1     .05       0  6989.4     .16       0  7487.7     .05       0
Bank Sta=4907.5,5038.6
XS Rating Curve= 0 ,0
Exp/Cntr=0.3,0.1

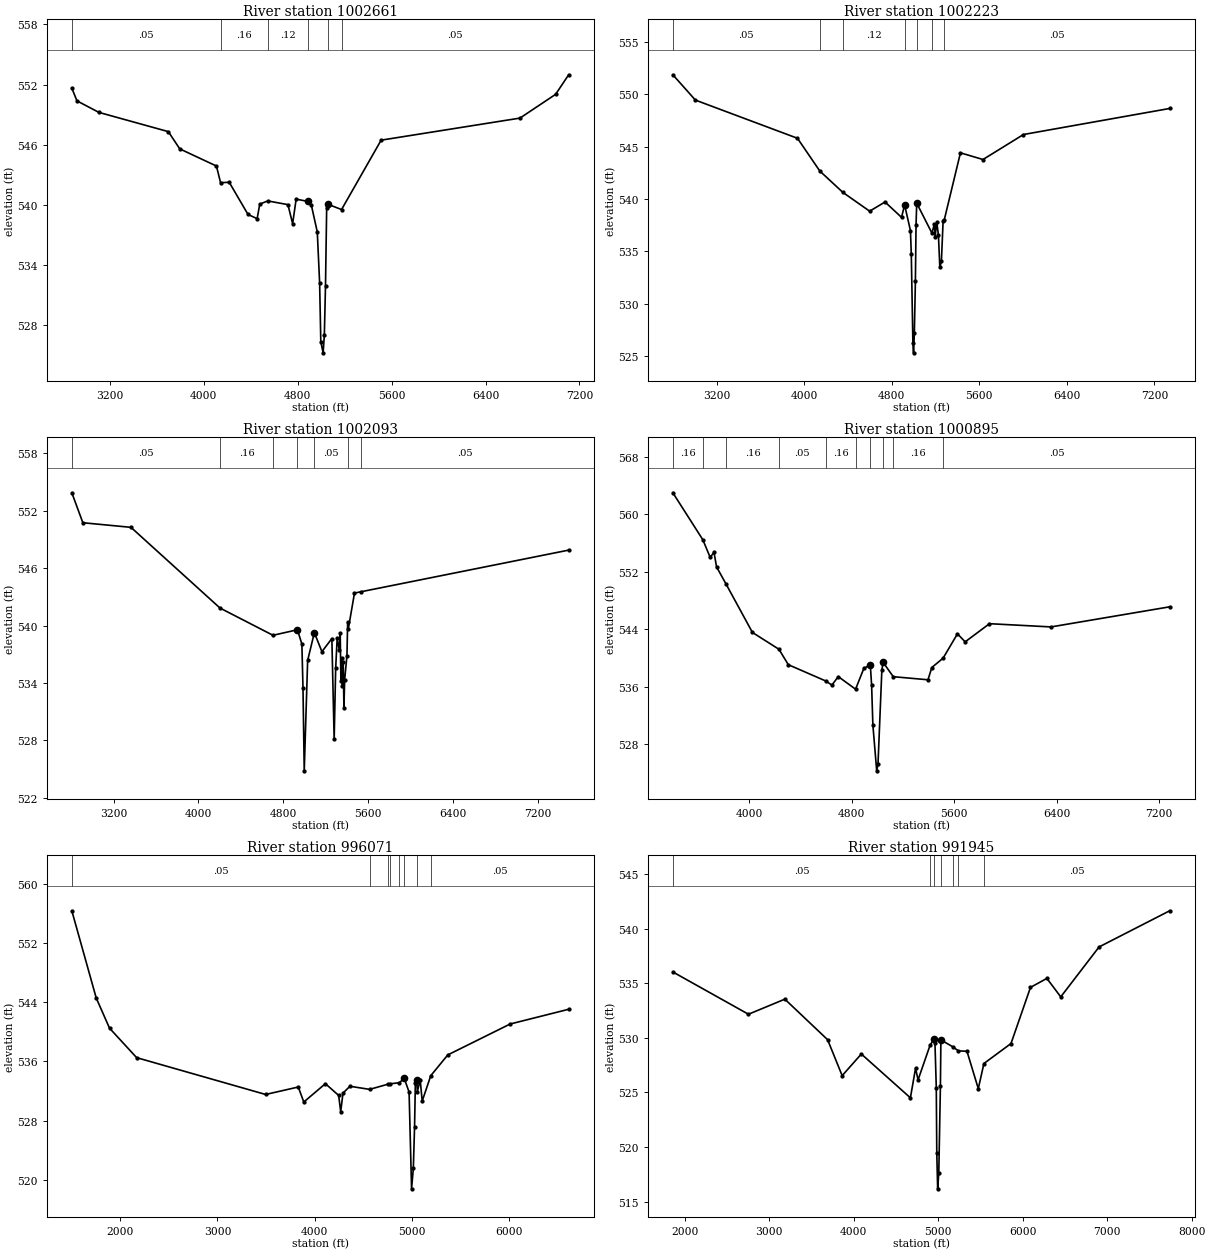
Type RM Length L Ch R = 1 ,1002661 ,438,438,438
BEGIN DESCRIPTION:
NAVASOTA RIVER 481
END DESCRIPTION:
XS GIS Cut Line= 4
      3391458.27     10617417.61      3391709.79     10616148.13
      3391698.94      10614987.1      3391189.41     10613285.07
#Sta/Elev= 30
  2876.4  551.64    2920  550.37  3106.8  549.22  3698.4   547.3  3795.7  545.58
  4108.1  543.87  4143.3  542.21    4217  542.25  4377.1  539.04  4454.9  538.62
  4477.1  540.07  4545.4  540.39  4717.1  540.02  4757.1  538.12  4787.1  540.57
  4887.1  540.34  4917.1  539.94  4967.1   537.3  4987.1  532.21  4997.1  526.36
  5016.8  525.24  5027.1  526.98  5037.1  531.92  5047.1  539.73  5057.1  540.06
  5173.8  539.53    5511  546.45  6693.5  548.65    6997  551.02  7108.3  552.97
#Mann= 6 ,-1 , 0
  2876.4     .05       0  4143.3     .16       0  4545.4     .12       0
  4887.1     .07       0  5057.1     .16       0  5173.8     .05       0
Bank Sta=4887.1,5057.1
XS Rating Curve= 0 ,0
Exp/Cntr=0.3,0.1

Type RM Length L Ch R = 1 ,1002223 ,130,130,130
BEGIN DESCRIPTION:
NAVASOTA RIVER 014
END DESCRIPTION:
XS GIS Cut Line= 6
      3391478.41     10617430.48      3392001.47     10615945.88
      3392042.84     10615460.25      3392105.85     10615335.39
      3392352.85     10614934.07      3392344.99     10613064.82
#Sta/Elev= 30
  2798.7  551.87  3004.8  549.45  3937.8   545.8  4142.1  542.67  4352.5  540.63
  4597.8  538.83  4738.3  539.71  4889.2  538.24  4917.1  539.43  4970.6  536.98
  4978.4  534.72    4993   526.2    4999  525.29  5006.3  527.19  5015.9  532.16
  5021.7  537.48  5027.9   539.6  5166.7  536.74  5189.8   537.6  5195.7  536.32
  5211.1   537.8  5226.5  536.53  5239.2  533.45  5253.6  534.04    5269  537.85
  5279.1  537.97  5427.6  544.41  5633.7  543.77  6003.7  546.16  7340.5  548.65
#Mann= 7 ,-1 , 0
  2798.7     .05       0  4142.1     .16       0  4352.5     .12       0
  4917.1     .07       0  5027.9     .05       0  5166.7     .12       0
  5279.1     .05       0
Bank Sta=4917.1,5027.9
XS Rating Curve= 0 ,0
Exp/Cntr=0.3,0.1

Type RM Length L Ch R = 1 ,1002093 ,1198,1198,1198
BEGIN DESCRIPTION:
NAVASOTA RIVER 023
END DESCRIPTION:
XS GIS Cut Line= 6
      3391607.84     10617500.26      3392193.72      10616007.2
      3392154.07     10615569.05      3392252.16     10615268.27
      3392503.89     10614986.15      3392621.73     10613050.18
#Sta/Elev= 30
  2806.8  553.87  2910.8  550.74  3363.9  550.26  4202.3  541.83  4701.9  538.98
  4931.9  539.56  4973.8  538.07  4984.3  533.48  4996.1  524.82  5028.2  536.35
  5091.4  539.26  5162.6  537.27  5256.3  538.64    5278   528.1  5292.2  535.52
  5306.4  538.69  5327.3   537.4  5334.8  539.24  5341.5  534.25  5349.1  536.65
  5355.8  533.73  5363.3  536.22    5370  531.41  5376.9  534.35  5398.4  536.84
  5405.1  540.34  5411.3  539.65  5469.4  543.39  5526.3  543.52    7487  547.88
#Mann= 7 ,-1 , 0
  2806.8     .05       0  4202.3     .16       0  4701.9     .05       0
  4931.9     .04       0  5091.4     .05       0  5411.3     .16       0
  5526.3     .05       0
Bank Sta=4931.9,5091.4
XS Rating Curve= 0 ,0
Exp/Cntr=0.3,0.1

Type RM Length L Ch R = 1 ,1000895 ,4824,4824,4824
BEGIN DESCRIPTION:
NAVASOTA RIVER 024
END DESCRIPTION:
XS GIS Cut Line= 2
      3392852.38     10616902.78      3392862.42      10613025.3
#Sta/Elev= 30
    3404  563.01    3638  556.47  3695.1  554.02  3725.1  554.72  3745.1  552.69
  3818.9  550.31  4025.1  543.56  4231.9  541.22  4305.1  539.07  4596.4  536.81
  4645.1  536.23  4695.1  537.41  4829.9  535.66  4895.1  538.58  4945.1  539.02
  4955.1  536.24  4965.1  530.66  4994.9  524.29  5005.1  525.26  5035.1  538.35
  5045.1  539.39  5124.1   537.4  5395.1  536.97  5425.1  538.68    5513  539.98
  5625.1  543.37  5685.1  542.25  5875.1  544.78  6355.2  544.33  7281.5  547.13
#Mann= 10 ,-1 , 0
    3404     .16       0    3638      .1       0  3818.9     .16       0
  4231.9     .05       0  4596.4     .16       0  4829.9     .12       0
  4945.1     .07       0  5045.1     .12       0  5124.1     .16       0
    5513     .05       0
Bank Sta=4945.1,5045.1
XS Rating Curve= 0 ,0
Exp/Cntr=0.3,0.1

Type RM Length L Ch R = 1 ,996071  ,4126,4126,4126
BEGIN DESCRIPTION:
NAVASOTA RIVER 025
END DESCRIPTION:
XS GIS Cut Line= 3
      3397252.75     10616621.22      3395231.46     10613764.86
      3394238.91     10612489.34
#Sta/Elev= 30
  1500.8  556.38  1752.2  544.58  1888.8  540.51  2168.2  536.52  3496.2  531.54
  3832.2  532.55  3889.1  530.52  4111.6     533  4248.2  531.41  4269.1   529.2
  4292.5  531.72  4363.9  532.65  4566.9  532.23  4761.1  532.95  4776.2  532.98
  4873.4  533.13  4922.6  533.74  4973.1  531.87  4998.7  518.78  5016.8  521.54
  5029.6  527.17  5037.7  533.11  5052.2  533.47  5058.5  531.94  5087.5  533.52
  5108.3  530.65  5196.3  534.08  5371.6  536.89    6014  541.07  6616.2  543.06
#Mann= 8 ,-1 , 0
  1500.8     .05       0  4566.9     .16       0  4761.1     .05       0
  4776.2     .16       0  4873.4     .12       0  4922.6     .07       0
  5052.2     .16       0  5196.3     .05       0
Bank Sta=4922.6,5052.2
XS Rating Curve= 0 ,0
Exp/Cntr=0.3,0.1

Type RM Length L Ch R = 1 ,991945  ,4200,4200,4200
BEGIN DESCRIPTION:
NAVASOTA RIVER 026
END DESCRIPTION:
XS GIS Cut Line= 3
      3400393.08     10612891.26      3397477.13     10611728.32
      3394918.95     10610746.29
#Sta/Elev= 30
  1860.7  536.03  2755.3  532.16    3186  533.54    3692  529.83  3864.2  526.54
  4091.2  528.52  4671.7  524.51  4732.7  527.22  4762.4  526.15  4906.5  529.37
  4953.8  529.88  4962.3  529.53    4978  525.45  4983.9  519.45  4994.4  516.18
  5007.7  517.66  5026.8  525.55  5032.4   529.7  5037.7  529.79  5171.3  529.19
  5239.4  528.81  5341.2  528.77  5475.2  525.35  5541.5  527.65  5862.3  529.48
  6092.8  534.62  6286.8  535.44  6450.9  533.75  6904.4  538.32  7740.2  541.63
#Mann= 7 ,-1 , 0
  1860.7     .05       0  4906.5     .16       0  4953.8     .07       0
  5037.7     .16       0  5171.3     .05       0  5239.4     .16       0
  5541.5     .05       0
Bank Sta=4953.8,5037.7
XS Rating Curve= 0 ,0
Exp/Cntr=0.3,0.1