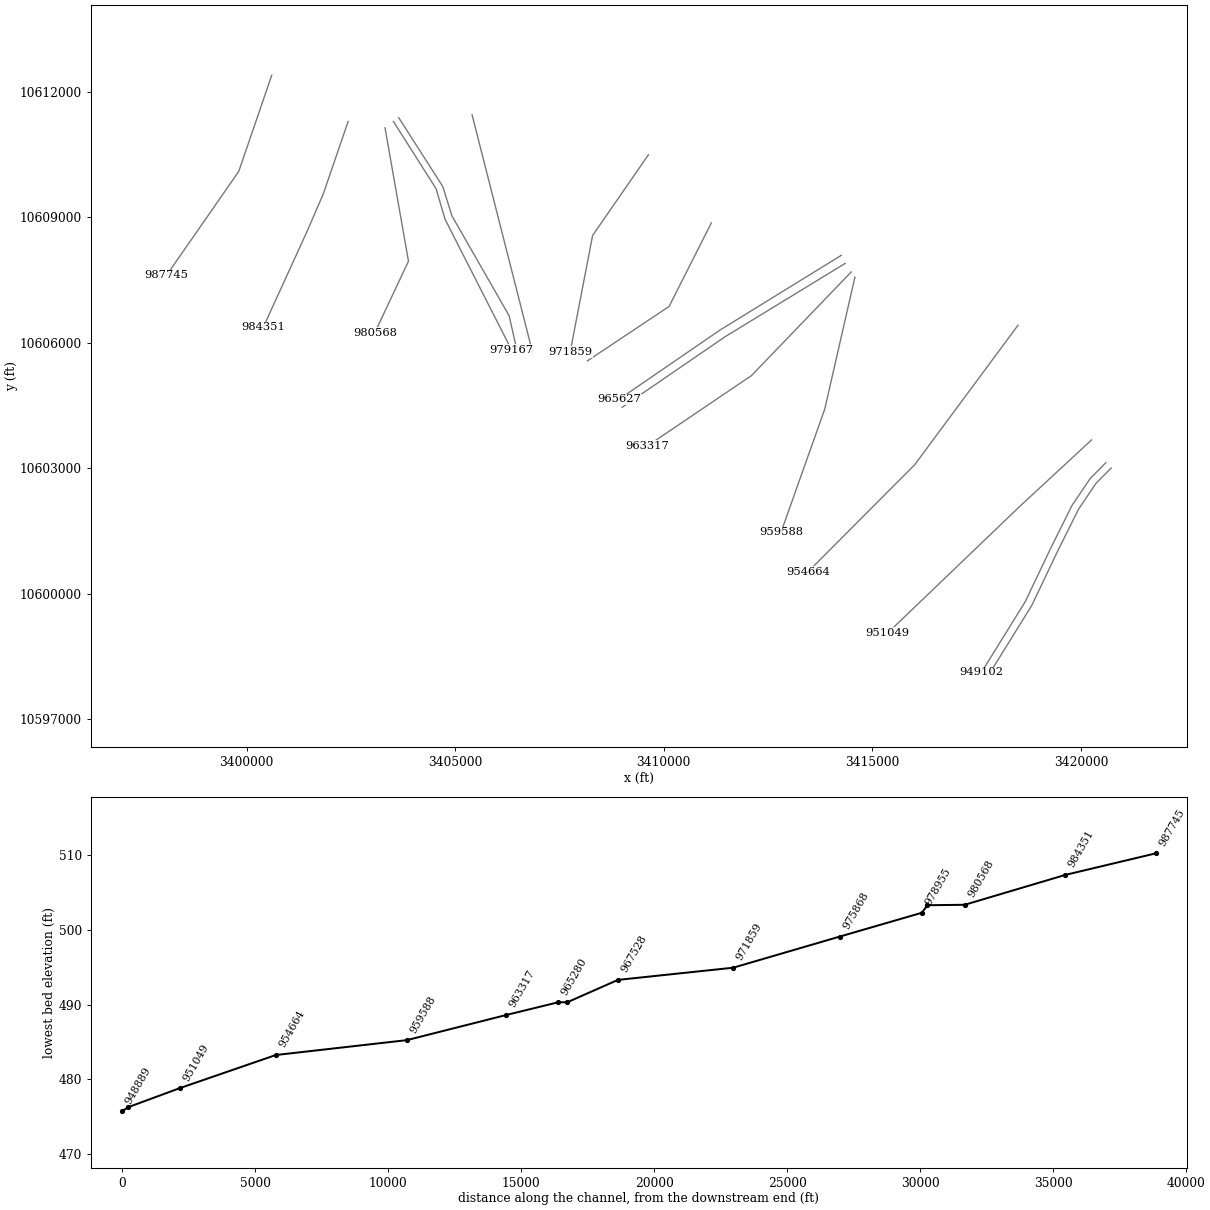
HEC-RAS study NAVASOTA RIVER.prj: NAVASOTA RIVER Base Level Engineering

--- NAVASOTA RIVER.g01 (geometry) --- (continued)

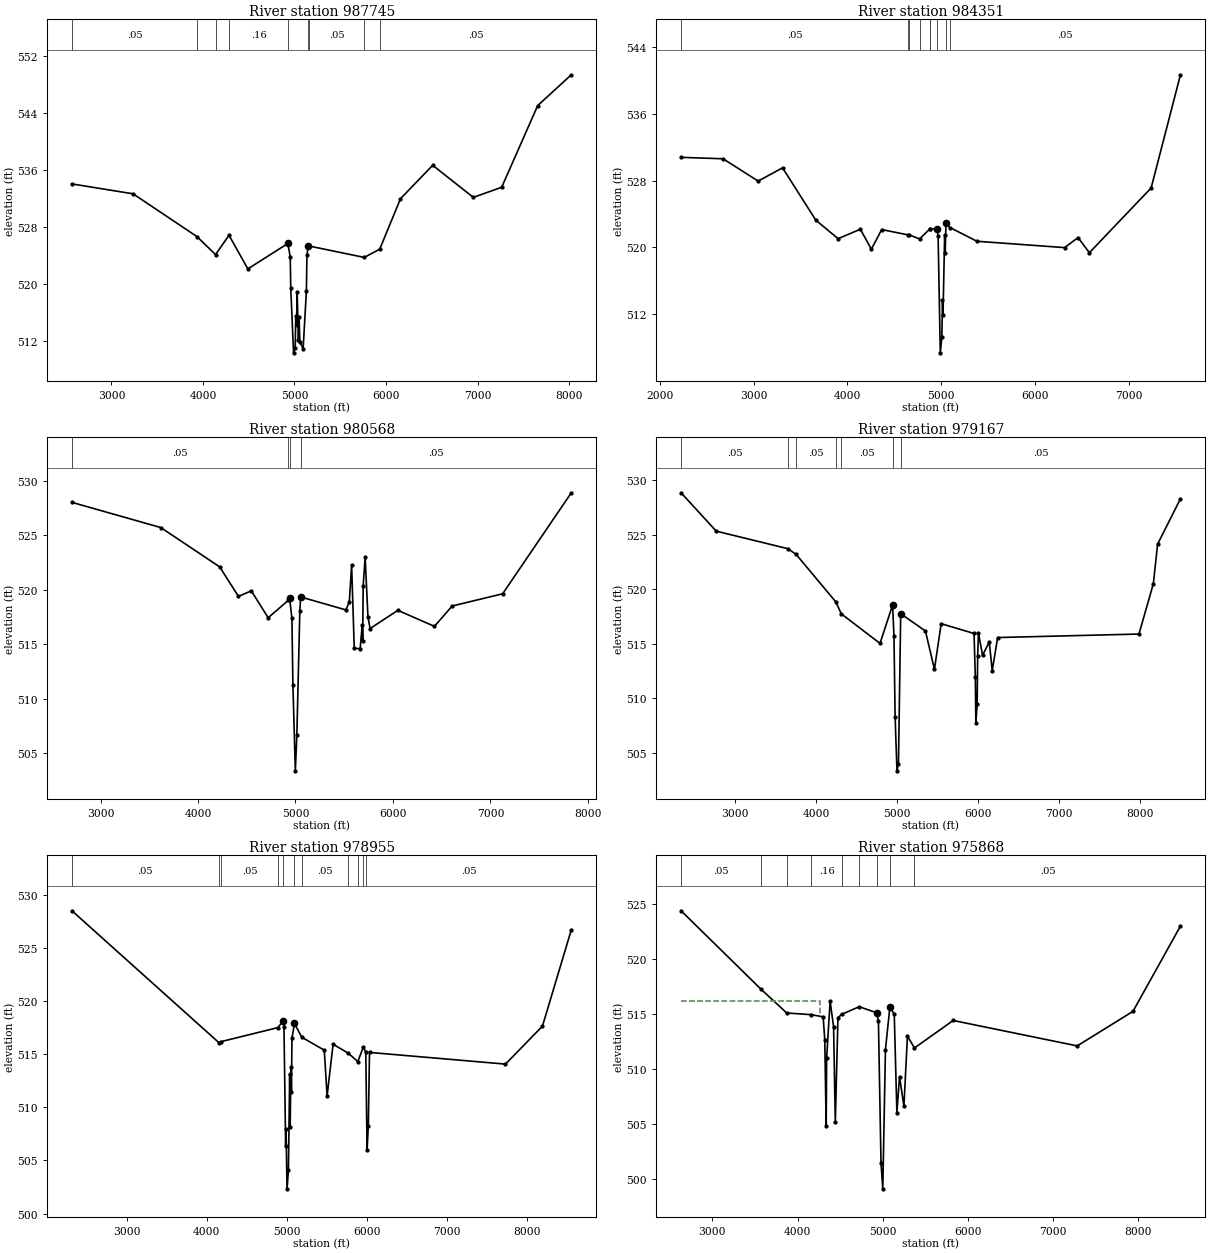
Type RM Length L Ch R = 1 ,987745  ,3394,3394,3394
BEGIN DESCRIPTION:
NAVASOTA RIVER 027
END DESCRIPTION:
XS GIS Cut Line= 3
      3400603.45     10612391.18      3399812.36     10610092.18
      3398083.54     10607610.37
#Sta/Elev= 30
  2568.7  534.01  3236.7  532.62  3934.4  526.61  4137.4  524.08  4284.8  526.79
  4490.7  522.07  4927.9  525.64  4953.8  523.72  4959.1  519.39  4990.1  510.27
    5008  511.01  5014.1   515.5  5022.8   514.2  5028.9   518.8  5043.8  512.11
  5049.8  515.33  5058.6  511.83  5094.4  510.84  5130.1  518.91  5136.2  524.02
  5151.1   525.3  5157.5  525.29  5762.4  523.68  5931.5  524.84  6158.1  531.93
  6509.8  536.63  6953.9  532.12  7263.7  533.54  7657.4  545.02  8024.6  549.35
#Mann= 9 ,-1 , 0
  2568.7     .05       0  3934.4     .16       0  4137.4     .05       0
  4284.8     .16       0  4927.9     .07       0  5151.1     .16       0
  5157.5     .05       0  5762.4     .12       0  5931.5     .05       0
Bank Sta=4927.9,5151.1
XS Rating Curve= 0 ,0
Exp/Cntr=0.3,0.1

Type RM Length L Ch R = 1 ,984351  ,3783,3783,3783
BEGIN DESCRIPTION:
NAVASOTA RIVER 028
END DESCRIPTION:
XS GIS Cut Line= 4
       3402434.1     10611285.38      3401841.67      10609561.9
       3401463.5     10608688.09      3400400.71     10606367.48
#Sta/Elev= 30
  2225.4  530.78  2672.9  530.61  3047.8  527.94  3307.9  529.53  3662.1  523.27
  3900.1  521.05  4137.8  522.18  4255.2  519.79  4365.5  522.14  4647.9   521.5
  4660.3   521.5  4769.1  521.02  4875.8  522.18  4877.8  522.19  4952.5  522.24
  4967.3  521.35  4990.5  507.39  5007.1  509.29    5014  513.66  5019.5   511.9
    5037  521.51  5042.5  519.31  5051.1  522.87  5096.3  522.37  5381.1  520.74
  6316.8  519.98  6460.4  521.18  6580.9  519.37  7239.9  527.12  7552.4  540.66
#Mann= 9 ,-1 , 0
  2225.4     .05       0  4647.9     .07       0  4660.3     .12       0
  4769.1     .16       0  4875.8     .12       0  4877.8     .16       0
  4952.5     .07       0  5051.1     .16       0  5096.3     .05       0
Bank Sta=4952.5,5051.1
XS Rating Curve= 0 ,0
Exp/Cntr=0.3,0.1

Type RM Length L Ch R = 1 ,980568  ,1401,1401,1401
BEGIN DESCRIPTION:
NAVASOTA RIVER 029
END DESCRIPTION:
XS GIS Cut Line= 3
      3403318.73     10611134.26      3403881.23     10607946.74
       3403076.4     10606239.95
#Sta/Elev= 30
  2706.4  528.03  3617.8  525.72  4222.1  522.11    4415   519.4    4547  519.91
  4719.7  517.44  4926.8  519.04  4939.6  519.27  4963.4  517.38  4973.5  511.31
  4998.6  503.39  5014.1  506.68  5044.6  518.04    5053  519.35  5516.7  518.16
  5552.3  518.87    5576  522.26  5603.1  514.62    5664  514.61  5684.3  516.76
  5689.3   515.3  5694.5  520.35  5714.8     523  5743.5  517.53  5765.6  516.45
  6050.2  518.12  6425.8  516.65    6608  518.52  7125.7  519.64  7830.2  528.91
#Mann= 4 ,-1 , 0
  2706.4     .05       0  4926.8     .16       0  4939.6     .07       0
    5053     .05       0
Bank Sta=4939.6,5053
XS Rating Curve= 0 ,0
Exp/Cntr=0.3,0.1

Type RM Length L Ch R = 1 ,979167  ,212,212,212
BEGIN DESCRIPTION:
NAVASOTA RIVER 030
END DESCRIPTION:
XS GIS Cut Line= 4
      3403519.04     10611288.06      3404542.81     10609679.67
      3404757.36     10608948.89       3406350.2     10605830.44
#Sta/Elev= 30
  2331.8  528.84  2766.2  525.32  3651.4  523.71  3754.1  523.18  4244.6  518.82
  4311.9  517.73    4790  515.02    4945  518.55  4962.1  515.68  4976.3  508.26
  4999.3  503.33  5017.6     504  5045.4  517.74  5350.9  516.16    5462  512.64
  5545.3  516.83  5951.4  515.93  5967.5   511.9  5973.8  507.76  5989.7  509.42
  5996.3  513.88  6006.3  515.95  6056.4  513.93  6139.6  515.15    6176  512.53
  6243.3  515.56  7989.3  515.88  8167.1   520.5  8219.6  524.13  8501.7  528.29
#Mann= 7 ,-1 , 0
  2331.8     .05       0  3651.4     .08       0  3754.1     .05       0
  4244.6     .08       0  4311.9     .05       0    4945    .035       0
  5045.4     .05       0
#XS Ineff= 2 , 0
       0                  5951.4       0  515.93
Permanent Ineff=
       F       F
Bank Sta=4945,5045.4
XS Rating Curve= 0 ,0
Exp/Cntr=0.3,0.1

Type RM Length L Ch R = 1 ,978955  ,3087,3087,3087
BEGIN DESCRIPTION:
NAVASOTA RIVER 031
END DESCRIPTION:
XS GIS Cut Line= 5
      3403646.42     10611378.35      3404704.13     10609730.36
      3404921.27      10609033.4      3406294.37     10606640.42
       3406468.9     10605870.21
#Sta/Elev= 30
  2318.4  528.47  4152.3  516.08  4183.4  516.17    4890  517.48  4954.9  518.08
  4966.6  517.52  4987.5  506.34  4992.7  507.91  5004.7  502.32  5022.1  504.06
    5038   513.1  5043.7  508.17  5053.8  513.79  5059.5  511.42  5066.3  516.47
  5096.9  517.87    5190  516.57  5469.8  515.36  5505.4  511.06  5580.1  515.92
  5768.6  515.08  5889.1  514.29  5958.3  515.68  5988.2  515.16  6004.4  505.99
  6020.2  508.25  6034.8  515.15  7733.1  514.05    8195  517.62  8555.3  526.68
#Mann= 11 ,-1 , 0
  2318.4     .05       0  4152.3     .16       0  4183.4     .05       0
    4890     .16       0  4954.9     .07       0  5096.9     .16       0
    5190     .05       0  5768.6     .16       0  5889.1     .05       0
  5958.3     .16       0  5988.2     .05       0
#XS Ineff= 2 ,-1
  5469.8  5580.1  515.36  5580.1    8091  515.92
Permanent Ineff=
       F       F
Bank Sta=4954.9,5096.9
XS Rating Curve= 0 ,0
Exp/Cntr=0.3,0.1

Type RM Length L Ch R = 1 ,975868  ,4009,4009,4009
BEGIN DESCRIPTION:
NAVASOTA RIVER 017
END DESCRIPTION:
XS GIS Cut Line= 2
      3405405.54     10611444.97      3406855.19     10605767.93
#Sta/Elev= 30
  2633.6   524.4  3572.9  517.26  3873.5  515.11  4160.1  514.96  4300.5  514.76
  4319.3  512.69  4336.1   504.8  4341.3  510.98  4382.2  516.18    4423  513.86
  4443.2  505.17  4474.2  514.69  4521.1     515  4723.1  515.68  4928.3  515.13
  4948.9  514.39  4979.4  501.48  5000.3  499.13  5031.5  511.79  5083.1  515.63
  5134.7  515.01  5165.6  506.04  5196.6  509.32  5248.2  506.64  5289.5  513.02
  5371.5  511.93  5826.2  514.43  7281.4  512.12  7935.8  515.26  8492.8  523.01
#Mann= 9 ,-1 , 0
  2633.6     .05       0  3572.9     .16       0  3873.5     .05       0
  4160.1     .16       0  4521.1     .05       0  4723.1     .16       0
  4928.3     .07       0  5083.1     .16       0  5371.5     .05       0
#XS Ineff= 2 , 0
       0  4267.7  516.21               0
Permanent Ineff=
       F       F
Bank Sta=4928.3,5083.1
XS Rating Curve= 0 ,0
Exp/Cntr=0.3,0.1

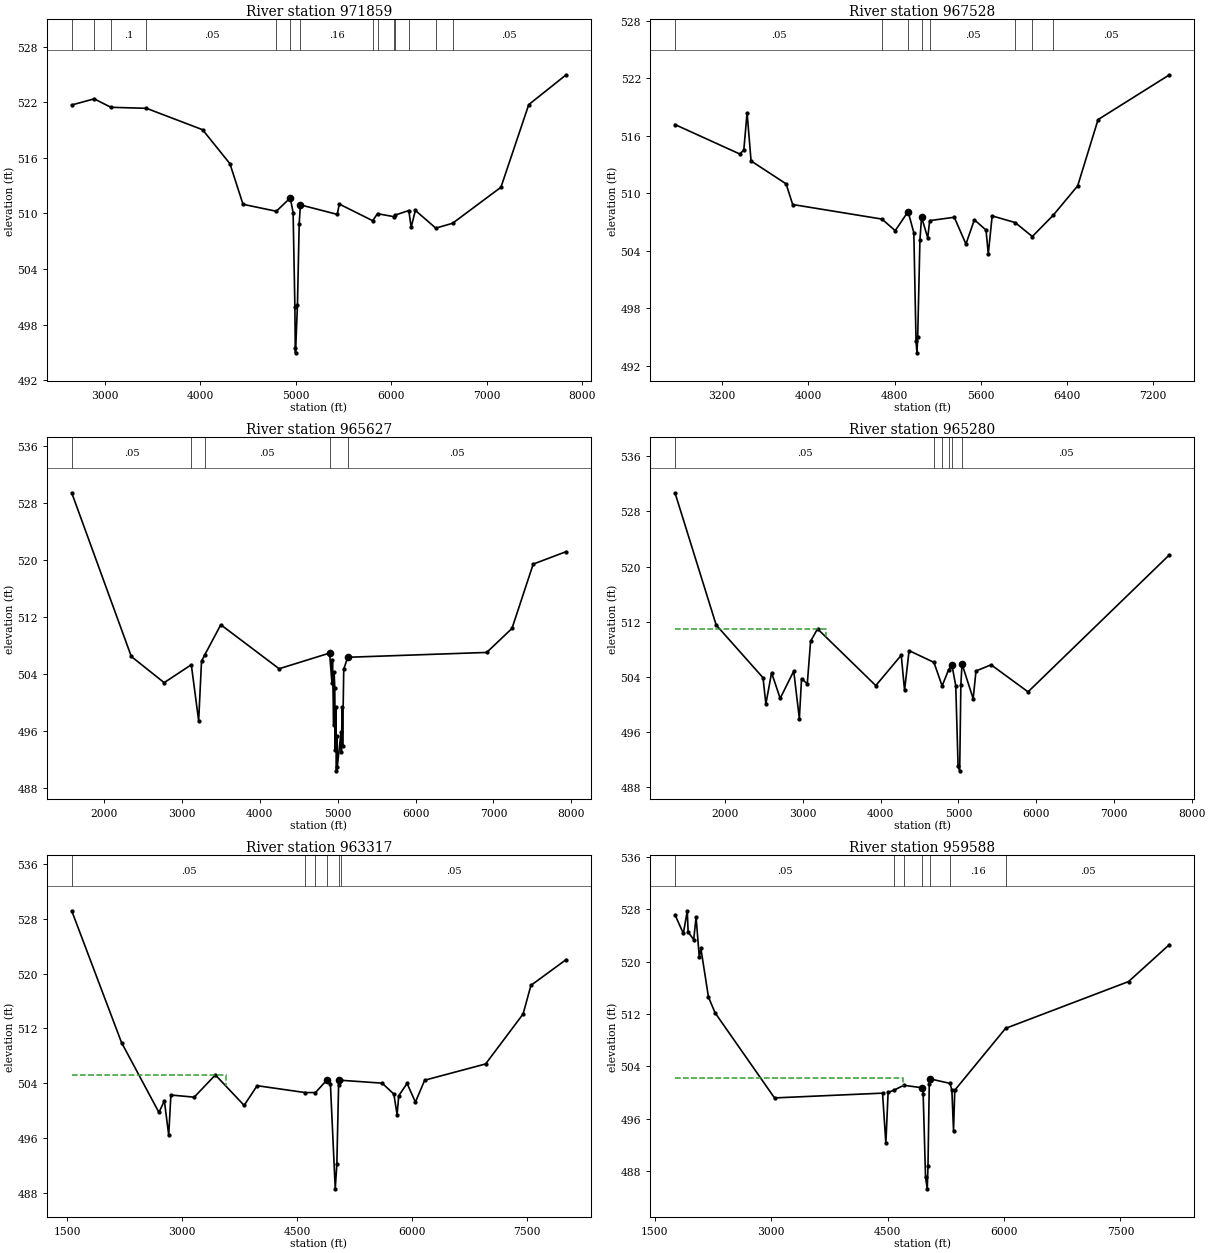
Type RM Length L Ch R = 1 ,971859  ,4331,4331,4331
BEGIN DESCRIPTION:
NAVASOTA RIVER 032
END DESCRIPTION:
XS GIS Cut Line= 3
      3409632.03     10610489.08      3408294.55     10608559.24
      3407757.18     10605776.25
#Sta/Elev= 30
    2652  521.71  2887.6  522.37  3063.2  521.46  3435.6  521.35  4023.7  519.04
  4310.3  515.37  4447.4  510.99  4796.5  510.24  4942.6  511.68  4972.3   510.1
    4991  499.93  4994.8  495.46  4997.5  494.96  5017.9  500.11  5036.2   508.9
  5048.5  510.93  5435.5   509.9  5455.9  511.02  5806.4  509.22  5856.8  509.98
  6025.9  509.66  6043.5  509.83  6184.9  510.32  6209.5  508.52  6253.9  510.33
  6467.7  508.42  6643.2  508.94  7150.4  512.83  7441.9  521.75  7834.4  524.97
#Mann= 14 ,-1 , 0
    2652     .16       0  2887.6     .05       0  3063.2      .1       0
  3435.6     .05       0  4796.5     .16       0  4942.6     .07       0
  5048.5     .16       0  5806.4     .05       0  5856.8     .16       0
  6025.9     .05       0  6043.5     .16       0  6184.9     .05       0
  6467.7     .16       0  6643.2     .05       0
Bank Sta=4942.6,5048.5
XS Rating Curve= 0 ,0
Exp/Cntr=0.3,0.1

Type RM Length L Ch R = 1 ,967528  ,1901,1901,1901
BEGIN DESCRIPTION:
NAVASOTA RIVER 035
END DESCRIPTION:
XS GIS Cut Line= 3
      3411140.75     10608861.55      3410128.43     10606864.58
      3408170.21     10605562.88
#Sta/Elev= 30
  2761.1  517.17  3363.6  514.09  3400.1  514.54  3430.4   518.4  3467.3  513.37
  3792.5  510.98  3853.5  508.82  4682.1   507.3  4805.5  506.09  4924.8  508.08
    4978  505.88  4998.8  494.52  5007.3  493.33    5014  494.95    5035  505.15
  5050.1  507.49  5107.2  505.34  5125.5  507.14  5353.7  507.49  5461.9  504.69
  5540.1  507.23  5648.3  506.15  5669.3  503.66  5705.4  507.63  5918.2  506.94
  6078.1  505.48  6270.5  507.68  6499.1  510.77  6688.5  517.69  7351.4  522.37
#Mann= 8 ,-1 , 0
  2761.1     .05       0  4682.1     .16       0  4924.8     .07       0
  5050.1     .16       0  5125.5     .05       0  5918.2     .12       0
  6078.1     .16       0  6270.5     .05       0
Bank Sta=4924.8,5050.1
XS Rating Curve= 0 ,0
Exp/Cntr=0.3,0.1

Type RM Length L Ch R = 1 ,965627  ,347,347,347
BEGIN DESCRIPTION:
NAVASOTA RIVER 036
END DESCRIPTION:
XS GIS Cut Line= 3
      3414257.98     10608087.47      3411351.55     10606301.89
      3408930.61      10604645.6
#Sta/Elev= 30
  1588.9  529.37  2353.7  506.39  2775.1  502.72  3123.4  505.23  3217.8  497.37
  3254.5  505.72  3297.5  506.65  3501.9  510.85    4250  504.67  4897.5  506.87
  4928.3  502.65  4934.2  505.95  4949.6  496.82  4955.5  504.18  4964.1  502.03
  4970.9  493.24  4976.8  499.32  4986.1  490.34  4992.2  495.26  4996.7  490.92
  5043.2  495.73  5049.3  492.94  5058.1  499.34  5064.2   493.8  5079.1   504.6
  5129.9  506.28  6913.7  506.96  7237.8  510.33  7509.9  519.36  7933.3  521.11
#Mann= 5 ,-1 , 0
  1588.9     .05       0  3123.4     .16       0  3297.5     .05       0
  4897.5     .07       0  5129.9     .05       0
#XS Ineff= 2 , 0
       0  3501.9  510.85               0
Permanent Ineff=
       F       F
Bank Sta=4897.5,5129.9
XS Rating Curve= 0 ,0
Exp/Cntr=0.3,0.1

Type RM Length L Ch R = 1 ,965280  ,1963,1963,1963
BEGIN DESCRIPTION:
NAVASOTA RIVER 037
END DESCRIPTION:
XS GIS Cut Line= 4
      3414348.22       10607893.      3411459.56     10606133.45
      3411242.48      10605984.9      3409001.98     10604451.84
#Sta/Elev= 30
  1354.6  530.71  1884.3  511.51  2486.7  503.85  2523.5  500.04  2597.1  504.58
  2707.4  500.85  2881.8  504.81  2954.2   497.9  2982.5  503.73  3056.1  502.95
  3098.7  509.14  3187.8  510.95  3937.3  502.71  4264.6  507.12  4307.3  502.02
  4365.4  507.79  4685.3  506.08  4790.7  502.66  4874.2  505.02  4915.6  505.74
  4965.8   502.7  4995.7  490.99  5016.4  490.33  5031.5  502.86  5046.5  505.85
    5190   500.8  5225.9  504.83  5420.2  505.73  5895.5   501.8  7714.8  521.71
#Mann= 6 ,-1 , 0
  1354.6     .05       0  4685.3     .12       0  4790.7     .16       0
  4874.2     .12       0  4915.6     .07       0  5046.5     .05       0
#XS Ineff= 2 , 0
       0  3294.4  510.94               0
Permanent Ineff=
       F       F
Bank Sta=4915.6,5046.5
XS Rating Curve= 0 ,0
Exp/Cntr=0.3,0.1

Type RM Length L Ch R = 1 ,963317  ,3729,3729,3729
BEGIN DESCRIPTION:
NAVASOTA RIVER 038
END DESCRIPTION:
XS GIS Cut Line= 3
      3414493.92     10607688.33      3412104.63     10605212.64
      3409612.09     10603532.01
#Sta/Elev= 30
  1559.4  529.14  2208.9  509.94  2696.9  499.75  2767.6  501.45  2824.2  496.44
  2852.5  502.29  3156.6  501.98  3432.4  505.22  3807.2  500.78    3977  503.65
  4603.6  502.65  4737.7  502.65  4882.2  504.43  4931.9  503.97  4995.2  488.62
  5015.9  492.19  5039.2   503.8  5045.9  504.42  5070.6  504.44  5606.6  504.02
  5759.4  502.43  5801.4  499.43  5823.2  502.19  5931.7  503.98  6040.3  501.26
  6161.2  504.45  6955.7  506.82  7444.4   514.1  7546.3  518.27  8006.2  522.03
#Mann= 6 ,-1 , 0
  1559.4     .05       0  4603.6      .1       0  4737.7     .16       0
  4882.2     .07       0  5045.9     .16       0  5070.6     .05       0
#XS Ineff= 2 , 0
       0  3566.9   505.2               0
Permanent Ineff=
       F       F
Bank Sta=4882.2,5045.9
XS Rating Curve= 0 ,0
Exp/Cntr=0.3,0.1

Type RM Length L Ch R = 1 ,959588  ,4924,4924,4924
BEGIN DESCRIPTION:
NAVASOTA RIVER 039
END DESCRIPTION:
XS GIS Cut Line= 3
      3414583.44     10607566.59      3413859.93     10604411.59
      3412809.86      10601461.6
#Sta/Elev= 30
  1763.1  527.19  1870.8  524.33  1921.3   527.8  1932.3  524.55  2004.1  523.38
  2034.9  526.84    2076  520.67  2096.5  522.04    2194  514.61  2279.8  512.18
  3044.8  499.17  4435.9   499.9  4478.8  492.21  4507.5  500.01  4584.5  500.36
  4709.4   501.1  4948.6  500.72  4958.9  499.81  4989.7     487  5011.9  485.26
  5021.2  488.73  5037.7  501.29    5053  502.07  5305.6  501.39    5329  500.31
  5350.2  494.12  5366.2  500.35  6020.2  509.81  7604.3  516.97  8131.3  522.64
#Mann= 7 ,-1 , 0
  1763.1     .05       0  4584.5     .16       0  4709.4     .12       0
  4948.6     .07       0    5053     .12       0  5305.6     .16       0
  6020.2     .05       0
#XS Ineff= 2 , 0
       0  4698.4  502.25               0
Permanent Ineff=
       F       F
Bank Sta=4948.6,5053
XS Rating Curve= 0 ,0
Exp/Cntr=0.3,0.1

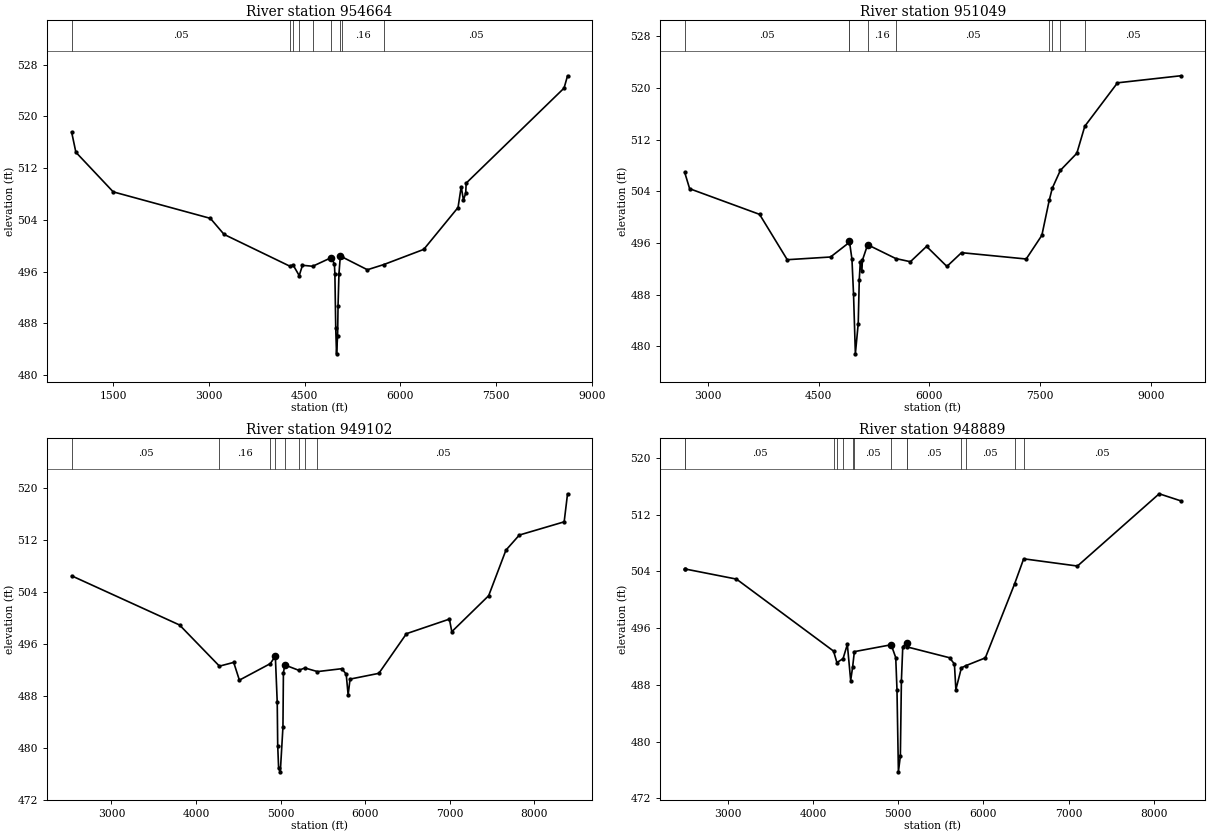
Type RM Length L Ch R = 1 ,954664  ,3615,3615,3615
BEGIN DESCRIPTION:
NAVASOTA RIVER 044
END DESCRIPTION:
XS GIS Cut Line= 3
      3418491.46      10606414.8      3416015.43     10603079.76
      3413457.14     10600519.31
#Sta/Elev= 30
   846.3  517.57   912.5  514.46  1497.9  508.33  3020.6  504.23  3235.5  501.75
  4262.7  496.85  4317.2  497.02  4413.5  495.37  4464.4  496.97  4624.7  496.82
    4915  498.15  4965.1  497.19  4972.7  495.59  4985.9  487.25  4998.3  483.27
  5015.2  486.06  5022.2  490.72  5036.4  495.65  5057.6  498.39  5078.1   498.3
  5481.9  496.28  5735.8  497.07  6365.7  499.43  6903.1  505.91  6952.6  509.13
    6988  507.06  7023.3  508.13  7030.4  509.68  8564.8  524.38  8619.5  526.29
#Mann= 9 ,-1 , 0
   846.3     .05       0  4262.7     .16       0  4317.2     .05       0
  4413.5     .16       0  4624.7     .12       0    4915     .07       0
  5057.6     .12       0  5078.1     .16       0  5735.8     .05       0
Bank Sta=4915,5057.6
XS Rating Curve= 0 ,0
Exp/Cntr=0.3,0.1

Type RM Length L Ch R = 1 ,951049  ,1947,1947,1947
BEGIN DESCRIPTION:
NAVASOTA RIVER 045
END DESCRIPTION:
XS GIS Cut Line= 3
      3420254.56     10603673.03      3418551.87     10602101.17
      3415366.99     10599056.75
#Sta/Elev= 30
  2682.7   506.9  2749.2  504.39  3697.3  500.42  4072.7   493.4  4659.6  493.82
  4907.5  496.02  4914.7  496.34  4949.9  493.48  4971.4  488.04  4996.2  478.83
  5034.9  483.52    5049   490.3  5063.2  493.08  5084.3  491.58  5091.5  493.31
  5162.3  495.72  5543.9  493.58  5742.2  493.09  5961.4  495.46  6237.2  492.36
  6435.4  494.49  7312.2  493.51  7524.5  497.17  7624.6   502.6  7665.9  504.47
  7775.5  507.23  7998.5  509.87  8106.7  514.06  8550.1  520.78  9405.9  521.87
#Mann= 9 ,-1 , 0
  2682.7     .05       0  4907.5     .16       0  4914.7     .07       0
  5162.3     .16       0  5543.9     .05       0  7624.6     .16       0
  7665.9     .05       0  7775.5      .1       0  8106.7     .05       0
Bank Sta=4914.7,5162.3
XS Rating Curve= 0 ,0
Exp/Cntr=0.3,0.1

Type RM Length L Ch R = 1 ,949102  ,213,213,213
BEGIN DESCRIPTION:
NAVASOTA RIVER 033
END DESCRIPTION:
XS GIS Cut Line= 6
       3420599.3     10603130.14      3420224.92     10602753.58
      3419788.17     10602110.22      3419269.45     10601070.76
      3418667.94     10599811.18      3417614.56     10598115.22
#Sta/Elev= 30
  2529.7  506.52  3805.5  498.93    4277  492.58  4445.6  493.16  4512.7  490.42
  4878.6  492.97  4937.8  494.14  4960.2  486.99  4965.8  480.32  4976.7  476.81
  4996.5  476.27  5027.7  483.17  5033.2  491.58  5050.4  492.76  5214.6  491.94
  5286.5   492.3  5436.2  491.74  5724.8  492.19  5775.8  491.33  5798.4  488.13
  5821.1  490.58  6161.4  491.47  6487.9  497.59  6995.7  499.84    7024   497.9
  7459.7  503.45    7664  510.48  7822.2  512.81  8352.4  514.85  8392.3  519.18
#Mann= 8 ,-1 , 0
  2529.7     .05       0    4277     .16       0  4878.6     .12       0
  4937.8     .07       0  5050.4     .12       0  5214.6     .05       0
  5286.5     .16       0  5436.2     .05       0
Bank Sta=4937.8,5050.4
XS Rating Curve= 0 ,0
Exp/Cntr=0.3,0.1

Type RM Length L Ch R = 1 ,948889  ,1317,1317,1317
BEGIN DESCRIPTION:
NAVASOTA RIVER 034
END DESCRIPTION:
XS GIS Cut Line= 6
      3420726.92      10603003.2      3420364.41     10602638.58
      3419943.86     10602019.08       3419431.2     10600991.78
      3418826.09     10599724.64      3417766.81     10598019.18
#Sta/Elev= 30
  2492.1  504.36  2498.6  504.34  3099.3  502.92  4239.3  492.77    4279  491.15
  4351.2   491.7  4401.6  493.71  4440.7  488.62    4463  490.46    4484  492.69
  4916.3  493.66  4969.8  491.85  4984.3  487.35  5001.2  475.74  5024.2     478
  5036.3  488.57  5052.4  493.39  5097.8   493.9  5105.6  493.35  5601.4  491.83
  5658.8  490.95    5676  487.34  5740.9  490.41  5796.8  490.73  6021.8  491.81
  6364.5  502.21  6472.2  505.78  7103.5  504.76  8063.5  514.95    8315  513.96
#Mann= 14 ,-1 , 0
  2492.1     .08       0  2498.6     .05       0  4239.3     .16       0
    4279     .05       0  4351.2     .16       0    4463     .12       0
    4484     .05       0  4916.3     .04       0  5097.8     .16       0
  5105.6     .05       0  5740.9     .08       0  5796.8     .05       0
  6364.5     .08       0  6472.2     .05       0
Bank Sta=4916.3,5097.8
XS Rating Curve= 0 ,0
Exp/Cntr=0.3,0.1