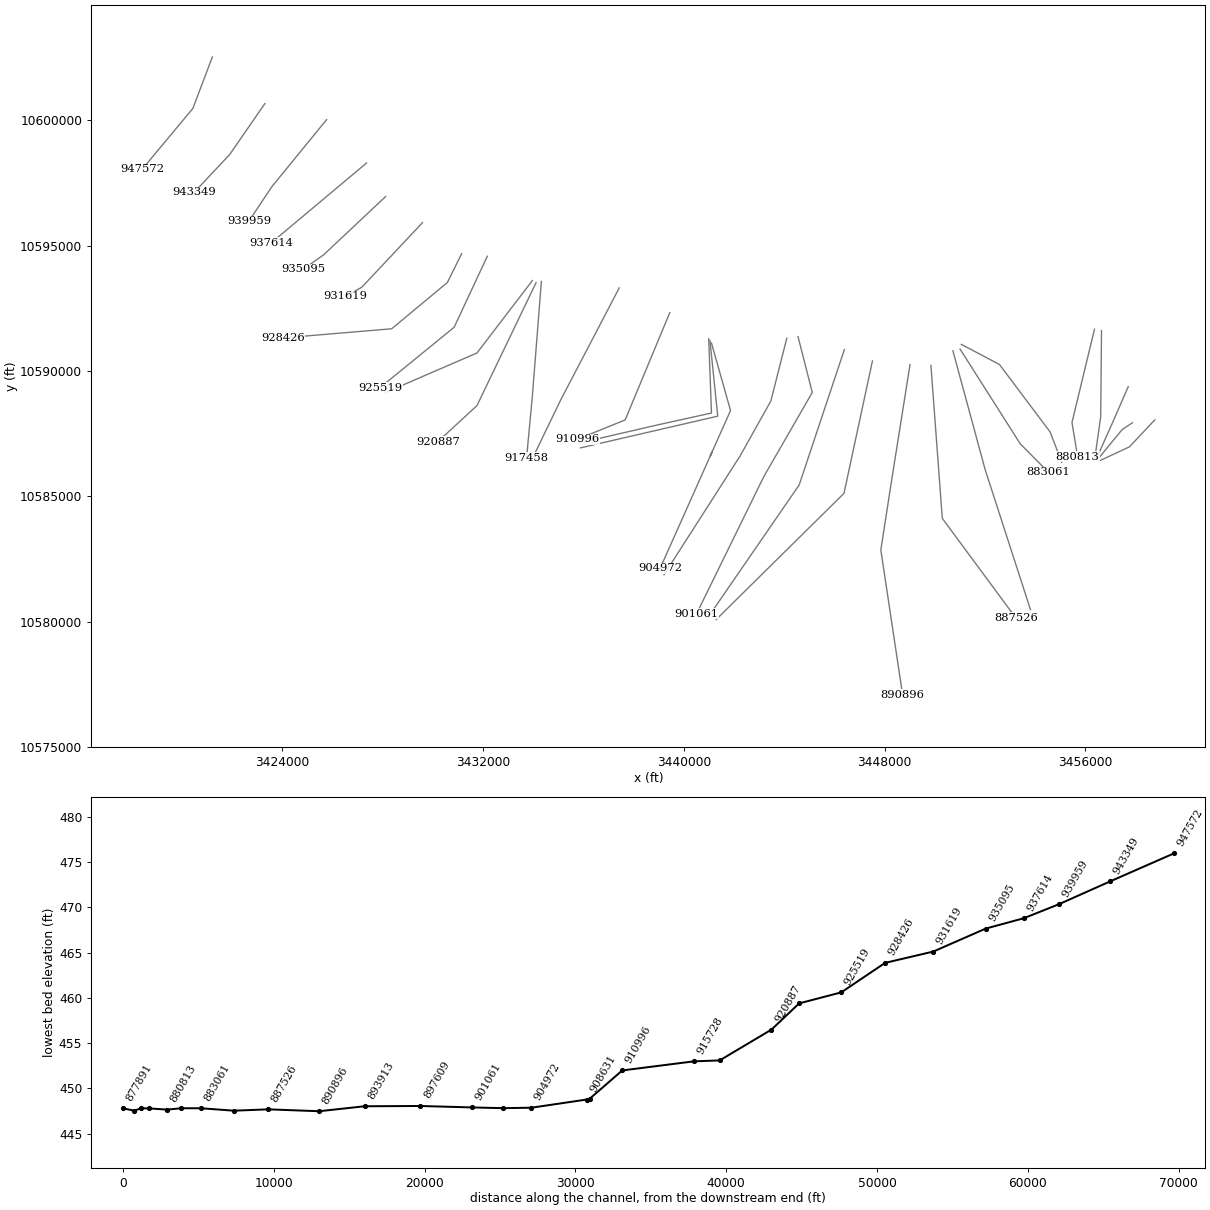
HEC-RAS study NAVASOTA RIVER.prj: NAVASOTA RIVER Base Level Engineering

--- NAVASOTA RIVER.g01 (geometry) --- (continued)

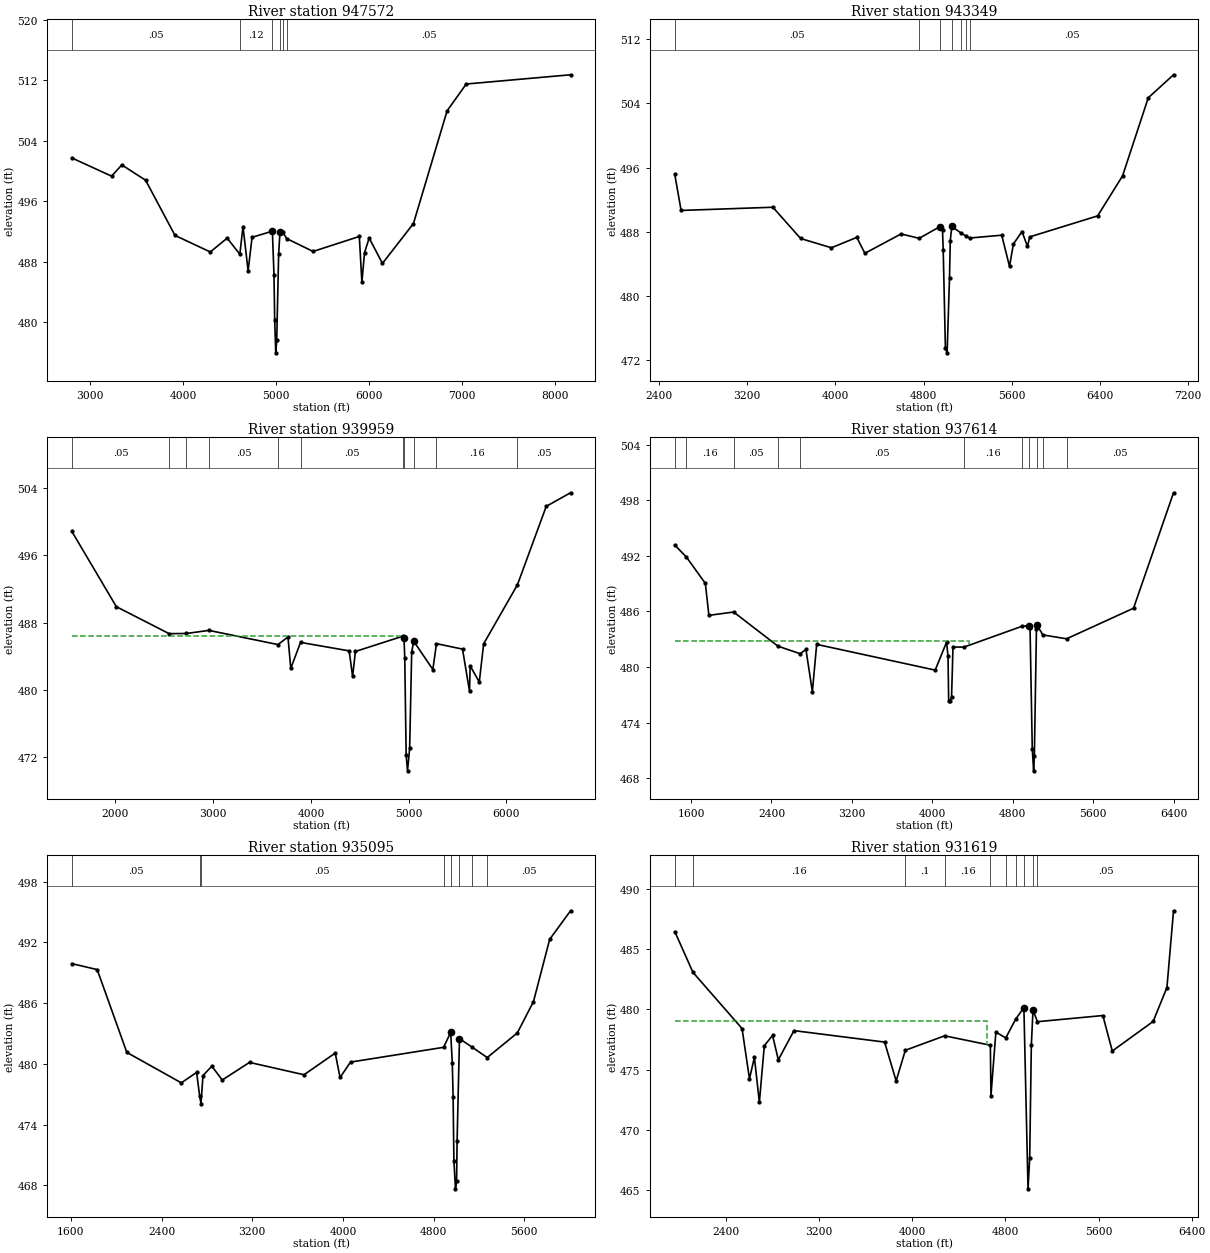
Type RM Length L Ch R = 1 ,947572  ,4223,4223,4223
BEGIN DESCRIPTION:
NAVASOTA RIVER 046
END DESCRIPTION:
XS GIS Cut Line= 3
      3421209.77     10602524.07      3420432.65      10600470.7
       3418407.5     10598038.29
#Sta/Elev= 30
  2804.5  501.73  3232.6  499.32  3341.7  500.81    3598  498.78  3913.8  491.49
  4293.3   489.3  4474.3  491.13  4610.7     489  4644.6  492.66  4699.6  486.81
  4742.4  491.24  4960.4  492.05  4977.6   486.3  4985.2  480.32  4996.6  475.97
    5007  477.63  5027.8  489.03  5042.1  491.89  5071.1  491.92  5115.7  491.06
  5397.5  489.37  5894.8  491.35  5922.6   485.3  5950.8   489.2  6000.7  491.14
  6143.5  487.79  6476.7  493.06  6838.6  507.96  7044.3   511.5  8165.1  512.72
#Mann= 6 ,-1 , 0
  2804.5     .05       0  4610.7     .12       0  4960.4     .07       0
  5042.1     .12       0  5071.1     .16       0  5115.7     .05       0
Bank Sta=4960.4,5042.1
XS Rating Curve= 0 ,0
Exp/Cntr=0.3,0.1

Type RM Length L Ch R = 1 ,943349  ,3390,3390,3390
BEGIN DESCRIPTION:
NAVASOTA RIVER 047
END DESCRIPTION:
XS GIS Cut Line= 3
      3423301.42     10600661.38      3421905.17     10598638.57
      3420490.85     10597128.86
#Sta/Elev= 30
  2542.1  495.14  2599.5  490.65  3432.4  491.05    3684  487.15  3963.7  485.99
  4194.3  487.29  4267.2   485.3  4596.5  487.72  4759.9  487.17  4948.8  488.63
    4972  488.18  4978.5  485.66  4998.3  473.45  5013.8  472.88  5035.5  482.24
  5042.4  486.88  5056.6  488.65  5140.2  487.83  5182.4  487.48  5219.6  487.21
  5509.4  487.56  5580.2  483.67  5615.4  486.46  5693.5  488.02  5742.9  486.16
  5763.9  487.35  6379.8  489.97    6606  494.96  6839.5  504.71  7068.7  507.58
#Mann= 7 ,-1 , 0
  2542.1     .05       0  4759.9     .12       0  4948.8     .07       0
  5056.6     .12       0  5140.2     .05       0  5182.4     .16       0
  5219.6     .05       0
Bank Sta=4948.8,5056.6
XS Rating Curve= 0 ,0
Exp/Cntr=0.3,0.1

Type RM Length L Ch R = 1 ,939959  ,2345,2345,2345
BEGIN DESCRIPTION:
NAVASOTA RIVER 048
END DESCRIPTION:
XS GIS Cut Line= 3
      3425762.52     10600023.58      3423584.47     10597352.92
      3422665.29     10595974.96
#Sta/Elev= 30
  1553.8  498.87  2009.9   489.9  2549.5  486.69  2726.8  486.71  2956.6  487.08
  3662.9  485.39  3765.5  486.29  3794.2  482.55    3894  485.65  4391.6  484.64
  4426.8   481.6  4455.6  484.57    4944   486.4  4952.4  486.21  4960.3  483.83
  4974.7  472.22  4988.5  470.36  5010.4  473.03  5031.4  484.53  5052.5  485.78
  5247.8  482.42  5284.8   485.5  5551.2  484.85  5623.3  479.83  5629.3  482.86
  5722.8  480.93  5767.5  485.48  6113.2  492.51    6408  501.85  6656.4  503.46
#Mann= 11 ,-1 , 0
  1553.8     .05       0  2549.5      .1       0  2726.8     .16       0
  2956.6     .05       0  3662.9     .16       0    3894     .05       0
    4944     .12       0  4952.4     .07       0  5052.5     .12       0
  5284.8     .16       0  6113.2     .05       0
#XS Ineff= 2 , 0
       0  4931.6  486.37               0
Permanent Ineff=
       F       F
Bank Sta=4952.4,5052.5
XS Rating Curve= 0 ,0
Exp/Cntr=0.3,0.1

Type RM Length L Ch R = 1 ,937614  ,2519,2519,2519
BEGIN DESCRIPTION:
NAVASOTA RIVER 049
END DESCRIPTION:
XS GIS Cut Line= 2
      3427357.16     10598294.44      3423556.11     10595107.81
#Sta/Elev= 30
  1438.2  493.17    1554  491.87  1742.2  489.03  1777.4  485.58  2023.6  485.94
  2463.4  482.26  2685.2  481.44  2742.7   481.9  2806.5  477.34  2849.4  482.45
  4028.1  479.67  4141.3  482.69  4155.6  481.16  4162.1  476.39  4176.4  476.33
  4190.8  476.77  4205.1  482.17  4313.1  482.15  4893.1  484.41  4964.8  484.46
  4971.4  484.18  4993.5  471.18    5007   468.8  5014.3  470.39  5035.1  484.15
  5042.9  484.49  5098.6  483.47  5334.6  483.05  6000.5  486.35  6398.3  498.81
#Mann= 11 ,-1 , 0
  1438.2     .05       0    1554     .16       0  2023.6     .05       0
  2463.4     .16       0  2685.2     .05       0  4313.1     .16       0
  4893.1     .12       0  4964.8     .07       0  5042.9     .12       0
  5098.6     .16       0  5334.6     .05       0
#XS Ineff= 2 , 0
       0  4361.2  482.76               0
Permanent Ineff=
       F       F
Bank Sta=4964.8,5042.9
XS Rating Curve= 0 ,0
Exp/Cntr=0.3,0.1

Type RM Length L Ch R = 1 ,935095  ,3476,3476,3476
BEGIN DESCRIPTION:
NAVASOTA RIVER 050
END DESCRIPTION:
XS GIS Cut Line= 3
      3428115.39     10596955.09      3425644.57     10594630.57
      3424822.09      10594046.1
#Sta/Elev= 30
  1607.6  489.91  1831.8  489.32  2093.2  481.14  2574.3  478.13  2709.1  479.16
  2735.9  476.84  2747.9  476.07  2765.4  478.85  2843.4  479.78  2935.2  478.41
    3176  480.15    3657  478.93  3932.5  481.07    3975  478.66  4067.3  480.18
  4888.6  481.64  4951.3  483.12  4965.5  480.05  4972.8   476.7  4979.7  470.45
  4993.6  467.66  5003.4  468.46    5008  472.42  5028.9   482.5    5140  481.66
  5273.8  480.63  5539.3  483.06    5682  486.16    5825  492.31    6009  495.13
#Mann= 8 ,-1 , 0
  1607.6     .05       0  2735.9     .16       0  2747.9     .05       0
  4888.6     .16       0  4951.3     .07       0  5028.9     .12       0
    5140     .16       0  5273.8     .05       0
#XS Ineff= 2 , 0
       0  3932.5  481.07               0
Permanent Ineff=
       F       F
Bank Sta=4951.3,5028.9
XS Rating Curve= 0 ,0
Exp/Cntr=0.3,0.1

Type RM Length L Ch R = 1 ,931619  ,3193,3193,3193
BEGIN DESCRIPTION:
NAVASOTA RIVER 051
END DESCRIPTION:
XS GIS Cut Line= 3
      3429585.31     10595914.73      3427163.95     10593335.49
      3426516.56     10592969.52
#Sta/Elev= 30
  1962.4  486.44  2118.3  483.06    2540   478.4  2603.5  474.24    2646  476.01
  2688.5  472.29    2731  476.98  2801.8  477.83  2851.2  475.81  2985.5  478.23
  3763.6  477.28  3862.7  474.06  3941.5   476.6  4278.9   477.8  4671.4  477.02
  4676.5  472.84  4718.9  478.11  4803.7  477.62  4888.1  479.17  4959.3  480.14
  4994.7  465.12  5009.1  467.66  5023.2  477.01  5037.4  479.92  5075.9  478.97
  5637.2  479.48    5718  476.54  6068.8  478.99  6187.2   481.8  6243.8  488.16
#Mann= 10 ,-1 , 0
  1962.4     .05       0  2118.3     .16       0  3941.5      .1       0
  4278.9     .16       0  4671.4     .12       0  4803.7     .16       0
  4888.1     .12       0  4959.3     .07       0  5037.4     .12       0
  5075.9     .05       0
#XS Ineff= 2 , 0
       0  4641.3  479.03               0
Permanent Ineff=
       F       F
Bank Sta=4959.3,5037.4
XS Rating Curve= 0 ,0
Exp/Cntr=0.3,0.1

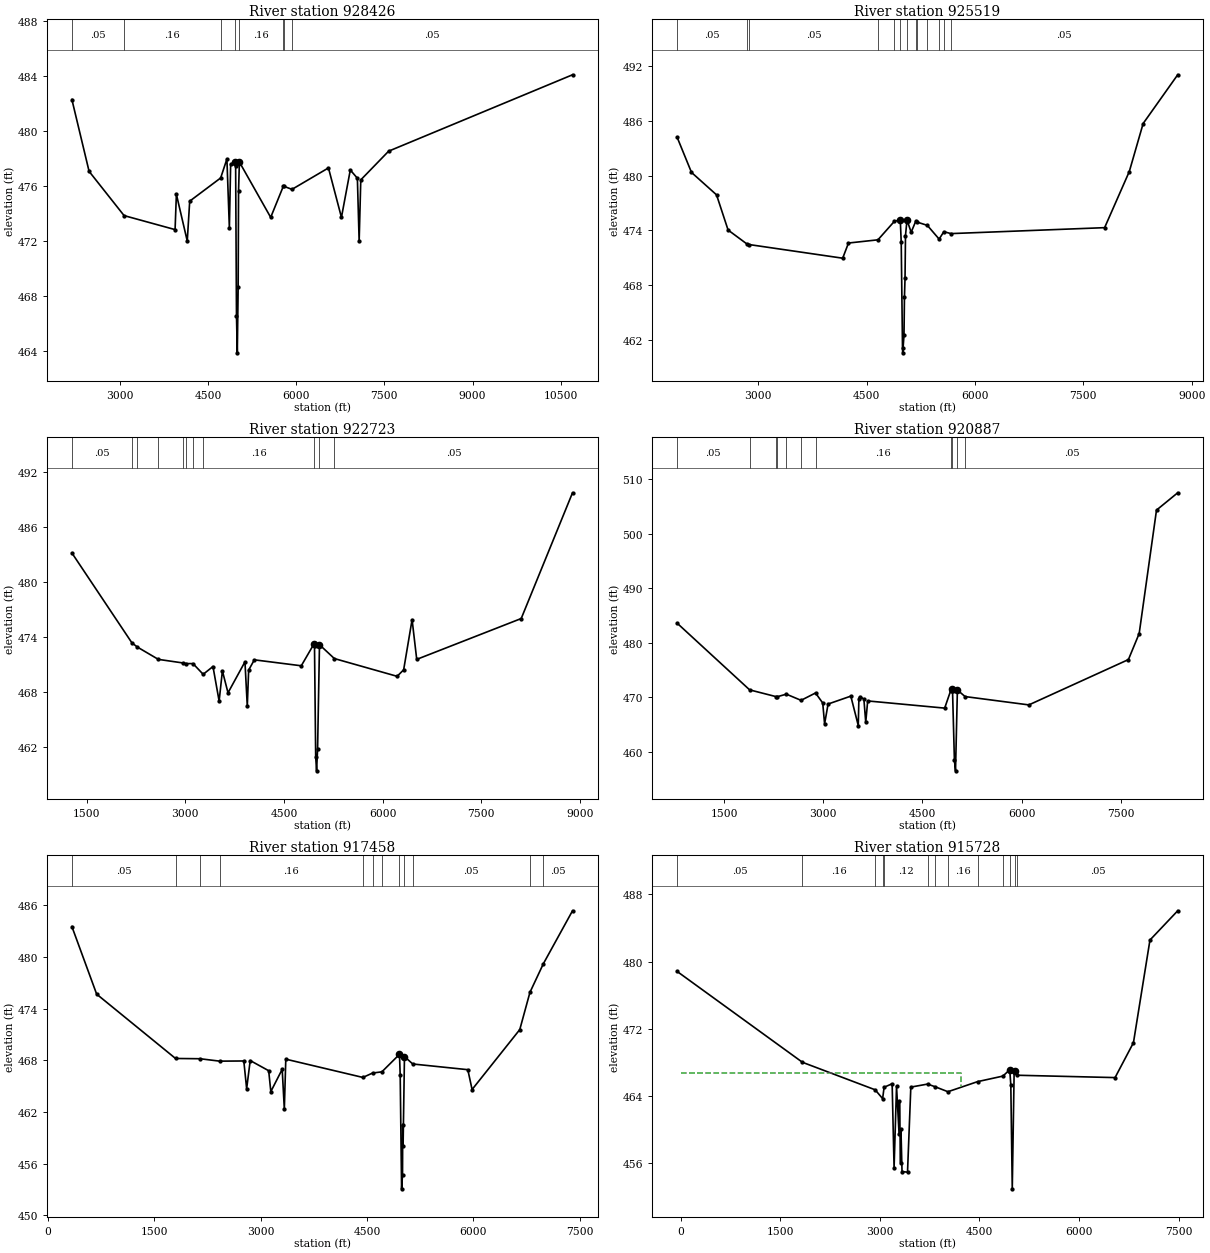
Type RM Length L Ch R = 1 ,928426  ,2907,2907,2907
BEGIN DESCRIPTION:
NAVASOTA RIVER 052
END DESCRIPTION:
XS GIS Cut Line= 4
      3431143.37     10594674.15      3430579.15     10593528.34
      3428356.92     10591679.38      3424026.17     10591314.87
#Sta/Elev= 30
    2186  482.31  2478.6  477.08  3073.7  473.86    3941  472.84  3963.2  475.41
    4148  472.01  4189.7  474.91  4716.4   476.6  4822.4  477.98  4864.3  472.97
  4886.2   477.6  4964.3  477.79  4970.8  477.46  4985.2  466.58  4999.2  463.87
  5013.8  468.68  5020.4  475.62  5034.6  477.76  5567.1  473.73  5782.4     476
  5786.6     476  5929.2  475.77  6549.5  477.33  6770.3  473.73  6920.8  477.18
  7041.3  476.58  7071.4  471.99  7099.2  476.46  7573.1  478.55 10700.1  484.11
#Mann= 8 ,-1 , 0
    2186     .05       0  3073.7     .16       0  4716.4     .12       0
  4964.3     .07       0  5034.6     .16       0  5782.4      .1       0
  5786.6     .16       0  5929.2     .05       0
Bank Sta=4964.3,5034.6
XS Rating Curve= 0 ,0
Exp/Cntr=0.3,0.1

Type RM Length L Ch R = 1 ,925519  ,2796,2796,2796
BEGIN DESCRIPTION:
NAVASOTA RIVER 053
END DESCRIPTION:
XS GIS Cut Line= 3
      3432167.66     10594572.61      3430846.54     10591740.27
      3427896.16     10589334.18
#Sta/Elev= 30
  1874.7   484.2  2074.4  480.34    2421  477.89  2581.1  474.04  2841.3  472.52
  2873.7  472.45    4168  470.96  4248.2  472.62  4656.2  472.97  4883.3  474.99
  4965.4  475.17  4978.5   472.7  4996.3  461.11  4999.1  460.61  5016.9  462.52
  5023.3  466.72  5031.2  468.76  5037.7  473.44  5058.5  475.14    5116   473.8
  5179.7     475  5198.1  474.91  5340.1  474.55  5503.3  473.05  5568.9  473.86
  5666.5  473.65    7795   474.3  8136.8  480.44  8328.5  485.69  8807.1  491.02
#Mann= 13 ,-1 , 0
  1874.7     .05       0  2841.3     .16       0  2873.7     .05       0
  4656.2     .16       0  4883.3     .12       0  4965.4     .07       0
  5058.5     .12       0  5179.7     .05       0  5198.1     .16       0
  5340.1     .12       0  5503.3     .05       0  5568.9     .16       0
  5666.5     .05       0
Bank Sta=4965.4,5058.5
XS Rating Curve= 0 ,0
Exp/Cntr=0.3,0.1

Type RM Length L Ch R = 1 ,922723  ,1836,1836,1836
BEGIN DESCRIPTION:
NAVASOTA RIVER 054
END DESCRIPTION:
XS GIS Cut Line= 3
      3433965.59     10593604.96      3431756.97     10590714.59
      3428112.83      10589136.2
#Sta/Elev= 30
  1277.3  483.18  2189.1  473.37  2273.6   472.9  2591.4  471.56  2964.7  471.17
  3013.4   471.1  3117.9   471.1  3272.7  469.93  3421.6  470.78  3515.1  467.01
  3564.9   470.3  3650.2  467.91  3907.8  471.29  3943.1  466.45  3963.9  470.39
  4050.2  471.51  4763.9  470.86  4952.9   473.2  4964.7  473.05  4982.7  460.93
  4996.3  459.39  5011.6  461.76  5040.5  473.16  5266.4  471.65  6220.3  469.71
  6319.7  470.42  6447.9   475.9  6518.4  471.56  8106.5  476.02  8886.2  489.75
#Mann= 11 ,-1 , 0
  1277.3     .05       0  2189.1      .1       0  2273.6     .16       0
  2591.4     .05       0  2964.7      .1       0  3013.4     .05       0
  3117.9      .1       0  3272.7     .16       0  4952.9     .07       0
  5040.5     .12       0  5266.4     .05       0
Bank Sta=4952.9,5040.5
XS Rating Curve= 0 ,0
Exp/Cntr=0.3,0.1

Type RM Length L Ch R = 1 ,920887  ,3429,3429,3429
BEGIN DESCRIPTION:
NAVASOTA RIVER 055
END DESCRIPTION:
XS GIS Cut Line= 3
      3434111.83      10593520.7      3431754.49     10588611.67
      3430190.36     10587169.98
#Sta/Elev= 30
   787.8   483.6  1885.4  471.35  2291.1  470.09  2293.2  470.06    2441  470.56
  2663.2  469.43  2882.1  470.78    2991  468.94  3019.2   465.1    3072  468.75
  3415.9   470.2  3528.5  464.81  3537.9  469.65  3551.1   470.1  3613.5  469.67
  3641.7   465.4    3671  469.32  4835.8     468  4924.6  471.14  4946.7   471.5
  4954.6  471.16  4982.8  458.48  4999.6  456.49  5028.1  471.33  5144.2  470.12
    6109  468.59  7615.1  476.91  7777.9  481.69  8039.9  504.34  8360.7  507.52
#Mann= 11 ,-1 , 0
   787.8     .05       0  1885.4     .16       0  2291.1     .05       0
  2293.2     .16       0    2441     .05       0  2663.2      .1       0
  2882.1     .16       0  4924.6     .12       0  4946.7     .07       0
  5028.1     .12       0  5144.2     .05       0
Bank Sta=4946.7,5028.1
XS Rating Curve= 0 ,0
Exp/Cntr=0.3,0.1

Type RM Length L Ch R = 1 ,917458  ,1730,1730,1730
BEGIN DESCRIPTION:
NAVASOTA RIVER 060
END DESCRIPTION:
XS GIS Cut Line= 3
      3434323.77     10593570.17      3433957.66     10588921.37
      3433732.62     10586530.64
#Sta/Elev= 30
   336.8  483.51   686.4  475.67  1799.5  468.21  2145.3  468.18  2421.6   467.9
  2762.8  467.92  2802.9   464.7  2853.1  467.97  3113.9  466.79    3144  464.37
  3304.5  466.95  3334.6  462.35  3355.4  468.13  4443.1  466.01  4579.9  466.52
  4711.2  466.66  4959.6  468.69  4969.6  466.27  4989.4  453.09  5002.4  454.71
  5005.3  460.55  5010.4  458.05  5029.9  468.43  5147.1  467.57  5923.8  466.91
  5984.1  464.61    6657  471.56  6800.5  475.88  6990.6  479.21  7401.3  485.34
#Mann= 12 ,-1 , 0
   336.8     .05       0  1799.5      .1       0  2145.3     .05       0
  2421.6     .16       0  4443.1     .12       0  4579.9     .16       0
  4711.2     .12       0  4959.6     .07       0  5029.9     .12       0
  5147.1     .05       0  6800.5      .1       0  6990.6     .05       0
Bank Sta=4959.6,5029.9
XS Rating Curve= 0 ,0
Exp/Cntr=0.3,0.1

Type RM Length L Ch R = 1 ,915728  ,4732,4732,4732
BEGIN DESCRIPTION:
NAVASOTA RIVER 059
END DESCRIPTION:
XS GIS Cut Line= 3
      3437426.11     10593309.92      3435086.82     10588828.88
      3434006.53     10586587.98
#Sta/Elev= 30
   -54.9  478.84    1834  468.03  2929.1  464.76  3042.1  463.71  3064.1  465.06
  3185.3  465.48  3214.5  455.47  3251.5  465.18  3290.1  459.46  3295.7  463.37
  3312.2  456.11  3317.8   460.1  3334.2  455.04  3416.9  454.96  3466.8  465.08
  3720.1  465.44  3833.1  465.12  4025.9  464.53  4472.6  465.73  4854.5  466.39
  4956.8  467.15  4973.2  465.36  4995.1  452.98  5023.5  466.94  5040.6  467.04
  5069.4  466.49  6543.9  466.21  6820.8  470.36  7069.6  482.57  7487.7  486.05
#Mann= 13 ,-1 , 0
   -54.9     .05       0    1834     .16       0  2929.1     .12       0
  3042.1     .16       0  3064.1     .12       0  3720.1     .16       0
  3833.1     .12       0  4025.9     .16       0  4472.6     .05       0
  4854.5     .12       0  4956.8     .07       0  5040.6     .12       0
  5069.4     .05       0
#XS Ineff= 2 , 0
       0  4217.2  466.77               0
Permanent Ineff=
       F       F
Bank Sta=4956.8,5040.6
XS Rating Curve= 0 ,0
Exp/Cntr=0.3,0.1

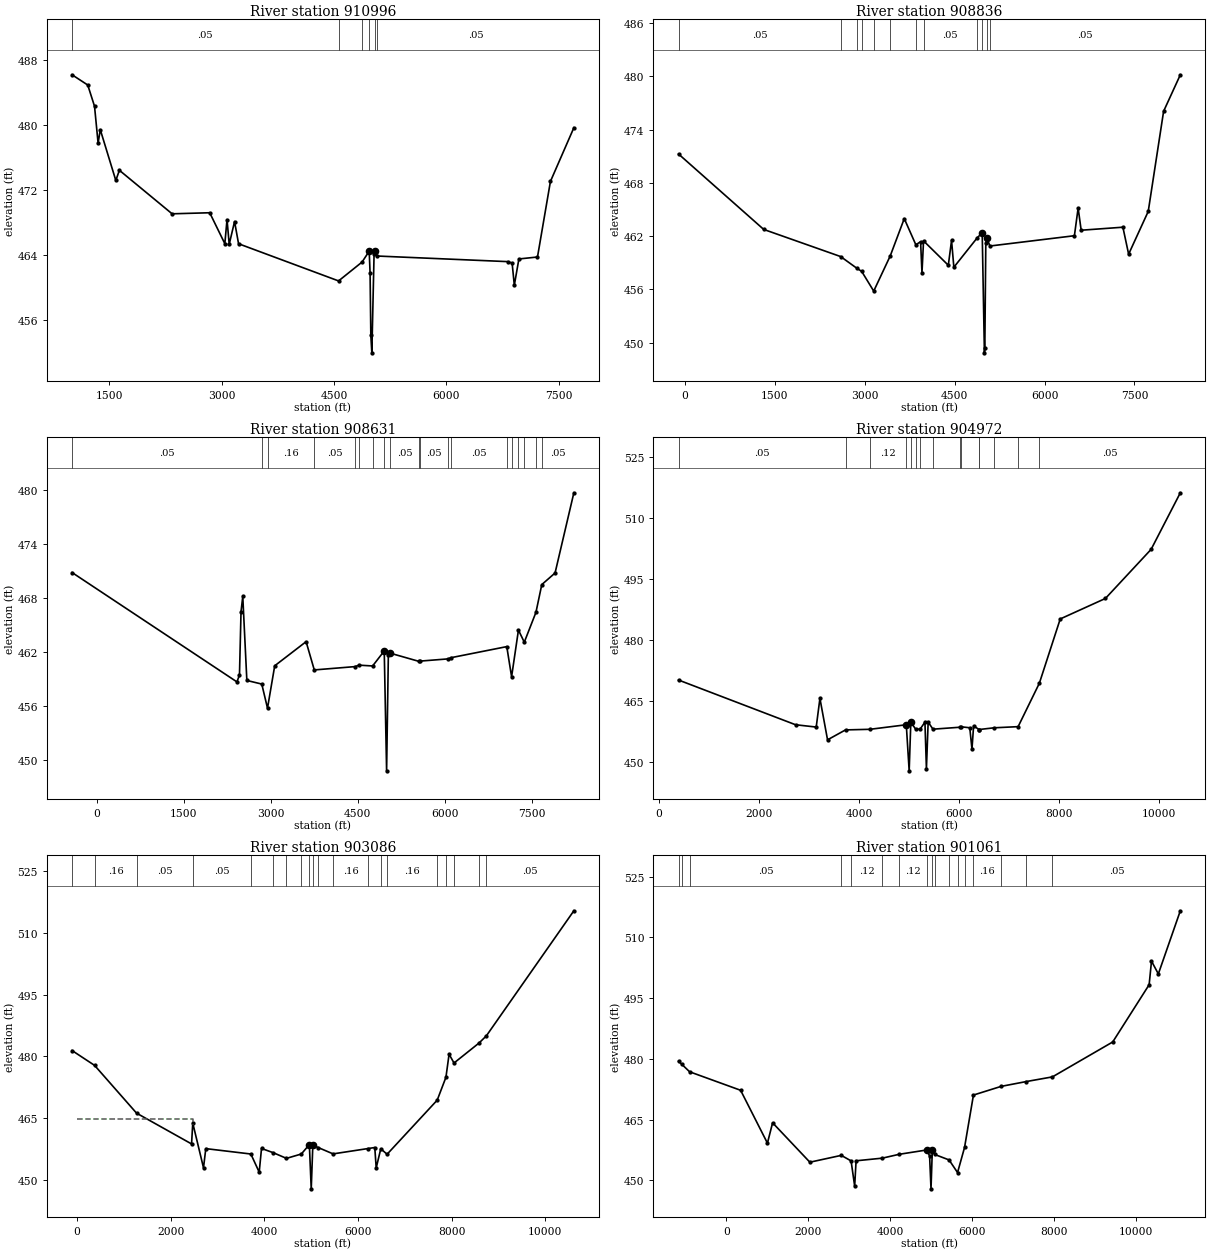
Type RM Length L Ch R = 1 ,910996  ,2160,2160,2160
BEGIN DESCRIPTION:
NAVASOTA RIVER 058
END DESCRIPTION:
XS GIS Cut Line= 3
      3439441.51     10592324.99      3437662.79     10588043.02
       3435752.2     10587266.97
#Sta/Elev= 30
  1002.5  486.16  1211.9   484.9  1302.3  482.29    1350  477.76  1379.3  479.41
  1586.5  473.17  1634.2  474.42    2338  469.07  2840.1   469.2  3041.9   465.4
  3071.1  468.36  3100.4  465.33  3171.8  468.12  3225.1  465.39  4560.3  460.82
    4874  463.14  4969.3  464.48  4980.9  461.79    4991  454.12  5004.5  451.98
  5034.3  464.14  5045.1  464.45  5076.1  463.88  6823.6  463.19  6877.2  463.01
  6906.6  460.29  6967.5  463.52  7215.8  463.76  7388.6  473.05  7701.4  479.65
#Mann= 6 ,-1 , 0
  1002.5     .05       0  4560.3     .16       0    4874     .12       0
  4969.3     .07       0  5045.1     .12       0  5076.1     .05       0
Bank Sta=4969.3,5045.1
XS Rating Curve= 0 ,0
Exp/Cntr=0.3,0.1

Type RM Length L Ch R = 1 ,908836  ,205,205,205
BEGIN DESCRIPTION:
NAVASOTA RIVER 056
END DESCRIPTION:
XS GIS Cut Line= 4
      3440992.36      10591281.7      3441102.18     10588318.23
      3439012.11     10587857.25      3435830.47     10587121.52
#Sta/Elev= 30
  -105.8  471.26  1315.2  462.76  2599.1   459.7  2869.7  458.38  2949.7  458.03
  3150.5  455.81  3425.7  459.77    3660  463.98  3853.3  461.03  3932.4  461.38
  3955.5  457.86  3981.7  461.47    4395  458.72  4448.9  461.52  4487.5   458.5
  4873.4  461.78  4960.3  462.39  4997.2  448.85  5003.9  449.37  5020.5  461.25
  5041.1  461.75  5088.8  460.89  6498.5  462.05  6560.7  465.17  6611.4  462.67
  7307.5  463.01  7403.2  459.97  7730.2  464.79  7986.8  476.08  8265.6  480.19
#Mann= 12 ,-1 , 0
  -105.8     .05       0  2599.1      .1       0  2869.7     .05       0
  2949.7     .07       0  3150.5     .16       0  3425.7     .05       0
  3853.3     .16       0  3981.7     .05       0  4873.4      .1       0
  4960.3     .07       0  5041.1      .1       0  5088.8     .05       0
Bank Sta=4960.3,5041.1
XS Rating Curve= 0 ,0
Exp/Cntr=0.3,0.1

Type RM Length L Ch R = 1 ,908631  ,3659,3659,3659
BEGIN DESCRIPTION:
NAVASOTA RIVER 057
END DESCRIPTION:
XS GIS Cut Line= 4
      3441042.19     10591209.89      3441352.18     10588193.23
       3439056.8     10587662.31      3435876.34     10586926.86
#Sta/Elev= 30
  -424.1  470.79    2419  458.64  2462.6   459.4  2489.4  466.44  2519.6  468.14
  2589.9   458.8  2847.1   458.4    2946  455.72  3070.4  460.43  3611.6  463.11
  3752.5  459.97  4456.7  460.34  4524.1   460.5  4758.4  460.41    4959  462.08
  4999.8  448.76  5029.8   461.6  5051.3  461.85  5563.2  460.91  5576.4  460.95
  6066.2   461.2  6102.7  461.32  7072.1  462.56  7155.1  459.21  7273.3   464.4
  7373.9  463.05  7575.1  466.37  7675.7  469.45  7904.7  470.74  8228.8  479.65
#Mann= 19 ,-1 , 0
  -424.1     .05       0  2847.1     .08       0    2946     .16       0
  3752.5     .05       0  4456.7     .08       0  4524.1     .05       0
  4758.4     .16       0    4959     .04       0  5051.3     .05       0
  5563.2     .08       0  5576.4     .05       0  6066.2     .08       0
  6102.7     .05       0  7072.1     .08       0  7155.1     .05       0
  7273.3     .08       0  7373.9     .05       0  7575.1     .08       0
  7675.7     .05       0
Bank Sta=4959,5051.3
XS Rating Curve= 0 ,0
Exp/Cntr=0.3,0.1

Type RM Length L Ch R = 1 ,904972  ,1886,1886,1886
BEGIN DESCRIPTION:
NAVASOTA RIVER 107
END DESCRIPTION:
XS GIS Cut Line= 5
      3441102.99     10591111.07      3441862.43     10588417.05
      3441053.65     10586602.84      3441124.18     10586761.07
       3439058.2      10582126.8
#Sta/Elev= 30
   387.9   470.2  2727.6   459.2  3140.6  458.63  3214.7  465.68  3367.2  455.49
  3726.2  457.93    4217  458.08  4941.4   459.2  4999.1  447.86  5032.2  459.85
  5128.7  458.11  5217.8  458.11  5314.3  459.85    5344  448.36  5378.7  459.85
  5475.1  458.11  6017.7  458.59  6044.3  458.68  6210.8  458.46  6254.6   453.2
  6287.4  458.91  6397.4  458.02  6401.3  458.03  6699.3  458.45  7177.5  458.73
  7602.2  469.42  8019.5  485.23  8922.8  490.27    9837  502.36 10420.4  516.27
#Mann= 15 ,-1 , 0
   387.9     .05       0  3726.2     .16       0    4217     .12       0
  4941.4     .07       0  5032.2     .12       0  5128.7     .16       0
  5217.8     .12       0  5475.1     .16       0  6017.7     .12       0
  6044.3     .16       0  6397.4     .12       0  6401.3     .16       0
  6699.3     .05       0  7177.5     .16       0  7602.2     .05       0
Bank Sta=4941.4,5032.2
XS Rating Curve= 0 ,0
Exp/Cntr=0.3,0.1

Type RM Length L Ch R = 1 ,903086  ,2025,2025,2025
BEGIN DESCRIPTION:
NAVASOTA RIVER 063
END DESCRIPTION:
XS GIS Cut Line= 4
      3444103.89     10591302.49      3443469.71     10588800.36
      3442236.13     10586593.81      3439211.82     10581868.94
#Sta/Elev= 30
  -107.4  481.44   373.8  477.83  1269.9  466.22  2445.2  458.73  2470.8   463.8
  2700.2  452.93  2749.3  457.59  3711.8  456.28  3890.2  451.86  3939.4  457.63
  4191.9  456.59  4472.5  455.22  4789.7  456.28  4961.5  458.57  5001.6  447.81
  5035.6  458.41  5152.9  457.84  5468.3  456.31  6215.8  457.61    6359  457.86
  6389.4   452.9  6487.2  457.55  6622.1  456.22  7692.7  469.38    7879  474.94
  7946.2  480.55  8051.6  478.41  8584.1  483.25  8742.3  485.01 10611.7  515.43
#Mann= 20 ,-1 , 0
  -107.4     .05       0   373.8     .16       0  1269.9     .05       0
  2470.8     .05       0  3711.8     .12       0  4191.9     .05       0
  4472.5     .16       0  4789.7     .12       0  4961.5     .07       0
  5035.6     .12       0  5152.9     .05       0  5468.3     .16       0
  6215.8     .16       0  6487.2     .12       0  6622.1     .16       0
  7692.7     .05       0    7879     .16       0  8051.6     .05       0
  8584.1     .16       0  8742.3     .05       0
#XS Ineff= 2 , 0
       0  2478.6  464.74               0
Permanent Ineff=
       F       F
Bank Sta=4961.5,5035.6
XS Rating Curve= 0 ,0
Exp/Cntr=0.3,0.1

Type RM Length L Ch R = 1 ,901061  ,3452,3452,3452
BEGIN DESCRIPTION:
NAVASOTA RIVER 064
END DESCRIPTION:
XS GIS Cut Line= 4
      3444553.26     10591363.95      3445119.19     10589138.27
      3443189.81     10585785.25      3440513.94     10580319.51
#Sta/Elev= 30
   -1165  479.43 -1081.1  478.62  -894.3  476.81   350.5  472.24  1005.3  459.18
  1131.5  464.21  2041.4  454.47  2808.4  456.16  3047.8  454.79    3135  448.56
  3169.7  454.82  3809.2  455.47  4224.8  456.43  4899.9   457.5  4964.5  455.99
  4998.9  447.89  5030.4  457.37  5090.3  456.38  5439.9  455.03    5647  451.91
  5817.9  458.13  6034.8  471.06    6709   473.2  7326.5   474.4  7963.2  475.55
  9435.4  484.18 10324.2  498.32 10381.8  504.15 10548.8  500.99 11085.6  516.59
#Mann= 17 ,-1 , 0
   -1165     .05       0 -1081.1     .16       0  -894.3     .05       0
  2808.4     .16       0  3047.8     .12       0  3809.2     .16       0
  4224.8     .12       0  4899.9     .07       0  5030.4     .12       0
  5090.3     .05       0  5439.9     .12       0    5647     .16       0
  5817.9     .05       0  6034.8     .16       0    6709     .05       0
  7326.5     .16       0  7963.2     .05       0
#XS Ineff= 2 , 0
       0  1131.5  464.21               0
Permanent Ineff=
       F       F
Bank Sta=4899.9,5030.4
XS Rating Curve= 0 ,0
Exp/Cntr=0.3,0.1

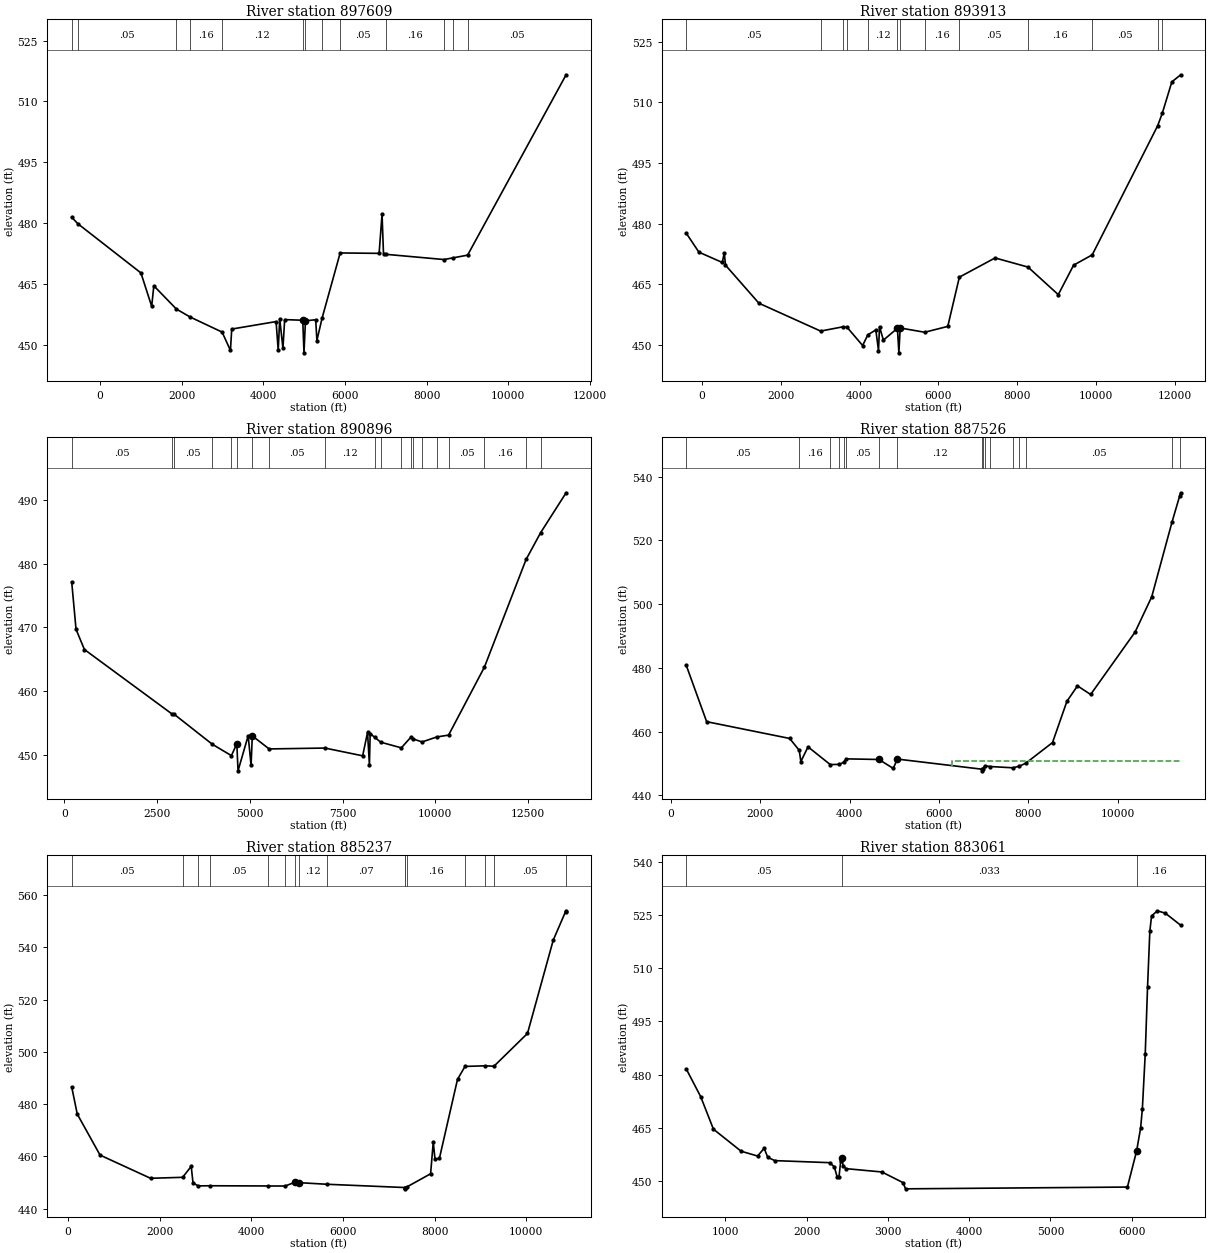
Type RM Length L Ch R = 1 ,897609  ,3696,3696,3696
BEGIN DESCRIPTION:
NAVASOTA RIVER 062
END DESCRIPTION:
XS GIS Cut Line= 3
      3446399.45     10590850.01      3444597.88     10585448.53
      3440961.93     10580162.48
#Sta/Elev= 30
    -694  481.47  -545.9  479.88  1001.5  467.74    1265  459.51  1317.7  464.57
  1868.8  458.85  2206.1  456.88  2990.2  453.16  3194.1  448.64  3225.7  453.91
    4312  455.75  4364.2  448.72  4401.5  456.43  4480.2  449.15  4522.3  456.24
  4965.1  456.08  4995.5  448.05  5031.6  455.95  5282.6   456.2  5311.8  451.09
  5440.5  456.66  5881.6  472.66  6835.8  472.56  6907.5  482.21  6943.3  472.44
  6995.2  472.33  8423.5  471.04  8646.1  471.45  9003.2  472.12 11415.8  516.56
#Mann= 13 ,-1 , 0
    -694     .16       0  -545.9     .05       0  1868.8      .1       0
  2206.1     .16       0  2990.2     .12       0  4965.1     .07       0
  5031.6     .12       0  5440.5     .16       0  5881.6     .05       0
  6995.2     .16       0  8423.5     .05       0  8646.1     .16       0
  9003.2     .05       0
#XS Ineff= 2 , 0
       0  1317.7  464.57  6907.5       0  482.21
Permanent Ineff=
       F       F
Bank Sta=4965.1,5031.6
XS Rating Curve= 0 ,0
Exp/Cntr=0.3,0.1

Type RM Length L Ch R = 1 ,893913  ,3017,3017,3017
BEGIN DESCRIPTION:
NAVASOTA RIVER 061
END DESCRIPTION:
XS GIS Cut Line= 3
      3447517.51     10590395.19      3446383.47     10585113.46
      3441293.52     10580082.62
#Sta/Elev= 30
  -402.1  477.59   -81.4  472.92   511.8  470.37   562.9  472.74   593.6  469.71
  1442.5  460.29  3010.7   453.4  3587.8  454.48  3686.6  454.29  4076.9  449.83
  4208.9  452.47  4412.4  453.69  4480.2  448.59  4506.1  454.48  4604.8  451.16
  4960.9   454.1  4998.1  448.02  5030.5  454.17  5654.5  453.11  6239.7  454.56
  6534.6  466.74  7441.8  471.49  8278.1  469.23    9047  462.41  9435.9   469.7
  9909.9  472.26 11571.4  504.18   11688  507.25   11932  515.04 12156.6  516.79
#Mann= 13 ,-1 , 0
  -402.1     .05       0  3010.7     .16       0  3587.8      .1       0
  3686.6     .16       0  4208.9     .12       0  4960.9     .07       0
  5030.5     .12       0  5654.5     .16       0  6534.6     .05       0
  8278.1     .16       0  9909.9     .05       0 11571.4     .08       0
   11688     .05       0
#XS Ineff= 2 , 0
       0                  7441.8       0  471.49
Permanent Ineff=
       F       F
Bank Sta=4960.9,5030.5
XS Rating Curve= 0 ,0
Exp/Cntr=0.3,0.1

Type RM Length L Ch R = 1 ,890896  ,3370,3370,3370
BEGIN DESCRIPTION:
NAVASOTA RIVER 065
END DESCRIPTION:
XS GIS Cut Line= 4
      3449015.76       10590250.      3448262.72     10585508.93
      3447852.18     10582851.22      3448720.24     10577078.66
#Sta/Elev= 30
   199.5  477.15   316.4   469.7   542.1  466.53  2911.4  456.37  2948.1  456.42
  3988.2  451.65  4504.7  449.86  4650.6  451.73  4683.1  447.47  4956.8  452.99
  5034.7  448.33  5068.1  452.96  5521.9  450.91  7025.7  451.05  8042.7  449.83
  8174.2  453.51  8224.8  448.39    8245  453.31    8367  452.74  8530.6  451.97
    9085  451.08  9335.1  452.71  9400.7  452.48  9645.5  452.01 10045.7   452.8
 10358.6  453.08 11323.8  463.75 12447.7  480.67 12837.8  484.86 13526.7  491.15
#Mann= 20 ,-1 , 0
   199.5     .05       0  2911.4     .16       0  2948.1     .05       0
  3988.2     .16       0  4504.7     .12       0  4650.6     .07       0
  5068.1     .12       0  5521.9     .05       0  7025.7     .12       0
    8367     .16       0  8530.6     .05       0    9085      .1       0
  9335.1     .05       0  9400.7      .1       0  9645.5     .05       0
 10045.7      .1       0 10358.6     .05       0 11323.8     .16       0
 12447.7     .05       0 12837.8     .16       0
#XS Ineff= 2 , 0
       0                  8174.2       0  453.51
Permanent Ineff=
       F       F
Bank Sta=4650.6,5068.1
XS Rating Curve= 0 ,0
Exp/Cntr=0.3,0.1

Type RM Length L Ch R = 1 ,887526  ,2289,2289,2289
BEGIN DESCRIPTION:
NAVASOTA RIVER 066
END DESCRIPTION:
XS GIS Cut Line= 4
      3449848.41      10590215.1      3450193.73     10585579.65
      3450302.19     10584115.47      3453230.96     10580145.35
#Sta/Elev= 30
   351.7  480.74   806.4   463.1  2661.5  457.84  2876.5  454.11  2912.2  450.59
  3072.7   455.2  3568.1  449.65  3764.2   449.7  3868.4  450.32  3925.7  451.44
  4657.1  451.24  4977.9  448.44  5068.2  451.37  6967.6  448.18  6970.3  447.68
  6973.6  448.18    7025  449.28  7134.3  449.04  7655.2  448.63  7797.9  449.17
  7933.2  450.01  8536.8  456.55  8858.9   469.5    9095  474.33  9388.8  471.63
 10382.8  491.22 10754.5  502.28   11209  525.78 11380.3  533.98 11401.7   534.9
#Mann= 17 ,-1 , 0
   351.7     .05       0  2876.5     .16       0  3568.1     .12       0
  3764.2     .07       0  3868.4     .12       0  3925.7     .05       0
  4657.1     .07       0  5068.2     .12       0  6967.6     .07       0
  6973.6     .12       0    7025     .07       0  7134.3     .16       0
  7655.2     .12       0  7797.9     .16       0  7933.2     .05       0
   11209     .16       0 11380.3     .05       0
#XS Ineff= 2 , 0
       0                  6281.5       0   450.8
Permanent Ineff=
       F       F
Bank Sta=4657.1,5068.2
XS Rating Curve= 0 ,0
Exp/Cntr=0.3,0.1

Type RM Length L Ch R = 1 ,885237  ,2176,2176,2176
BEGIN DESCRIPTION:
NAVASOTA RIVER 067
END DESCRIPTION:
XS GIS Cut Line= 3
      3450724.73      10590801.2      3452011.28     10586057.67
      3453816.18     10580474.99
#Sta/Elev= 30
    85.1  486.56   206.3  476.15   703.3  460.45  1804.6  451.57  2504.6  451.94
  2691.2  456.13    2731  449.81  2841.7  448.66  3107.9  448.71  4369.3  448.63
  4739.2   448.6  4947.6  450.01  5037.9   449.9  5653.7  449.28    7347  448.03
  7349.7  447.53    7353  448.03    7395  448.26  7912.2   453.3  7970.1  465.46
  8008.2   458.9  8104.3   459.2    8499  489.45  8662.4   494.4  9098.4  494.63
  9294.4  494.48 10024.9  507.03   10587  542.76 10855.3  553.67 10867.2  553.99
#Mann= 16 ,-1 , 0
    85.1     .05       0  2504.6     .16       0  2841.7     .07       0
  3107.9     .05       0  4369.3     .07       0  4739.2     .12       0
  4947.6     .07       0  5037.9     .12       0  5653.7     .07       0
    7347     .07       0    7353     .07       0    7395     .16       0
  8662.4     .05       0  9098.4     .16       0  9294.4     .05       0
 10855.3      .1       0
Bank Sta=4947.6,5037.9
XS Rating Curve= 0 ,0
Exp/Cntr=0.3,0.1

Type RM Length L Ch R = 1 ,883061  ,1296,1296,1296
BEGIN DESCRIPTION:
NAVASOTA RIVER 076
END DESCRIPTION:
XS GIS Cut Line= 3
      3451009.43     10590870.71      3453409.79      10587088.5
      3454537.81      10585950.4
#Sta/Elev= 30
   520.4  481.54   696.9  473.79   854.4   464.6  1194.4   458.4  1397.4  457.04
  1478.6  459.23    1522  456.69  1608.9  455.75  2283.5  455.17  2341.1  454.01
  2377.6  451.05  2398.7   451.1  2419.9  455.63  2435.2  456.36  2449.8  454.24
  2485.4  453.49  2926.5  452.55  3187.4  449.54  3217.7   447.8    5947   448.3
  6060.1  458.46  6109.6  464.97  6130.8  470.33  6166.1  485.76  6194.4  504.55
  6222.7  520.35  6243.9  524.65  6314.7  526.12  6413.7  525.44  6602.4  522.04
#Mann= 3 , 0 , 0
   520.4     .05       0  2435.2    .033       0  6060.1     .16       0
Bank Sta=2435.2,6060.1
XS Rating Curve= 0 ,0
Exp/Cntr=0.3,0.1

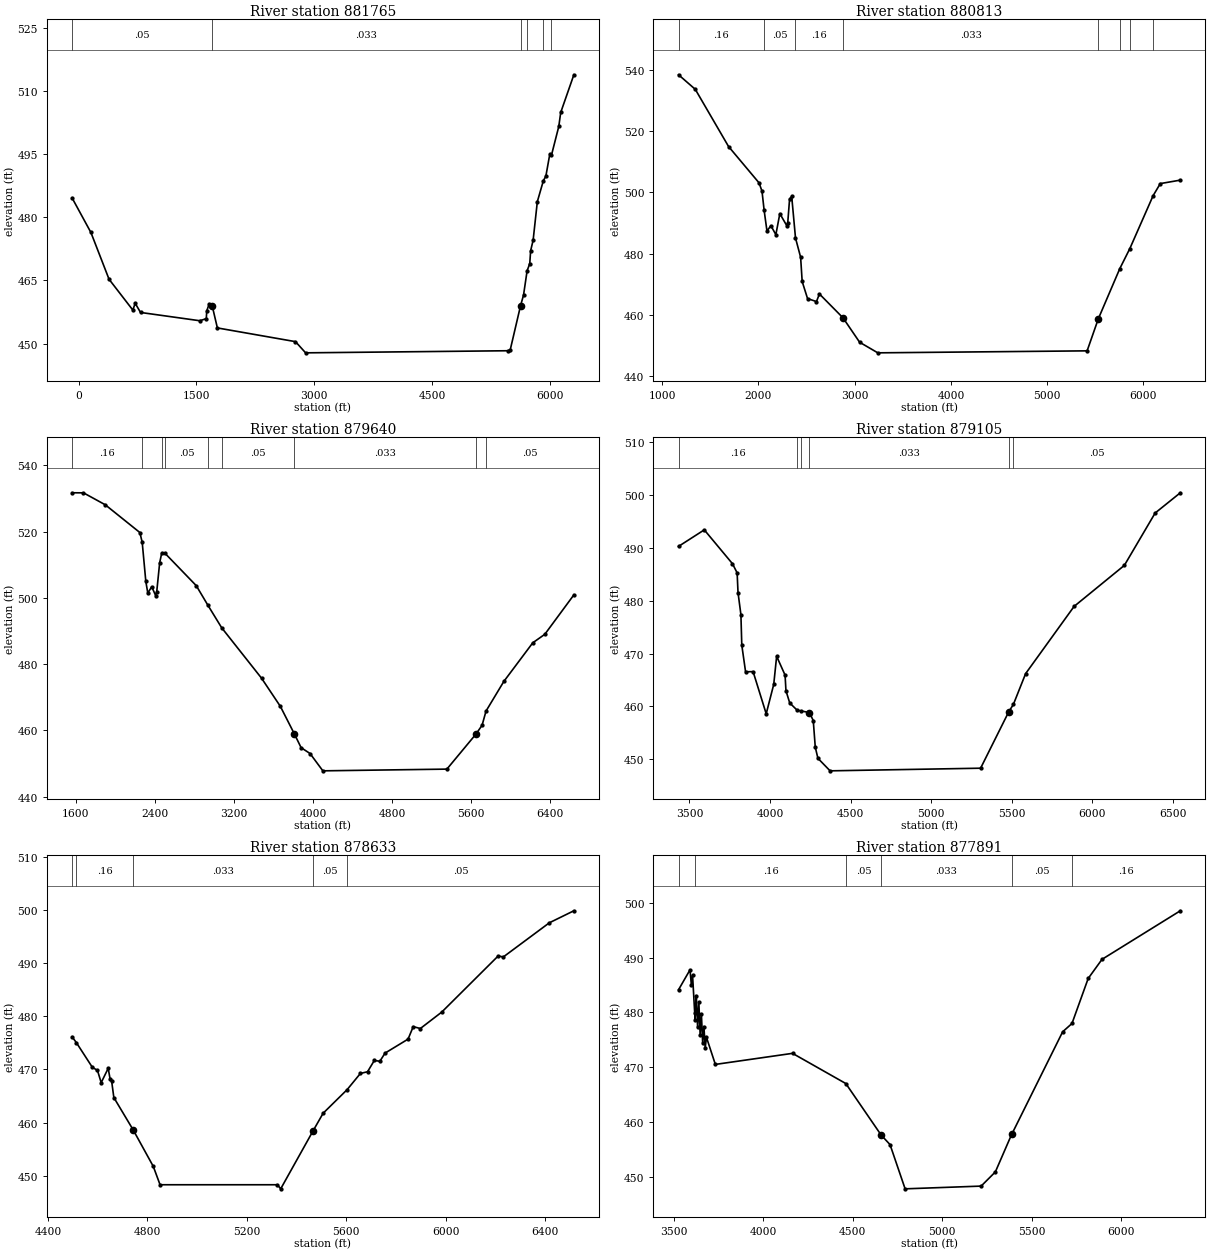
Type RM Length L Ch R = 1 ,881765  ,952,952,952
BEGIN DESCRIPTION:
NAVASOTA RIVER 077
END DESCRIPTION:
XS GIS Cut Line= 4
      3451062.16     10591057.09      3452581.22     10590254.16
      3454599.63     10587562.85      3455066.04      10586347.9
#Sta/Elev= 30
   -82.3  484.63   157.4  476.41   388.2  465.29   690.7  457.97   720.7  459.58
   788.6   457.4  1542.9  455.43  1625.3  455.93  1630.9  457.74  1660.1  459.34
  1701.8  458.86  1766.3  453.72  2760.1  450.46  2888.8   447.8  5467.3   448.3
  5491.9  448.51  5622.6  458.96  5661.3  461.54  5706.5  467.29  5740.4  469.02
  5751.4  472.06  5783.2  474.57  5836.8  483.75  5913.4  488.71  5945.5  489.82
  5994.8  494.99  6016.9  494.81  6109.5  501.61  6134.2  504.94  6301.4   513.9
#Mann= 6 ,-1 , 0
   -82.3     .05       0  1701.8    .033       0  5622.6     .05       0
  5706.5     .16       0  5913.4     .08       0  6016.9     .16       0
Bank Sta=1701.8,5622.6
XS Rating Curve= 0 ,0
Exp/Cntr=0.3,0.1

Type RM Length L Ch R = 1 ,880813  ,1173,1173,1173
BEGIN DESCRIPTION:
NAVASOTA RIVER 078
END DESCRIPTION:
XS GIS Cut Line= 3
      3456368.11     10591664.74      3455471.06     10587941.48
      3455695.31     10586576.17
#Sta/Elev= 30
  1170.2  538.29  1344.2  533.55  1689.8  514.91  2006.6  503.06  2037.4  500.35
  2059.6   494.1  2088.9  487.38    2130  489.09  2181.4  486.17  2222.6  493.03
  2294.6  489.11  2304.9  490.05  2323.8  497.75    2346  498.64  2385.4  485.09
  2438.6  478.82  2454.7  470.91  2510.6  465.34  2603.2  464.36    2634  466.84
    2879  459.06  3051.8   451.1  3240.6  447.65  5415.3   448.3  5531.4  458.73
    5755  475.12  5859.1  481.64  6100.7  498.87  6175.4  502.82  6383.6  503.95
#Mann= 8 ,-1 , 0
  1170.2     .16       0  2059.6     .05       0  2385.4     .16       0
    2879    .033       0  5531.4     .16       0    5755     .05       0
  5859.1     .16       0  6100.7     .05       0
Bank Sta=2879,5531.4
XS Rating Curve= 0 ,0
Exp/Cntr=0.3,0.1

Type RM Length L Ch R = 1 ,879640  ,535,535,535
BEGIN DESCRIPTION:
NAVASOTA RIVER 079
END DESCRIPTION:
XS GIS Cut Line= 3
      3456648.06       10591607.      3456615.45     10588172.26
      3456387.65     10586550.58
#Sta/Elev= 30
  1565.1   531.7  1680.5  531.68  1900.5  528.08  2250.5   519.7  2274.2  516.73
  2310.5  504.98  2330.5  501.44  2370.5  503.34  2410.5  500.64  2420.5  501.69
  2450.5  510.55  2470.5  513.38  2503.1  513.48  2820.5  503.67  2939.5  497.69
  3077.5  490.96  3480.5  475.74  3670.6  467.24  3810.6  459.02  3880.6  454.77
  3970.6  453.01  4100.3  447.78  5354.1   448.3  5646.9  458.83  5709.7  461.52
  5749.9  465.83  5929.7  474.76  6222.5  486.43  6343.7  488.98  6637.6  500.88
#Mann= 9 ,-1 , 0
  1565.1     .16       0  2274.2     .05       0  2470.5     .16       0
  2503.1     .05       0  2939.5     .16       0  3077.5     .05       0
  3810.6    .033       0  5646.9     .16       0  5749.9     .05       0
Bank Sta=3810.6,5646.9
XS Rating Curve= 0 ,0
Exp/Cntr=0.3,0.1

Type RM Length L Ch R = 1 ,879105  ,472,472,472
BEGIN DESCRIPTION:
NAVASOTA RIVER 084
END DESCRIPTION:
XS GIS Cut Line= 3
      3457712.23     10589370.23      3457086.88     10587932.44
       3456455.3     10586519.58
#Sta/Elev= 30
  3432.1  490.29    3592  493.42    3767  487.01  3795.9  485.28  3801.4  481.56
  3819.4  477.36  3824.8  471.61  3848.3  466.55  3895.1  466.58  3976.4   458.6
  4023.2  464.17  4041.2  469.48  4093.6  465.92    4099  462.98  4122.5  460.65
  4168.5  459.28  4192.9  459.14  4245.1  458.83  4268.6  457.31  4281.1  452.27
  4297.5  450.17    4373   447.8  5307.6   448.3  5482.8  459.01  5510.9  460.36
  5587.2  466.21  5888.1  478.93  6200.2   486.7  6391.3  496.61  6547.6  500.44
#Mann= 6 ,-1 , 0
  3432.1     .16       0  4168.5     .07       0  4192.9     .05       0
  4245.1    .033       0  5482.8     .16       0  5510.9     .05       0
Bank Sta=4245.1,5482.8
XS Rating Curve= 0 ,0
Exp/Cntr=0.3,0.1

Type RM Length L Ch R = 1 ,878633  ,742,742,742
BEGIN DESCRIPTION:
NAVASOTA RIVER 083
END DESCRIPTION:
XS GIS Cut Line= 3
      3457882.39     10587933.46      3457466.14     10587651.42
      3456503.91     10586481.37
#Sta/Elev= 30
  4497.2  476.15  4514.4  475.06  4578.4  470.43  4599.4  469.81  4614.3  467.52
  4642.5  470.22  4650.3  468.15  4656.3  467.81  4665.2  464.71  4743.1  458.61
  4823.7  451.76    4851   448.3    5323   448.3  5336.1  447.53  5465.1  458.35
  5506.7  461.76    5603  466.19  5656.6  469.25  5685.3  469.57  5712.6   471.7
  5734.8  471.54  5755.7  473.08  5848.2  475.71    5869  478.06  5897.7  477.71
  5983.7   480.8  6210.5  491.36  6231.3  491.18  6416.4  497.61  6514.9  499.87
#Mann= 5 ,-1 , 0
  4497.2     .07       0  4514.4     .16       0  4743.1    .033       0
  5465.1     .05       0    5603     .05       0
Bank Sta=4743.1,5465.1
XS Rating Curve= 0 ,0
Exp/Cntr=0.3,0.1

Type RM Length L Ch R = 1 ,877891  ,891,891,891
BEGIN DESCRIPTION:
NAVASOTA RIVER 082
END DESCRIPTION:
XS GIS Cut Line= 3
      3458770.76     10588043.71      3457761.28     10586970.87
      3456555.82     10586405.41
#Sta/Elev= 30
  3526.9  484.12  3591.1  487.76  3598.4  485.06  3605.2   486.8  3619.4  478.69
  3621.2  479.83  3626.3  483.06  3633.5  477.26  3640.4  481.87  3647.7  475.93
  3654.6  479.72  3661.9  474.41  3668.7  477.41    3676  473.53  3682.9  475.45
  3732.7   470.5    4164  472.52  4461.9  467.01  4659.2  457.62    4709  455.87
  4793.3   447.8  5218.2   448.3  5297.7  450.89  5388.5  457.72    5389  457.73
  5673.8  476.45    5726  477.97  5816.5  486.18  5893.8  489.67  6331.5  498.53
#Mann= 6 ,-1 , 0
  3526.9     .05       0  3621.2     .16       0  4461.9     .05       0
  4659.2    .033       0    5389     .05       0    5726     .16       0
Bank Sta=4659.2,5388.5
XS Rating Curve= 0 ,0
Exp/Cntr=0.3,0.1