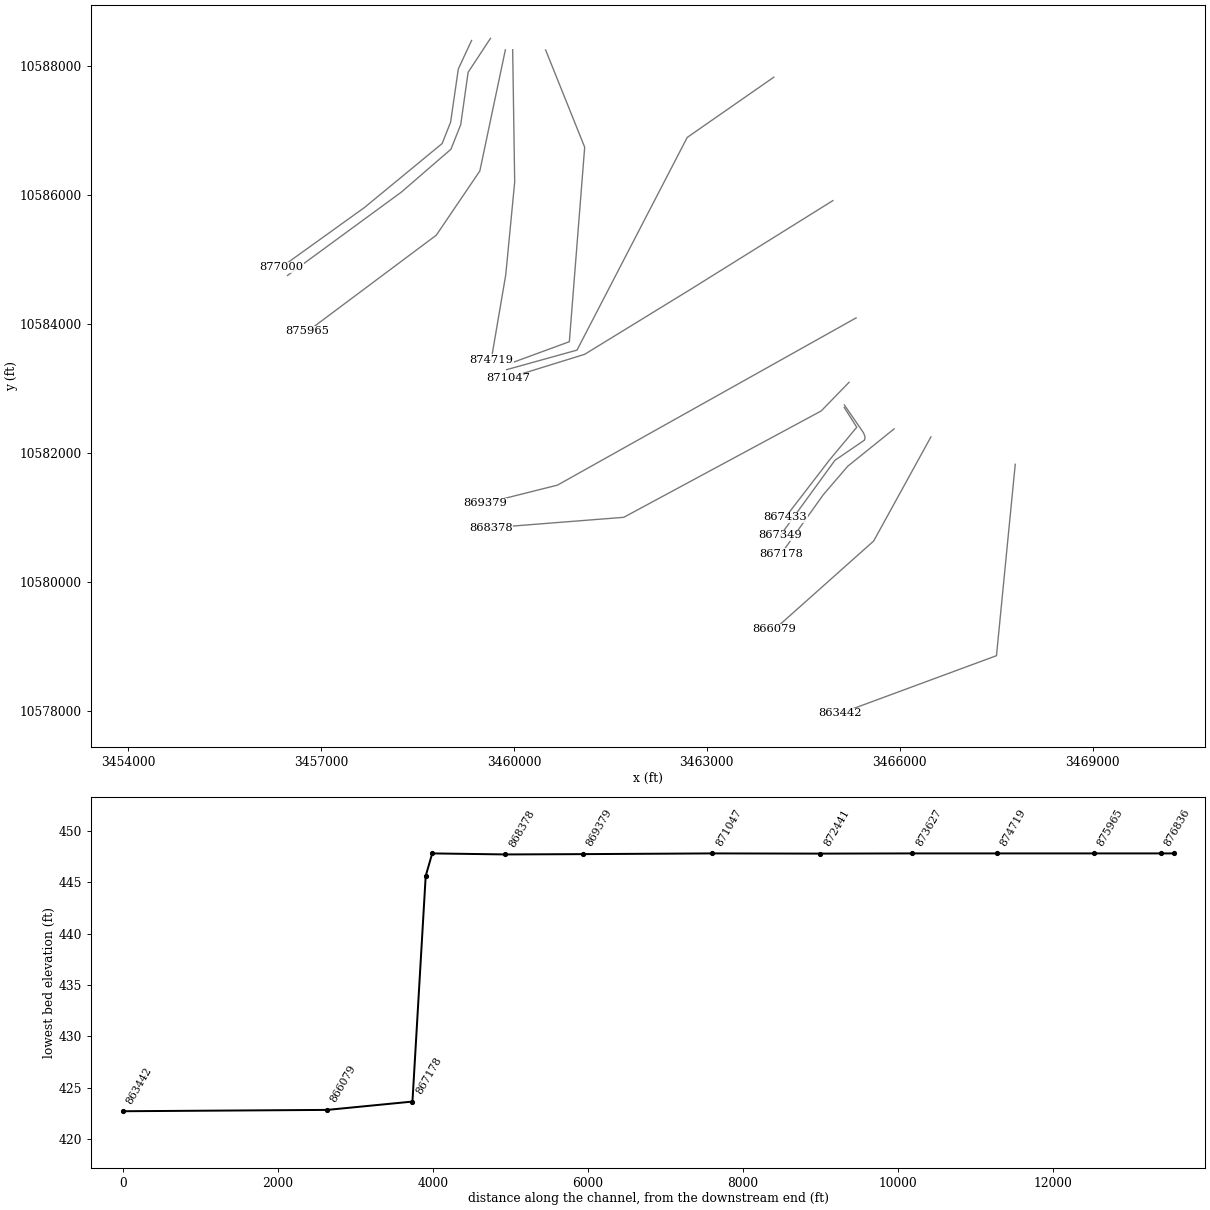
HEC-RAS study NAVASOTA RIVER.prj: NAVASOTA RIVER Base Level Engineering

--- NAVASOTA RIVER.g01 (geometry) --- (continued)

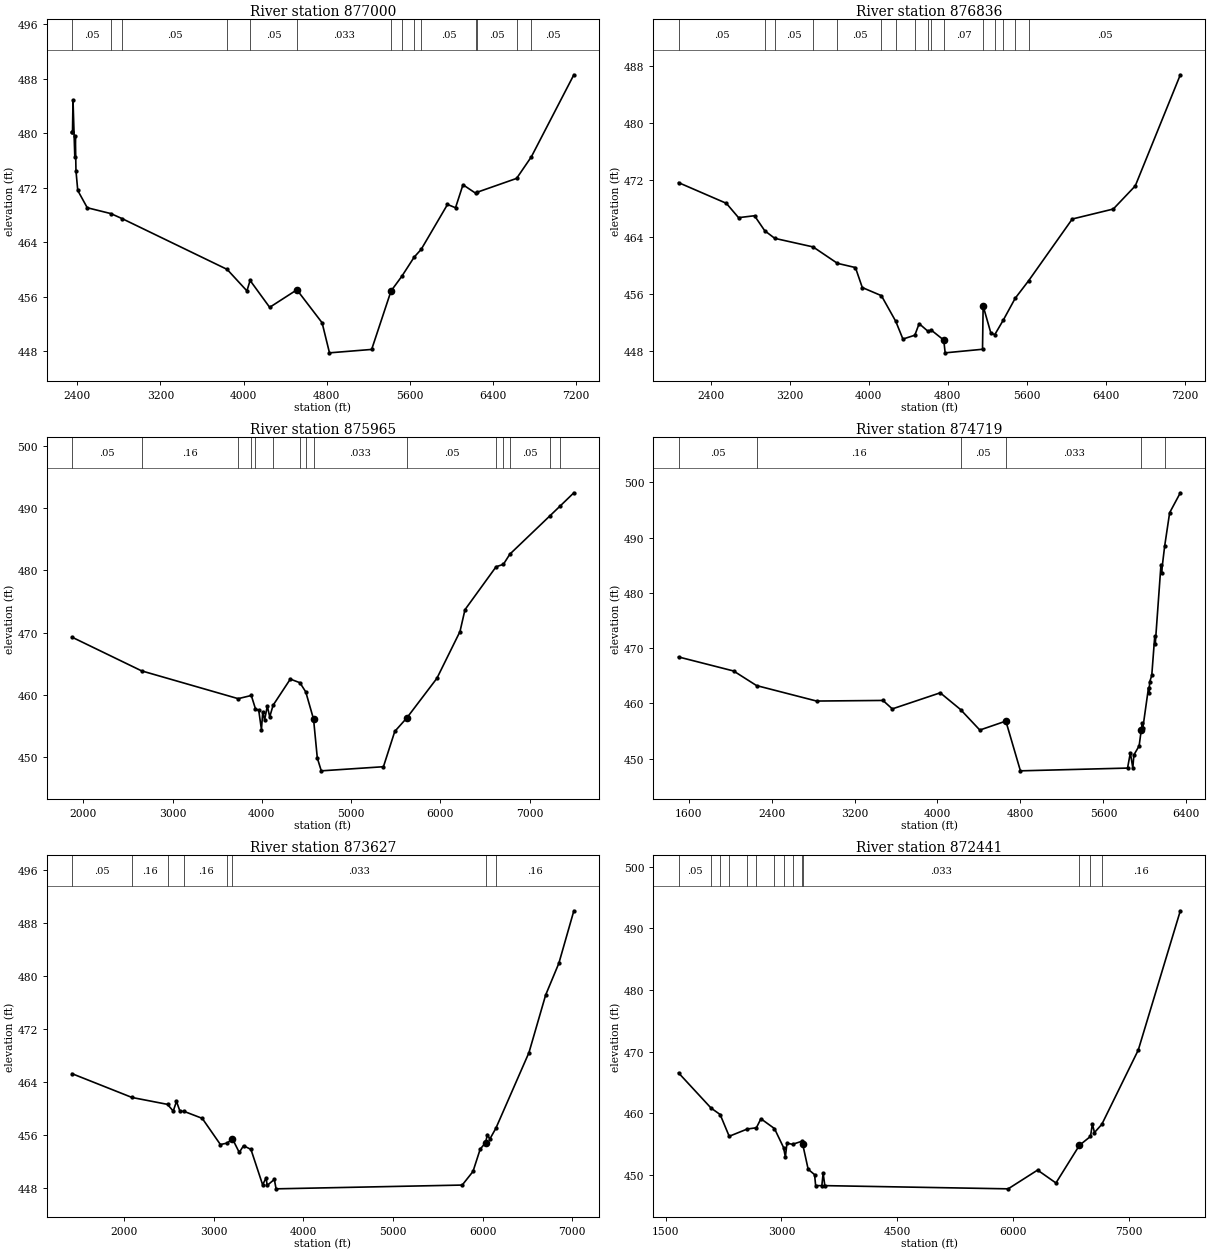
Type RM Length L Ch R = 1 ,877000  ,164,164,164
BEGIN DESCRIPTION:
NAVASOTA RIVER 080
END DESCRIPTION:
XS GIS Cut Line= 6
      3459340.56     10588395.65      3459134.47      10587953.6
      3459014.67     10587128.94      3458882.73     10586797.35
      3457673.53     10585804.29      3456383.61     10584880.69
#Sta/Elev= 30
  2348.3  480.15  2352.4  480.15  2357.4  484.83  2374.7  476.48  2380.2  479.56
  2385.8  474.51  2403.1   471.6  2494.6  469.07  2722.3  468.21  2832.6  467.46
  3842.2  460.03  4032.7  456.88  4063.3  458.41  4251.9  454.47  4514.1  457.04
  4756.9  452.21    4828   447.8  5234.4   448.3    5421  456.87  5524.4  459.01
  5644.3  461.84  5711.5  462.97  5964.9  469.55  6042.3  469.07    6114  472.44
  6235.7   471.2  6246.7  471.32  6630.6  473.37  6772.9  476.54  7182.2  488.56
#Mann= 14 ,-1 , 0
  2348.3     .05       0  2722.3     .08       0  2832.6     .05       0
  3842.2     .16       0  4063.3     .05       0  4514.1    .033       0
    5421     .16       0  5524.4     .05       0  5644.3     .16       0
  5711.5     .05       0  6235.7     .16       0  6246.7     .05       0
  6630.6     .16       0  6772.9     .05       0
Bank Sta=4514.1,5421
XS Rating Curve= 0 ,0
Exp/Cntr=0.3,0.1

Type RM Length L Ch R = 1 ,876836  ,871,871,871
BEGIN DESCRIPTION:
NAVASOTA RIVER 081
END DESCRIPTION:
XS GIS Cut Line= 6
      3459634.54     10588429.06      3459286.81     10587901.72
      3459172.15     10587091.94      3459019.69     10586708.79
      3458246.76     10586042.66      3456476.94     10584750.73
#Sta/Elev= 30
  2075.4  471.65  2559.3  468.75  2682.8  466.74  2844.3  467.01  2948.2   464.9
  3049.6  463.84  3437.2  462.64  3683.5  460.34  3865.6  459.75    3935  456.95
  4128.4  455.81  4273.9  452.21  4346.2  449.73  4466.7  450.27  4510.2  451.89
  4597.3  450.85  4635.2  450.96  4759.3  449.59  4773.6   447.8  5151.7   448.3
    5158  454.37  5236.8  450.54  5275.7  450.35  5361.6  452.38  5482.6  455.45
  5618.1   457.9  6059.9  466.55  6475.1  467.95  6697.5  471.19  7153.5  486.76
#Mann= 16 ,-1 , 0
  2075.4     .05       0  2948.2     .08       0  3049.6     .05       0
  3437.2     .16       0  3683.5     .05       0  4128.4     .05       0
  4273.9     .16       0  4466.7     .05       0  4597.3     .16       0
  4635.2     .05       0  4759.3     .07       0    5158     .07       0
  5275.7     .05       0  5361.6      .1       0  5482.6      .1       0
  5618.1     .05       0
Bank Sta=4759.3,5158
XS Rating Curve= 0 ,0
Exp/Cntr=0.3,0.1

Type RM Length L Ch R = 1 ,875965  ,1246,1246,1246
BEGIN DESCRIPTION:
NAVASOTA RIVER 088
END DESCRIPTION:
XS GIS Cut Line= 4
      3459866.27     10588251.17      3459469.13     10586371.81
       3458791.9     10585376.05      3456792.47     10583886.14
#Sta/Elev= 30
  1874.9  469.26  2653.9  463.85  3734.7  459.39  3881.8   459.9  3927.5   457.8
  3965.4  457.49  3995.2  454.43  4010.2  457.24  4031.2  455.99    4061   458.2
  4088.1  456.46  4125.7  458.33  4318.5  462.53  4425.9  461.95  4491.4  460.48
  4578.9   456.1  4620.9  449.85  4665.4   447.8  5361.2  448.46  5488.3  454.13
  5623.9  456.31    5960  462.66  6218.2  470.16  6274.5  473.68  6622.5  480.57
  6704.5  480.96  6776.6  482.59  7224.8  488.74  7341.2  490.34  7493.5  492.45
#Mann= 15 ,-1 , 0
  1874.9     .05       0  2653.9     .16       0  3734.7     .05       0
  3881.8     .08       0  3927.5     .16       0  4125.7     .05       0
  4425.9     .08       0  4491.4     .05       0  4578.9    .033       0
  5623.9     .05       0  6622.5     .08       0  6704.5     .16       0
  6776.6     .05       0  7224.8     .08       0  7341.2     .05       0
Bank Sta=4578.9,5623.9
XS Rating Curve= 0 ,0
Exp/Cntr=0.3,0.1

Type RM Length L Ch R = 1 ,874719  ,1092,1092,1092
BEGIN DESCRIPTION:
NAVASOTA RIVER 089
END DESCRIPTION:
XS GIS Cut Line= 4
      3459979.91     10588252.52      3460011.16     10586200.47
      3459872.39     10584762.53      3459646.08     10583440.16
#Sta/Elev= 30
  1503.1  468.41    2034  465.87  2255.3  463.23  2834.1  460.43  3474.2  460.54
  3564.3  459.01  4026.4  461.92    4222   458.9  4408.2  455.18  4659.3   456.8
  4799.7   447.8  5832.8   448.3  5859.7  451.07  5883.6   448.3  5893.7  450.67
  5944.4  452.32  5964.7  455.16  5974.8  456.49  5979.9  455.51  6034.9  462.87
    6040  461.89  6045.9  463.88  6066.2  465.07    6095   472.2  6100.1  470.79
  6155.1  485.14  6160.1  483.69  6190.5  488.46  6238.6  494.51  6341.6  498.12
#Mann= 6 ,-1 , 0
  1503.1     .05       0  2255.3     .16       0    4222     .05       0
  4659.3    .033       0  5964.7     .05       0  6190.5     .16       0
Bank Sta=4659.3,5964.7
XS Rating Curve= 0 ,0
Exp/Cntr=0.3,0.1

Type RM Length L Ch R = 1 ,873627  ,1186,1186,1186
BEGIN DESCRIPTION:
NAVASOTA RIVER 018
END DESCRIPTION:
XS GIS Cut Line= 4
      3460492.34     10588248.81      3461099.98     10586740.58
      3460861.26     10583724.08       3459971.5     10583398.56
#Sta/Elev= 30
  1418.1  465.18    2087  461.59    2483  460.55  2547.1  459.53  2583.2     461
  2622.5   459.5  2667.8  459.49  2870.5  458.44  3073.2  454.49  3147.4   454.7
    3208  455.34  3283.8  453.29  3331.5  454.31  3414.2  453.75  3544.6  448.41
  3583.7  449.47  3594.8  448.31    3675  449.22  3694.9   447.8  5771.6  448.37
  5891.9  450.42  5972.2  453.79  6032.4  454.77  6052.4  455.99  6079.8  455.31
  6147.8  456.96  6516.4  468.36  6702.8  477.06  6850.1  481.85  7017.5  489.77
#Mann= 8 ,-1 , 0
  1418.1     .05       0    2087     .16       0    2483     .05       0
  2667.8     .16       0  3147.4     .05       0    3208    .033       0
  6032.4     .05       0  6147.8     .16       0
Bank Sta=3208,6032.4
XS Rating Curve= 0 ,0
Exp/Cntr=0.3,0.1

Type RM Length L Ch R = 1 ,872441  ,1394,1394,1394
BEGIN DESCRIPTION:
NAVASOTA RIVER 019
END DESCRIPTION:
XS GIS Cut Line= 4
      3464040.49     10587825.62      3462695.03     10586892.49
      3460980.62     10583593.87      3459885.92     10583290.39
#Sta/Elev= 30
  1668.3  466.58  2089.4  460.87  2206.5  459.83  2323.7   456.3  2557.9  457.48
  2675.1  457.68    2734  459.14  2909.3  457.55  3026.5  454.48  3050.2  452.94
  3071.1  455.17  3143.6     455  3260.7  455.48  3272.7  455.11  3345.3  450.95
  3428.1  450.08  3441.9   448.3  3522.2   448.3  3538.7  450.33  3560.8   448.3
  5932.3  447.78  6312.7  450.82  6550.3  448.73  6854.2  454.84  6997.2  456.28
  7021.6  458.28  7048.9  456.91  7143.8  458.24  7615.1  470.28  8159.2  492.86
#Mann= 14 ,-1 , 0
  1668.3     .05       0  2089.4     .16       0  2206.5     .16       0
  2323.7     .05       0  2557.9     .08       0  2675.1     .05       0
  2909.3     .16       0  3026.5     .05       0  3143.6     .08       0
  3260.7     .05       0  3272.7    .033       0  6854.2     .16       0
  6997.2     .05       0  7143.8     .16       0
Bank Sta=3272.7,6854.2
XS Rating Curve= 0 ,0
Exp/Cntr=0.3,0.1

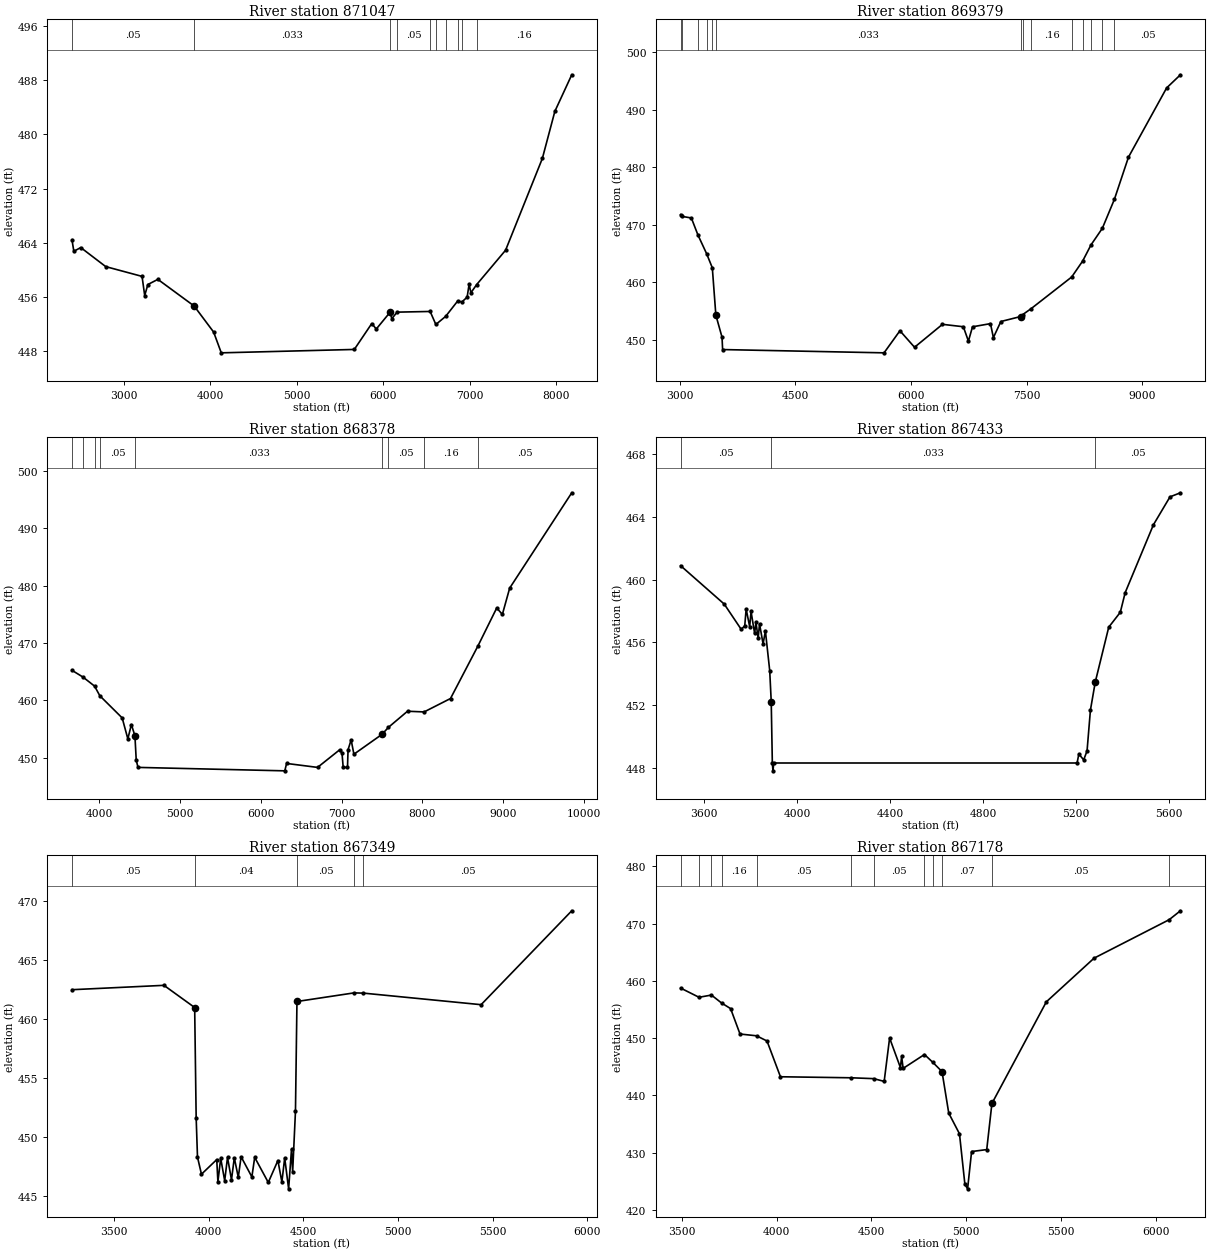
Type RM Length L Ch R = 1 ,871047  ,1668,1668,1668
BEGIN DESCRIPTION:
NAVASOTA RIVER 020
END DESCRIPTION:
XS GIS Cut Line= 4
      3464960.42      10585912.3      3462750.46     10584538.24
      3461099.98     10583528.77      3459906.78     10583159.96
#Sta/Elev= 30
  2397.7  464.47  2419.3  462.77  2499.5  463.32  2788.7  460.51    3209  459.07
  3239.7  456.25  3276.3  457.87    3392  458.63  3812.3   454.7  4037.8  450.86
  4126.1   447.8  5666.2   448.3  5868.4  452.12  5920.6  451.31  6079.3  453.77
  6100.7  452.84  6161.7   453.8  6544.2   453.9  6610.2  451.98  6723.4  453.17
  6862.3  455.43  6912.9  455.31  6972.4  456.01  6995.3  457.91  7016.2  456.66
  7083.3  457.87  7417.6  462.93  7843.1  476.45    7988   483.4  8183.6  488.79
#Mann= 10 ,-1 , 0
  2397.7     .05       0  3812.3    .033       0  6079.3     .16       0
  6161.7     .05       0  6544.2     .08       0  6610.2     .16       0
  6723.4     .05       0  6862.3     .16       0  6912.9     .05       0
  7083.3     .16       0
Bank Sta=3812.3,6079.3
XS Rating Curve= 0 ,0
Exp/Cntr=0.3,0.1

Type RM Length L Ch R = 1 ,869379  ,1001,1001,1001
BEGIN DESCRIPTION:
NAVASOTA RIVER 040
END DESCRIPTION:
XS GIS Cut Line= 3
       3465320.9     10584093.01       3460676.8     10581499.69
      3459548.35     10581217.58
#Sta/Elev= 30
  3010.9  471.77  3031.9  471.46  3149.9  471.19  3236.3   468.2  3347.1     465
  3421.8  462.52  3467.7  454.29  3547.8  450.45  3555.4   448.3  5649.2  447.73
  5855.1  451.57  6044.7   448.7  6406.9  452.69  6677.6  452.27  6743.4  449.77
  6796.4  452.26  7029.7  452.81  7067.2  450.38  7164.3  453.18  7419.1  454.04
  7447.4  454.38  7558.2  455.43  8082.7  460.92  8225.2   463.7  8333.6  466.51
  8480.7   469.4  8636.4  474.42  8819.3  481.77  9314.1  493.81  9493.2   496.1
#Mann= 14 ,-1 , 0
  3010.9     .05       0  3031.9     .16       0  3236.3     .05       0
  3347.1     .16       0  3421.8     .16       0  3467.7    .033       0
  7419.1     .16       0  7447.4     .05       0  7558.2     .16       0
  8082.7     .16       0  8225.2     .05       0  8333.6     .16       0
  8480.7     .16       0  8636.4     .05       0
Bank Sta=3467.7,7419.1
XS Rating Curve= 0 ,0
Exp/Cntr=0.3,0.1

Type RM Length L Ch R = 1 ,868378  ,945,945,945
BEGIN DESCRIPTION:
NAVASOTA RIVER 041
END DESCRIPTION:
XS GIS Cut Line= 4
      3465212.41     10583094.77      3464778.37     10582649.86
      3461707.62     10581000.56       3459636.1     10580837.87
#Sta/Elev= 30
  3664.3  465.24  3801.7  464.05  3944.2  462.48  4009.1   460.8  4285.9  456.93
  4355.7  453.28  4399.6  455.78  4443.4  453.81  4459.6  449.56  4481.6   448.3
  6298.2   447.7  6320.3  448.99  6703.5   448.3  6977.1  451.37  7005.9  450.81
  7020.9   448.3    7074   448.3    7081  451.39  7119.2   453.1  7153.4   450.6
  7502.3  454.08  7579.7  455.28  7816.8   458.1  8022.2  457.98  8348.8  460.32
  8686.9  469.45  8920.5  476.11  8990.8     475    9081  479.58  9849.4  496.22
#Mann= 9 ,-1 , 0
  3664.3     .16       0  3801.7     .05       0  3944.2     .08       0
  4009.1     .05       0  4443.4    .033       0  7502.3     .08       0
  7579.7     .05       0  8022.2     .16       0  8686.9     .05       0
Bank Sta=4443.4,7502.3
XS Rating Curve= 0 ,0
Exp/Cntr=0.3,0.1

Type RM Length L Ch R = 1 ,867433  ,84,84,84
BEGIN DESCRIPTION:
NAVASOTA RIVER 087
END DESCRIPTION:
XS GIS Cut Line= 4
      3465136.62     10582705.37      3465331.93     10582397.23
      3464910.92     10581893.76       3464220.8     10580999.63
#Sta/Elev= 30
  3498.7  460.88  3686.5  458.43  3759.4  456.82  3774.6  457.05  3780.6  458.12
  3795.8  456.99  3801.7  457.96    3817  456.57  3822.9  457.26  3832.3  456.25
  3838.2  457.17  3853.4   455.9  3863.5  456.71    3882  454.19  3888.5  452.22
  3893.3   448.3    3896   447.8  3899.3   448.3  5204.6   448.3  5212.2  448.87
    5233   448.5  5247.5  449.07    5262  451.67  5282.8  453.46  5340.8  456.96
  5390.6  457.91  5411.5  459.16  5533.1  463.49  5604.4  465.27  5649.3  465.53
#Mann= 3 , 0 , 0
  3498.7     .05       0  3888.5    .033       0  5282.8     .05       0
Bank Sta=3888.5,5282.8
XS Rating Curve= 0 ,0
Exp/Cntr=0.3,0.1

Type RM Length L Ch R = 1 ,867349  ,171,171,171
BEGIN DESCRIPTION:
NAVASOTA RIVER 085
END DESCRIPTION:
XS GIS Cut Line= 6
      3465139.03     10582743.38      3465436.33     10582311.97
      3465460.64     10582252.94      3465453.69     10582199.12
      3464991.89     10581884.16      3464143.86     10580721.24
#Sta/Elev= 30
  3277.2  462.49  3763.1  462.86  3925.4  460.98  3933.3  451.64  3940.3   448.3
  3961.3  446.85    4042  448.09  4048.1  446.22    4063  448.19    4084   446.3
  4098.9  448.27  4119.9  446.38  4134.8  448.24  4155.8  446.59  4170.7  448.33
  4227.6  446.62  4242.5  448.28  4314.3  446.15  4365.1  448.01  4386.1  446.19
    4401  448.23  4421.8  445.61    4437  448.97    4443  447.03  4457.9  452.19
  4465.8  461.49  4767.3  462.22  4817.1   462.2  5438.6  461.22  5917.5  469.18
#Mann= 5 ,-1 , 0
  3277.2     .05       0  3925.4     .04       0  4465.8     .05       0
  4767.3      .1       0  4817.1     .05       0
Bank Sta=3925.4,4465.8
XS Rating Curve= 0 ,0
Exp/Cntr=0.3,0.1

Type RM Length L Ch R = 1 ,867178  ,1099,1099,1099
BEGIN DESCRIPTION:
NAVASOTA RIVER 086
END DESCRIPTION:
XS GIS Cut Line= 4
      3465912.58     10582371.79      3465191.25     10581792.38
      3464811.98     10581351.62      3464154.31     10580433.09
#Sta/Elev= 30
  3493.3  458.75  3590.3  457.14  3655.7  457.53  3708.9  456.15  3756.9  455.16
  3806.5  450.72  3893.5  450.41  3948.9   449.5  4019.8  443.25  4393.3  443.07
  4511.5  442.92    4567  442.44  4595.6  450.02  4652.6  444.86  4659.2   446.8
  4666.9  444.71  4779.5  447.14  4823.5  445.77  4872.1  444.15  4907.6  436.89
  4964.2  433.28  4992.8  424.44    5007  423.66  5028.1  430.18    5108  430.52
  5135.3  438.58  5422.5  456.35  5674.3  463.98  6070.3   470.7  6129.7  472.26
#Mann= 12 ,-1 , 0
  3493.3     .05       0  3590.3     .16       0  3655.7     .05       0
  3708.9     .16       0  3893.5     .05       0  4393.3      .1       0
  4511.5     .05       0  4779.5     .16       0  4823.5     .05       0
  4872.1     .07       0  5135.3     .05       0  6070.3     .16       0
Bank Sta=4872.1,5135.3
XS Rating Curve= 0 ,0
Exp/Cntr=0.3,0.1

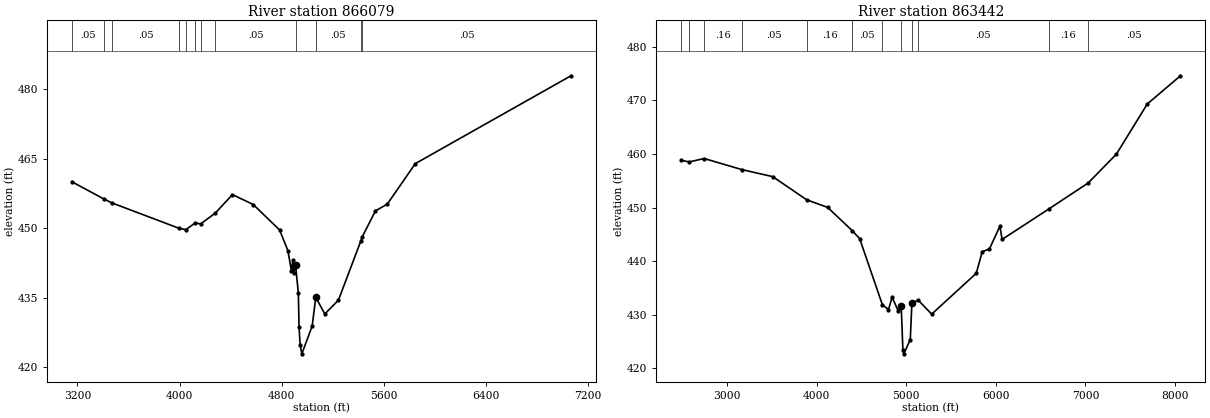
Type RM Length L Ch R = 1 ,866079  ,2637,2637,2637
BEGIN DESCRIPTION:
NAVASOTA RIVER 090
END DESCRIPTION:
XS GIS Cut Line= 3
      3466484.93     10582247.12      3465594.76     10580632.78
      3464051.33     10579261.51
#Sta/Elev= 30
  3156.5  460.01  3406.4   456.3  3469.9  455.44  3999.5  449.92  4050.4  449.68
  4122.5  451.11  4164.9   450.9  4279.4  453.22  4414.2  457.22    4577  455.09
  4783.3  449.59  4848.7  445.11  4876.1  440.69  4886.5  443.04  4892.2  440.22
  4908.3  441.96    4930  436.02  4935.8  428.55  4944.2  424.85  4957.3  422.85
  5038.2  428.83  5066.6  435.04  5137.3  431.46  5243.9  434.44  5418.7  447.17
  5430.4  448.11  5534.1  453.73  5626.1  455.16    5846  463.92  7064.6  482.88
#Mann= 12 ,-1 , 0
  3156.5     .05       0  3406.4     .16       0  3469.9     .05       0
  3999.5     .16       0  4050.4      .1       0  4122.5     .16       0
  4164.9      .1       0  4279.4     .05       0  4908.3     .07       0
  5066.6     .05       0  5418.7      .1       0  5430.4     .05       0
Bank Sta=4908.3,5066.6
XS Rating Curve= 0 ,0
Exp/Cntr=0.3,0.1

Type RM Length L Ch R = 1 ,863442  ,2732,2732,2732
BEGIN DESCRIPTION:
NAVASOTA RIVER 091
END DESCRIPTION:
XS GIS Cut Line= 3
      3467796.96     10581822.81      3467505.04     10578854.57
      3465076.26     10577959.85
#Sta/Elev= 30
  2489.5  458.83  2577.6  458.53  2745.2  459.16  3166.5  457.09  3510.1  455.78
    3889  451.46  4123.1  450.04    4397  445.71  4480.2  444.21  4734.2  431.86
  4801.8  430.99  4842.5  433.29  4912.3  430.66  4943.8   431.7  4962.5   423.5
  4972.3  422.72  5045.1  425.36    5063  432.13  5132.5  432.75  5284.1  430.13
  5781.6  437.75  5848.2  441.78  5928.5  442.28    6045  446.54  6070.1  444.07
  6587.8  449.71  7030.5   454.6    7346  459.99  7690.1  469.34  8060.4   474.6
#Mann= 12 ,-1 , 0
  2489.5     .16       0  2577.6     .05       0  2745.2     .16       0
  3166.5     .05       0    3889     .16       0    4397     .05       0
  4734.2     .16       0  4943.8     .07       0    5063     .16       0
  5132.5     .05       0  6587.8     .16       0  7030.5     .05       0
Bank Sta=4943.8,5063
XS Rating Curve= 0 ,0
Exp/Cntr=0.3,0.1