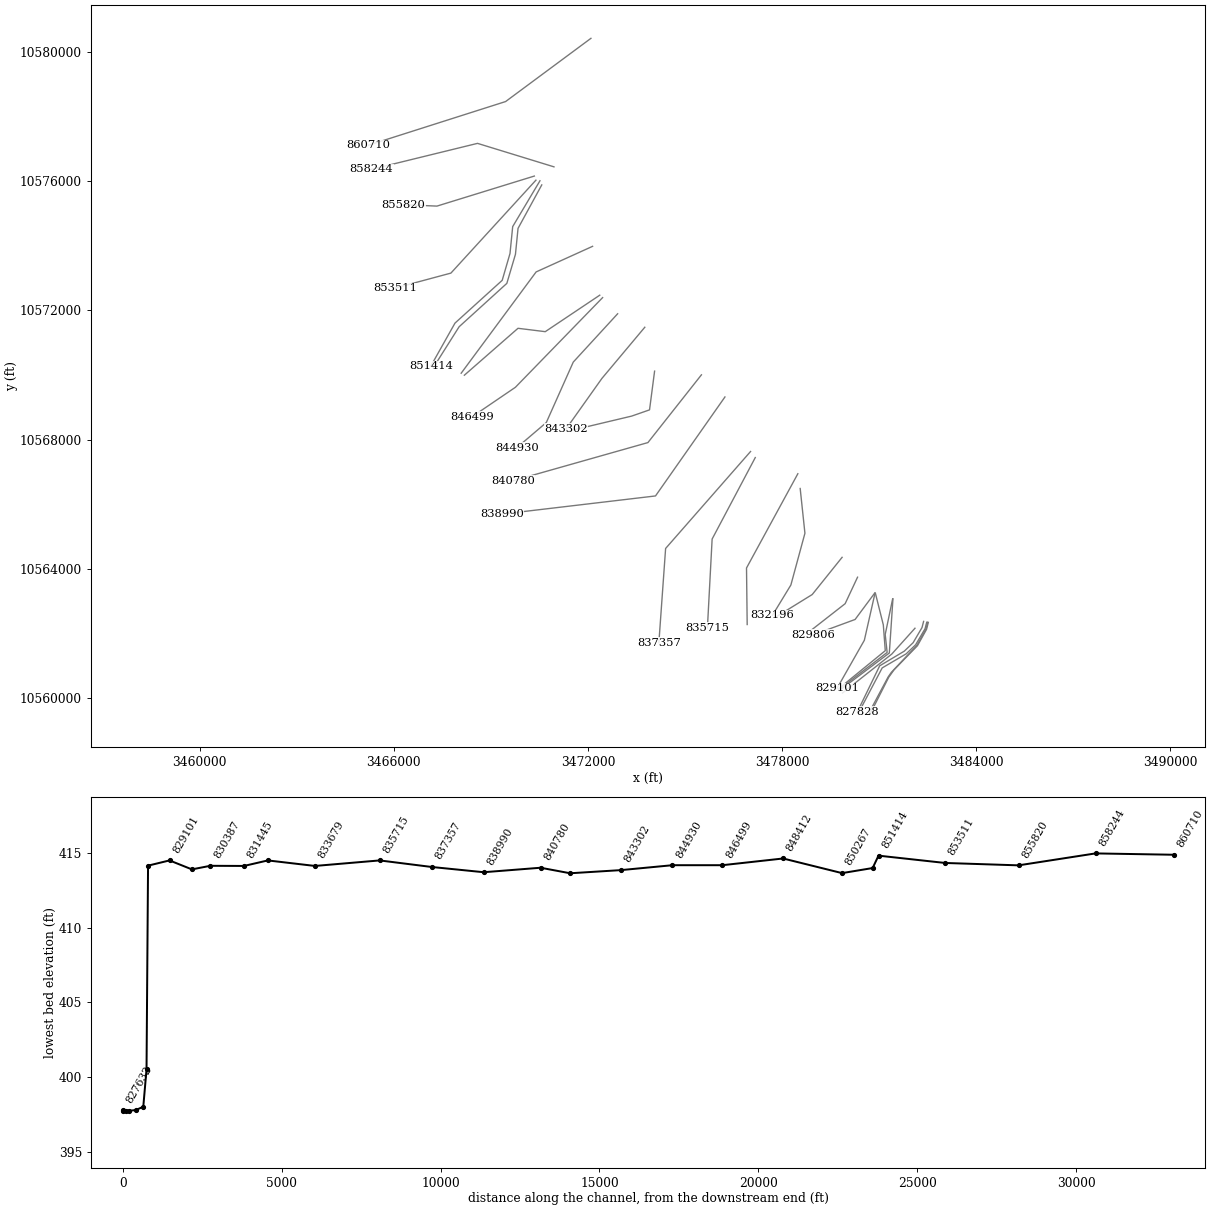
HEC-RAS study NAVASOTA RIVER.prj: NAVASOTA RIVER Base Level Engineering

--- NAVASOTA RIVER.g01 (geometry) --- (continued)

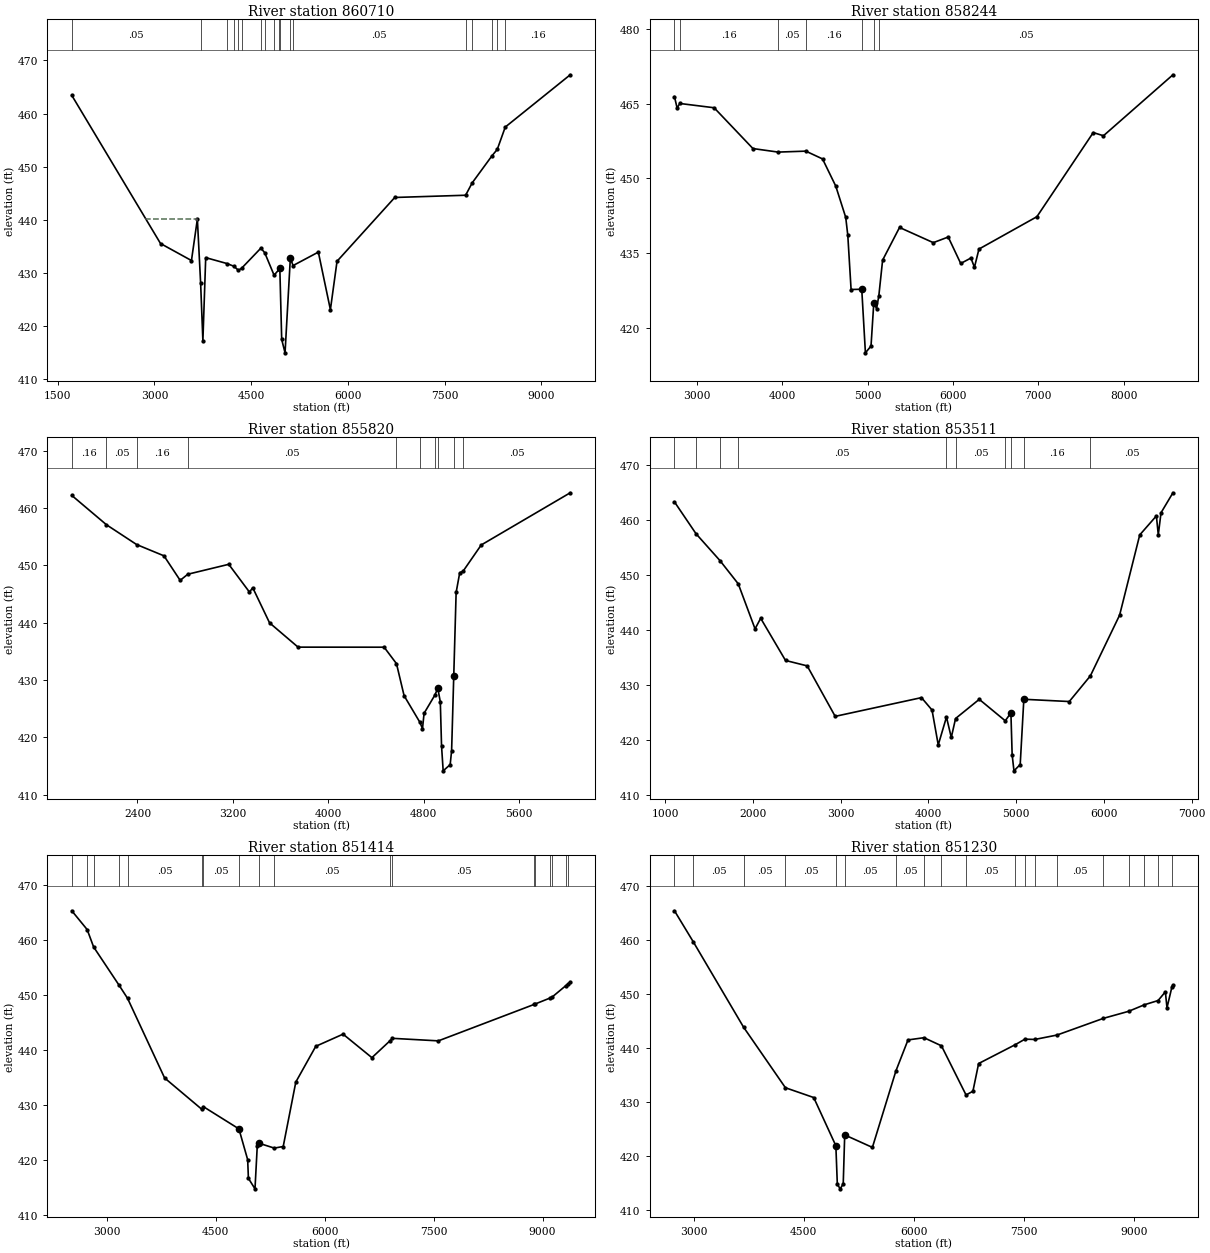
Type RM Length L Ch R = 1 ,860710  ,2466,2466,2466
BEGIN DESCRIPTION:
NAVASOTA RIVER 092
END DESCRIPTION:
XS GIS Cut Line= 3
      3472093.56     10580416.34      3469456.96     10578460.39
      3465216.96     10577108.49
#Sta/Elev= 30
  1717.1  463.42  3093.8  435.49  3573.8  432.28  3665.5  440.09    3716  428.02
  3751.1  417.16  3794.9  432.83    4129   431.7  4231.7   431.2  4302.9  430.44
  4351.3  430.82  4650.9  434.62  4710.2  433.76  4855.6  429.52  4933.4  430.61
  4944.6  430.87  4973.8   417.4  5025.8  414.88  5107.9  432.75    5150  431.33
  5542.3  433.87  5729.3  423.02  5832.2  432.14  6727.9  444.17    7827  444.59
  7929.5  446.93    8237  452.04  8317.9  453.23    8442  457.44  9450.3   467.3
#Mann= 18 ,-1 , 0
  1717.1     .05       0    3716     .16       0    4129     .05       0
  4231.7     .16       0  4302.9     .05       0  4351.3     .16       0
  4650.9     .05       0  4710.2     .16       0  4855.6     .05       0
  4933.4     .16       0  4944.6     .07       0  5107.9     .16       0
    5150     .05       0    7827     .08       0  7929.5     .05       0
    8237     .16       0  8317.9     .05       0    8442     .16       0
#XS Ineff= 2 ,-1
  2858.1  3659.3  440.18  3659.3  3794.9  432.83
Permanent Ineff=
       F       F
Bank Sta=4944.6,5107.9
XS Rating Curve= 0 ,0
Exp/Cntr=0.3,0.1

Type RM Length L Ch R = 1 ,858244  ,2424,2424,2424
BEGIN DESCRIPTION:
NAVASOTA RIVER 093
END DESCRIPTION:
XS GIS Cut Line= 3
       3470951.6     10576440.07      3468588.31     10577166.46
      3465313.05     10576363.31
#Sta/Elev= 30
  2733.8  466.41  2764.7  464.11    2796  465.03  3198.7  464.17  3653.9  455.98
    3949  455.27    4274  455.46  4469.9   453.9  4624.9  448.45  4741.9  442.16
  4766.2  438.55  4804.7  427.68  4929.8  427.74  4972.7  414.97  5038.4  416.33
  5071.1  425.03  5103.8  423.85    5130  426.42  5174.4  433.58  5372.8  440.14
  5768.6  437.09  5943.6  438.22  6090.1  432.91  6209.7     434  6251.2  432.15
    6304   435.8  6983.5   442.3  7644.2  459.19  7763.8  458.55  8578.5  470.79
#Mann= 7 ,-1 , 0
  2733.8     .08       0    2796     .16       0    3949     .05       0
    4274     .16       0  4929.8     .07       0  5071.1     .16       0
    5130     .05       0
Bank Sta=4929.8,5071.1
XS Rating Curve= 0 ,0
Exp/Cntr=0.3,0.1

Type RM Length L Ch R = 1 ,855820  ,2309,2309,2309
BEGIN DESCRIPTION:
NAVASOTA RIVER 097
END DESCRIPTION:
XS GIS Cut Line= 3
      3470344.43     10576155.19      3467333.98      10575225.3
      3466306.24     10575269.72
#Sta/Elev= 30
  1849.2  462.22  2140.2   457.1  2392.8  453.65  2622.2  451.68    2758   447.4
    2822  448.47  3165.4   450.2  3339.1  445.35  3366.5  446.12  3507.5  439.99
  3746.5  435.75  4468.2  435.74  4571.7  432.87  4635.6  427.28  4767.1  422.67
  4789.8  421.54  4803.1  424.21  4891.8  427.32  4918.2  428.56  4939.2  426.22
  4949.6   418.5  4963.2  414.17  5021.9  415.25    5034  417.69  5051.9  430.69
  5071.9  445.29    5102  448.73  5129.6  448.98  5282.1  453.57  6028.7  462.68
#Mann= 10 ,-1 , 0
  1849.2     .16       0  2140.2     .05       0  2392.8     .16       0
    2822     .05       0  4571.7     .16       0  4767.1     .05       0
  4891.8     .16       0  4918.2     .07       0  5051.9     .16       0
  5129.6     .05       0
Bank Sta=4918.2,5051.9
XS Rating Curve= 0 ,0
Exp/Cntr=0.3,0.1

Type RM Length L Ch R = 1 ,853511  ,2097,2097,2097
BEGIN DESCRIPTION:
NAVASOTA RIVER 096
END DESCRIPTION:
XS GIS Cut Line= 3
      3470393.72     10576027.98      3467766.27     10573152.38
      3466040.88     10572688.72
#Sta/Elev= 30
  1104.8   463.3  1350.6   457.5    1623  452.62  1831.9  448.38  2023.3  440.18
  2087.5  442.11  2370.5  434.43  2617.8  433.44  2936.7  424.25  3920.3  427.66
  4040.6   425.4  4111.5  419.05  4205.2  424.12  4260.1  420.41  4309.1  423.86
    4579  427.35  4875.4  423.44  4939.7  424.89  4953.9  417.25  4974.6  414.33
  5045.7  415.48  5087.1  427.36  5605.1  426.95  5845.4  431.62  6178.8  442.68
  6408.3  457.29  6597.9  460.75  6619.7  457.31  6650.7  461.32  6786.6  464.96
#Mann= 10 ,-1 , 0
  1104.8     .16       0  1350.6     .05       0    1623     .16       0
  1831.9     .05       0  4205.2     .16       0  4309.1     .05       0
  4875.4     .16       0  4939.7     .07       0  5087.1     .16       0
  5845.4     .05       0
Bank Sta=4939.7,5087.1
XS Rating Curve= 0 ,0
Exp/Cntr=0.3,0.1

Type RM Length L Ch R = 1 ,851414  ,184,184,184
BEGIN DESCRIPTION:
NAVASOTA RIVER 094
END DESCRIPTION:
XS GIS Cut Line= 6
      3470518.47      10576009.2      3469675.58      10574591.2
      3469592.68     10573760.13      3469351.65     10572928.99
      3467892.01     10571604.77      3467144.13     10570272.35
#Sta/Elev= 30
  2515.2  465.33    2727  461.92  2815.9  458.76  3166.5  451.81  3283.3  449.43
  3793.9  434.96  4309.1  429.24  4326.4  429.76  4817.6  425.71  4938.2  420.11
  4948.2  416.73    5039  414.82  5069.9  422.53  5090.4  423.12  5304.9  422.22
  5427.7  422.51  5601.3  434.22  5876.2  440.71  6252.2  442.92  6649.5  438.65
  6899.1  441.72    6932  442.16  7564.9   441.7  8888.2  448.34    8897  448.39
  9105.3  449.49  9126.7   449.6  9322.5  451.75  9356.5   452.1  9381.6  452.39
#Mann= 18 ,-1 , 0
  2515.2     .05       0    2727     .16       0  2815.9     .05       0
  3166.5     .08       0  3283.3     .05       0  4309.1     .08       0
  4326.4     .05       0  4817.6     .04       0  5090.4     .16       0
  5304.9     .05       0  6899.1     .08       0    6932     .05       0
  8888.2     .08       0    8897     .05       0  9105.3     .08       0
  9126.7     .05       0  9322.5     .08       0  9356.5     .05       0
Bank Sta=4817.6,5090.4
XS Rating Curve= 0 ,0
Exp/Cntr=0.3,0.1

Type RM Length L Ch R = 1 ,851230  ,963,963,963
BEGIN DESCRIPTION:
NAVASOTA RIVER 095
END DESCRIPTION:
XS GIS Cut Line= 6
      3470573.79      10575880.7      3469840.99     10574536.78
      3469760.96     10573734.43      3469494.77     10572834.53
       3468020.4     10571492.62      3467217.91     10570220.97
#Sta/Elev= 30
  2739.3  465.34  2995.1  459.62  3680.3  443.86  4251.3  432.66    4637  430.85
  4938.5  421.95  4958.6  414.81  4998.5  413.99    5039  414.93  5059.1  423.95
  5436.5  421.64    5757  435.77  5921.6  441.49  6139.6   441.9  6377.5   440.4
  6712.4  431.33  6806.1  432.01  6883.9  437.13  7384.2  440.62  7514.8  441.63
  7650.6  441.58  7951.9  442.39  8585.3  445.48  8927.1  446.77  9144.3  447.99
  9329.2  448.76  9428.7  450.37  9450.7  447.42  9518.7  451.32  9531.8  451.57
#Mann= 19 ,-1 , 0
  2739.3     .05       0  2995.1     .05       0  3680.3     .05       0
  4251.3     .05       0  4938.5     .07       0  5059.1     .05       0
    5757     .05       0  6139.6     .08       0  6377.5     .05       0
  6712.4     .05       0  7384.2     .05       0  7514.8     .16       0
  7650.6     .05       0  7951.9     .05       0  8585.3     .05       0
  8927.1     .05       0  9144.3     .05       0  9329.2     .08       0
  9518.7     .05       0
Bank Sta=4938.5,5059.1
XS Rating Curve= 0 ,0
Exp/Cntr=0.3,0.1

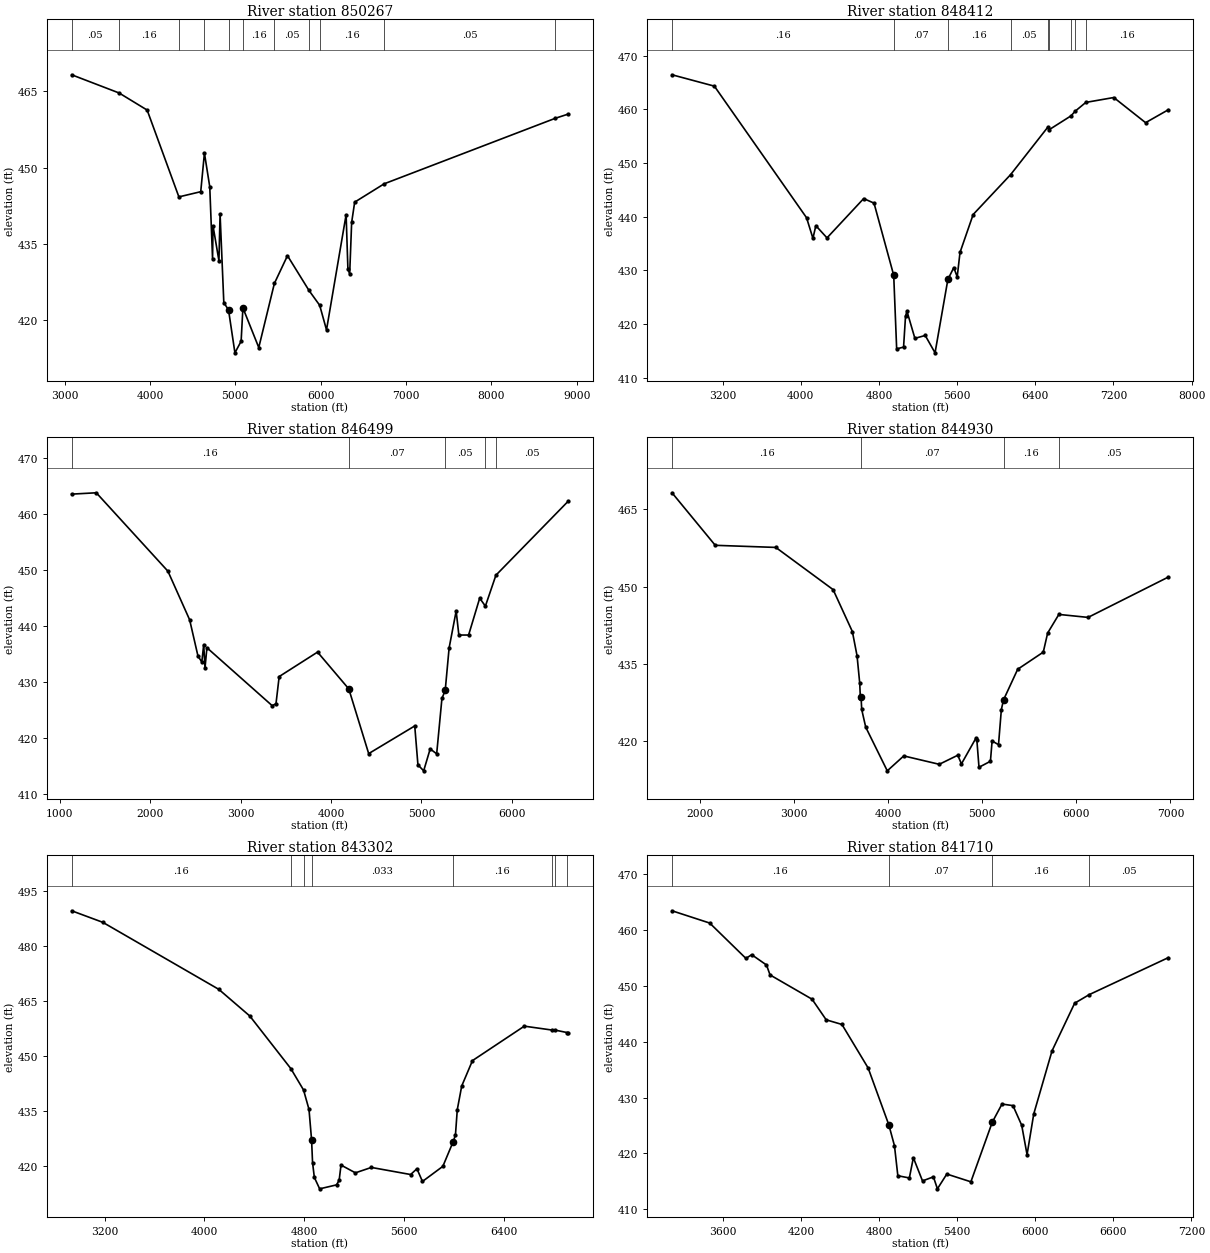
Type RM Length L Ch R = 1 ,850267  ,1855,1855,1855
BEGIN DESCRIPTION:
NAVASOTA RIVER 221
END DESCRIPTION:
XS GIS Cut Line= 3
      3472144.69     10573980.87      3470399.95     10573188.84
      3468084.01     10570055.03
#Sta/Elev= 30
  3083.9  468.23  3638.9  464.66  3967.9   461.3  4339.5  444.26  4595.4  445.28
  4638.7  452.85  4701.1  446.25  4733.9  432.11  4739.4  438.57  4808.6  431.73
  4821.9   440.9  4865.8  423.49  4920.8  422.09  4995.8  413.65  5068.5  415.93
  5089.3  422.48  5275.1  414.69    5458  427.28  5611.3  432.72    5863   425.9
  5988.6  422.98  6068.4  418.15  6298.1  440.77    6319  430.13  6339.8  429.12
  6362.9  439.25  6398.3  443.23    6744  446.83  8749.5   459.7  8896.7   460.5
#Mann= 11 ,-1 , 0
  3083.9     .05       0  3638.9     .16       0  4339.5     .05       0
  4638.7     .16       0  4920.8     .07       0  5089.3     .16       0
    5458     .05       0    5863     .12       0  5988.6     .16       0
    6744     .05       0  8749.5     .16       0
Bank Sta=4920.8,5089.3
XS Rating Curve= 0 ,0
Exp/Cntr=0.3,0.1

Type RM Length L Ch R = 1 ,848412  ,1913,1913,1913
BEGIN DESCRIPTION:
NAVASOTA RIVER 222
END DESCRIPTION:
XS GIS Cut Line= 4
      3472365.84     10572468.86      3470681.81     10571340.38
      3469839.79     10571444.55      3468182.09     10569993.16
#Sta/Elev= 30
  2682.4  466.47  3115.9  464.35  4059.2  439.82  4124.4  435.98  4154.4  438.34
  4268.5  436.06  4643.7  443.39  4749.6  442.54  4951.1  429.09  4981.3  415.37
  5051.9   415.7    5072  421.45  5086.7  422.39  5167.8  417.33  5273.5  417.87
  5374.1  414.63  5505.3  428.31  5565.8  430.52  5600.9   428.8  5629.4  433.34
  5764.1  440.42    6148  447.87  6525.7  456.65  6542.6  456.24  6766.1  458.82
  6806.6  459.66    6917  461.32    7203  462.23  7528.5  457.54  7761.3  459.95
#Mann= 9 ,-1 , 0
  2682.4     .16       0  4951.1     .07       0  5505.3     .16       0
    6148     .05       0  6525.7     .08       0  6542.6     .05       0
  6766.1     .16       0  6806.6     .05       0    6917     .16       0
Bank Sta=4951.1,5505.3
XS Rating Curve= 0 ,0
Exp/Cntr=0.3,0.1

Type RM Length L Ch R = 1 ,846499  ,1569,1569,1569
BEGIN DESCRIPTION:
NAVASOTA RIVER 225
END DESCRIPTION:
XS GIS Cut Line= 3
       3472454.6     10572394.28      3469759.32     10569619.39
      3468419.88     10568706.77
#Sta/Elev= 30
  1131.6  463.49  1403.9  463.73  2195.9  449.76  2436.4  441.09  2528.5  434.63
  2570.9  433.58    2592  436.67  2606.2  432.49  2627.3  436.12  3348.8   425.8
  3391.2  426.13  3426.5  430.98  3850.9  435.34 4196.45  428.78  4416.5  417.25
  4925.8  422.18  4961.1  415.25  5024.5  414.18  5096.6  418.09  5168.4  417.21
  5226.5  427.08  5262.8  428.51    5306  436.08  5383.9  442.66  5413.7  438.38
  5521.5  438.38  5644.1  444.95  5707.1  443.53  5823.6  449.04  6620.8  462.19
#Mann= 5 ,-1 , 0
  1131.6     .16       0 4196.45     .07       0  5262.8     .05       0
  5707.1     .08       0  5823.6     .05       0
Bank Sta=4196.45,5262.8
XS Rating Curve= 0 ,0
Exp/Cntr=0.3,0.1

Type RM Length L Ch R = 1 ,844930  ,1628,1628,1628
BEGIN DESCRIPTION:
NAVASOTA RIVER 226
END DESCRIPTION:
XS GIS Cut Line= 4
      3472918.97     10571894.23      3471547.47     10570399.03
      3470714.14     10568528.38      3469801.74     10567749.27
#Sta/Elev= 30
  1701.4  468.22  2161.1  458.01  2804.9   457.6  3414.1   449.4  3618.8  441.25
  3668.7  436.54  3697.1  431.21  3703.9  428.31  3711.3  428.54  3718.1  426.11
  3760.8  422.67    3990  414.18  4165.4  417.08  4542.6  415.45  4739.5  417.21
  4778.4  415.53  4930.8  420.48  4942.6  420.12    4965  414.87  5086.6  416.04
  5104.4  419.99  5172.5  419.26  5202.8   426.1    5226  427.98  5376.4  433.92
  5648.4  437.25  5694.9  440.96  5814.3  444.58  6124.5     444    6978  451.84
#Mann= 4 ,-1 , 0
  1701.4     .16       0  3711.3     .07       0    5226     .16       0
  5814.3     .05       0
Bank Sta=3711.3,5226
XS Rating Curve= 0 ,0
Exp/Cntr=0.3,0.1

Type RM Length L Ch R = 1 ,843302  ,1592,1592,1592
BEGIN DESCRIPTION:
NAVASOTA RIVER 224
END DESCRIPTION:
XS GIS Cut Line= 3
      3473758.23     10571477.43      3472432.93      10569893.7
      3471324.69     10568330.25
#Sta/Elev= 30
  2934.9  489.62  3184.8  486.47  4115.2  468.21  4363.7  460.95  4693.1  446.61
  4794.9  440.79  4838.7   435.5  4859.5  427.14  4867.3  420.97  4881.6  416.96
  4924.2  413.85  5059.8  414.93  5080.7  416.22  5095.5  420.33  5210.9  418.21
  5339.1  419.68  5654.1  417.75  5704.5  419.32  5748.9  415.86  5912.5  419.98
  5992.5  426.48  6013.4  428.46  6028.2  435.42  6063.8  441.87    6150  448.79
  6565.9  458.18  6787.7  457.12  6815.3  457.09  6911.5  456.42  6916.4  456.36
#Mann= 8 ,-1 , 0
  2934.9     .16       0  4693.1     .05       0  4794.9     .12       0
  4859.5    .033       0  5992.5     .16       0  6787.7     .05       0
  6815.3     .16       0  6911.5     .05       0
Bank Sta=4859.5,5992.5
XS Rating Curve= 0 ,0
Exp/Cntr=0.3,0.1

Type RM Length L Ch R = 1 ,841710  ,930,930,930
BEGIN DESCRIPTION:
NAVASOTA RIVER 223
END DESCRIPTION:
XS GIS Cut Line= 4
      3474060.74      10570118.8      3473904.49     10568920.88
      3473354.02     10568728.43      3471385.84     10568260.25
#Sta/Elev= 30
  3208.8  463.49  3498.4  461.29  3776.9  454.95  3821.1  455.62  3934.9  453.77
  3962.3  451.99    4285  447.64  4393.8  443.94  4514.7  443.11    4716  435.31
  4874.9  425.12  4918.5  421.36  4944.3  415.99  5032.8  415.59  5063.6  419.22
  5133.9  415.06  5217.8  415.79  5248.4  413.64  5320.6  416.29  5505.6   414.9
  5670.1  425.59  5744.8  428.84  5829.1  428.56  5896.2  425.04  5937.4  419.77
  5988.8  427.07  6129.4  438.38  6303.2  446.92  6415.4  448.46  7023.1  455.09
#Mann= 4 ,-1 , 0
  3208.8     .16       0  4874.9     .07       0  5670.1     .16       0
  6415.4     .05       0
Bank Sta=4874.9,5670.1
XS Rating Curve= 0 ,0
Exp/Cntr=0.3,0.1

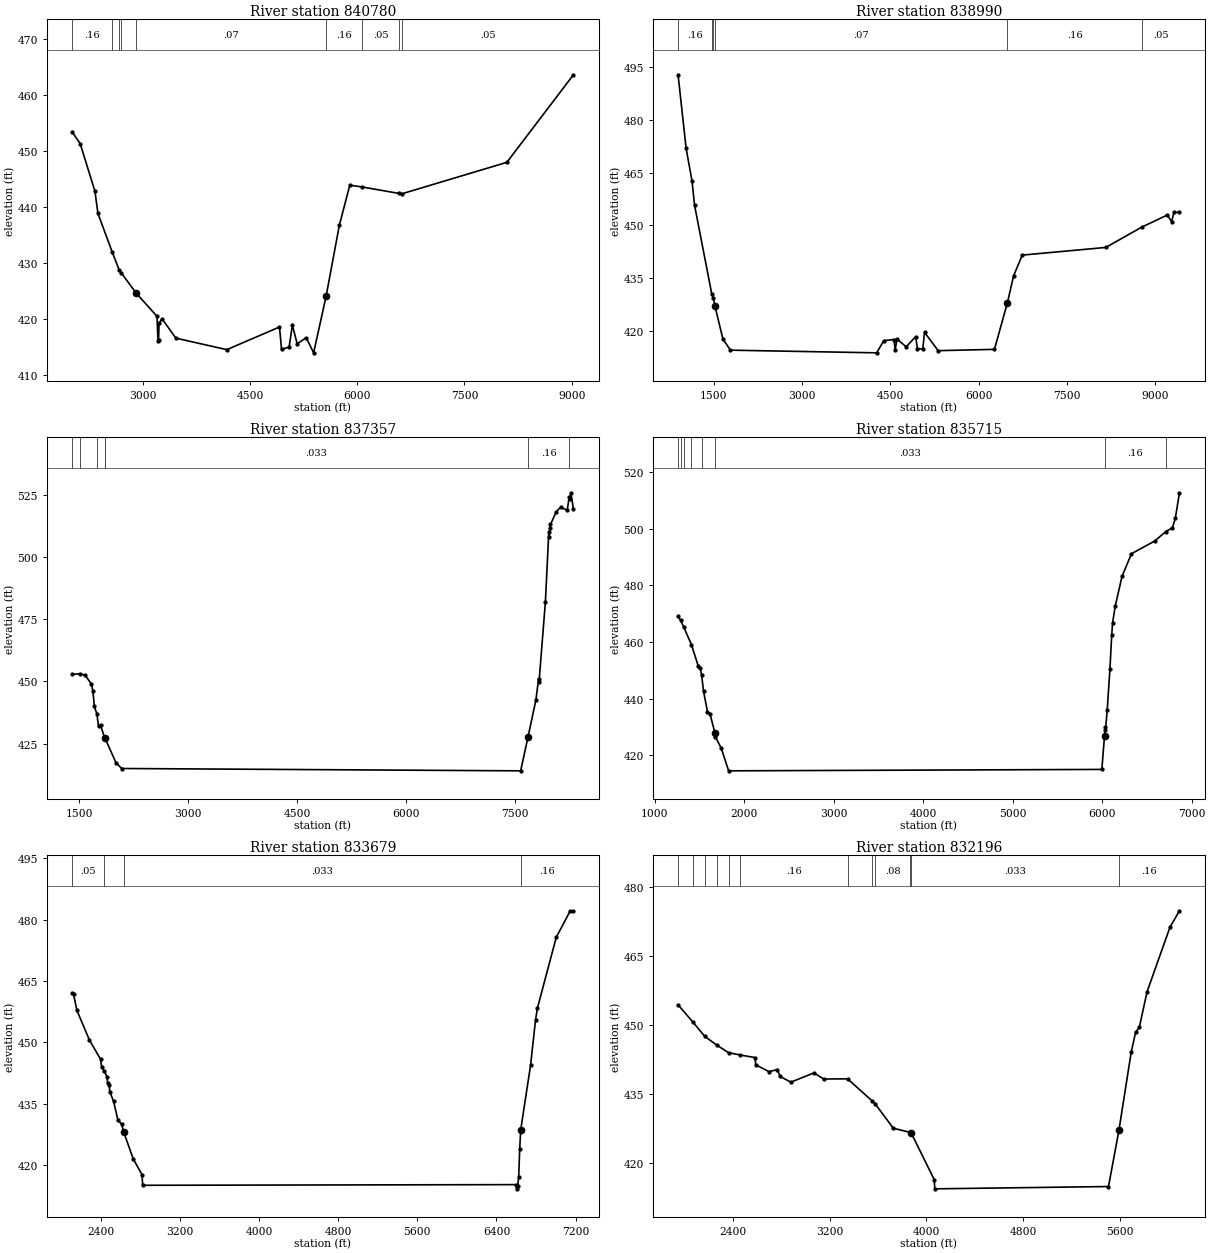
Type RM Length L Ch R = 1 ,840780  ,1790,1790,1790
BEGIN DESCRIPTION:
NAVASOTA RIVER 219
END DESCRIPTION:
XS GIS Cut Line= 3
      3475508.13     10570004.85       3473854.5     10567908.51
        3469676.     10566723.95
#Sta/Elev= 30
  2011.1  453.47  2124.6  451.36  2331.5  442.84  2373.1  438.89  2570.3  432.09
  2672.1  428.74  2699.3   428.3    2907  424.68  3199.7  420.52  3213.2  416.04
  3221.3  416.23  3227.6  419.33    3271  420.07  3463.4  416.63  4175.2  414.58
  4912.7  418.62  4941.5  414.63  5047.4  415.04  5092.8  418.94  5160.6  415.62
  5286.5  416.72  5390.2  414.01  5564.9  424.12  5750.1  436.78  5896.2  443.94
  6061.2  443.63  6590.6  442.45  6620.1  442.38  8092.8  448.01  9024.3  463.64
#Mann= 9 ,-1 , 0
  2011.1     .16       0  2570.3     .08       0  2672.1     .05       0
  2699.3     .16       0    2907     .07       0  5564.9     .16       0
  6061.2     .05       0  6590.6     .16       0  6620.1     .05       0
Bank Sta=2907,5564.9
XS Rating Curve= 0 ,0
Exp/Cntr=0.3,0.1

Type RM Length L Ch R = 1 ,838990  ,1633,1633,1633
BEGIN DESCRIPTION:
NAVASOTA RIVER 220
END DESCRIPTION:
XS GIS Cut Line= 3
       3476234.7     10569319.97      3474088.87     10566257.47
      3469338.91     10565694.98
#Sta/Elev= 30
   890.7   492.8  1027.5  471.88  1128.6  462.51  1170.5  455.73  1464.9  430.32
  1491.5   429.4  1515.7  427.14  1652.5  417.67  1780.7  414.47  4265.8  413.71
  4388.1  417.18  4560.7   417.5  4581.6   414.6  4611.3  417.62  4767.9  415.44
    4929   418.3  4959.2  414.94  5049.8  414.79    5080  419.54  5311.6  414.33
  6268.3   414.7  6489.8  428.02  6594.3  435.63  6741.6  441.51  8161.4  443.69
  8772.7  449.47  9208.7  452.92  9279.2  451.01  9319.5  453.64  9413.3  453.72
#Mann= 6 ,-1 , 0
   890.7     .16       0  1464.9     .05       0  1491.5     .16       0
  1515.7     .07       0  6489.8     .16       0  8772.7     .05       0
Bank Sta=1515.7,6489.8
XS Rating Curve= 0 ,0
Exp/Cntr=0.3,0.1

Type RM Length L Ch R = 1 ,837357  ,1642,1642,1642
BEGIN DESCRIPTION:
NAVASOTA RIVER 070
END DESCRIPTION:
XS GIS Cut Line= 3
      3477026.38     10567632.48      3474401.37     10564632.47
      3474193.07     10561716.22
#Sta/Elev= 30
  1399.8  452.88  1506.5  453.08  1580.6  452.49    1666  448.96  1686.9  446.13
  1707.8  439.95  1742.1  436.91  1764.7  432.05  1793.2  432.34  1847.6  427.42
  1850.2  427.41  2005.8  417.31  2083.6     415  7582.3  414.06  7682.8  427.56
  7793.1  442.62  7830.1  451.17  7835.1  449.58  7923.4     482  7970.5  510.09
  7975.5  507.96  7983.5  511.54  7993.6  513.11  8073.8  518.28  8133.9  520.01
  8224.2  518.81  8251.2  524.09  8256.2  523.17  8274.3  525.84  8309.8  519.35
#Mann= 7 ,-1 , 0
  1399.8     .05       0  1506.5     .16       0  1742.1     .05       0
  1847.6     .16       0  1850.2    .033       0  7682.8     .16       0
  8251.2     .05       0
Bank Sta=1850.2,7682.8
XS Rating Curve= 0 ,0
Exp/Cntr=0.3,0.1

Type RM Length L Ch R = 1 ,835715  ,2036,2036,2036
BEGIN DESCRIPTION:
NAVASOTA RIVER 218
END DESCRIPTION:
XS GIS Cut Line= 3
      3477172.18     10567444.93      3475838.87     10564924.14
       3475693.1     10562175.38
#Sta/Elev= 30
  1259.6  468.99  1287.5  467.63  1323.5  465.22  1409.5  459.01  1484.1  451.59
  1506.1  450.83  1522.8   448.4  1544.5  442.54  1588.5  435.36  1616.2  434.61
  1670.6  428.02  1676.5  426.56  1742.5  422.46  1824.7   414.5  5996.4     415
  6026.5  426.96  6032.2  429.86  6037.2  428.83  6056.5  436.05  6086.6  450.28
  6106.6  462.41  6116.6  466.72  6146.6  472.74  6221.8   483.1  6326.9  491.11
  6587.3  495.61  6708.4  498.87  6785.4  500.31  6817.6  503.61  6863.9  512.64
#Mann= 8 ,-1 , 0
  1259.6     .05       0  1287.5     .16       0  1323.5     .05       0
  1409.5     .16       0  1522.8     .05       0  1670.6    .033       0
  6026.5     .16       0  6708.4     .05       0
Bank Sta=1670.6,6026.5
XS Rating Curve= 0 ,0
Exp/Cntr=0.3,0.1

Type RM Length L Ch R = 1 ,833679  ,1483,1483,1483
BEGIN DESCRIPTION:
NAVASOTA RIVER 071
END DESCRIPTION:
XS GIS Cut Line= 4
      3478487.82     10566944.69      3477105.93     10564404.33
      3476901.37      10564028.3       3476922.2     10562278.29
#Sta/Elev= 30
  2108.1  462.01    2123  461.79  2157.1  457.81  2282.5   450.6  2396.2  445.85
  2407.9  443.87  2433.9  442.93  2462.1  441.53  2467.8  439.94  2483.9  439.48
  2489.6  437.89  2527.6   435.6  2571.3  431.02  2609.3   429.9  2631.2     428
  2726.3  421.48  2816.4  417.56  2822.1     415  6594.8  415.16  6604.6  414.13
  6614.8  414.87  6624.8  417.14  6634.8   423.8  6644.8  428.54  6744.8  444.38
  6794.8  455.45  6814.8  458.43  7004.8  475.69  7144.8   482.1  7178.2  482.17
#Mann= 4 ,-1 , 0
  2108.1     .05       0  2433.9     .16       0  2631.2    .033       0
  6644.8     .16       0
Bank Sta=2631.2,6644.8
XS Rating Curve= 0 ,0
Exp/Cntr=0.3,0.1

Type RM Length L Ch R = 1 ,832196  ,751,751,751
BEGIN DESCRIPTION:
NAVASOTA RIVER 217
END DESCRIPTION:
XS GIS Cut Line= 4
      3478560.07     10566488.23      3478706.59     10565102.95
      3478272.39     10563501.79      3477706.43     10562570.71
#Sta/Elev= 30
    1948   454.4  2070.6  450.66  2168.8  447.55  2267.1  445.68  2365.3  444.02
  2463.5  443.51  2584.2  442.96  2589.3   441.4  2698.8  439.91  2769.1  440.37
  2789.3  438.89  2879.8  437.63  3070.8  439.64    3151  438.31  3347.9  438.36
  3553.3  433.52  3575.7  432.94    3726  427.64  3861.6  426.76    3875  426.55
  4063.7  416.52  4068.7   414.5  5503.4     415  5589.4  427.15  5690.6  444.07
    5727  448.42    5758  449.53    5822  457.23  6011.9  471.27  6089.6  474.79
#Mann= 12 ,-1 , 0
    1948     .05       0  2070.6     .08       0  2168.8     .05       0
  2267.1     .08       0  2365.3     .05       0  2463.5     .16       0
  3347.9     .05       0  3553.3     .16       0  3575.7     .08       0
  3861.6     .05       0    3875    .033       0  5589.4     .16       0
Bank Sta=3875,5589.4
XS Rating Curve= 0 ,0
Exp/Cntr=0.3,0.1

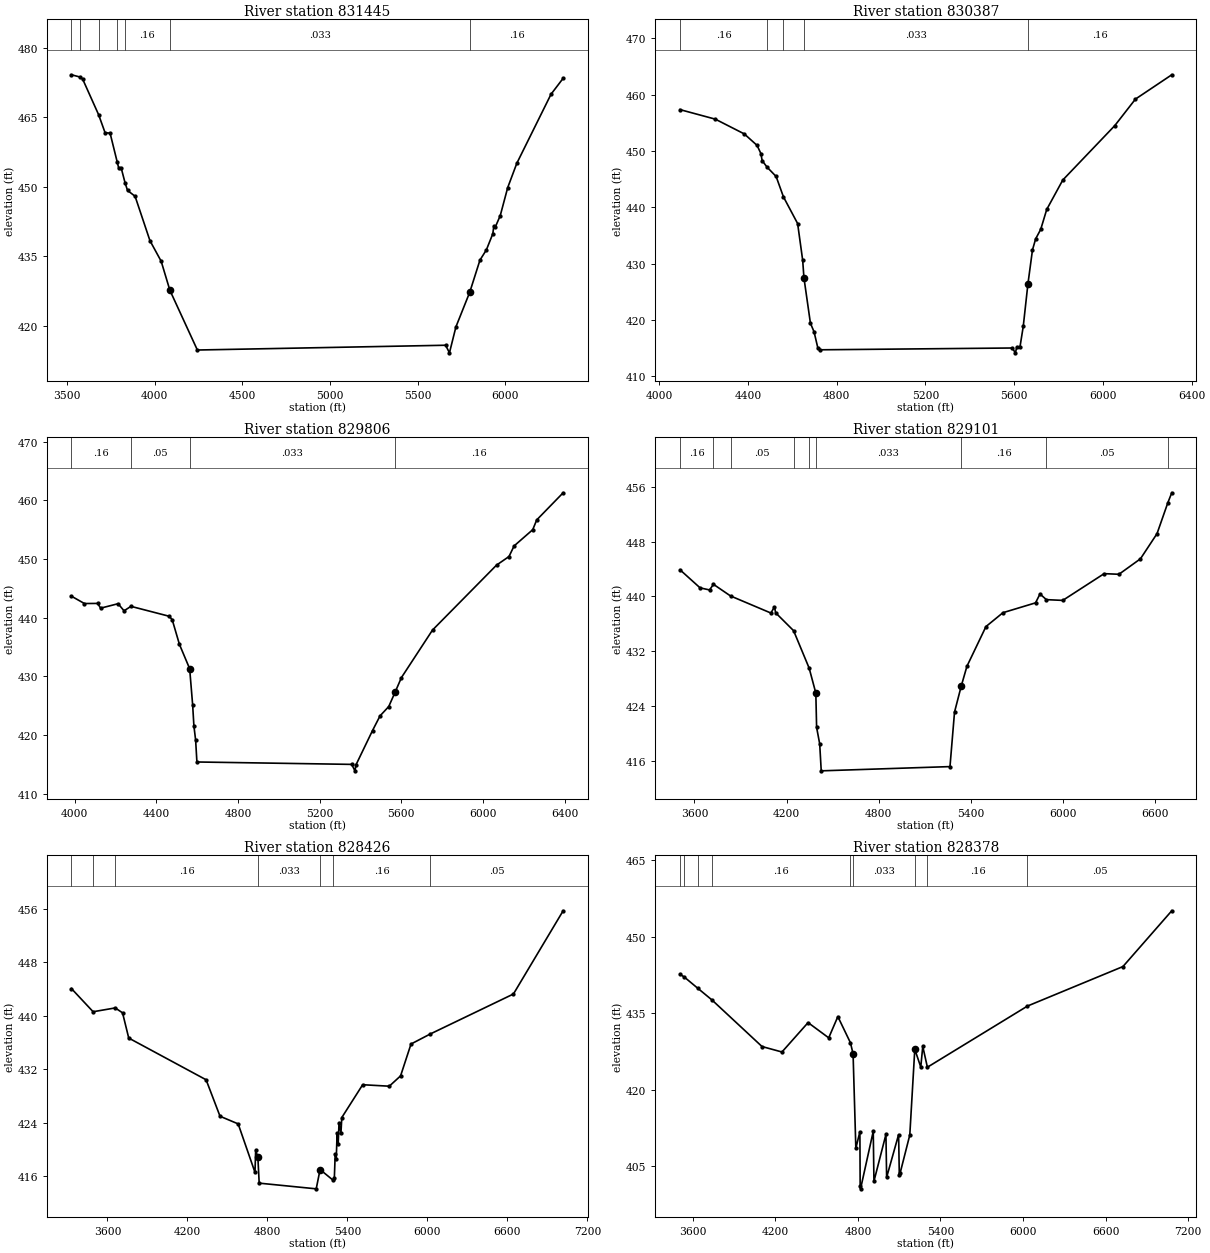
Type RM Length L Ch R = 1 ,831445  ,1058,1058,1058
BEGIN DESCRIPTION:
NAVASOTA RIVER 216
END DESCRIPTION:
XS GIS Cut Line= 3
      3479855.47     10564358.21      3478932.11     10563207.21
      3477802.15      10562507.8
#Sta/Elev= 30
  3524.4  474.15  3571.9  473.68  3588.1  473.24  3679.3  465.54  3716.1  461.66
  3744.9  461.54  3785.3  455.34  3794.5  453.94  3808.9  453.93  3829.9  450.88
  3844.2  449.19  3887.4  447.92  3972.2  438.34  4036.2   433.9  4085.8  427.64
  4242.6  414.74  5658.6  415.77  5680.4  414.13  5717.3  419.73  5796.5  427.25
  5854.4  434.15    5891  436.35  5927.7  439.83  5933.5   441.5  5940.9  441.19
  5970.2  443.76  6012.7   449.8  6064.7  455.05  6259.7  469.95  6328.9  473.39
#Mann= 7 ,-1 , 0
  3524.4     .05       0  3571.9     .16       0  3679.3     .08       0
  3785.3     .12       0  3829.9     .16       0  4085.8    .033       0
  5796.5     .16       0
Bank Sta=4085.8,5796.5
XS Rating Curve= 0 ,0
Exp/Cntr=0.3,0.1

Type RM Length L Ch R = 1 ,830387  ,581,581,581
BEGIN DESCRIPTION:
NAVASOTA RIVER 215
END DESCRIPTION:
XS GIS Cut Line= 3
      3480332.93     10563743.67      3479949.14     10562923.74
      3478917.29      10562116.5
#Sta/Elev= 30
  4094.7  457.33  4253.5  455.64    4384  453.02  4441.7  450.98    4459  449.52
  4464.5  448.28  4486.4  447.13  4527.5  445.46  4560.6  441.83  4624.4   437.1
  4647.2  430.57  4652.8  427.48  4682.1  419.39  4698.4  417.88  4715.2  415.05
  4726.8  414.68  5591.2     415  5605.4  414.14    5612  415.17  5626.5  415.26
  5640.9  418.82  5661.8  426.32  5682.6  432.43    5697   434.4  5719.6  436.06
  5746.8  439.61  5819.1  444.83  6053.3  454.49  6146.4   459.2  6310.1  463.52
#Mann= 5 ,-1 , 0
  4094.7     .16       0  4486.4     .05       0  4560.6     .16       0
  4652.8    .033       0  5661.8     .16       0
Bank Sta=4652.8,5661.8
XS Rating Curve= 0 ,0
Exp/Cntr=0.3,0.1

Type RM Length L Ch R = 1 ,829806  ,705,705,705
BEGIN DESCRIPTION:
NAVASOTA RIVER 214
END DESCRIPTION:
XS GIS Cut Line= 3
      3480862.41     10563251.22      3480257.27     10562435.59
       3478950.6     10561953.98
#Sta/Elev= 30
  3984.4  443.67    4048  442.42  4112.7  442.44  4127.3  441.63  4212.9  442.39
  4242.1  441.18  4275.8  441.94  4463.2  440.25  4477.9  439.67  4513.3  435.46
  4563.4  431.31    4578  425.15  4584.2  421.55  4592.6  419.15  4598.9  415.41
  5357.2     415  5372.8   413.9  5378.5  414.96    5459  420.77  5495.8  423.27
  5538.4  424.86  5570.1  427.35  5600.6   429.8  5752.8   437.9  6066.4  448.97
  6127.3  450.43  6152.4  452.24  6243.7  455.01  6263.1  456.67  6392.6   461.3
#Mann= 4 ,-1 , 0
  3984.4     .16       0  4275.8     .05       0  4563.4    .033       0
  5570.1     .16       0
Bank Sta=4563.4,5570.1
XS Rating Curve= 0 ,0
Exp/Cntr=0.3,0.1

Type RM Length L Ch R = 1 ,829101  ,675,675,675
BEGIN DESCRIPTION:
NAVASOTA RIVER 213
END DESCRIPTION:
XS GIS Cut Line= 3
      3480872.17     10563249.06      3480542.89      10561791.8
      3479698.54     10560305.03
#Sta/Elev= 30
    3506   443.9  3636.6  441.26  3698.1  440.96  3723.7  441.78  3834.7  440.08
    4098  437.58  4121.2   438.5  4128.7  437.62  4245.7     435  4347.2  429.52
  4390.6  425.87  4395.7  420.85  4415.8  418.45  4425.8   414.5  5264.7  415.12
  5294.3  423.09  5337.6  426.86  5375.1  429.79  5499.1   435.6  5609.7  437.63
  5822.1  439.07  5851.2  440.37  5892.6  439.54  5999.5  439.43  6269.1  443.34
  6365.7  443.25  6505.6  445.51  6613.7  449.19  6684.6  453.74  6709.8  455.17
#Mann= 9 ,-1 , 0
    3506     .16       0  3723.7     .08       0  3834.7     .05       0
  4245.7     .07       0  4347.2     .05       0  4390.6    .033       0
  5337.6     .16       0  5892.6     .05       0  6684.6     .16       0
Bank Sta=4390.6,5337.6
XS Rating Curve= 0 ,0
Exp/Cntr=0.3,0.1

Type RM Length L Ch R = 1 ,828426  ,48,48,48
BEGIN DESCRIPTION:
NAVASOTA RIVER 072
END DESCRIPTION:
XS GIS Cut Line= 5
      3480884.14     10563248.44      3481129.01     10562268.68
      3481179.08     10561610.68      3481189.78     10561470.07
      3479736.47     10560282.22
#Sta/Elev= 30
  3330.2  444.06  3492.8   440.6  3658.4  441.17  3713.5  440.44  3759.9  436.67
  4340.1  430.44  4444.6  424.99  4580.7  423.85  4706.8  416.61  4711.8  419.88
  4728.3  418.91  4738.3     415    5166  414.15    5195  417.03  5290.6  415.47
  5301.9  415.73  5308.4  419.33  5316.3  418.63  5322.8  422.48  5330.7  420.82
  5337.1  424.04  5351.5  422.48  5357.9   424.8  5514.4   429.7    5714  429.48
  5798.7  431.02    5877  435.78  6021.7  437.28  6645.1  443.25    7018  455.68
#Mann= 7 ,-1 , 0
  3330.2     .16       0  3492.8     .08       0  3658.4     .16       0
  4728.3    .033       0    5195     .05       0  5290.6     .16       0
  6021.7     .05       0
Bank Sta=4728.3,5195
XS Rating Curve= 0 ,0
Exp/Cntr=0.3,0.1

Type RM Length L Ch R = 1 ,828378  ,102,102,102
BEGIN DESCRIPTION:
NAVASOTA RIVER 098
END DESCRIPTION:
XS GIS Cut Line= 5
      3481417.85     10563074.86      3481187.47     10561971.21
      3481226.47     10561607.43      3481247.15     10561414.57
      3479751.61     10560263.32
#Sta/Elev= 30
  3506.7  442.61  3536.3  442.11  3637.3  439.84  3738.4  437.59  4102.6  428.44
  4247.5  427.37  4437.3  433.14  4587.4  430.15  4653.8  434.32  4745.7  429.16
  4764.5  426.99  4784.6  408.47    4814  411.71    4816  401.01  4818.8  400.51
  4911.2  411.81  4916.2     402  5003.4  411.19  5008.4  402.76  5095.5  411.16
  5100.6  403.19  5106.4  403.59  5176.8  411.08  5213.1  427.91  5256.6  424.41
  5271.1  428.47  5304.7  424.38  6032.4  436.39  6726.3  444.14  7081.3  455.09
#Mann= 9 ,-1 , 0
  3506.7     .05       0  3536.3     .08       0  3637.3     .05       0
  3738.4     .16       0  4745.7     .07       0  4764.5    .033       0
  5213.1     .05       0  5304.7     .16       0  6032.4     .05       0
Bank Sta=4764.5,5213.1
XS Rating Curve= 0 ,0
Exp/Cntr=0.3,0.1

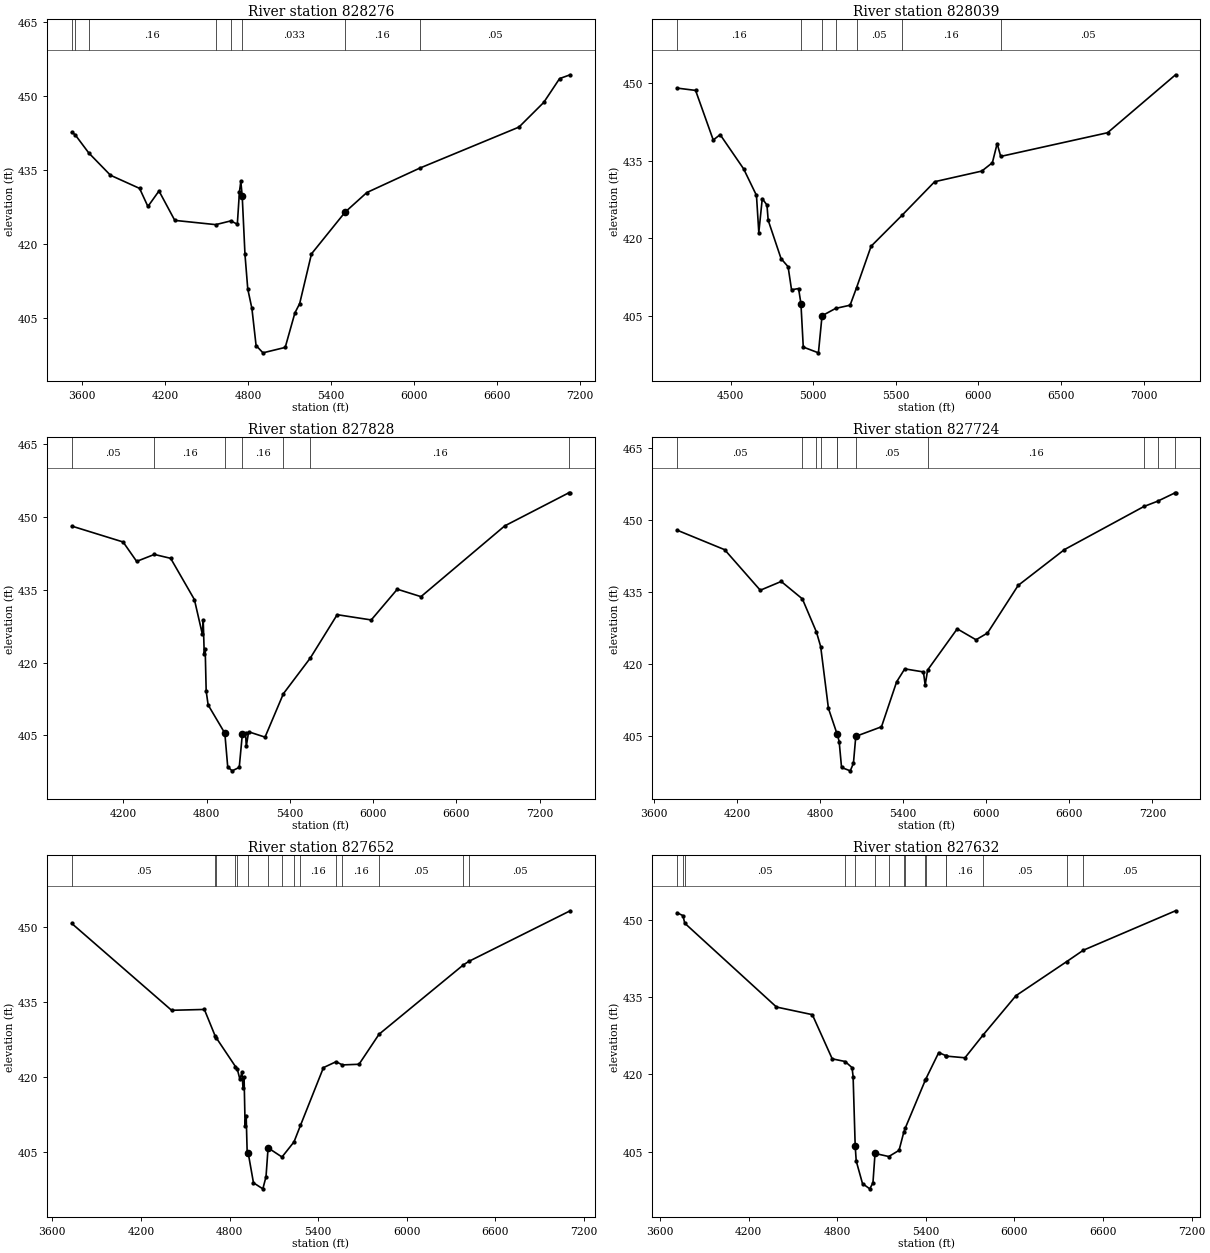
Type RM Length L Ch R = 1 ,828276  ,237,237,237
BEGIN DESCRIPTION:
NAVASOTA RIVER 099
END DESCRIPTION:
XS GIS Cut Line= 4
      3481426.32      10563070.6      3481328.76     10561600.44
       3481315.1     10561398.49      3479775.89     10560240.62
#Sta/Elev= 30
  3526.6  442.61  3550.8  442.12  3649.4  438.43  3806.2  433.92  4016.6  431.26
  4076.8   427.6  4156.9  430.74    4271  424.79    4567  423.93  4676.4  424.69
    4723  424.01  4738.2  430.55  4748.2  432.67  4758.3  429.73  4778.3  417.89
  4798.4  410.92  4828.4  406.97  4858.5  399.48  4908.3     398    5069   399.1
  5139.1  406.08  5173.5  407.96  5258.9  418.02  5502.6  426.48  5658.8  430.42
  6039.8  435.34  6758.3  443.66  6937.4  448.65  7051.9  453.47  7128.5  454.24
#Mann= 8 ,-1 , 0
  3526.6     .05       0  3550.8     .08       0  3649.4     .16       0
    4567     .05       0  4676.4     .16       0  4758.3    .033       0
  5502.6     .16       0  6039.8     .05       0
Bank Sta=4758.3,5502.6
XS Rating Curve= 0 ,0
Exp/Cntr=0.3,0.1

Type RM Length L Ch R = 1 ,828039  ,211,211,211
BEGIN DESCRIPTION:
NAVASOTA RIVER 305
END DESCRIPTION:
XS GIS Cut Line= 4
      3482107.71     10562164.36      3481557.14     10561551.29
      3481391.55     10561366.17      3479866.57     10560159.68
#Sta/Elev= 30
    4176  449.08  4287.8  448.63  4394.7  439.02  4436.5  440.06  4578.6  433.43
  4656.3  428.29  4670.5  421.09  4691.4  427.66  4719.8  426.42  4727.3  423.46
  4805.1  416.04  4847.7  414.47  4868.6     410  4911.2  410.24  4925.4  407.34
  4939.6   398.9  5031.3  397.78  5053.2  404.96  5135.4  406.39    5223  407.01
  5262.2  410.41  5350.2  418.44  5536.3   424.4  5734.9  430.94  6020.2     433
  6084.3  434.62  6113.2  438.33  6134.7  435.84  6781.5  440.43  7192.9  451.66
#Mann= 7 ,-1 , 0
    4176     .16       0  4925.4     .07       0  5053.2     .07       0
  5135.4     .16       0  5262.2     .05       0  5536.3     .16       0
  6134.7     .05       0
Bank Sta=4925.4,5053.2
XS Rating Curve= 0 ,0
Exp/Cntr=0.3,0.1

Type RM Length L Ch R = 1 ,827828  ,104,104,104
BEGIN DESCRIPTION:
NAVASOTA RIVER 304
END DESCRIPTION:
XS GIS Cut Line= 6
      3482374.17     10562375.18      3482325.01     10562185.09
      3482051.22     10561717.91       3481778.3     10561455.64
      3481016.41      10561000.5      3480327.04     10559577.85
#Sta/Elev= 30
    3828  448.06  4197.9  444.79  4295.5   440.8  4422.9  442.23  4540.5  441.43
  4711.6  432.95  4768.2  425.92  4775.2  428.72  4782.4  421.79  4789.3  422.78
  4796.5   414.1  4810.7  411.27  4930.8  405.47  4951.7  398.54  4983.7  397.73
  5034.7  398.44  5057.3  405.35  5079.9   405.5  5085.4  402.79  5102.5  405.76
  5220.5  404.66  5352.8  413.59    5547  420.94  5740.4  429.84  5985.8  428.76
  6173.6  435.08  6344.2  433.55  6947.7   448.1    7410  454.91  7419.4  454.81
#Mann= 7 ,-1 , 0
    3828     .05       0  4422.9     .16       0  4930.8     .07       0
  5057.3     .16       0  5352.8     .05       0    5547     .16       0
    7410     .05       0
Bank Sta=4930.8,5057.3
XS Rating Curve= 0 ,0
Exp/Cntr=0.3,0.1

Type RM Length L Ch R = 1 ,827724  ,72,72,72
BEGIN DESCRIPTION:
NAVASOTA RIVER 303
END DESCRIPTION:
XS GIS Cut Line= 6
      3482470.97     10562350.08       3482418.9     10562148.72
      3482128.97     10561653.93      3481836.14     10561372.54
      3481093.94     10560936.72      3480374.69     10559568.96
#Sta/Elev= 30
    3768  447.94  4111.2  443.87  4368.5  435.41  4519.7  437.24  4672.4  433.61
  4774.3  426.68  4804.6  423.66  4860.6  410.78    4922  405.52  4924.2  405.47
  4938.3  403.81  4955.4  398.44  5018.4  397.74  5041.2  399.32  5058.2  404.93
  5243.8  406.93  5353.2  416.31  5411.8  419.01  5546.6  418.37  5559.3  415.63
  5576.9  418.77  5790.6  427.36  5926.3  425.08  6009.2  426.48  6230.8  436.42
    6565  443.89  7138.9  452.88  7236.9  453.97  7364.3  455.74  7367.1  455.73
#Mann= 11 ,-1 , 0
    3768     .05       0  4672.4     .16       0  4774.3     .05       0
  4804.6     .16       0    4922     .08       0  4924.2     .04       0
  5058.2     .05       0  5576.9     .16       0  7138.9     .08       0
  7236.9     .16       0  7364.3     .05       0
Bank Sta=4924.2,5058.2
XS Rating Curve= 0 ,0
Exp/Cntr=0.3,0.1

Type RM Length L Ch R = 1 ,827652  ,20,20,20
BEGIN DESCRIPTION:
NAVASOTA RIVER 302
END DESCRIPTION:
XS GIS Cut Line= 6
      3482499.66     10562348.15      3482446.14     10562137.38
      3482168.54     10561636.73       3481376.1      10560797.9
      3481277.99     10560656.34      3480687.17     10559547.22
#Sta/Elev= 30
  3731.5  450.66  4407.3  433.33  4629.2   433.5  4703.4  428.12  4709.6  427.84
  4839.5  422.11  4852.2  421.58  4869.7  419.56  4883.9  420.97  4890.9  417.73
    4898  420.02    4905  410.34  4912.2  412.32  4919.2  404.75  4926.3   404.8
  4961.6   398.9  5025.1   397.7  5046.5  400.11  5060.6  405.88  5154.7  404.05
  5236.1  407.07  5279.8  410.36  5435.4  421.89  5520.8  423.07  5563.4  422.43
  5676.2  422.56  5811.7  428.55  6382.2  442.38  6420.9  443.11  7105.9  453.19
#Mann= 15 ,-1 , 0
  3731.5     .05       0  4703.4     .16       0  4709.6     .05       0
  4839.5     .16       0  4852.2     .08       0  4926.3     .04       0
  5060.6     .05       0  5154.7     .16       0  5236.1     .05       0
  5279.8     .16       0  5520.8     .05       0  5563.4     .16       0
  5811.7     .05       0  6382.2     .08       0  6420.9     .05       0
Bank Sta=4926.3,5060.6
XS Rating Curve= 0 ,0
Exp/Cntr=0.3,0.1

Type RM Length L Ch R = 1 ,827632  ,206,206,206
BEGIN DESCRIPTION:
NAVASOTA RIVER 299
END DESCRIPTION:
XS GIS Cut Line= 6
      3482519.04     10562343.21      3482465.04     10562130.55
      3482184.52     10561624.52      3481460.99     10560878.69
      3481295.41     10560646.36      3480730.57     10559529.87
#Sta/Elev= 30
  3716.2  451.33  3755.9  450.78  3767.8  449.31    4389  433.04  4631.7  431.56
  4766.2  422.99  4853.7  422.47  4900.5  421.28  4907.7  419.56  4921.8   406.1
  4928.8  403.16  4971.3  398.78  5020.4  397.76    5042  398.91  5056.1  404.63
  5149.3  404.03  5218.7  405.23  5250.5  408.72  5261.9  409.62  5396.1  418.82
  5398.3  418.98  5487.5  424.21    5535  423.61    5538  423.52  5664.9  423.19
  5788.5  427.64    6010  435.24  6353.8  441.86    6466  444.06  7090.6  451.72
#Mann= 16 ,-1 , 0
  3716.2     .08       0  3755.9      .1       0  3767.8     .05       0
  4853.7     .08       0  4921.8     .04       0  5056.1     .05       0
  5149.3     .16       0  5250.5     .05       0  5261.9     .16       0
  5396.1     .05       0  5398.3     .16       0    5535     .05       0
    5538     .16       0  5788.5     .05       0  6353.8     .08       0
    6466     .05       0
Bank Sta=4921.8,5056.1
XS Rating Curve= 0 ,0
Exp/Cntr=0.3,0.1