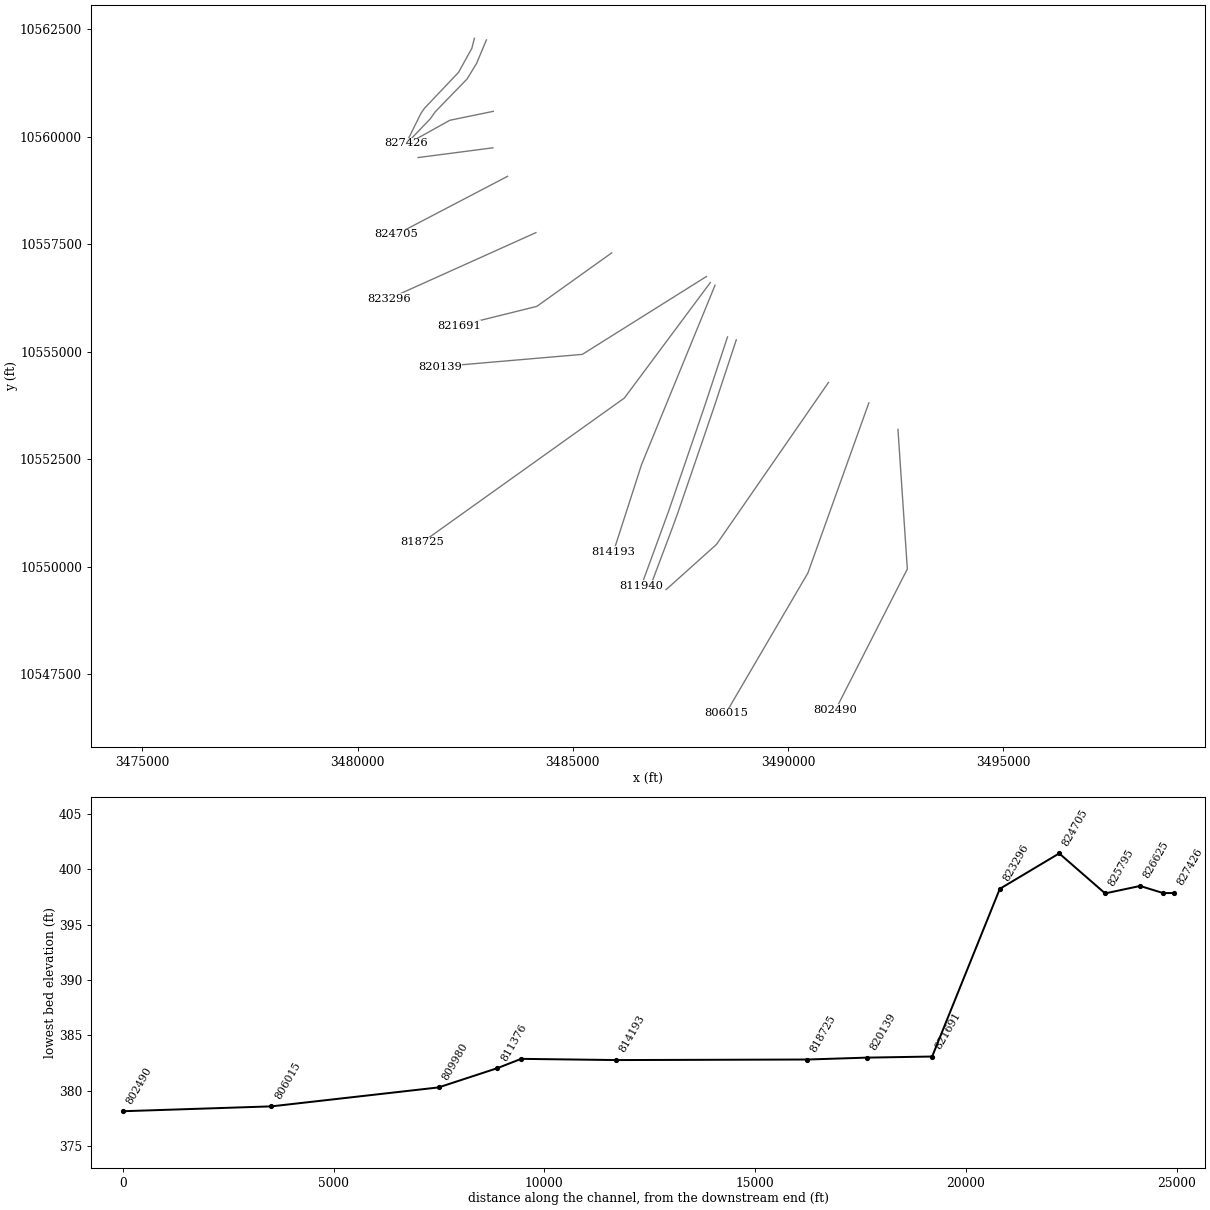
HEC-RAS study NAVASOTA RIVER.prj: NAVASOTA RIVER Base Level Engineering

--- NAVASOTA RIVER.g01 (geometry) --- (continued)

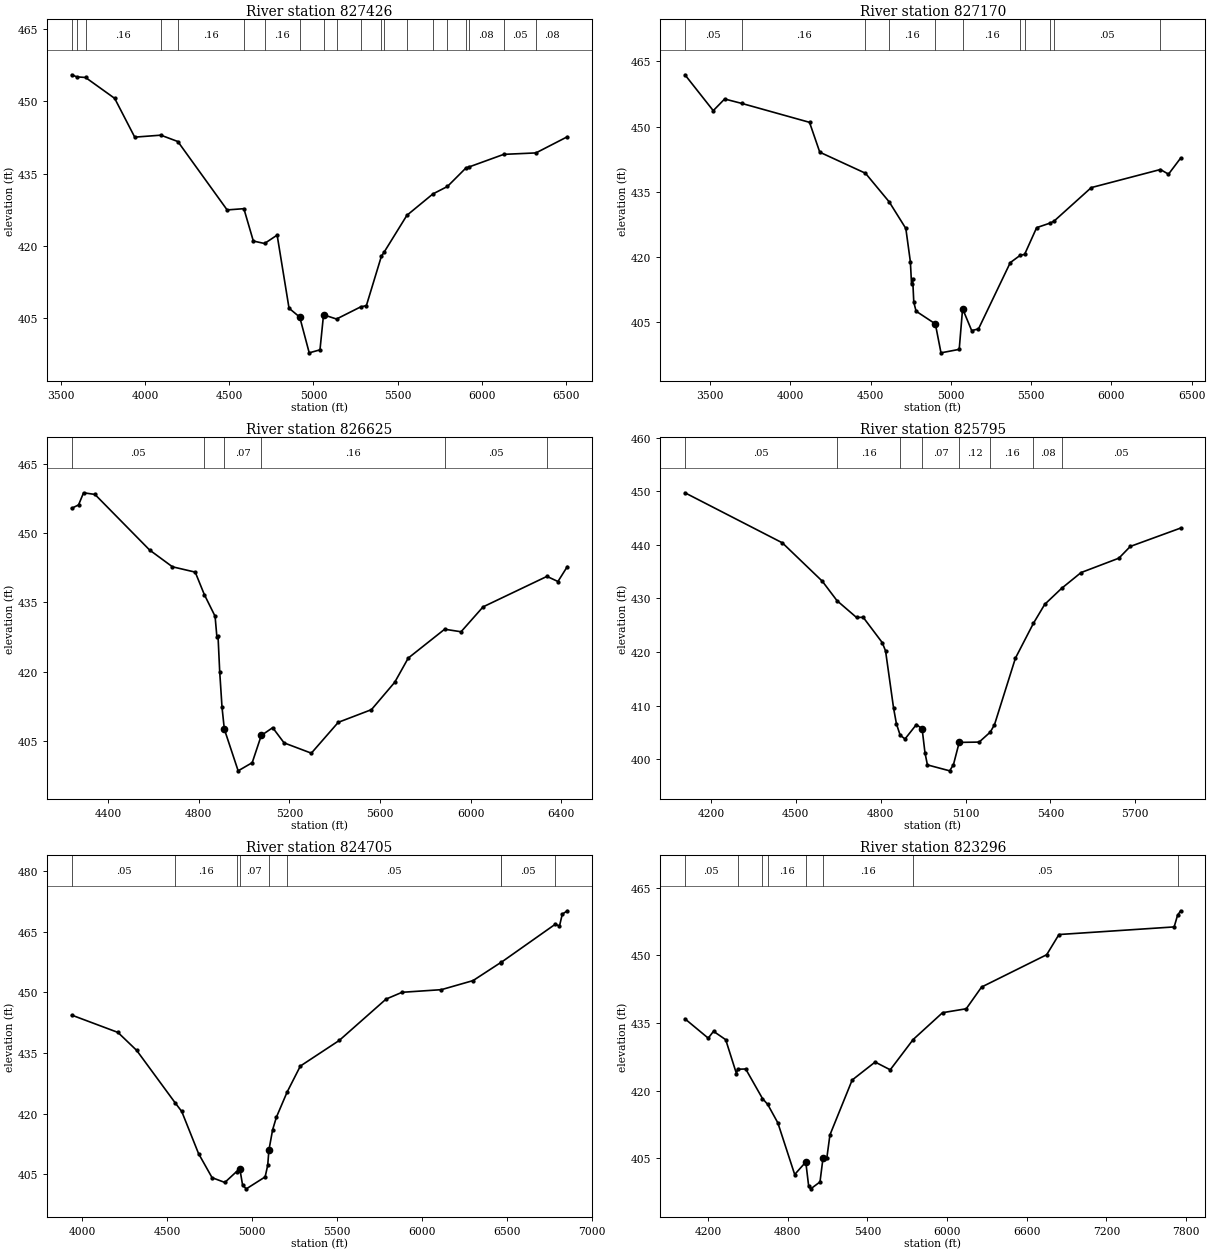
Type RM Length L Ch R = 1 ,827426  ,256,256,256
BEGIN DESCRIPTION:
NAVASOTA RIVER 300
END DESCRIPTION:
XS GIS Cut Line= 6
      3482712.89       10562294.      3482654.06      10562062.3
      3482344.31     10561502.36      3481554.88     10560669.63
      3481469.53     10560546.49      3481129.43     10559857.81
#Sta/Elev= 30
    3563   455.5  3593.9  455.07  3645.6  454.94  3818.8  450.61  3937.9  442.57
  4093.1  442.98  4194.2  441.66  4487.1  427.48  4586.6  427.74  4642.8  421.03
  4709.5  420.52  4784.3  422.26    4855   407.1  4918.6  405.26  4974.9  397.85
  5038.9  398.47    5060  405.74  5137.2  404.86  5279.7  407.36  5314.7  407.65
  5403.8  417.87  5421.6  418.81  5555.4  426.36  5710.2   430.8  5796.3  432.34
  5907.8  436.23  5922.4  436.36    6131     439  6322.3   439.3  6508.9  442.65
#Mann= 20 ,-1 , 0
    3563     .08       0  3593.9      .1       0  3645.6     .16       0
  4093.1     .05       0  4194.2     .16       0  4586.6     .08       0
  4709.5     .16       0  4918.6     .07       0    5060     .16       0
  5137.2     .16       0  5279.7     .16       0  5403.8     .05       0
  5421.6     .16       0  5555.4     .16       0  5710.2     .08       0
  5796.3      .1       0  5907.8     .05       0  5922.4     .08       0
    6131     .05       0  6322.3     .08       0
Bank Sta=4918.6,5060
XS Rating Curve= 0 ,0
Exp/Cntr=0.3,0.1

Type RM Length L Ch R = 1 ,827170  ,545,545,545
BEGIN DESCRIPTION:
NAVASOTA RIVER 301
END DESCRIPTION:
XS GIS Cut Line= 6
       3482992.3      10562257.4      3482763.73     10561711.12
      3482544.06     10561349.66       3481804.9     10560587.01
      3481687.19     10560421.67       3481128.9     10559837.84
#Sta/Elev= 30
  3343.2  461.93  3519.6  453.66  3590.6  456.35  3697.4  455.33  4119.5  450.97
  4183.4  444.09    4468  439.24    4616  432.64  4719.6  426.51  4747.9  418.84
  4755.1  413.75  4762.1  414.98  4769.2  409.52  4783.4  407.45  4903.5  404.52
  4938.7  397.85  5052.2  398.65  5073.3  408.02  5129.9  402.98  5172.3  403.36
  5370.4  418.64  5433.9  420.37  5459.5  420.52  5534.7   426.7  5618.2  427.75
  5643.3  428.21  5875.1  435.93    6306   440.1  6356.3  439.02  6431.9  442.73
#Mann= 11 ,-1 , 0
  3343.2     .05       0  3697.4     .16       0    4468     .05       0
    4616     .16       0  4903.5     .07       0  5073.3     .16       0
  5433.9     .12       0  5459.5     .16       0  5618.2     .08       0
  5643.3     .05       0    6306     .08       0
Bank Sta=4903.5,5073.3
XS Rating Curve= 0 ,0
Exp/Cntr=0.3,0.1

Type RM Length L Ch R = 1 ,826625  ,830,830,830
BEGIN DESCRIPTION:
NAVASOTA RIVER 307
END DESCRIPTION:
XS GIS Cut Line= 3
      3483151.96      10560596.6      3482141.57     10560388.27
      3481132.29     10559825.74
#Sta/Elev= 30
  4239.5  455.42    4270  456.16  4292.1  458.79  4342.4  458.43  4583.7  446.37
  4684.2  442.74  4784.8  441.58  4824.9  436.72  4872.4  432.01  4880.3  427.58
  4885.4  427.68  4892.8  419.99    4903  412.28  4913.2  407.53  4974.2  398.49
  5036.2  400.26  5076.3  406.17  5126.6  407.85  5176.9  404.55  5297.1  402.32
  5415.9  409.01  5562.3  411.76  5665.1   417.7  5724.6  422.94  5885.3   429.2
  5957.7  428.65  6054.9  434.05  6336.7  440.66  6385.2  439.55  6426.6  442.79
#Mann= 6 ,-1 , 0
  4239.5     .05       0  4824.9     .16       0  4913.2     .07       0
  5076.3     .16       0  5885.3     .05       0  6336.7     .08       0
Bank Sta=4913.2,5076.3
XS Rating Curve= 0 ,0
Exp/Cntr=0.3,0.1

Type RM Length L Ch R = 1 ,825795  ,1090,1090,1090
BEGIN DESCRIPTION:
NAVASOTA RIVER 073
END DESCRIPTION:
XS GIS Cut Line= 2
      3483143.75     10559747.83      3481405.63     10559521.47
#Sta/Elev= 30
  4107.9  449.74  4452.4  440.39  4593.6  433.23  4645.7  429.59  4714.6  426.46
  4738.2  426.49  4805.4  421.78  4817.3  420.22  4845.7  409.52  4855.8  406.59
  4868.9  404.48  4886.1  403.77  4926.4  406.47  4946.6  405.66  4956.7  401.19
  4965.3  398.93  5044.1  397.82  5057.5     399  5077.7  403.13  5148.3  403.19
  5187.5  405.05  5202.4  406.42  5276.5  418.86  5340.2  425.37  5380.2  428.91
  5439.5  431.88  5508.6  434.84  5642.4  437.53  5682.7  439.72  5860.7  443.15
#Mann= 8 ,-1 , 0
  4107.9     .05       0  4645.7     .16       0  4868.9     .12       0
  4946.6     .07       0  5077.7     .12       0  5187.5     .16       0
  5340.2     .08       0  5439.5     .05       0
Bank Sta=4946.6,5077.7
XS Rating Curve= 0 ,0
Exp/Cntr=0.3,0.1

Type RM Length L Ch R = 1 ,824705  ,1409,1409,1409
BEGIN DESCRIPTION:
NAVASOTA RIVER 306
END DESCRIPTION:
XS GIS Cut Line= 2
      3483484.01     10559085.31      3480900.71      10557732.9
#Sta/Elev= 30
  3938.8  444.38  4211.2  440.09  4321.6  435.64  4547.9  422.68  4586.4  420.56
  4685.4  410.14  4764.9  404.19  4839.9  403.01  4908.9  405.69  4928.2  406.37
  4944.6  402.31  4966.4  401.43    5077  404.38  5092.3  407.27  5099.1  410.97
  5121.1  416.03  5143.2  419.13  5206.6  425.37  5284.2  431.78  5512.7   438.1
  5788.3  448.33  5882.4  450.01  6113.7  450.66    6300   452.9  6462.5  457.35
  6465.3   457.4  6783.6  466.83  6808.6   466.4    6825  469.32  6854.7  470.16
#Mann= 9 ,-1 , 0
  3938.8     .05       0  4547.9     .16       0  4908.9     .12       0
  4928.2     .07       0  5099.1     .16       0  5206.6     .05       0
  6462.5     .08       0  6465.3     .05       0  6783.6     .08       0
Bank Sta=4928.2,5099.1
XS Rating Curve= 0 ,0
Exp/Cntr=0.3,0.1

Type RM Length L Ch R = 1 ,823296  ,1605,1605,1605
BEGIN DESCRIPTION:
NAVASOTA RIVER 308
END DESCRIPTION:
XS GIS Cut Line= 2
      3484142.08     10557775.66      3480737.65     10556241.85
#Sta/Elev= 30
  4024.8  435.95  4200.3  431.66  4240.1  433.18  4331.9  431.32    4413  423.77
  4421.3  424.77  4482.5  424.82    4609  418.26  4648.3  416.96  4724.8  412.86
  4851.5  401.41  4935.1  404.18  4957.1  398.77  4972.4  398.23  5042.1  399.76
  5065.2  405.13  5093.9  405.13    5117  410.19  5284.5  422.37  5457.4  426.36
  5571.3  424.64    5744  431.36  5965.3  437.31  6143.7  438.18  6259.4     443
  6749.7  450.17  6842.2  454.65    7710  456.34  7735.5  458.91  7758.8  459.92
#Mann= 8 ,-1 , 0
  4024.8     .05       0  4421.3     .16       0    4609     .05       0
  4648.3     .16       0  4935.1     .07       0  5065.2     .16       0
    5744     .05       0  7735.5     .08       0
Bank Sta=4935.1,5065.2
XS Rating Curve= 0 ,0
Exp/Cntr=0.3,0.1

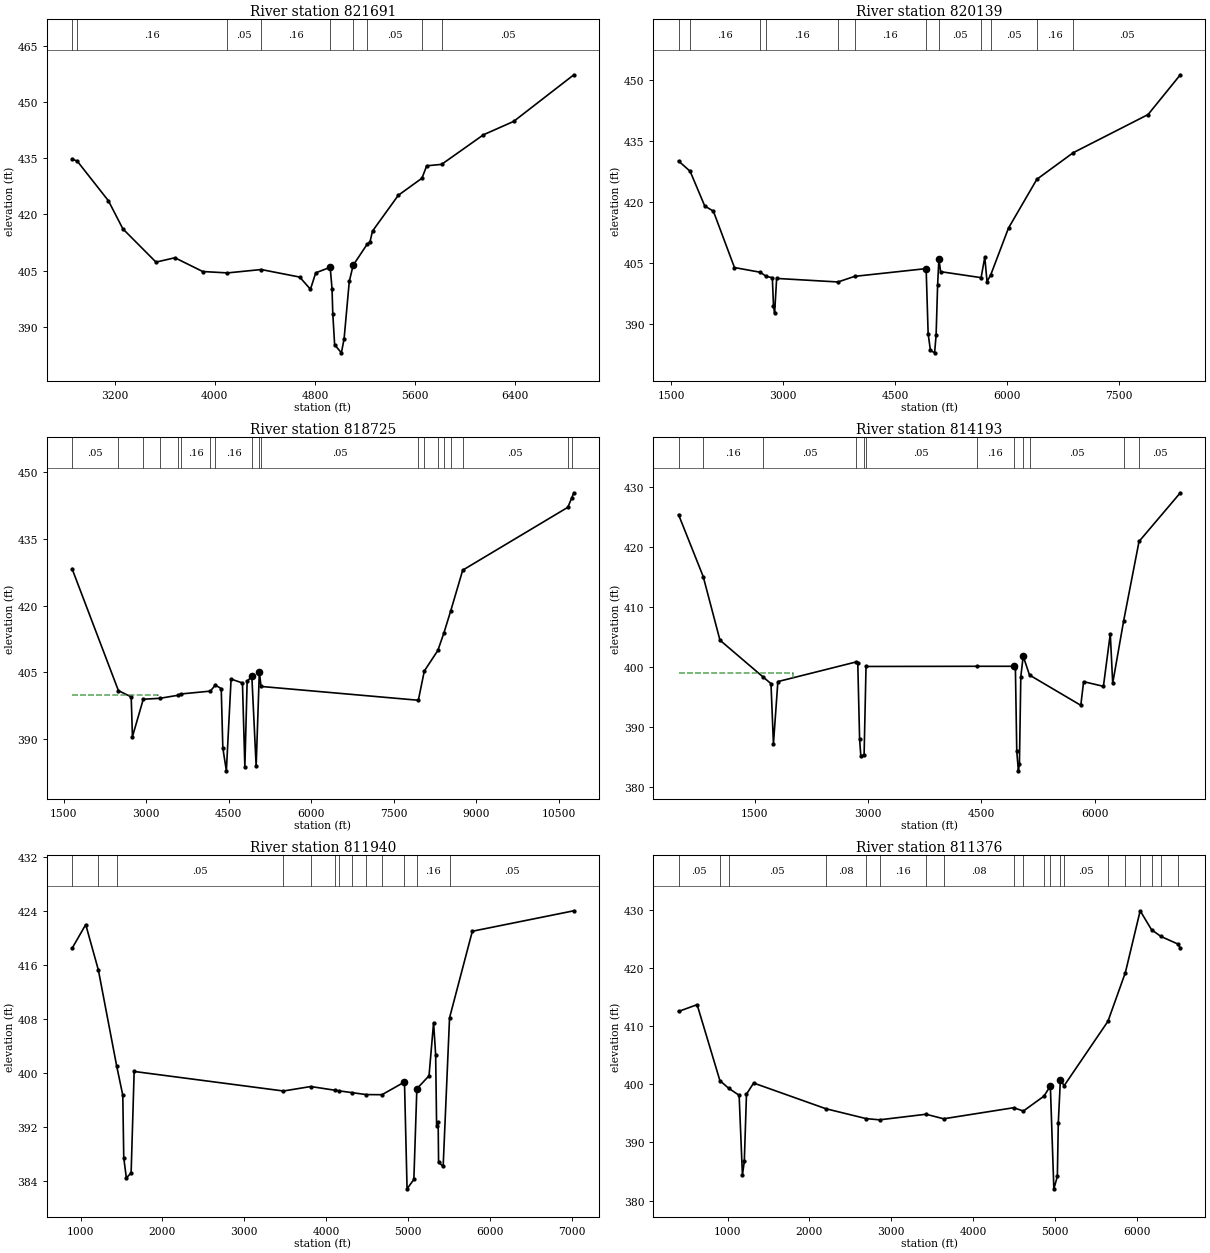
Type RM Length L Ch R = 1 ,821691  ,1552,1552,1552
BEGIN DESCRIPTION:
NAVASOTA RIVER 309
END DESCRIPTION:
XS GIS Cut Line= 3
      3485903.94      10557304.9      3484163.68     10556060.33
      3482351.89     10555610.48
#Sta/Elev= 30
  2860.5  434.77  2901.4  434.25  3150.7  423.65  3266.2  416.16  3530.4  407.29
  3681.5  408.45  3903.9  404.78  4101.1  404.41  4370.5  405.31  4677.9   403.3
  4763.9  400.04  4805.7  404.42  4921.2  405.92    4936  400.22  4942.1  393.56
  4956.8  385.25  5010.8  383.09  5032.5  386.87  5073.7  402.13  5104.7  406.45
    5215  411.99  5238.6  412.62  5259.2  415.57  5465.3  425.12  5653.9  429.67
    5692  432.98  5810.7  433.36  6145.3  441.26  6386.1  444.82  6866.8  457.26
#Mann= 9 ,-1 , 0
  2860.5     .05       0  2901.4     .16       0  4101.1     .05       0
  4370.5     .16       0  4921.2     .07       0  5104.7     .16       0
    5215     .05       0  5653.9      .1       0  5810.7     .05       0
Bank Sta=4921.2,5104.7
XS Rating Curve= 0 ,0
Exp/Cntr=0.3,0.1

Type RM Length L Ch R = 1 ,820139  ,1414,1414,1414
BEGIN DESCRIPTION:
NAVASOTA RIVER 310
END DESCRIPTION:
XS GIS Cut Line= 3
      3488103.21     10556754.59      3485220.73     10554944.29
       3481910.6     10554659.09
#Sta/Elev= 30
  1596.2  430.09  1751.4  427.57  1947.7  419.04  2063.2  417.78  2345.9  403.93
  2690.4  402.78  2774.8  401.74  2853.6  401.44  2868.9  394.58  2884.2  392.77
  2911.3  401.26  3733.5  400.39  3957.5  401.77  4915.1  403.67  4942.2  387.63
  4972.8  383.59  5028.5  382.99  5048.8  387.31  5068.9  399.62  5086.5  406.07
    5109  402.92    5652  401.45  5701.2  406.47  5731.3  400.47  5781.9  402.17
  6019.2  413.63  6399.3   425.6  6886.2  432.12  7889.6  441.49  8322.4  451.26
#Mann= 12 ,-1 , 0
  1596.2     .05       0  1751.4     .16       0  2690.4     .05       0
  2774.8     .16       0  3733.5     .05       0  3957.5     .16       0
  4915.1     .07       0  5086.5     .05       0    5652     .12       0
  5781.9     .05       0  6399.3     .16       0  6886.2     .05       0
#XS Ineff= 2 , 0
       0  2911.3  401.26               0
Permanent Ineff=
       F       F
Bank Sta=4915.1,5086.5
XS Rating Curve= 0 ,0
Exp/Cntr=0.3,0.1

Type RM Length L Ch R = 1 ,818725  ,4532,4532,4532
BEGIN DESCRIPTION:
NAVASOTA RIVER 311
END DESCRIPTION:
XS GIS Cut Line= 3
       3488194.5     10556614.41      3486197.09     10553928.26
      3481496.86     10550569.46
#Sta/Elev= 30
  1652.6  428.32  2495.2  400.88  2727.8  399.47  2750.4  390.51  2947.2  398.94
    3251  399.15  3576.4  399.83  3628.9  400.12  4167.6  400.77  4257.4  402.13
  4364.8  401.33    4394  387.98  4458.4  382.82  4544.2  403.48  4750.7   402.6
  4794.5   383.7  4836.2     403  4921.7  404.06    5000  383.86  5057.9  405.07
  5088.8  401.82  7948.9  398.71  8057.6  405.29  8303.5  409.92    8415   413.9
  8539.9  418.91    8756     428 10667.3  442.15 10737.5  444.25   10777  445.42
#Mann= 19 ,-1 , 0
  1652.6     .05       0  2495.2     .16       0  2947.2      .1       0
    3251     .16       0  3576.4     .05       0  3628.9     .16       0
  4167.6      .1       0  4257.4     .16       0  4921.7     .07       0
  5057.9     .16       0  5088.8     .05       0  7948.9     .16       0
  8057.6     .12       0  8303.5     .16       0    8415     .05       0
  8539.9     .16       0    8756     .05       0 10667.3     .08       0
 10737.5     .05       0
#XS Ineff= 2 , 0
       0  3206.8  399.92               0
Permanent Ineff=
       F       F
Bank Sta=4921.7,5057.9
XS Rating Curve= 0 ,0
Exp/Cntr=0.3,0.1

Type RM Length L Ch R = 1 ,814193  ,2253,2253,2253
BEGIN DESCRIPTION:
NAVASOTA RIVER 312
END DESCRIPTION:
XS GIS Cut Line= 3
      3488304.78      10556553.9      3486597.05     10552381.77
      3485943.65     10550352.47
#Sta/Elev= 30
   491.9  425.46   818.1  415.15  1040.1  404.54  1610.5  398.41  1715.3   397.3
  1747.6  387.26  1806.4  397.64  2840.9  400.91  2863.8  400.71  2887.9  388.06
  2903.9  385.29  2947.3  385.38    2973  400.16  4435.3  400.19  4935.3  400.19
  4949.3  399.95  4967.7  386.01  4989.1  382.77  5002.7  383.91  5021.1  398.48
  5052.7  401.87  5136.3  398.73  5814.9  393.69  5852.2  397.63  6114.1  396.85
    6205  405.59  6237.1  397.37  6382.3  407.79  6585.5  420.99  7131.9   429.1
#Mann= 12 ,-1 , 0
   491.9     .05       0   818.1     .16       0  1610.5     .05       0
  2840.9     .16       0  2947.3      .1       0    2973     .05       0
  4435.3     .16       0  4935.3     .07       0  5052.7     .16       0
  5136.3     .05       0  6382.3     .16       0  6585.5     .05       0
#XS Ineff= 2 , 0
       0  2007.1  399.07               0
Permanent Ineff=
       F       F
Bank Sta=4935.3,5052.7
XS Rating Curve= 0 ,0
Exp/Cntr=0.3,0.1

Type RM Length L Ch R = 1 ,811940  ,564,564,564
BEGIN DESCRIPTION:
NAVASOTA RIVER 296
END DESCRIPTION:
XS GIS Cut Line= 5
      3488593.98     10555350.11      3488087.25     10553816.06
      3487812.36     10553008.71      3487229.55     10551309.74
      3486589.57     10549556.27
#Sta/Elev= 30
   896.8  418.47  1063.7  421.99  1218.2  415.26  1441.9  401.06  1516.5  396.73
  1528.4  387.46  1560.1  384.49  1618.4  385.24  1655.4  400.25  3479.5  397.36
  3813.1  398.02  4110.4  397.47    4161  397.38  4320.7  397.11  4489.4  396.83
  4683.4  396.81  4958.5  398.69    4990  382.88    5073  384.27  5109.6  397.69
  5258.3  399.61    5314  407.48  5339.3  402.73    5351  392.23  5369.8  392.72
  5375.1  386.81  5430.9  386.19  5509.1  408.19  5787.4     421    7028  424.03
#Mann= 13 ,-1 , 0
   896.8     .05       0  1218.2     .16       0  1441.9     .05       0
  3479.5     .16       0  3813.1     .05       0  4110.4     .16       0
    4161     .05       0  4320.7     .16       0  4489.4     .05       0
  4683.4     .16       0  4958.5     .07       0  5109.6     .16       0
  5509.1     .05       0
#XS Ineff= 2 , 0
       0  1655.4  400.25               0
Permanent Ineff=
       F       F
Bank Sta=4958.5,5109.6
XS Rating Curve= 0 ,0
Exp/Cntr=0.3,0.1

Type RM Length L Ch R = 1 ,811376  ,1396,1396,1396
BEGIN DESCRIPTION:
NAVASOTA RIVER 295
END DESCRIPTION:
XS GIS Cut Line= 6
      3488798.13     10555282.69       3488291.1     10553747.69
       3488015.8     10552939.18      3487432.24     10551237.99
      3487289.11     10550845.84      3486780.55     10549495.76
#Sta/Elev= 30
   401.8   412.5   628.8  413.67   907.4  400.61  1016.2  399.29  1141.9  398.11
  1182.2  384.41  1205.3  386.77  1231.8   398.3  1319.1  400.21  2200.7   395.8
  2693.5   394.1  2856.8  393.89    3425  394.85  3639.6  394.07  4495.5  395.97
  4613.9   395.4  4865.6  397.96  4943.5   399.7  4986.2  382.04    5029  384.16
  5040.5  393.33  5065.7  400.67  5112.9  399.77  5647.2  410.82    5860  419.19
  6040.6  429.79  6179.3  426.54  6294.3  425.38  6498.5   424.1  6531.1  423.39
#Mann= 20 ,-1 , 0
   401.8     .05       0   907.4     .16       0  1016.2     .05       0
  2200.7     .08       0  2693.5     .08       0  2856.8     .16       0
    3425     .05       0  3639.6     .08       0  4495.5     .16       0
  4613.9     .05       0  4865.6     .16       0  4943.5     .07       0
  5065.7     .16       0  5112.9     .05       0  5647.2     .05       0
    5860     .05       0  6040.6     .05       0  6179.3     .08       0
  6294.3     .05       0  6498.5     .08       0
#XS Ineff= 2 , 0
       0  1319.1  400.21               0
Permanent Ineff=
       F       F
Bank Sta=4943.5,5065.7
XS Rating Curve= 0 ,0
Exp/Cntr=0.3,0.1

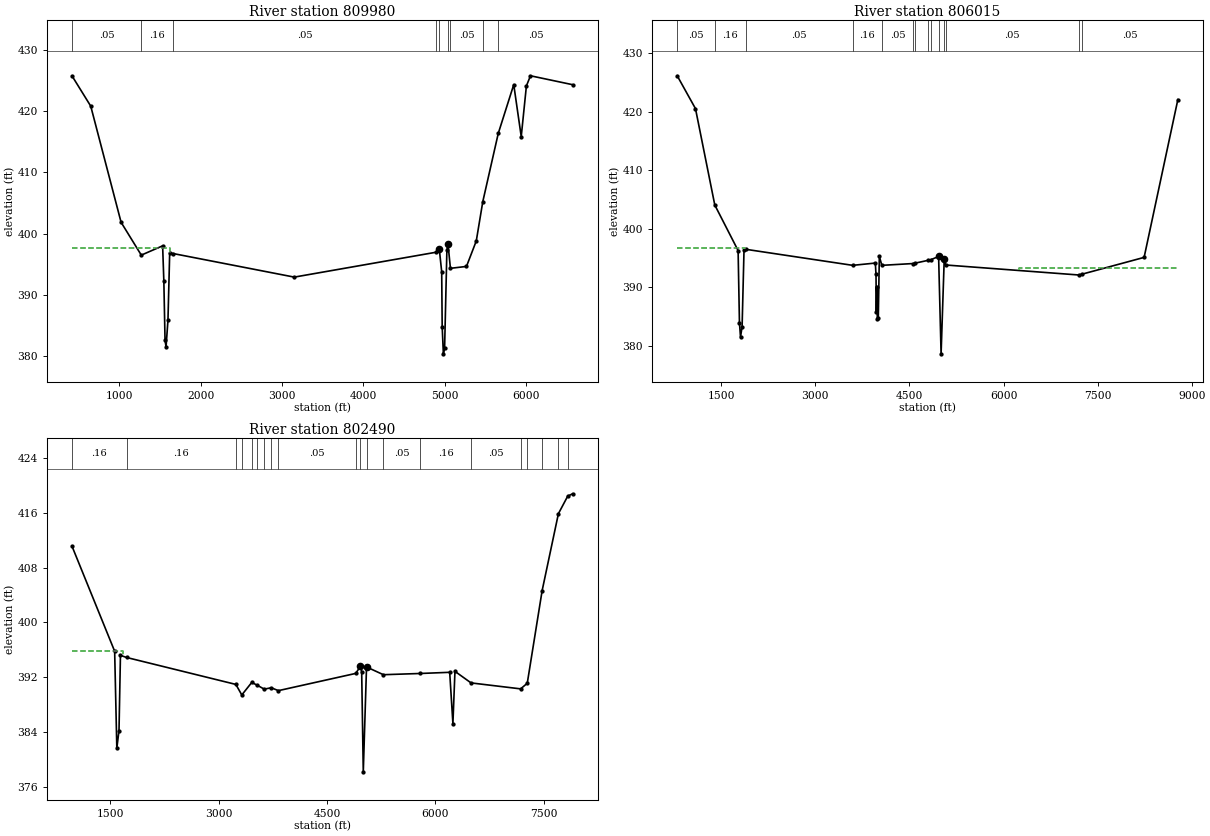
Type RM Length L Ch R = 1 ,809980  ,3965,3965,3965
BEGIN DESCRIPTION:
NAVASOTA RIVER 313
END DESCRIPTION:
XS GIS Cut Line= 3
      3490940.61     10554292.04      3488337.28     10550524.36
      3487167.63     10549473.92
#Sta/Elev= 30
   420.4   425.8   650.5  420.85  1023.6  401.83  1271.7  396.46  1533.9  397.98
  1548.8  392.23  1563.4  382.56  1575.8  381.42  1599.5  385.82  1620.5  396.79
  1666.3  396.71  3151.4  392.86  4892.7  396.93  4933.2  397.48  4962.9  393.74
    4969  384.75  4983.6   380.3  4998.6  381.21  5026.8   397.3    5041  398.21
  5070.2   394.3  5267.5  394.61  5387.9  398.78    5468  405.22  5657.9  416.38
  5848.3  424.37  5940.3  415.87  6003.8  424.16  6053.9  425.82  6572.1  424.36
#Mann= 9 ,-1 , 0
   420.4     .05       0  1271.7     .16       0  1666.3     .05       0
  4892.7     .16       0  4933.2     .07       0    5041     .16       0
  5070.2     .05       0    5468     .16       0  5657.9     .05       0
#XS Ineff= 2 , 0
       0  1626.5  397.58               0
Permanent Ineff=
       F       F
Bank Sta=4933.2,5041
XS Rating Curve= 0 ,0
Exp/Cntr=0.3,0.1

Type RM Length L Ch R = 1 ,806015  ,3525,3525,3525
BEGIN DESCRIPTION:
NAVASOTA RIVER 314
END DESCRIPTION:
XS GIS Cut Line= 3
      3491877.68     10553815.89      3490460.96     10549858.97
       3488553.9     10546595.18
#Sta/Elev= 30
   797.1  426.16  1088.4  420.54  1396.4  404.05  1768.2  396.26  1789.4  383.95
  1806.4  381.45  1831.9  383.24  1862.6  396.43  1892.6  396.47  3595.4  393.73
  3956.2  394.12  3966.9  392.18  3972.6  385.71    3978  390.09  3988.1  384.61
  4003.4  384.68    4020  395.28    4060  393.73  4562.9  394.04    4585  394.09
  4803.3   394.6  4841.2  394.69  4965.3  395.25  5004.9  378.59  5054.8  394.76
  5078.6  393.79  7199.2  392.08  7249.2  392.21  8242.1  395.09  8780.1  422.08
#Mann= 14 ,-1 , 0
   797.1     .05       0  1396.4     .16       0  1892.6     .05       0
  3595.4     .16       0    4060     .05       0  4562.9     .12       0
    4585     .16       0  4803.3     .12       0  4841.2     .16       0
  4965.3     .07       0  5054.8     .16       0  5078.6     .05       0
  7199.2     .16       0  7249.2     .05       0
#XS Ineff= 2 , 0
       0  1874.4  396.65  6239.3       0  393.32
Permanent Ineff=
       F       F
Bank Sta=4965.3,5054.8
XS Rating Curve= 0 ,0
Exp/Cntr=0.3,0.1

Type RM Length L Ch R = 1 ,802490  ,3817,3817,3817
BEGIN DESCRIPTION:
NAVASOTA RIVER 315
END DESCRIPTION:
XS GIS Cut Line= 3
       3492553.9     10553200.32      3492771.79     10549953.08
      3491105.11     10546680.49
#Sta/Elev= 30
     973  411.13    1563  395.78  1593.1   381.6  1623.2  384.19  1643.2  395.18
  1727.7  394.87  3240.1  390.93  3322.2  389.39  3460.1  391.22  3534.4  390.82
  3632.4  390.24  3730.5  390.44  3828.6  390.02  4898.9  392.54  4964.6   393.6
    4981  392.74  5003.2  378.15    5048  393.48  5281.6  392.35  5792.8  392.53
  6198.8   392.7  6243.3  385.21  6271.6  392.84  6494.4  391.15  7180.5  390.28
  7272.1   391.1  7478.2  404.66    7703  415.89  7832.1  418.46  7900.1   418.8
#Mann= 20 ,-1 , 0
     973     .16       0  1727.7     .16       0  3240.1     .05       0
  3322.2     .16       0  3460.1     .05       0  3534.4     .16       0
  3632.4     .05       0  3730.5     .16       0  3828.6     .05       0
  4898.9     .16       0  4964.6     .07       0    5048     .16       0
  5281.6     .05       0  5792.8     .16       0  6494.4     .05       0
  7180.5     .16       0  7272.1     .05       0  7478.2     .12       0
    7703     .16       0  7832.1     .16       0
#XS Ineff= 2 , 0
       0  1673.3  395.86  6198.8       0   392.7
Permanent Ineff=
       F       F
Bank Sta=4964.6,5048
XS Rating Curve= 0 ,0
Exp/Cntr=0.3,0.1