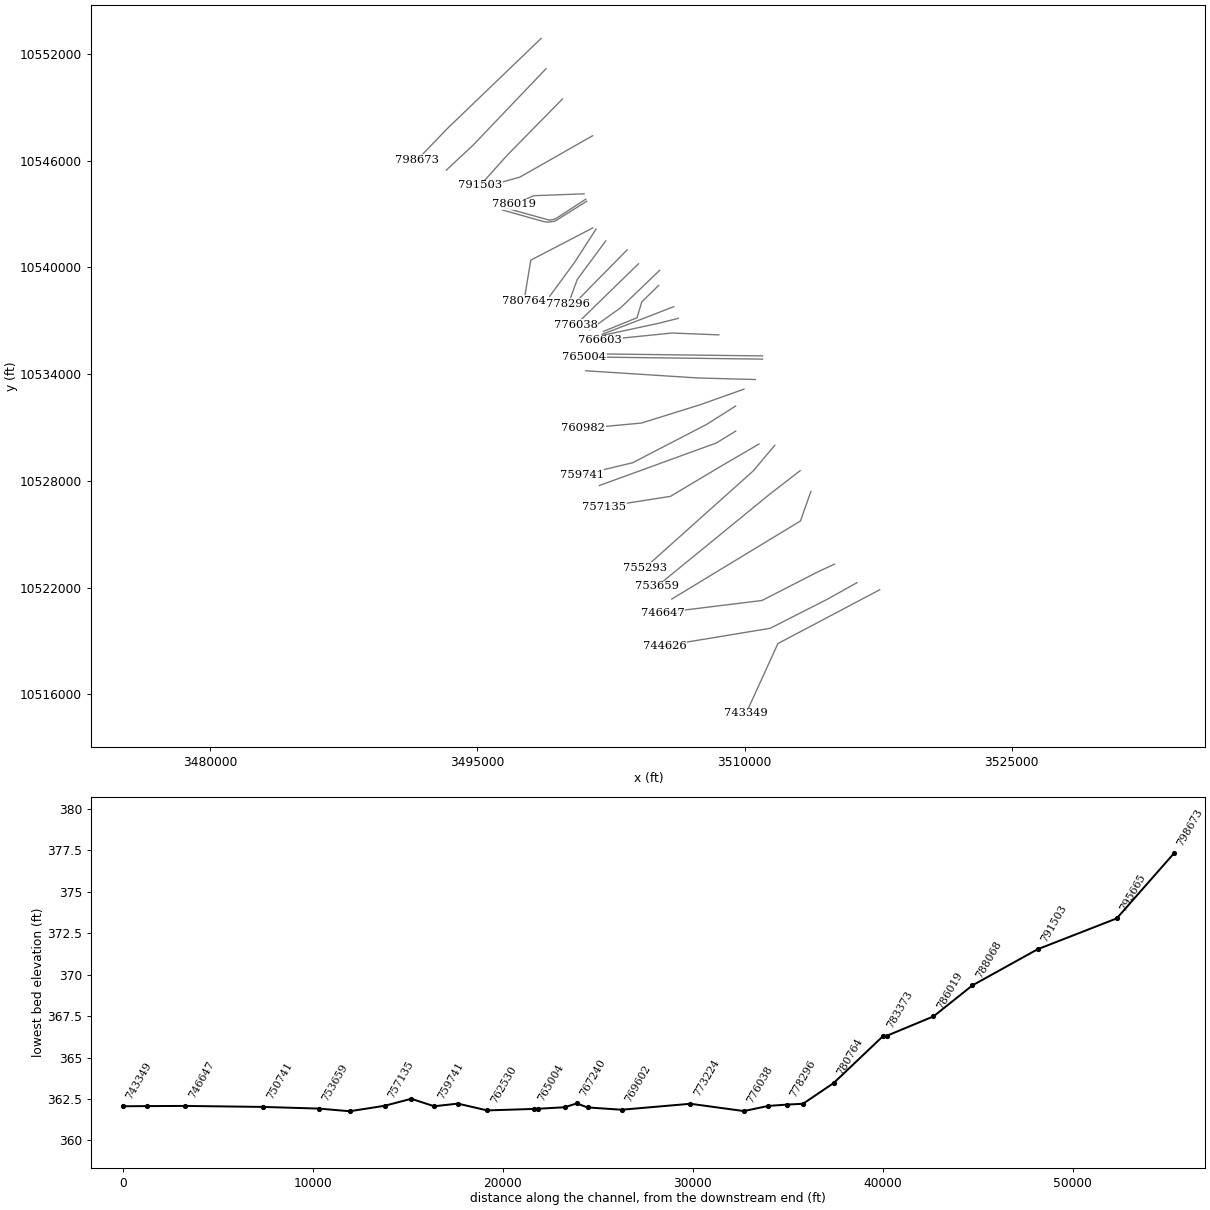
HEC-RAS study NAVASOTA RIVER.prj: NAVASOTA RIVER Base Level Engineering

--- NAVASOTA RIVER.g01 (geometry) --- (continued)

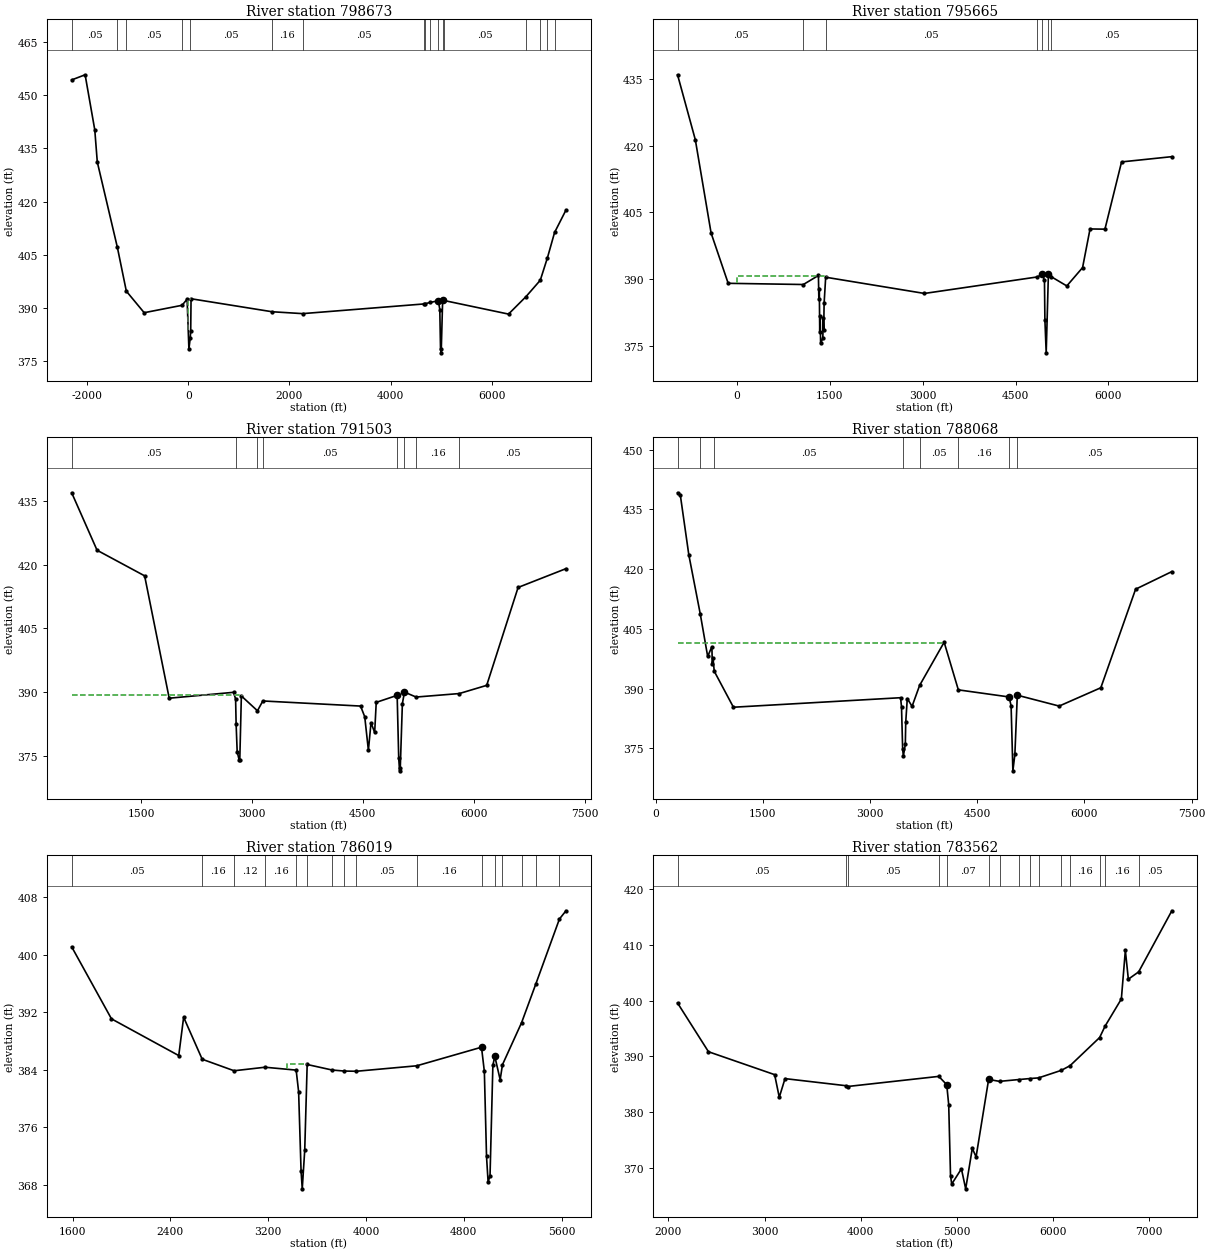
Type RM Length L Ch R = 1 ,798673  ,3008,3008,3008
BEGIN DESCRIPTION:
NAVASOTA RIVER 316
END DESCRIPTION:
XS GIS Cut Line= 3
       3498579.1     10552869.77      3493315.42     10547807.56
      3491608.61     10546029.49
#Sta/Elev= 30
 -2302.9  454.36 -2037.6  455.81 -1846.7  440.25 -1797.1  431.18 -1400.5   407.1
 -1223.2  394.72  -870.6  388.64  -122.7  390.73   -21.9  392.46    13.3  378.41
    39.9  381.52    48.8  383.54    55.8  392.58  1657.4  388.91  2260.5  388.38
  4665.3  391.12  4681.2  391.18  4779.6  391.53  4942.9  392.02  4971.2  389.51
  4985.3  378.41  4998.6  377.31  5027.7  392.36  5052.9  392.09    6329  388.25
  6673.8  393.17  6956.6   397.8  7097.9  404.14  7239.3  411.29  7464.7  417.63
#Mann= 17 ,-1 , 0
 -2302.9     .05       0 -1400.5     .16       0 -1223.2     .05       0
  -122.7     .16       0    39.9     .05       0  1657.4     .16       0
  2260.5     .05       0  4665.3     .16       0  4681.2     .05       0
  4779.6     .16       0  4942.9     .07       0  5027.7     .16       0
  5052.9     .05       0  6673.8     .16       0  6956.6     .05       0
  7097.9     .16       0  7239.3     .05       0
#XS Ineff= 2 , 0
       0    55.8  392.58               0
Permanent Ineff=
       F       F
Bank Sta=4942.9,5027.7
XS Rating Curve= 0 ,0
Exp/Cntr=0.3,0.1

Type RM Length L Ch R = 1 ,795665  ,4162,4162,4162
BEGIN DESCRIPTION:
NAVASOTA RIVER 317
END DESCRIPTION:
XS GIS Cut Line= 3
      3498848.06      10551161.6      3494737.44      10546848.9
      3493256.75     10545470.02
#Sta/Elev= 30
  -957.9  435.94  -670.7  421.31  -416.3  400.34  -140.4  389.03  1073.2  388.76
  1316.8  390.79  1323.7  385.47    1331  387.86  1337.9  378.06  1345.1  381.68
    1352  375.55  1387.6  376.64  1394.5   381.3  1401.7  378.45  1408.6  384.51
  1433.8   390.4  3028.5  386.75  4844.8  390.45    4931  391.02  4966.6  389.68
  4973.5  380.88  4994.4  373.39  5030.2  391.14  5074.1  390.53  5327.3  388.44
  5581.8  392.56  5702.5  401.26  5942.9  401.21  6211.6  416.34  7023.3  417.52
#Mann= 7 ,-1 , 0
  -957.9     .05       0  1073.2     .16       0  1433.8     .05       0
  4844.8     .16       0    4931     .07       0  5030.2     .16       0
  5074.1     .05       0
#XS Ineff= 2 , 0
       0  1458.3  390.77               0
Permanent Ineff=
       F       F
Bank Sta=4931,5030.2
XS Rating Curve= 0 ,0
Exp/Cntr=0.3,0.1

Type RM Length L Ch R = 1 ,791503  ,3435,3435,3435
BEGIN DESCRIPTION:
NAVASOTA RIVER 318
END DESCRIPTION:
XS GIS Cut Line= 3
      3499769.64      10549459.2      3496660.48     10546293.75
      3495163.65     10544615.75
#Sta/Elev= 30
     563  436.91   906.1   423.4  1549.5  417.38  1881.9  388.61  2751.6  389.99
  2779.9  388.44  2786.9  382.55  2801.2  376.06  2829.5  373.97  2836.5  374.08
  2857.8  389.14  3075.7  385.65    3148  387.96  4470.1  386.76  4526.5  384.25
  4576.1  376.36  4611.4  382.83  4660.9  380.56  4682.1  387.63    4965  389.28
  4986.2   374.5  4997.7  371.53  5007.3  372.27  5035.7  387.36  5064.1  390.04
  5221.5  388.88    5805   389.7  6176.1  391.63  6600.8  414.65  7248.6  419.07
#Mann= 8 ,-1 , 0
     563     .05       0  2786.9     .12       0  3075.7     .16       0
    3148     .05       0    4965    .035       0  5064.1     .12       0
  5221.5     .16       0    5805     .05       0
#XS Ineff= 2 , 0
       0  2864.8  389.37               0
Permanent Ineff=
       F       F
Bank Sta=4965,5064.1
XS Rating Curve= 0 ,0
Exp/Cntr=0.3,0.1

Type RM Length L Ch R = 1 ,788068  ,2049,2049,2049
BEGIN DESCRIPTION:
NAVASOTA RIVER 319
END DESCRIPTION:
XS GIS Cut Line= 3
      3501463.91      10547394.8      3497385.07     10545073.14
       3495245.7     10544469.86
#Sta/Elev= 30
   306.7  439.16   346.2   438.5   464.4  423.57   625.1  408.68   728.1  398.08
   787.2  400.52     793  396.16   803.1  397.68     820  394.36  1088.4  385.32
    3427  387.71  3440.3  385.43  3456.2  374.87  3466.2  373.06  3493.7  376.02
  3499.4  381.53    3521  387.49  3588.1  385.55  3693.8   390.8  4036.9  401.64
  4235.5  389.68  4945.9   387.9  4973.7  385.66  4998.6  369.35  5026.5  373.48
  5060.5  388.34  5646.2  385.61  6229.1  390.21  6715.5  414.95  7222.8  419.37
#Mann= 8 ,-1 , 0
   306.7     .05       0   625.1     .16       0     820     .05       0
  3466.2     .16       0  3693.8     .05       0  4235.5     .16       0
  4945.9     .07       0  5060.5     .05       0
#XS Ineff= 2 , 0
       0  4021.1  401.56               0
Permanent Ineff=
       F       F
Bank Sta=4945.9,5060.5
XS Rating Curve= 0 ,0
Exp/Cntr=0.3,0.1

Type RM Length L Ch R = 1 ,786019  ,2457,2457,2457
BEGIN DESCRIPTION:
NAVASOTA RIVER 110
END DESCRIPTION:
XS GIS Cut Line= 3
       3500987.3     10544131.53      3498160.87     10544027.36
       3497049.8     10543534.32
#Sta/Elev= 30
  1592.8  401.09  1918.2  391.09  2468.6  385.99  2508.6  391.31  2660.5  385.48
  2921.2  383.88  3174.5  384.37  3429.2  383.97  3449.3  380.97  3469.3  369.97
    3479  367.48  3499.3  372.85  3519.3  384.75    3724  383.98  3822.8  383.84
  3921.8  383.81  4415.7  384.57  4945.5  387.15  4968.8  383.79  4986.6  371.98
  4999.6   368.4  5015.3  369.33  5038.6  384.65  5054.3  385.88  5098.1  382.64
  5117.2  384.73  5273.7  390.57  5389.6  395.92  5583.1  404.96  5636.7   406.1
#Mann= 16 ,-1 , 0
  1592.8     .05       0  2660.5     .16       0  2921.2     .12       0
  3174.5     .16       0  3429.2     .07       0  3519.3     .12       0
    3724     .16       0  3822.8     .12       0  3921.8     .05       0
  4415.7     .16       0  4945.5     .07       0  5054.3     .16       0
  5117.2     .12       0  5273.7     .16       0  5389.6     .12       0
  5583.1     .16       0
#XS Ineff= 2 ,-1
  1838.2  2508.6  391.31  3354.3  3519.3  384.75
Permanent Ineff=
       F       F
Bank Sta=4945.5,5054.3
XS Rating Curve= 0 ,0
Exp/Cntr=0.3,0.1

Type RM Length L Ch R = 1 ,783562  ,189,189,189
BEGIN DESCRIPTION:
NAVASOTA RIVER 108
END DESCRIPTION:
XS GIS Cut Line= 4
       3501077.9     10543831.46      3499365.73     10542713.99
      3499035.87     10542653.23      3496376.23     10543390.81
#Sta/Elev= 30
  2094.3  399.56  2415.9  390.84  3103.9  386.74  3152.1  382.69  3211.8  386.03
  3846.8  384.76  3862.7  384.62  4810.6  386.43  4893.3  384.95    4914  381.37
  4932.8  368.69  4945.2  367.16  5046.1  369.89  5090.5  366.31  5159.3  373.55
  5198.7  372.03  5329.1  385.88  5442.5  385.54  5640.7  385.86  5763.6  386.05
  5848.2  386.16  6084.8  387.51  6175.6  388.34  6483.3  393.38  6540.7  395.44
  6709.3  400.28  6750.8  408.96    6782  403.82  6889.2  405.13  7234.3  416.06
#Mann= 15 ,-1 , 0
  2094.3     .05       0  3846.8     .08       0  3862.7     .05       0
  4810.6     .16       0  4893.3     .07       0  5329.1     .05       0
  5442.5     .12       0  5640.7     .05       0  5763.6     .12       0
  5848.2     .05       0  6084.8     .12       0  6175.6     .16       0
  6483.3     .12       0  6540.7     .16       0  6889.2     .05       0
Bank Sta=4893.3,5329.1
XS Rating Curve= 0 ,0
Exp/Cntr=0.3,0.1

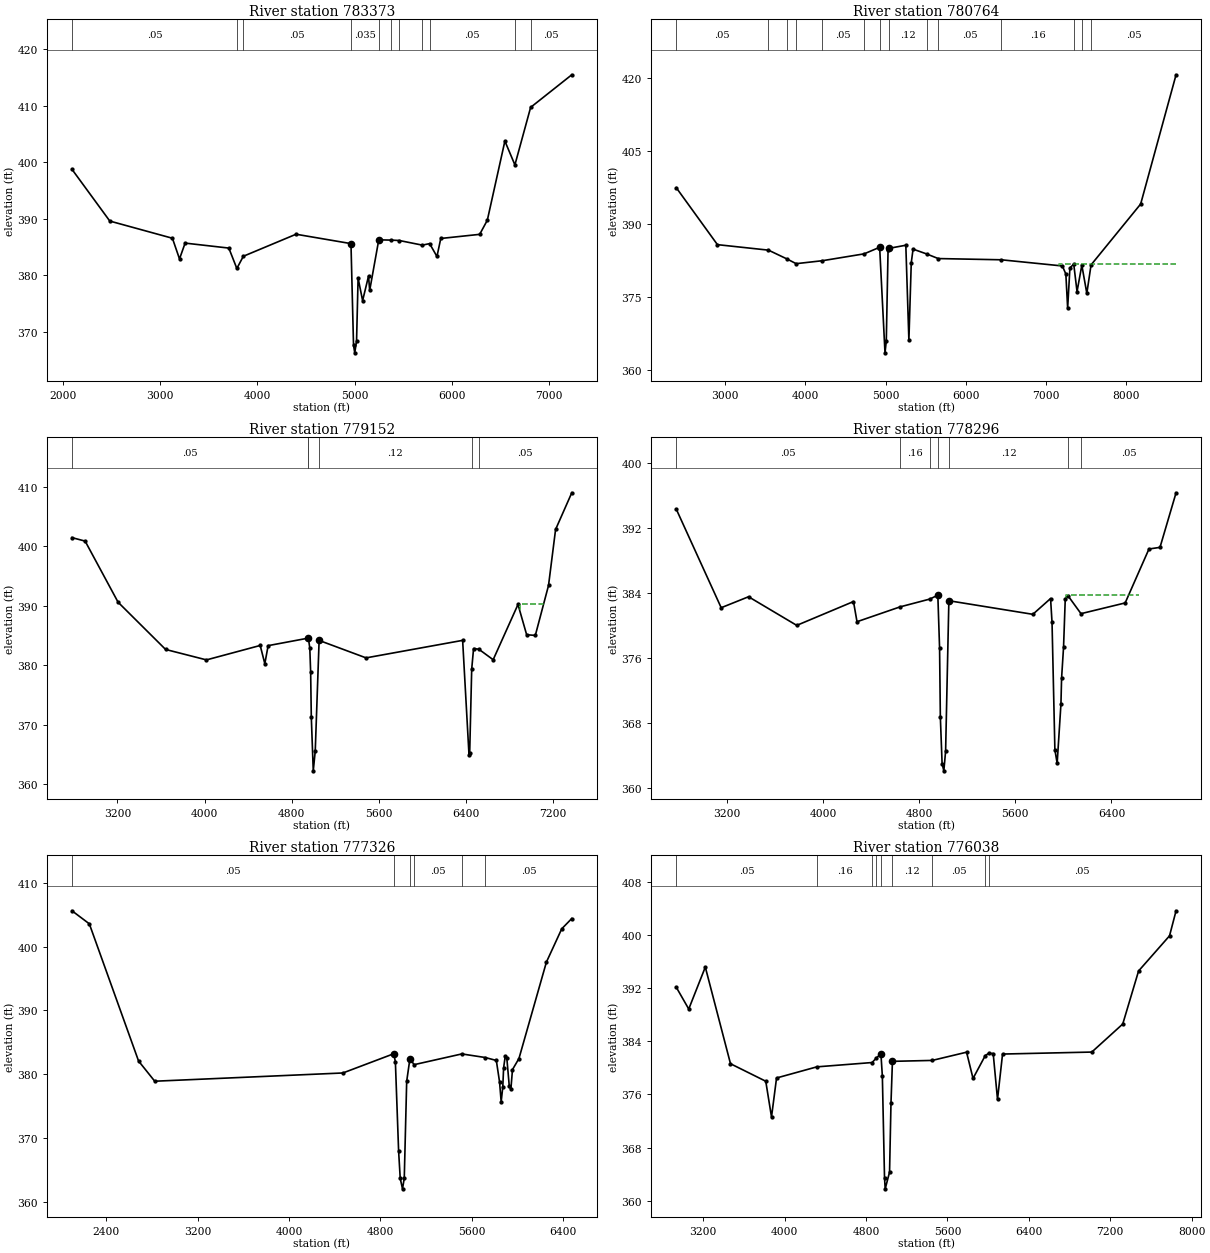
Type RM Length L Ch R = 1 ,783373  ,2609,2609,2609
BEGIN DESCRIPTION:
NAVASOTA RIVER 109
END DESCRIPTION:
XS GIS Cut Line= 5
      3501134.08     10543715.68      3499348.37     10542592.46
      3498949.07     10542540.38      3498740.73     10542566.42
      3496410.05     10543221.79
#Sta/Elev= 30
  2092.4  398.78  2481.8  389.62    3126  386.58    3199  382.92  3256.7  385.72
  3706.6  384.84    3789  381.23  3855.8  383.39  4398.2  387.29  4963.5  385.63
  4989.8  367.61  5002.5   366.3    5021  368.42  5036.8  379.53  5083.3  375.54
  5144.2  379.89    5156  377.34  5249.5   386.3    5380  386.25  5460.9  386.18
  5697.6  385.36  5772.6  385.63  5848.3  383.35  5887.6  386.54  6288.1  387.27
  6366.6  389.77  6547.3  403.78  6650.4  399.56  6812.2  409.74  7235.7  415.51
#Mann= 11 ,-1 , 0
  2092.4     .05       0    3789     .08       0  3855.8     .05       0
  4963.5    .035       0  5249.5     .05       0    5380     .08       0
  5460.9     .05       0  5697.6     .08       0  5772.6     .05       0
  6650.4     .16       0  6812.2     .05       0
Bank Sta=4963.5,5249.5
XS Rating Curve= 0 ,0
Exp/Cntr=0.3,0.1

Type RM Length L Ch R = 1 ,780764  ,1612,1612,1612
BEGIN DESCRIPTION:
NAVASOTA RIVER 111
END DESCRIPTION:
XS GIS Cut Line= 3
      3501469.94     10542214.88      3497993.34     10540404.96
      3497615.75     10538126.44
#Sta/Elev= 30
  2392.1  397.41  2905.3   385.7  3541.5  384.57  3776.9  382.72  3886.2  381.79
  4213.9   382.4  4733.8  383.81    4927  385.16  4993.7  363.46  5009.7  365.86
  5031.8  384.55    5039  384.93  5253.2  385.58  5291.4  366.04  5320.9  381.97
  5343.4  384.78  5510.9   383.8  5657.2  382.84  6442.1  382.59    7204  381.32
  7247.5  379.67  7270.1  372.65  7298.2  380.91  7345.8   381.7    7387  376.05
  7446.7  381.47    7509  375.69  7561.8  381.54  8179.9  394.05  8621.2  420.62
#Mann= 14 ,-1 , 0
  2392.1     .05       0  3541.5      .1       0  3776.9     .05       0
  3886.2     .16       0  4213.9     .05       0  4733.8     .12       0
    4927     .07       0    5039     .12       0  5510.9     .16       0
  5657.2     .05       0  6442.1     .16       0  7345.8     .05       0
  7446.7     .16       0  7561.8     .05       0
#XS Ineff= 2 , 0
       0                  7156.3       0  381.78
Permanent Ineff=
       F       F
Bank Sta=4927,5039
XS Rating Curve= 0 ,0
Exp/Cntr=0.3,0.1

Type RM Length L Ch R = 1 ,779152  ,856,856,856
BEGIN DESCRIPTION:
NAVASOTA RIVER 117
END DESCRIPTION:
XS GIS Cut Line= 3
      3501653.78      10542146.3      3500453.82     10540282.95
       3499052.8     10538372.01
#Sta/Elev= 30
  2783.7  401.48  2904.5  400.89  3206.9   390.6  3642.7  382.65  4017.7  380.89
  4510.8  383.32  4553.1  380.25  4583.5  383.29  4949.8  384.55  4952.5   384.6
  4965.9  382.86  4973.6  378.83  4979.6  371.27  4997.6  362.21  5015.8  365.56
  5051.3  384.17    5482  381.23  6368.1  384.18  6426.7  364.84  6432.9  365.28
  6451.3  379.34  6468.4   382.8  6516.5  382.69  6648.2  380.92    6876  390.22
  6955.4  385.13  7034.9  385.01  7156.1  393.42  7220.9  402.85  7369.5  409.03
#Mann= 6 ,-1 , 0
  2783.7     .05       0  4949.8     .12       0  4952.5     .07       0
  5051.3     .12       0  6451.3     .16       0  6516.5     .05       0
#XS Ineff= 2 ,-1
  6368.1  6890.6  384.18  6890.6  7126.8  390.27
Permanent Ineff=
       F       F
Bank Sta=4952.5,5051.3
XS Rating Curve= 0 ,0
Exp/Cntr=0.3,0.1

Type RM Length L Ch R = 1 ,778296  ,970,970,970
BEGIN DESCRIPTION:
NAVASOTA RIVER 245
END DESCRIPTION:
XS GIS Cut Line= 3
      3502201.39     10541484.25      3500604.16     10539322.79
       3500100.7     10537942.62
#Sta/Elev= 30
  2780.3  394.33    3154  382.21  3381.5  383.56  3782.4  380.04  4254.2  382.97
  4283.5  380.49  4640.7  382.31  4890.2  383.28  4955.7  383.76  4970.3  377.22
  4976.6  368.81  4991.2  363.05  5005.6  362.16  5020.4  364.58  5047.5  383.07
  5745.8   381.4  5893.3  383.34  5905.5   380.4  5929.2  364.75  5948.1  363.09
  5979.6  370.37  5984.9  373.55  6001.3  377.37  6015.5  383.31  6040.3  383.64
  6146.3  381.48  6513.7   382.8  6711.6  389.43  6803.3  389.63    6937  396.34
#Mann= 7 ,-1 , 0
  2780.3     .05       0  4640.7     .16       0  4890.2     .05       0
  4955.7     .07       0  5047.5     .12       0  6040.3     .16       0
  6146.3     .05       0
#XS Ineff= 2 ,-1
  5893.3  6022.6  383.34  6022.6  6630.6  383.73
Permanent Ineff=
       F       F
Bank Sta=4955.7,5047.5
XS Rating Curve= 0 ,0
Exp/Cntr=0.3,0.1

Type RM Length L Ch R = 1 ,777326  ,1288,1288,1288
BEGIN DESCRIPTION:
NAVASOTA RIVER 116
END DESCRIPTION:
XS GIS Cut Line= 3
      3503405.55     10540983.01      3501368.53     10538918.33
      3500343.65     10537856.03
#Sta/Elev= 30
  2099.6  405.59  2251.5  403.55  2682.8  382.08  2824.3  378.92  4471.9  380.21
  4917.3  383.22  4931.5  381.95  4959.8     368  4973.9  363.71  4993.9  362.08
  5009.3  363.75  5030.5  378.91  5058.8  382.44  5095.6  381.51  5513.3  383.19
  5717.9  382.63  5815.4  382.17  5843.7   378.8  5857.8  375.69    5872  378.04
  5879.2  381.02  5893.3   382.8  5907.5  382.51  5928.6  378.18  5942.7  377.66
  5956.9  380.74  6013.5  382.47    6254  397.56  6388.3  402.77  6476.1  404.38
#Mann= 6 ,-1 , 0
  2099.6     .05       0  4917.3     .07       0  5058.8     .05       0
  5095.6     .05       0  5513.3     .12       0  5717.9     .05       0
Bank Sta=4917.3,5058.8
XS Rating Curve= 0 ,0
Exp/Cntr=0.3,0.1

Type RM Length L Ch R = 1 ,776038  ,2814,2814,2814
BEGIN DESCRIPTION:
NAVASOTA RIVER 246
END DESCRIPTION:
XS GIS Cut Line= 2
      3504037.31     10540199.95      3500521.72     10536771.16
#Sta/Elev= 30
  2936.1  392.18  3058.8  388.89  3221.5  395.22    3469  380.64  3815.5     378
    3872  372.61  3921.5  378.49  4317.7  380.17  4860.1  380.82  4902.8  381.51
  4946.9  382.14  4961.1  378.78  4982.4  363.41  4989.1  361.77  5031.8  364.29
  5045.9  374.71  5060.1     381  5451.2  381.14  5788.5  382.38    5852  378.42
  5972.2  381.87  6005.4  382.21  6050.1  382.18  6092.5  375.26  6142.1   382.1
    7019   382.4    7323  386.63  7478.6  394.63  7782.6  399.93  7846.9  403.71
#Mann= 9 ,-1 , 0
  2936.1     .05       0  4317.7     .16       0  4860.1     .05       0
  4902.8     .12       0  4946.9     .07       0  5060.1     .12       0
  5451.2     .05       0  5972.2     .12       0  6005.4     .05       0
Bank Sta=4946.9,5060.1
XS Rating Curve= 0 ,0
Exp/Cntr=0.3,0.1

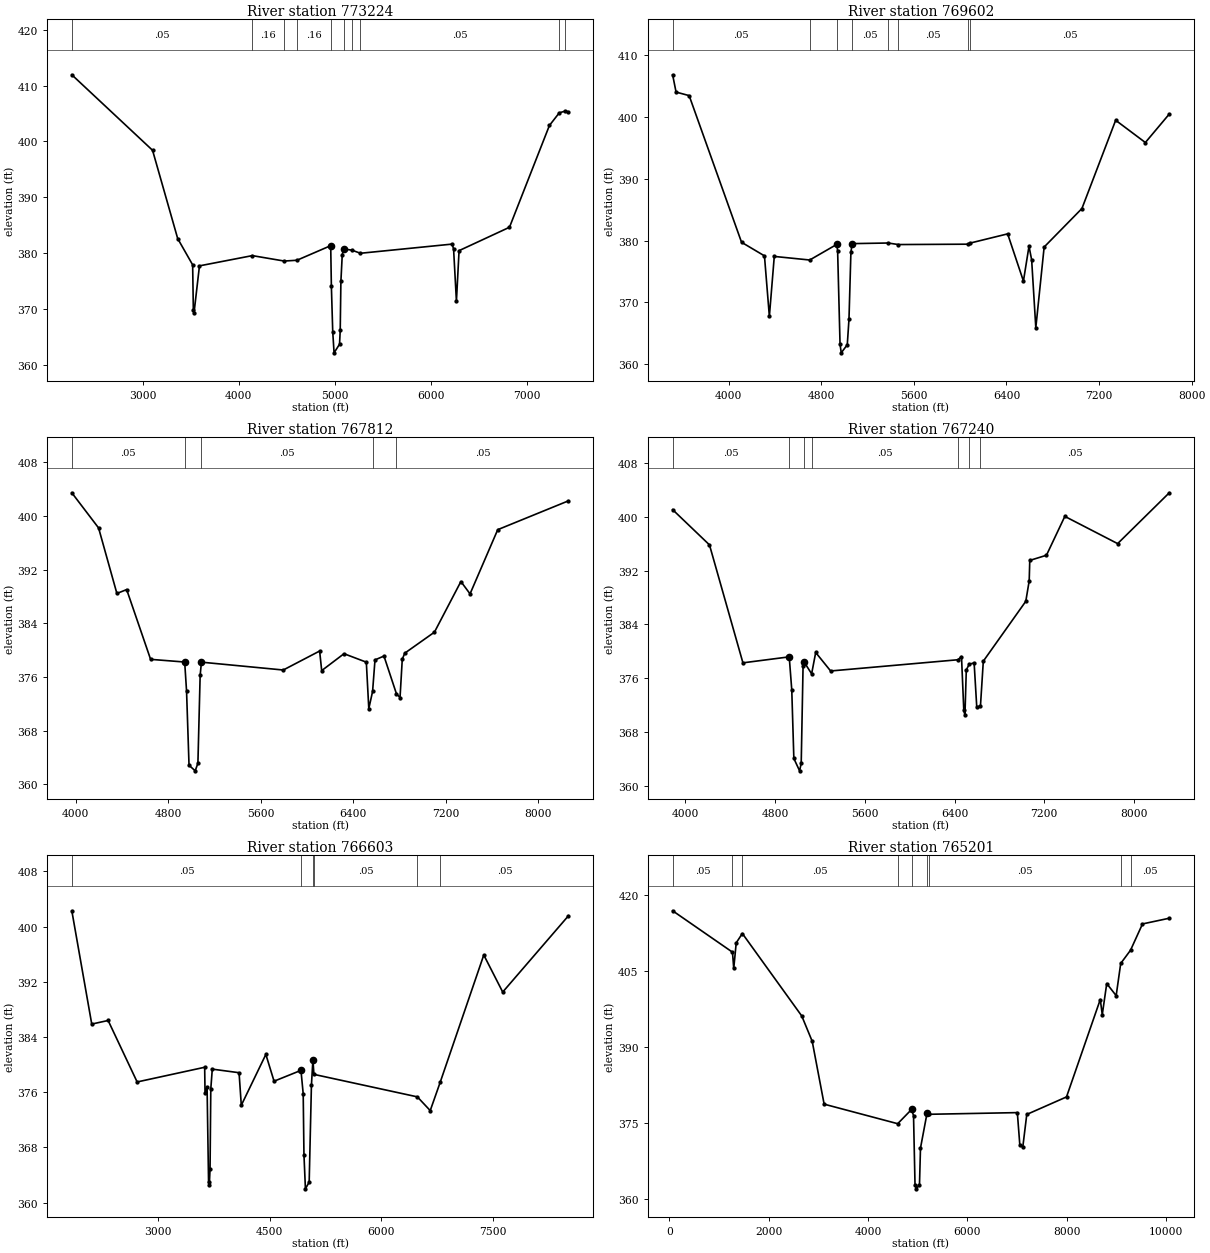
Type RM Length L Ch R = 1 ,773224  ,3622,3622,3622
BEGIN DESCRIPTION:
NAVASOTA RIVER 022
END DESCRIPTION:
XS GIS Cut Line= 3
      3505228.21     10539832.74      3503032.05     10537723.39
      3501305.84     10536491.62
#Sta/Elev= 30
  2262.5  411.92  3102.3  398.42  3363.9  382.63  3519.3  377.94  3526.5  369.92
  3533.4  369.31  3590.1  377.76    4140  379.59  4471.7  378.62  4603.7  378.76
  4955.2  381.37  4962.1  374.18  4976.3  365.99  4990.2  362.21    5047  363.75
  5054.2  366.24  5061.2  374.97  5075.3  379.75  5089.5  380.79  5177.3  380.56
  5264.1  380.01  6218.6  381.65  6233.3  380.77  6262.8  371.43  6290.3  380.48
  6814.7  384.66  7230.1  402.86  7332.7  405.12  7395.1  405.43  7428.2   405.3
#Mann= 10 ,-1 , 0
  2262.5     .05       0    4140     .16       0  4471.7     .05       0
  4603.7     .16       0  4955.2     .07       0  5089.5     .12       0
  5177.3     .07       0  5264.1     .05       0  7332.7     .08       0
  7395.1      .1       0
Bank Sta=4955.2,5089.5
XS Rating Curve= 0 ,0
Exp/Cntr=0.3,0.1

Type RM Length L Ch R = 1 ,769602  ,1790,1790,1790
BEGIN DESCRIPTION:
NAVASOTA RIVER 115
END DESCRIPTION:
XS GIS Cut Line= 4
      3505171.47     10538984.17       3504221.9      10538054.2
      3503961.48     10537171.39      3502070.82     10536400.54
#Sta/Elev= 30
  3515.4  406.84    3545  404.04  3658.1  403.47  4110.8  379.74  4308.8  377.54
  4351.2  367.75  4393.6  377.45  4699.8  376.87    4934   379.4    4941  378.32
  4961.9  363.23  4972.2  361.85  5024.4  363.16  5039.1  367.28  5055.7  378.09
  5066.1  379.52  5376.2  379.62  5466.5  379.37  6064.2  379.43  6086.2  379.61
    6410   381.1  6546.4  373.46  6594.5   379.1  6617.4   376.9  6653.4  365.91
  6725.4  378.97  7051.8   385.2  7343.3  399.48  7599.9  395.88  7806.7  400.49
#Mann= 8 ,-1 , 0
  3515.4     .05       0  4699.8     .16       0    4934     .07       0
  5066.1     .05       0  5376.2     .16       0  5466.5     .05       0
  6064.2     .16       0  6086.2     .05       0
Bank Sta=4934,5066.1
XS Rating Curve= 0 ,0
Exp/Cntr=0.3,0.1

Type RM Length L Ch R = 1 ,767812  ,572,572,572
BEGIN DESCRIPTION:
NAVASOTA RIVER 114
END DESCRIPTION:
XS GIS Cut Line= 2
      3506017.63     10537788.33      3502011.52     10536240.57
#Sta/Elev= 30
  3965.2  403.44  4196.7   398.2    4355  388.43  4439.5  389.01  4646.5  378.61
  4941.2  378.21  4957.4  373.88  4978.8  362.82  5032.2  361.99  5055.6  363.13
  5074.9  376.21    5086  378.19  5793.6  377.02  6108.2  379.85  6125.9  376.93
  6318.9  379.45  6511.9  378.19  6533.3  371.26    6566  373.82  6586.9  378.53
  6664.4   379.1  6772.6  373.46  6803.4  372.92  6822.7  378.62  6844.2  379.53
  7100.8  382.66  7329.7  390.21  7408.8  388.37  7648.2  397.94  8259.9  402.24
#Mann= 5 ,-1 , 0
  3965.2     .05       0  4941.2    .035       0    5086     .05       0
    6566     .12       0  6772.6     .05       0
Bank Sta=4941.2,5086
XS Rating Curve= 0 ,0
Exp/Cntr=0.3,0.1

Type RM Length L Ch R = 1 ,767240  ,637,637,637
BEGIN DESCRIPTION:
NAVASOTA RIVER 113
END DESCRIPTION:
XS GIS Cut Line= 3
      3506279.37      10537136.1      3505201.39     10536863.56
      3501962.13     10536164.21
#Sta/Elev= 30
  3888.1  401.07  4216.4  395.83  4514.5  378.29  4927.1  379.18  4949.7  374.27
  4968.3  364.07  5019.5  362.23  5033.9  363.36  5050.4   377.8  5060.7  378.39
  5126.7  376.66    5163  379.83    5296  377.08  6430.7  378.75  6462.2  379.23
  6482.7  371.23  6492.9  370.52    6505  377.22    6531   378.1  6574.8  378.27
  6598.4  371.66  6631.3  371.91  6656.6  378.54  7035.1  387.44  7065.5  390.48
  7070.6  393.52  7219.3  394.29    7383  400.07  7853.6  396.02  8313.9  403.58
#Mann= 7 ,-1 , 0
  3888.1     .05       0  4927.1    .035       0  5060.7     .16       0
  5126.7     .05       0  6430.7     .16       0    6531     .12       0
  6631.3     .05       0
Bank Sta=4927.1,5060.7
XS Rating Curve= 0 ,0
Exp/Cntr=0.3,0.1

Type RM Length L Ch R = 1 ,766603  ,1402,1402,1402
BEGIN DESCRIPTION:
NAVASOTA RIVER 247
END DESCRIPTION:
XS GIS Cut Line= 3
      3508550.12     10536205.82      3505919.91     10536309.98
      3501892.09     10535901.99
#Sta/Elev= 30
  1837.8   402.3    2106  385.88  2326.2   386.4  2716.5  377.49  3624.9  379.62
  3629.9  375.82  3657.2  376.79  3677.3  362.93  3687.3  362.54  3697.3  364.89
  3707.3  376.48  3727.3  379.35  4087.6  378.83  4117.6  374.11  4447.9  381.48
  4558.3   377.6  4920.2  379.17  4950.3  375.78  4960.4  366.96  4980.2     362
  5030.7  362.98  5060.9     377    5081  380.73  5094.4  378.59    6486  375.33
    6659  373.34    6795  377.51  7379.3  395.89    7634  390.52  8518.5  401.58
#Mann= 6 ,-1 , 0
  1837.8     .05       0  4920.2     .07       0    5081     .16       0
  5094.4     .05       0    6486     .16       0    6795     .05       0
#XS Ineff= 2 , 0
       0  4447.9  381.48               0
Permanent Ineff=
       F       F
Bank Sta=4920.2,5081
XS Rating Curve= 0 ,0
Exp/Cntr=0.3,0.1

Type RM Length L Ch R = 1 ,765201  ,197,197,197
BEGIN DESCRIPTION:
NAVASOTA RIVER 298
END DESCRIPTION:
XS GIS Cut Line= 6
      3511002.43     10535023.33      3510992.98     10535023.45
        3507000.     10535072.81      3506978.83     10535073.07
      3506093.47     10535084.02      3501002.59     10535146.95
#Sta/Elev= 30
      64  416.85  1269.1  408.67  1294.4  405.46  1344.4  410.52  1467.8  412.36
  2664.5  396.06  2874.5  391.06  3114.6  378.64  4595.7  374.78  4874.7  377.59
  4914.7  376.39  4944.7  362.65  4971.3  361.91  5034.7  362.76  5054.7  369.96
  5187.7  376.91  5227.6  376.64  7004.9  376.97  7054.9  370.58  7114.9  370.18
  7194.9  376.61  7994.9  380.07    8675  399.32    8715  396.33    8805  402.47
    8995  400.08  9086.3  406.44  9284.2  409.06    9525  414.25 10064.6  415.38
#Mann= 9 ,-1 , 0
      64     .05       0  1269.1     .16       0  1467.8     .05       0
  4595.7     .16       0  4874.7     .04       0  5187.7     .16       0
  5227.6     .05       0  9086.3      .1       0  9284.2     .05       0
Bank Sta=4874.7,5187.7
XS Rating Curve= 0 ,0
Exp/Cntr=0.3,0.1

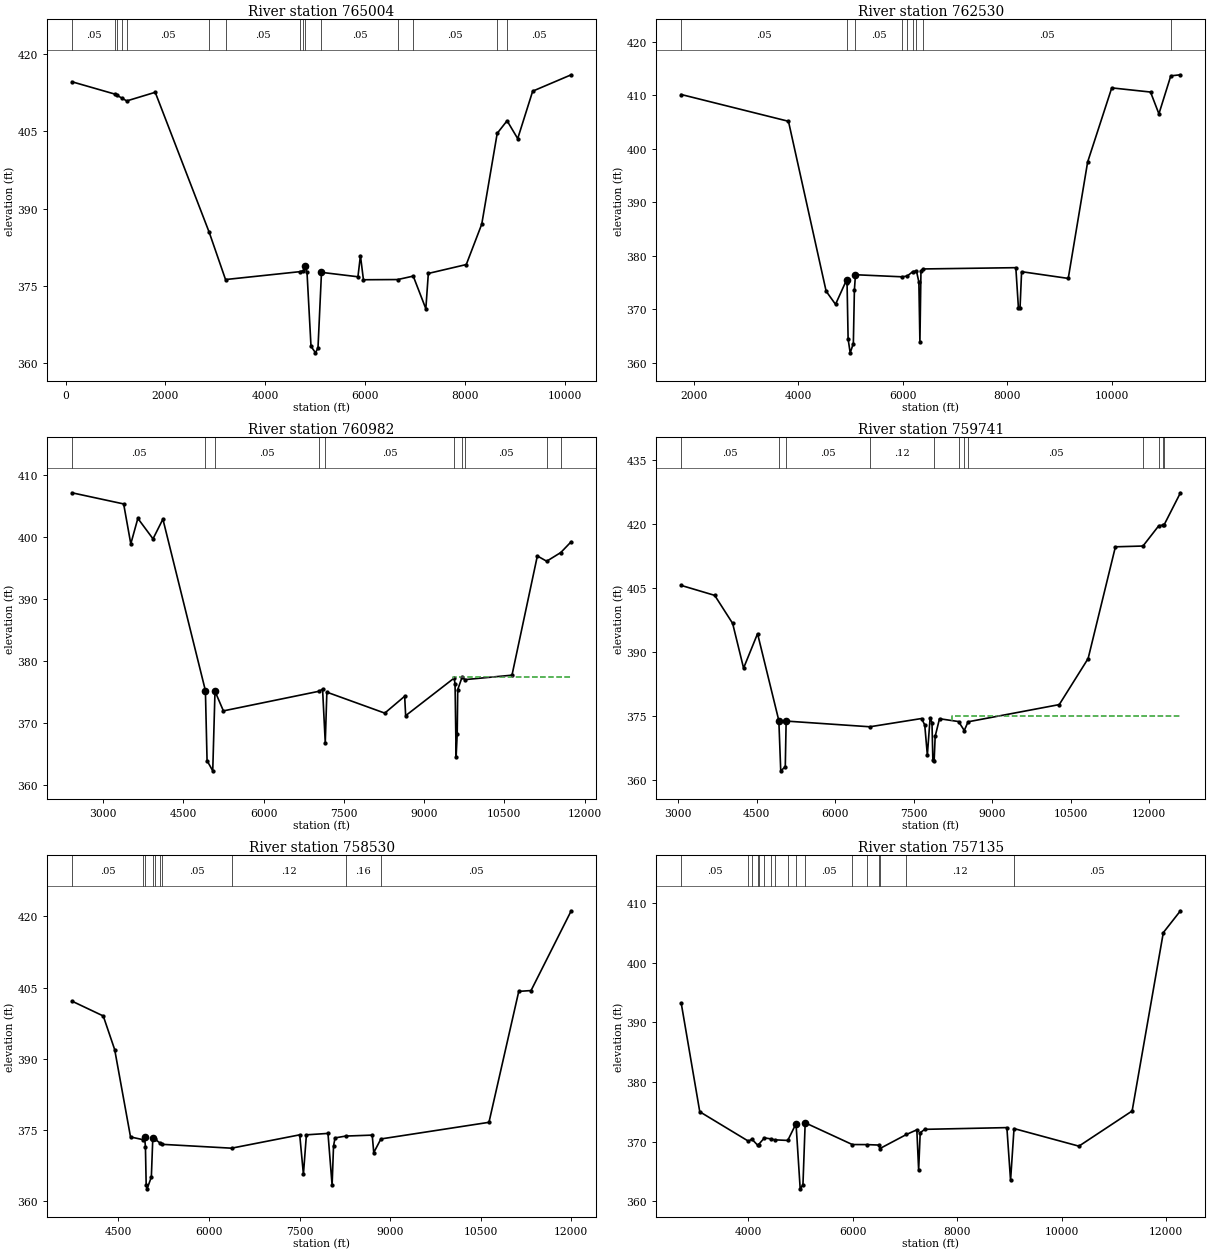
Type RM Length L Ch R = 1 ,765004  ,2474,2474,2474
BEGIN DESCRIPTION:
NAVASOTA RIVER 297
END DESCRIPTION:
XS GIS Cut Line= 6
      3511000.22     10534843.35      3510990.75     10534843.46
      3506997.77     10534892.82      3506976.61     10534893.09
      3506091.25     10534904.03      3501000.28     10534966.96
#Sta/Elev= 30
     129  414.68   991.9  412.27  1028.7  412.06  1127.6  411.51  1226.6  410.95
  1797.2  412.63  2879.5  385.34  3205.4  376.17  4689.6   377.7  4766.8  377.89
  4787.5  378.85  4837.5  377.56  4917.5  363.18  5007.2   361.9  5057.5  362.87
  5127.5  377.57  5857.6  376.71  5907.6  380.83  5967.6  376.13  6653.8  376.17
  6965.2  376.84  7217.7  370.49  7267.7  377.36  8027.7  379.09  8337.7  386.96
  8647.3  404.64  8845.1  407.09  9057.8  403.61  9357.8  412.85 10129.7  416.04
#Mann= 15 ,-1 , 0
     129     .05       0   991.9     .08       0  1028.7     .05       0
  1127.6     .08       0  1226.6     .05       0  2879.5     .08       0
  3205.4     .05       0  4689.6     .16       0  4766.8     .08       0
  4787.5     .07       0  5127.5     .05       0  6653.8     .08       0
  6965.2     .05       0  8647.3     .08       0  8845.1     .05       0
Bank Sta=4787.5,5127.5
XS Rating Curve= 0 ,0
Exp/Cntr=0.3,0.1

Type RM Length L Ch R = 1 ,762530  ,1548,1548,1548
BEGIN DESCRIPTION:
NAVASOTA RIVER 118
END DESCRIPTION:
XS GIS Cut Line= 3
      3510602.52     10533696.15      3507365.72     10533784.34
       3501071.2     10534188.78
#Sta/Elev= 30
    1762  410.13  3813.2  405.12  4533.4  373.34  4712.9  370.88  4923.6  375.44
  4933.6   374.8  4953.6   364.4  4993.4  361.81  5053.7  363.55  5073.8  373.56
  5093.8  376.42  5984.9  376.03  6084.2  376.18  6189.5     377  6260.1  377.14
  6306.3  375.05  6326.3   363.8  6346.4  377.14  6382.2   377.5  8160.1  377.74
  8210.2  370.15  8240.3  370.14  8270.3  376.99  9162.2  375.73  9532.9   397.5
  9993.9  411.37 10735.4  410.59 10895.7  406.51 11122.9  413.62 11307.5  413.82
#Mann= 9 ,-1 , 0
    1762     .05       0  4923.6    .035       0  5093.8     .05       0
  5984.9     .12       0  6084.2     .16       0  6189.5     .12       0
  6260.1     .16       0  6382.2     .05       0 11122.9      .1       0
Bank Sta=4923.6,5093.8
XS Rating Curve= 0 ,0
Exp/Cntr=0.3,0.1

Type RM Length L Ch R = 1 ,760982  ,1241,1241,1241
BEGIN DESCRIPTION:
NAVASOTA RIVER 119
END DESCRIPTION:
XS GIS Cut Line= 4
      3509963.01     10533156.35      3507527.18     10532288.25
      3504213.21      10531251.5      3500949.27     10530947.67
#Sta/Elev= 30
  2414.1  407.07  3381.1  405.27  3514.6  398.83  3646.5  402.94  3930.1  399.64
    4115  402.82  4909.8  375.16  4940.8  363.86    5047  362.22  5089.1  375.05
  5246.3  371.89  7036.7  375.06  7100.9   375.4  7151.1  366.75  7180.9  374.91
    8264  371.53  8635.9  374.25  8654.2  371.12  9562.3  377.19  9578.2  376.18
  9598.3  364.49  9618.4  368.21  9628.4  375.33  9711.2  377.37  9760.2  376.93
 10642.8  377.65   11117  396.88 11291.6  396.03 11555.1  397.43 11750.4  399.18
#Mann= 10 ,-1 , 0
  2414.1     .05       0  4909.8    .035       0  5089.1     .05       0
  7036.7     .16       0  7151.1     .05       0  9562.3     .12       0
  9711.2     .16       0  9760.2     .05       0 11291.6     .16       0
 11555.1     .05       0
#XS Ineff= 2 , 0
       0                  9548.1       0  377.37
Permanent Ineff=
       F       F
Bank Sta=4909.8,5089.1
XS Rating Curve= 0 ,0
Exp/Cntr=0.3,0.1

Type RM Length L Ch R = 1 ,759741  ,1211,1211,1211
BEGIN DESCRIPTION:
NAVASOTA RIVER 120
END DESCRIPTION:
XS GIS Cut Line= 4
      3509493.58     10532205.29       3507852.7     10531167.15
      3503707.65     10529019.03      3500855.32     10528338.91
#Sta/Elev= 30
  3058.3  405.62    3699  403.28  4041.7   396.7    4251  386.19  4518.1  394.29
    4925  373.85  4961.2  362.06    5048     363  5064.5  373.75  6664.9  372.41
  7652.9  374.35  7713.6  372.83  7763.5  365.74  7816.4  374.54    7852   373.4
  7868.5  364.62  7893.4  364.46  7912.8  370.17  7995.7   374.3  8359.8  373.64
  8468.9  371.53  8542.1  373.58 10284.2  377.62   10836  388.43 11357.8  414.69
 11884.7  414.87 12186.8  419.64 12266.6  419.78 12287.5  419.82 12600.9  427.38
#Mann= 12 ,-1 , 0
  3058.3     .05       0    4925    .033       0  5064.5     .05       0
  6664.9     .12       0  7893.4     .16       0  8359.8     .05       0
  8468.9     .16       0  8542.1     .05       0 11884.7      .1       0
 12186.8     .05       0 12266.6     .08       0 12287.5     .05       0
#XS Ineff= 2 , 0
       0                  8239.1       0  375.03
Permanent Ineff=
       F       F
Bank Sta=4925,5064.5
XS Rating Curve= 0 ,0
Exp/Cntr=0.3,0.1

Type RM Length L Ch R = 1 ,758530  ,1395,1395,1395
BEGIN DESCRIPTION:
NAVASOTA RIVER 121
END DESCRIPTION:
XS GIS Cut Line= 3
      3509497.92     10530799.04       3508417.8      10530133.3
      3501841.67     10527739.14
#Sta/Elev= 30
  3731.2  402.13  4249.7     399    4439  391.89  4701.3  373.46  4915.2  372.87
  4933.4  373.43    4948  371.42  4960.5  363.29  4975.7  362.51    5046     365
  5069.9  373.15  5112.8  372.94  5185.3  372.22  5216.5  371.91  6373.7  371.09
  7502.9  373.91    7564  365.57  7613.4  373.91  7970.8  374.21  8039.1  363.27
  8062.6  371.53  8087.8  373.26  8265.9  373.65  8703.4  373.85  8728.6  370.16
  8847.2  373.04 10636.4  376.55 11129.7  404.19 11333.1  404.36 11998.4   421.2
#Mann= 10 ,-1 , 0
  3731.2     .05       0  4915.2     .07       0  4933.4     .07       0
  5069.9     .05       0  5112.8     .07       0  5185.3     .12       0
  5216.5     .05       0  6373.7     .12       0  8265.9     .16       0
  8847.2     .05       0
#XS Ineff= 2 , 0
       0                  7970.8       0  374.21
Permanent Ineff=
       F       F
Bank Sta=4933.4,5069.9
XS Rating Curve= 0 ,0
Exp/Cntr=0.3,0.1

Type RM Length L Ch R = 1 ,757135  ,1842,1842,1842
BEGIN DESCRIPTION:
NAVASOTA RIVER 122
END DESCRIPTION:
XS GIS Cut Line= 4
      3510808.79     10530073.73      3508833.17     10528921.06
      3505834.82     10527131.01      3502097.82     10526545.07
#Sta/Elev= 30
  2712.7  393.28  3068.8  375.02  4001.2  370.08  4066.2  370.43  4175.4  369.43
  4194.5  369.51  4306.4  370.64  4442.2  370.45  4500.5  370.31    4754  370.21
    4912  373.01  4991.9  362.09  5044.8  362.76  5087.6  373.17  5990.2  369.52
  6268.2  369.51  6509.3  369.43    6515  368.83  7027.4  371.21  7225.7  371.99
  7260.7  365.24  7290.4   371.5  7377.1  372.07  8950.3  372.36  9021.1   363.5
  9087.2   372.2 10329.9  369.25 11349.2  375.15 11946.6  405.07 12274.7  408.73
#Mann= 17 ,-1 , 0
  2712.7     .05       0  4001.2     .07       0  4066.2     .05       0
  4175.4     .07       0  4194.5     .05       0  4306.4      .1       0
  4442.2     .05       0  4500.5      .1       0    4754     .05       0
    4912    .035       0  5087.6     .05       0  5990.2     .12       0
  6268.2     .05       0  6509.3     .12       0    6515     .05       0
  7027.4     .12       0  9087.2     .05       0
#XS Ineff= 2 , 0
       0                  8950.3       0  372.36
Permanent Ineff=
       F       F
Bank Sta=4912,5087.6
XS Rating Curve= 0 ,0
Exp/Cntr=0.3,0.1

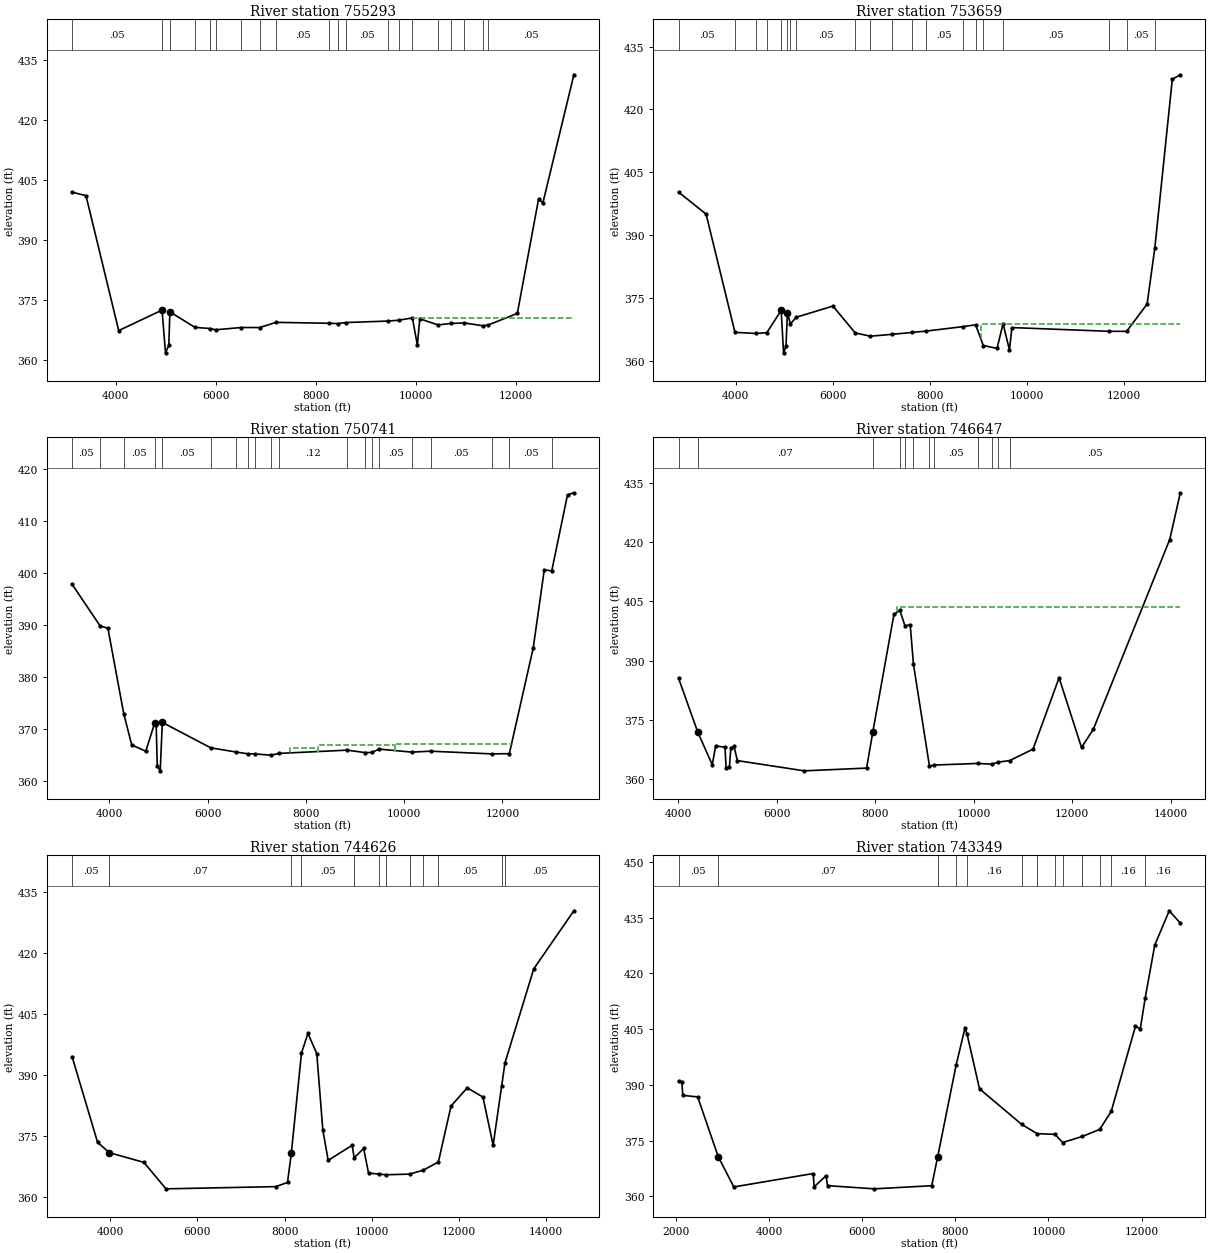
Type RM Length L Ch R = 1 ,755293  ,1634,1634,1634
BEGIN DESCRIPTION:
NAVASOTA RIVER 123
END DESCRIPTION:
XS GIS Cut Line= 3
      3511693.22     10530003.03      3510490.72      10528569.5
      3504419.78     10523129.77
#Sta/Elev= 30
  3128.9  401.98  3407.1   401.1  4060.2  367.33  4926.6  372.46  4995.1  361.76
  5061.4  363.69  5082.3  372.02  5584.3  368.13    5892  367.84    5994  367.53
  6507.2   368.1  6875.1  368.09  7205.1  369.39  8266.6  369.16  8436.2  369.09
  8609.2  369.35  9429.8  369.71  9653.5  369.92  9926.2  370.51 10025.4  363.72
 10074.8  370.28 10435.8  368.75 10692.2  369.11 10961.9  369.25 11330.7  368.54
 11442.3  368.73 12022.3  371.63 12447.7  400.31 12532.1  399.24 13151.5  431.36
#Mann= 20 ,-1 , 0
  3128.9     .05       0  4926.6    .033       0  5082.3     .05       0
  5584.3     .05       0    5892     .12       0    5994     .05       0
  6507.2     .05       0  6875.1     .12       0  7205.1     .05       0
  8266.6     .05       0  8436.2     .12       0  8609.2     .05       0
  9429.8     .12       0  9653.5     .12       0  9926.2     .05       0
 10435.8     .05       0 10692.2     .07       0 10961.9     .12       0
 11330.7     .07       0 11442.3     .05       0
#XS Ineff= 2 , 0
       0                    9926       0  370.51
Permanent Ineff=
       F       F
Bank Sta=4926.6,5082.3
XS Rating Curve= 0 ,0
Exp/Cntr=0.3,0.1

Type RM Length L Ch R = 1 ,753659  ,2918,2918,2918
BEGIN DESCRIPTION:
NAVASOTA RIVER 126
END DESCRIPTION:
XS GIS Cut Line= 3
      3513116.38     10528573.13      3511394.37     10527241.37
      3505076.55       10522074.
#Sta/Elev= 30
  2823.1  400.28  3390.3  395.04  3985.7  366.81  4418.2  366.54  4642.2  366.73
  4937.8  372.04  4987.4  361.92  5037.1  363.45  5065.9  371.48  5127.3  368.83
    5251  370.42  6003.3  373.08    6463  366.68  6774.5  365.89  7222.1  366.34
  7643.1   366.8  7914.5   367.1    8675  368.16  8943.9  368.61  9102.3  363.67
  9385.8  362.98  9508.9  368.85  9641.3  362.65  9692.3  367.95 11684.8  367.06
 12055.9  367.05 12477.5  373.56 12637.3  387.02 12996.5  427.23 13161.9  428.28
#Mann= 20 ,-1 , 0
  2823.1     .05       0  3985.7     .07       0  4418.2     .12       0
  4642.2     .05       0  4937.8     .07       0  5065.9     .05       0
  5127.3     .07       0    5251     .05       0    6463     .12       0
  6774.5     .07       0  7222.1     .07       0  7643.1     .12       0
  7914.5     .05       0    8675     .12       0  8943.9     .07       0
  9102.3     .12       0  9508.9     .05       0 11684.8     .05       0
 12055.9     .05       0 12637.3     .05       0
#XS Ineff= 2 , 0
       0                    9052       0  368.77
Permanent Ineff=
       F       F
Bank Sta=4937.8,5065.9
XS Rating Curve= 0 ,0
Exp/Cntr=0.3,0.1

Type RM Length L Ch R = 1 ,750741  ,4094,4094,4094
BEGIN DESCRIPTION:
NAVASOTA RIVER 127
END DESCRIPTION:
XS GIS Cut Line= 3
      3513719.98     10527406.07      3513132.46     10525746.92
      3505907.19      10521359.6
#Sta/Elev= 30
  3239.9   397.9  3809.1  389.91  3969.4  389.42  4291.5  373.02    4454     367
  4740.4  365.79  4920.7  371.22  4951.7  370.92  4973.8  362.97  5034.1  362.02
    5077  371.33  6063.9  366.44  6582.2  365.63  6812.3   365.3  6962.9  365.27
    7291  365.03  7450.8  365.37  8839.7     366  9199.4  365.53  9343.7  365.55
  9486.5   366.2 10156.7  365.62 10536.8   365.8 11778.8  365.28 12139.7  365.32
 12626.3  385.66 12850.6  400.66 13003.1  400.48 13324.1  415.11   13453  415.49
#Mann= 20 ,-1 , 0
  3239.9     .05       0  3809.1     .16       0  4291.5     .05       0
  4920.7     .03       0    5077     .05       0  6063.9     .07       0
  6582.2     .07       0  6812.3     .07       0  6962.9     .12       0
    7291     .07       0  7450.8     .12       0  8839.7     .05       0
  9199.4     .05       0  9343.7     .12       0  9486.5     .05       0
 10156.7     .07       0 10536.8     .05       0 11778.8     .07       0
 12139.7     .05       0 13003.1     .05       0
#XS Ineff= 3 ,-1
  7676.2  8236.3  366.32  8236.3    9816  366.98    9816 12218.8  367.13
Permanent Ineff=
       F       F       F
Bank Sta=4920.7,5077
XS Rating Curve= 0 ,0
Exp/Cntr=0.3,0.1

Type RM Length L Ch R = 1 ,746647  ,2021,2021,2021
BEGIN DESCRIPTION:
NAVASOTA RIVER 128
END DESCRIPTION:
XS GIS Cut Line= 4
      3515050.16     10523322.76      3514146.72      10522906.8
      3510971.97     10521278.58      3505388.67     10520591.08
#Sta/Elev= 30
  4005.4  385.56 4397.51  371.83  4690.4  363.62  4759.3  368.44  4948.5  368.03
  4971.5  362.86  5038.7   363.1  5066.5  367.78  5133.1  368.25  5199.7  364.67
  6558.7  362.08  7823.8  362.78 7948.78  371.85  8378.7   401.7  8498.7  402.73
    8604  398.78  8708.9  399.12  8774.8  389.09  9099.7  363.29  9198.9  363.55
 10078.6  363.95 10366.5  363.77 10499.3   364.3 10726.5  364.67 11202.4  367.57
 11731.5  385.64   12187     368 12425.6  372.56 13978.4  420.67 14193.4  432.51
#Mann= 12 ,-1 , 0
  4005.4     .05       0 4397.51     .07       0 7948.78     .05       0
  8498.7     .08       0    8604     .05       0  8774.8     .16       0
  9099.7     .12       0  9198.9     .05       0 10078.6     .12       0
 10366.5     .05       0 10499.3     .12       0 10726.5     .05       0
#XS Ineff= 2 , 0
       0                  8445.2       0  403.46
Permanent Ineff=
       F       F
Bank Sta=4397.51,7948.78
XS Rating Curve= 0 ,0
Exp/Cntr=0.3,0.1

Type RM Length L Ch R = 1 ,744626  ,1277,1277,1277
BEGIN DESCRIPTION:
NAVASOTA RIVER 125
END DESCRIPTION:
XS GIS Cut Line= 4
       3516307.4      10522282.8      3514675.28     10521365.78
      3511430.31     10519716.08       3505515.4     10518737.21
#Sta/Elev= 30
  3127.9  394.54  3712.7   373.5 3982.06  370.95  4776.8  368.56  5281.4  362.07
  7795.9  362.61  8068.5  363.63 8157.71  370.95  8388.6  395.39  8537.3  400.24
  8739.8  395.28  8879.2  376.47  9001.3  369.07  9550.6  372.75  9598.2   369.7
  9814.2  371.99  9926.9  365.94 10170.9  365.69 10329.5  365.53 10867.9  365.68
   11182  366.65 11528.9  368.67 11818.9  382.41 12190.1  386.88 12550.9  384.59
 12784.1  372.78   12978  387.21 13055.5  392.99 13715.9  416.09 14635.6  430.35
#Mann= 12 ,-1 , 0
  3127.9     .05       0 3982.06     .07       0 8157.71     .16       0
  8388.6     .05       0  9598.2     .16       0 10170.9     .12       0
 10329.5     .12       0 10867.9     .16       0   11182     .05       0
 11528.9     .05       0   12978     .12       0 13055.5     .05       0
#XS Ineff= 2 , 0
       0                  8537.3       0  400.24
Permanent Ineff=
       F       F
Bank Sta=3982.06,8157.71
XS Rating Curve= 0 ,0
Exp/Cntr=0.3,0.1

Type RM Length L Ch R = 1 ,743349  ,3584,3584,3584
BEGIN DESCRIPTION:
NAVASOTA RIVER 140
END DESCRIPTION:
XS GIS Cut Line= 3
      3517579.59     10521879.27      3511867.81     10518858.44
      3510080.03     10514935.74
#Sta/Elev= 30
  2058.1  390.94  2128.3  390.79  2150.3  387.21  2469.1  386.79 2908.95  370.75
  3244.4  362.57  4948.4  366.18  4970.5   362.6  5222.7  365.58  5256.7  362.92
  6263.2  362.06  7493.8   362.9  7620.2  370.63  8017.1  395.35  8209.2   405.4
  8250.7  403.75  8519.5  388.96  9426.6  379.38    9756  376.91 10138.7  376.72
   10305  374.52 10724.5  376.15 11099.5  378.04 11347.1  382.89 11867.6  405.81
 11970.8  405.08 12077.5   413.5 12281.4  427.63   12592  436.87 12830.4  433.57
#Mann= 13 ,-1 , 0
  2058.1     .05       0 2908.95     .07       0  7620.2     .16       0
  8017.1     .05       0  8250.7     .16       0  9426.6     .05       0
    9756     .05       0 10138.7     .05       0   10305      .1       0
 10724.5     .16       0 11099.5     .05       0 11347.1     .16       0
 12077.5     .16       0
#XS Ineff= 2 , 0
       0                  8209.2       0   405.4
Permanent Ineff=
       F       F
Bank Sta=2908.95,7620.2
XS Rating Curve= 0 ,0
Exp/Cntr=0.3,0.1