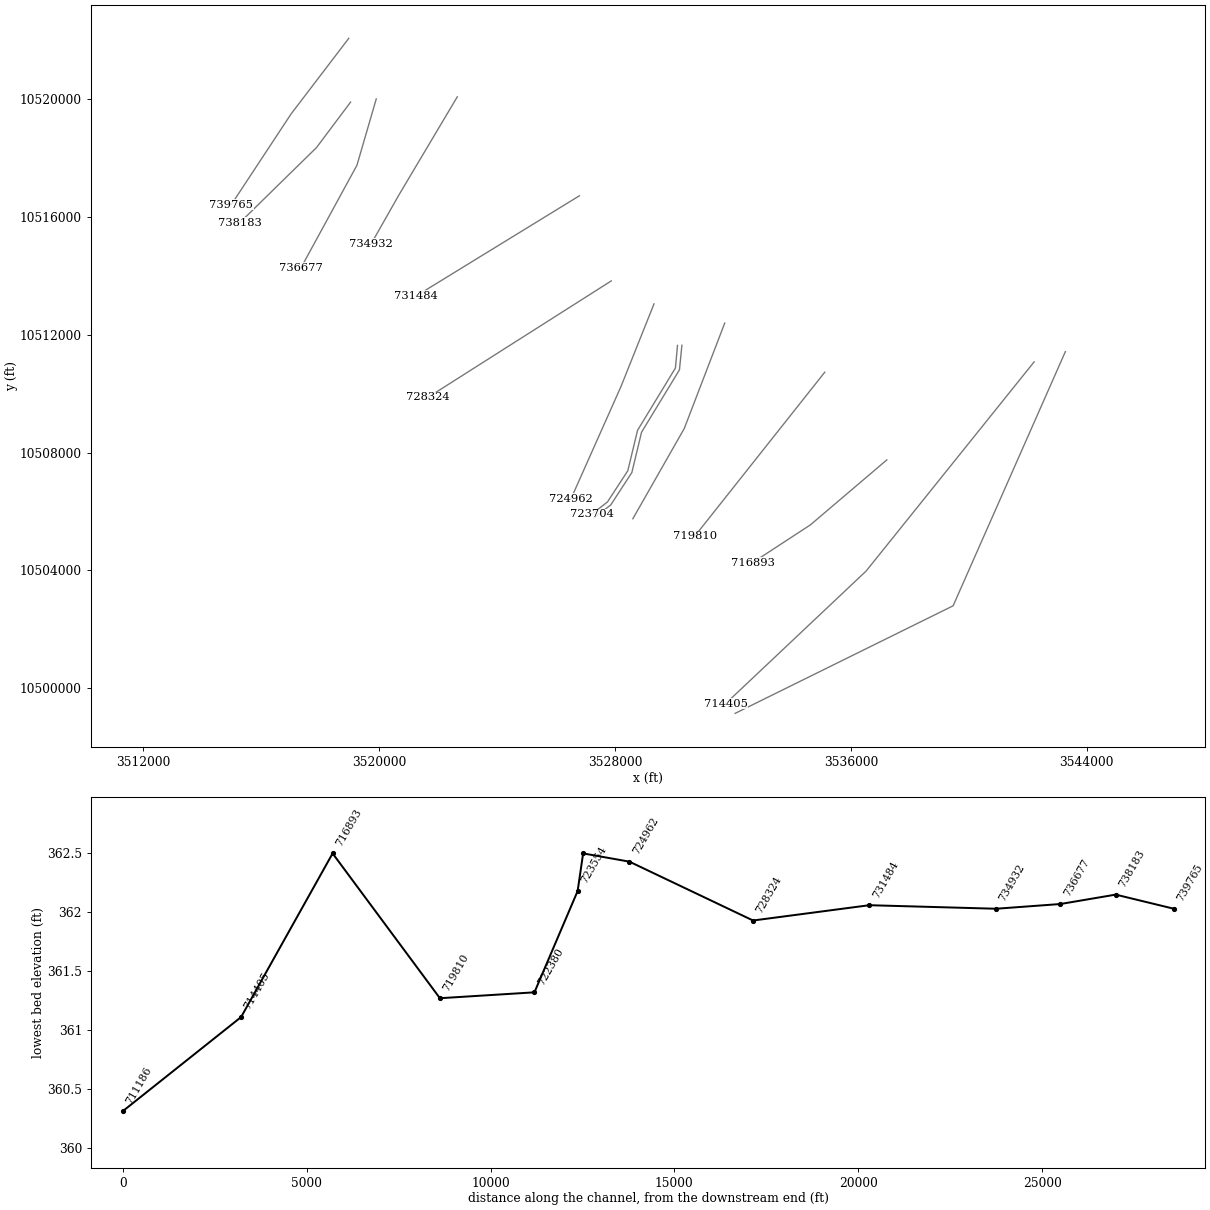
HEC-RAS study NAVASOTA RIVER.prj: NAVASOTA RIVER Base Level Engineering

--- NAVASOTA RIVER.g01 (geometry) --- (continued)

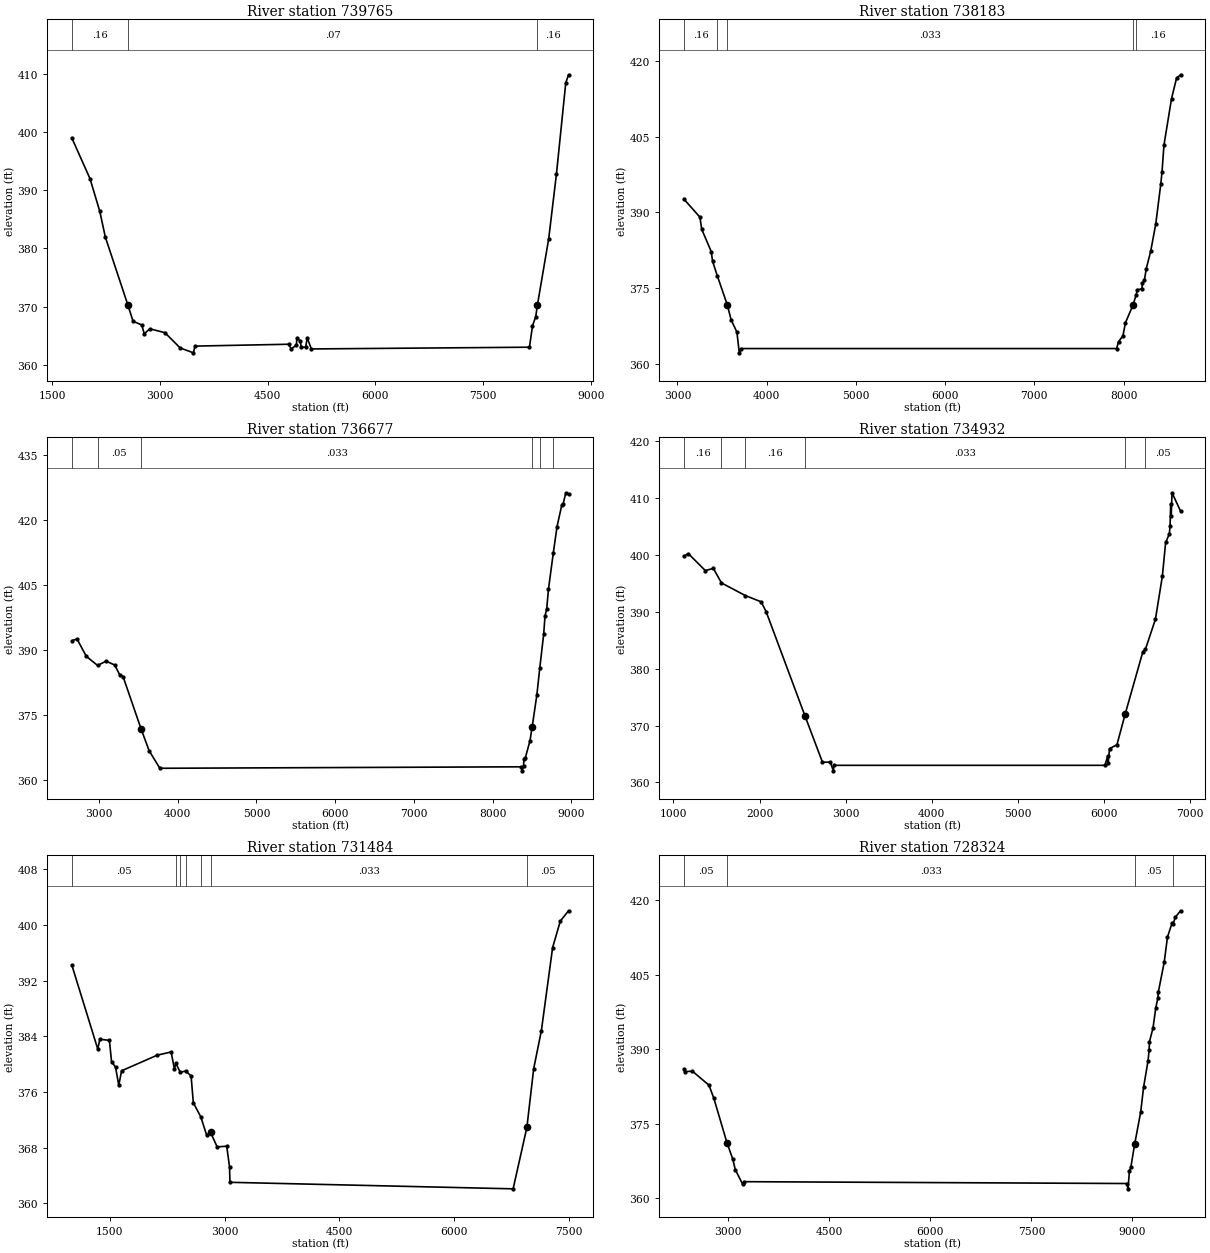
Type RM Length L Ch R = 1 ,739765  ,1582,1582,1582
BEGIN DESCRIPTION:
NAVASOTA RIVER 124
END DESCRIPTION:
XS GIS Cut Line= 3
      3518965.96     10522063.11      3517007.62     10519493.73
      3514977.94     10516411.02
#Sta/Elev= 30
  1769.4  399.02  2022.7  392.01  2159.1  386.39  2236.5  381.95  2550.8  370.25
  2622.6  367.47  2743.3  366.83  2778.6  365.32  2857.6  366.16  3065.4  365.51
  3279.5  362.87  3464.3  362.03  3485.3  363.19  4790.8  363.51  4826.6   362.7
  4898.8  363.37  4905.1  364.51    4955  364.08  4963.2     363  5026.5     363
    5050  364.59  5107.2   362.7  8146.1     363  8188.3  366.66  8233.5  368.26
  8257.4   370.3  8414.2  381.67  8522.5  392.86  8652.1  408.52  8690.9  409.89
#Mann= 3 , 0 , 0
  1769.4     .16       0  2550.8     .07       0  8257.4     .16       0
#XS Ineff= 2 , 0
       0  3485.3  363.19               0
Permanent Ineff=
       F       F
Bank Sta=2550.8,8257.4
XS Rating Curve= 0 ,0
Exp/Cntr=0.3,0.1

Type RM Length L Ch R = 1 ,738183  ,1506,1506,1506
BEGIN DESCRIPTION:
NAVASOTA RIVER 294
END DESCRIPTION:
XS GIS Cut Line= 3
      3519027.49     10519897.54      3517871.77     10518354.58
      3515273.16     10515806.84
#Sta/Elev= 30
  3072.2  392.64  3252.3  389.04  3273.1  386.62  3379.4  382.22    3394  380.32
  3446.5  377.45  3558.6   371.7  3602.4  368.68  3666.8  366.27  3693.8  362.15
  3716.8     363  7922.4     363  7943.5  364.35  7993.1  365.52  8021.4  368.12
  8106.2  371.63  8140.2  373.59  8155.7  374.66  8205.3  374.82  8212.3  375.97
  8233.5   376.5  8254.7  378.84  8304.3  382.29  8360.7  387.64  8417.3  395.58
  8431.4  398.05  8452.7  403.29  8537.6  412.52  8594.1   416.6  8639.2  417.26
#Mann= 5 ,-1 , 0
  3072.2     .16       0  3446.5     .05       0  3558.6    .033       0
  8106.2     .07       0  8140.2     .16       0
Bank Sta=3558.6,8106.2
XS Rating Curve= 0 ,0
Exp/Cntr=0.3,0.1

Type RM Length L Ch R = 1 ,736677  ,1745,1745,1745
BEGIN DESCRIPTION:
NAVASOTA RIVER 293
END DESCRIPTION:
XS GIS Cut Line= 3
      3519898.16     10520004.76      3519243.16     10517752.79
      3517344.94     10514271.58
#Sta/Elev= 30
  2654.7  392.08  2720.4   392.5  2838.9  388.48  2982.1  386.38  3089.2  387.37
  3200.1  386.48    3262  384.25  3305.9  383.81  3532.8  371.83  3636.9  366.71
    3773  362.66  8361.4     363  8376.8  362.07  8393.2   363.3  8398.9  364.76
    8415  365.01  8474.9     369  8502.4  372.17  8562.2  379.54  8599.9  385.87
  8649.5  393.67  8665.7  397.76  8687.5  399.41  8709.3  403.91  8771.8  412.39
  8818.5   418.4  8878.3  423.32  8894.5  423.56  8930.9  426.21  8965.1  425.96
#Mann= 6 ,-1 , 0
  2654.7     .16       0  2982.1     .05       0  3532.8    .033       0
  8502.4     .16       0  8599.9     .05       0  8771.8     .16       0
Bank Sta=3532.8,8502.4
XS Rating Curve= 0 ,0
Exp/Cntr=0.3,0.1

Type RM Length L Ch R = 1 ,734932  ,3448,3448,3448
BEGIN DESCRIPTION:
NAVASOTA RIVER 292
END DESCRIPTION:
XS GIS Cut Line= 3
      3522647.39     10520076.77      3520665.34     10516741.69
       3519731.4     10515095.34
#Sta/Elev= 30
  1120.4  399.82  1172.9  400.26  1370.1  397.28  1463.7  397.66  1557.6   395.1
  1835.1  392.88  2018.8  391.78  2077.2  390.03  2529.2  371.66  2731.7  363.53
  2821.4  363.59  2858.2  362.03  2864.2     363  6013.6     363  6045.4  364.62
  6051.2  363.37    6067  365.92  6153.6  366.64  6250.2  372.09    6455  383.02
  6484.5  383.43  6600.7  388.72  6681.5  396.33    6719  402.22  6762.2  403.71
  6770.6  405.12  6778.1  409.05  6783.9  406.85  6793.6  410.97  6892.8  407.74
#Mann= 6 ,-1 , 0
  1120.4     .16       0  1557.6     .05       0  1835.1     .16       0
  2529.2    .033       0  6250.2     .16       0  6484.5     .05       0
Bank Sta=2529.2,6250.2
XS Rating Curve= 0 ,0
Exp/Cntr=0.3,0.1

Type RM Length L Ch R = 1 ,731484  ,3160,3160,3160
BEGIN DESCRIPTION:
NAVASOTA RIVER 244
END DESCRIPTION:
XS GIS Cut Line= 2
      3526790.95     10516717.54      3521257.07     10513319.09
#Sta/Elev= 30
  1003.3  394.25  1342.3  382.18  1369.8  383.59  1494.8  383.41  1522.6  380.36
  1574.7  379.57  1617.3  376.96    1654  379.04    2118  381.28  2301.6  381.75
  2344.1  379.32  2363.6   380.1  2421.7  378.83  2490.4     379  2562.7  378.31
  2591.6  374.46  2690.8  372.38  2765.6  369.79  2817.7  370.17    2903   368.1
  3028.4  368.19  3065.1  365.23    3071     363  6772.6  362.06  6952.7  370.91
  7041.6  379.35  7142.2  384.83    7289  396.77  7389.6  400.58  7497.4  402.06
#Mann= 7 ,-1 , 0
  1003.3     .05       0  2363.6     .08       0  2421.7     .15       0
  2490.4      .1       0  2690.8     .05       0  2817.7    .033       0
  6952.7     .05       0
Bank Sta=2817.7,6952.7
XS Rating Curve= 0 ,0
Exp/Cntr=0.3,0.1

Type RM Length L Ch R = 1 ,728324  ,3362,3362,3362
BEGIN DESCRIPTION:
NAVASOTA RIVER 243
END DESCRIPTION:
XS GIS Cut Line= 2
      3527871.72     10513826.94      3521647.71     10509868.57
#Sta/Elev= 30
  2338.7  386.07  2350.1   385.5  2466.2   385.6  2711.7  382.79  2784.6  380.14
  2978.5  371.23  3066.5  367.86  3102.9  365.78  3212.2  362.87  3233.3  363.37
  8919.3     363  8934.3  361.93  8955.7  365.56  8976.9  366.35  9034.5  371.03
  9122.5  377.38  9164.9  382.32  9231.8   387.7    9247  389.77  9252.9  391.54
  9304.6  394.24  9346.9  398.35  9377.4  400.32  9383.3  401.44  9471.4  407.48
    9520  412.57  9586.6  415.33  9605.1  415.25  9638.2  416.61  9714.8  417.87
#Mann= 4 ,-1 , 0
  2338.7     .05       0  2978.5    .033       0  9034.5     .05       0
  9605.1     .16       0
Bank Sta=2978.5,9034.5
XS Rating Curve= 0 ,0
Exp/Cntr=0.3,0.1

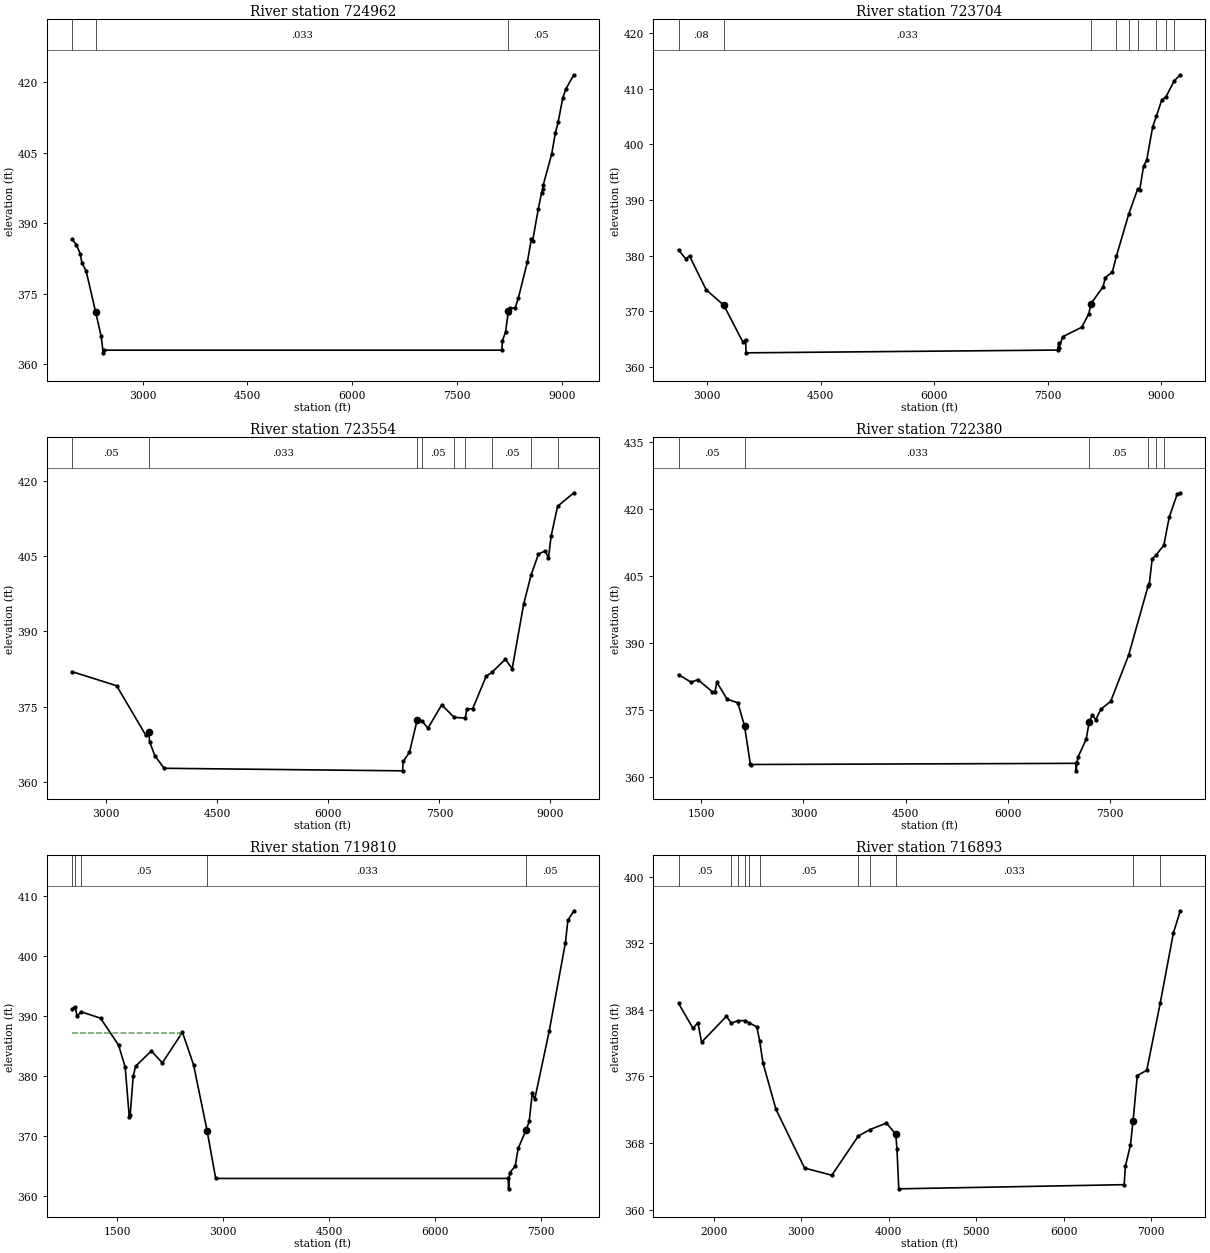
Type RM Length L Ch R = 1 ,724962  ,1258,1258,1258
BEGIN DESCRIPTION:
NAVASOTA RIVER 242
END DESCRIPTION:
XS GIS Cut Line= 3
      3529320.49     10513045.88      3528204.18     10510248.92
      3526508.06     10506436.38
#Sta/Elev= 30
  1988.5  386.56  2051.9  385.41  2105.8  383.47  2130.1  381.54  2189.4  379.87
  2326.8  371.05  2404.9  365.95  2434.3  362.43  2445.3     363  8142.8     363
  8149.2  364.95  8194.7  366.89  8235.8  371.32  8241.2   370.9  8264.5   371.9
  8334.2  372.03    8379  374.15  8507.9  381.81  8565.3  386.75  8583.1  386.32
  8663.8  393.04  8710.3  396.45    8728  397.18  8733.5  398.09  8855.2  404.71
  8907.2  409.13  8948.1  411.52  9013.8  416.64  9057.6  418.54  9172.8  421.58
#Mann= 3 , 0 , 0
  1988.5     .05       0  2326.8    .033       0  8235.8     .05       0
Bank Sta=2326.8,8235.8
XS Rating Curve= 0 ,0
Exp/Cntr=0.3,0.1

Type RM Length L Ch R = 1 ,723704  ,150,150,150
BEGIN DESCRIPTION:
NAVASOTA RIVER 239
END DESCRIPTION:
XS GIS Cut Line= 6
      3530117.43     10511636.34      3530047.11     10510868.13
      3528762.22     10508753.33      3528432.54     10507381.93
      3527743.09     10506322.18      3527198.55     10505897.12
#Sta/Elev= 30
  2625.1  381.02  2719.9  379.41  2769.9  379.93  2990.1  373.85    3222  371.07
  3472.4  364.52  3511.1  364.88  3516.5   362.5    7631     363  7646.3  364.33
  7652.2  363.42  7696.3  365.39    7950  367.11  8044.1  369.57  8070.6  371.34
  8230.8  374.38  8260.9  376.03  8353.5  377.05  8408.4  379.95  8571.9  387.54
  8689.5  392.02  8715.7  391.87  8765.2  396.03  8808.4  397.24  8886.7  403.21
  8936.2  405.11  9006.9  408.03  9060.4  408.55  9171.1  411.45  9251.3  412.53
#Mann= 9 ,-1 , 0
  2625.1     .08       0    3222    .033       0  8070.6     .05       0
  8408.4     .08       0  8571.9     .08       0  8689.5      .1       0
  8936.2     .15       0  9060.4      .1       0  9171.1     .08       0
Bank Sta=3222,8070.6
XS Rating Curve= 0 ,0
Exp/Cntr=0.3,0.1

Type RM Length L Ch R = 1 ,723554  ,1174,1174,1174
BEGIN DESCRIPTION:
NAVASOTA RIVER 240
END DESCRIPTION:
XS GIS Cut Line= 6
      3530267.32     10511642.21        3530184.      10510806.3
      3528898.86     10508690.49      3528568.82     10507318.83
      3527853.43     10506220.16      3527282.51     10505772.82
#Sta/Elev= 30
    2537  381.96  3139.2  379.15  3532.5  369.29  3575.4  369.83  3583.6  368.02
  3655.8  365.18  3780.6  362.69  7002.3  362.18    7009  364.06  7094.6  365.85
  7199.3  372.33  7265.8   372.1  7344.6  370.68  7530.2  375.34  7698.1  372.86
  7847.7  372.69  7870.4  374.48  7949.3  374.58  8131.1  381.05  8206.7   381.8
  8390.2  384.42  8482.8  382.56  8638.3  395.48  8737.2  401.18  8836.6  405.38
  8929.3  406.07  8972.5   404.6  9007.7  408.93    9096  414.94  9315.7  417.63
#Mann= 9 ,-1 , 0
    2537     .05       0  3575.4    .033       0  7199.3     .16       0
  7265.8     .05       0  7698.1     .08       0  7847.7     .05       0
  8206.7     .05       0  8737.2     .05       0    9096     .05       0
Bank Sta=3575.4,7199.3
XS Rating Curve= 0 ,0
Exp/Cntr=0.3,0.1

Type RM Length L Ch R = 1 ,722380  ,2570,2570,2570
BEGIN DESCRIPTION:
NAVASOTA RIVER 241
END DESCRIPTION:
XS GIS Cut Line= 3
       3531720.2     10512395.56       3530348.2     10508817.17
      3528602.17      10505749.8
#Sta/Elev= 30
  1167.6  382.86  1353.9  381.17  1450.2  381.77  1664.5  379.03  1704.4  379.08
  1728.7  381.18  1879.3   377.4    2038  376.55  2135.7  371.36  2221.4   362.8
  2232.1  362.74    6997     363  7002.8  361.32  7008.9     363  7031.5  364.51
  7148.6  368.41  7192.6  372.32  7238.6  373.81  7288.4  372.75  7363.4  375.11
  7508.9  376.91  7772.6  387.31  8056.7  402.76  8073.8  403.13  8117.1  408.87
  8172.2  409.64  8287.7  411.89  8366.3  418.14  8483.1  423.31  8529.5  423.63
#Mann= 6 ,-1 , 0
  1167.6     .05       0  2135.7    .033       0  7192.6     .05       0
  8056.7     .08       0  8172.2      .1       0  8287.7     .05       0
Bank Sta=2135.7,7192.6
XS Rating Curve= 0 ,0
Exp/Cntr=0.3,0.1

Type RM Length L Ch R = 1 ,719810  ,2917,2917,2917
BEGIN DESCRIPTION:
NAVASOTA RIVER 238
END DESCRIPTION:
XS GIS Cut Line= 2
      3535113.65     10510726.65      3530700.73     10505155.18
#Sta/Elev= 30
   857.8  391.24     903  391.61   927.2  390.03   988.1  390.74  1260.5  389.69
  1516.9   385.2  1609.8  381.55  1667.6   373.3  1680.6   373.5  1723.6  380.03
  1758.9   381.7    1980  384.23  2137.1  382.25  2420.7  387.35  2577.8  381.96
  2770.1  370.96  2891.9     363  7034.5     363  7040.6  361.27  7055.3  363.95
  7133.8  365.02  7177.1  368.02  7290.9   371.1  7332.5  372.51  7375.8  377.17
  7411.1  376.19  7617.8  387.63  7845.4  402.24  7880.6  405.99  7965.2  407.57
#Mann= 5 ,-1 , 0
   857.8     .05       0     903     .08       0   988.1     .05       0
  2770.1    .033       0  7290.9     .05       0
#XS Ineff= 2 , 0
       0  2385.5  387.23               0
Permanent Ineff=
       F       F
Bank Sta=2770.1,7290.9
XS Rating Curve= 0 ,0
Exp/Cntr=0.3,0.1

Type RM Length L Ch R = 1 ,716893  ,2488,2488,2488
BEGIN DESCRIPTION:
NAVASOTA RIVER 237
END DESCRIPTION:
XS GIS Cut Line= 3
      3537217.64     10507748.25      3534624.97     10505542.05
      3532670.07       10504264.
#Sta/Elev= 30
  1595.7  384.78  1760.5  381.78  1816.9  382.43  1859.8  380.11  2143.1  383.22
  2199.9  382.38  2272.2   382.7  2358.7   382.7  2397.8  382.46  2491.2  381.96
  2523.4  380.28  2561.5  377.62  2710.8  372.03    3037     365  3349.3  364.13
  3653.7  368.86  3787.6  369.62  3973.8   370.4  4080.3  369.06  4094.6  367.23
  4115.2   362.5  6692.6     363  6707.7  365.23    6765  367.76  6795.2  370.68
  6843.3   376.1  6951.9  376.74  7104.9  384.76  7256.6  393.24  7335.6  395.89
#Mann= 11 ,-1 , 0
  1595.7     .05       0  2199.9      .1       0  2272.2     .08       0
  2358.7     .15       0  2397.8      .1       0  2523.4     .05       0
  3653.7     .16       0  3787.6     .12       0  4080.3    .033       0
  6795.2     .05       0  7104.9     .16       0
Bank Sta=4080.3,6795.2
XS Rating Curve= 0 ,0
Exp/Cntr=0.3,0.1

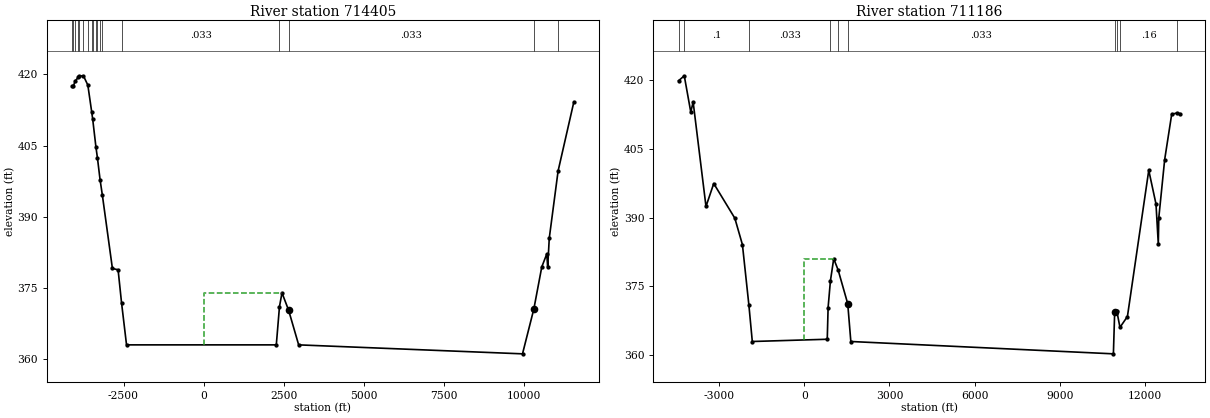
Type RM Length L Ch R = 1 ,714405  ,3219,3219,3219
BEGIN DESCRIPTION:
NAVASOTA RIVER 236
END DESCRIPTION:
XS GIS Cut Line= 3
      3542215.65      10511077.3       3536517.1     10503975.29
        3531753.     10499476.13
#Sta/Elev= 30
 -4105.6  417.46 -4065.3  417.48 -4011.5  418.57 -3914.7  419.35 -3881.6  419.64
 -3751.7   419.7 -3613.6  417.74 -3491.9  412.03   -3463  410.62 -3361.9  404.74
 -3312.4  402.31   -3232  397.81 -3161.9  394.62 -2846.9   379.1 -2669.3  378.82
 -2562.1  371.89   -2406     363  2267.5     363  2366.7  371.07  2445.1  373.96
  2651.6   370.3  2965.2     363  9950.5  361.11 10304.4  370.57   10552  379.43
 10707.7  382.15   10736  379.38 10785.4  385.48 11060.9  399.64 11552.8   414.2
#Mann= 18 ,-1 , 0
 -4105.6     .05       0 -4065.3     .16       0 -4011.5     .05       0
 -3914.7     .16       0 -3881.6     .05       0 -3751.7     .08       0
 -3613.6     .08       0 -3491.9     .05       0   -3463     .08       0
 -3361.9     .16       0 -3312.4     .08       0   -3232     .05       0
 -3161.9     .08       0 -2562.1    .033       0  2366.7     .16       0
  2651.6    .033       0 10304.4     .16       0 11060.9     .05       0
#XS Ineff= 2 , 0
       0  2445.1  373.96               0
Permanent Ineff=
       F       F
Bank Sta=2651.6,10304.4
XS Rating Curve= 0 ,0
Exp/Cntr=0.3,0.1

Type RM Length L Ch R = 1 ,711186  ,2682,2682,2682
BEGIN DESCRIPTION:
NAVASOTA RIVER 477
END DESCRIPTION:
XS GIS Cut Line= 3
      3543275.71     10511425.96      3539467.95     10502795.31
      3532073.32     10499142.14
#Sta/Elev= 30
 -4433.3  419.84 -4231.2  420.93 -4002.3  413.03 -3918.4   415.2 -3465.9  392.44
   -3193  397.44 -2449.8  389.88 -2182.4  384.12 -1956.2  371.05 -1834.1     363
   806.9  363.49   837.1  370.41     918   376.2  1034.6  381.05  1190.9  378.58
  1528.3  371.24  1637.9     363 10889.6  360.31 10934.8  369.52 11007.7  369.71
 11120.5  366.08 11383.6  368.44 12135.4  400.32 12390.3  392.98   12472  384.24
 12488.9  389.96 12696.4  402.67 12943.3  412.52   13130  412.83 13247.8  412.66
#Mann= 10 ,-1 , 0
 -4433.3     .05       0 -4231.2      .1       0 -1956.2    .033       0
     918     .16       0  1190.9     .05       0  1528.3    .033       0
 10934.8     .16       0 11007.7     .05       0 11120.5     .16       0
   13130     .05       0
#XS Ineff= 2 , 0
       0  1034.6  381.05               0
Permanent Ineff=
       F       F
Bank Sta=1528.3,10934.8
XS Rating Curve= 0 ,0
Exp/Cntr=0.3,0.1