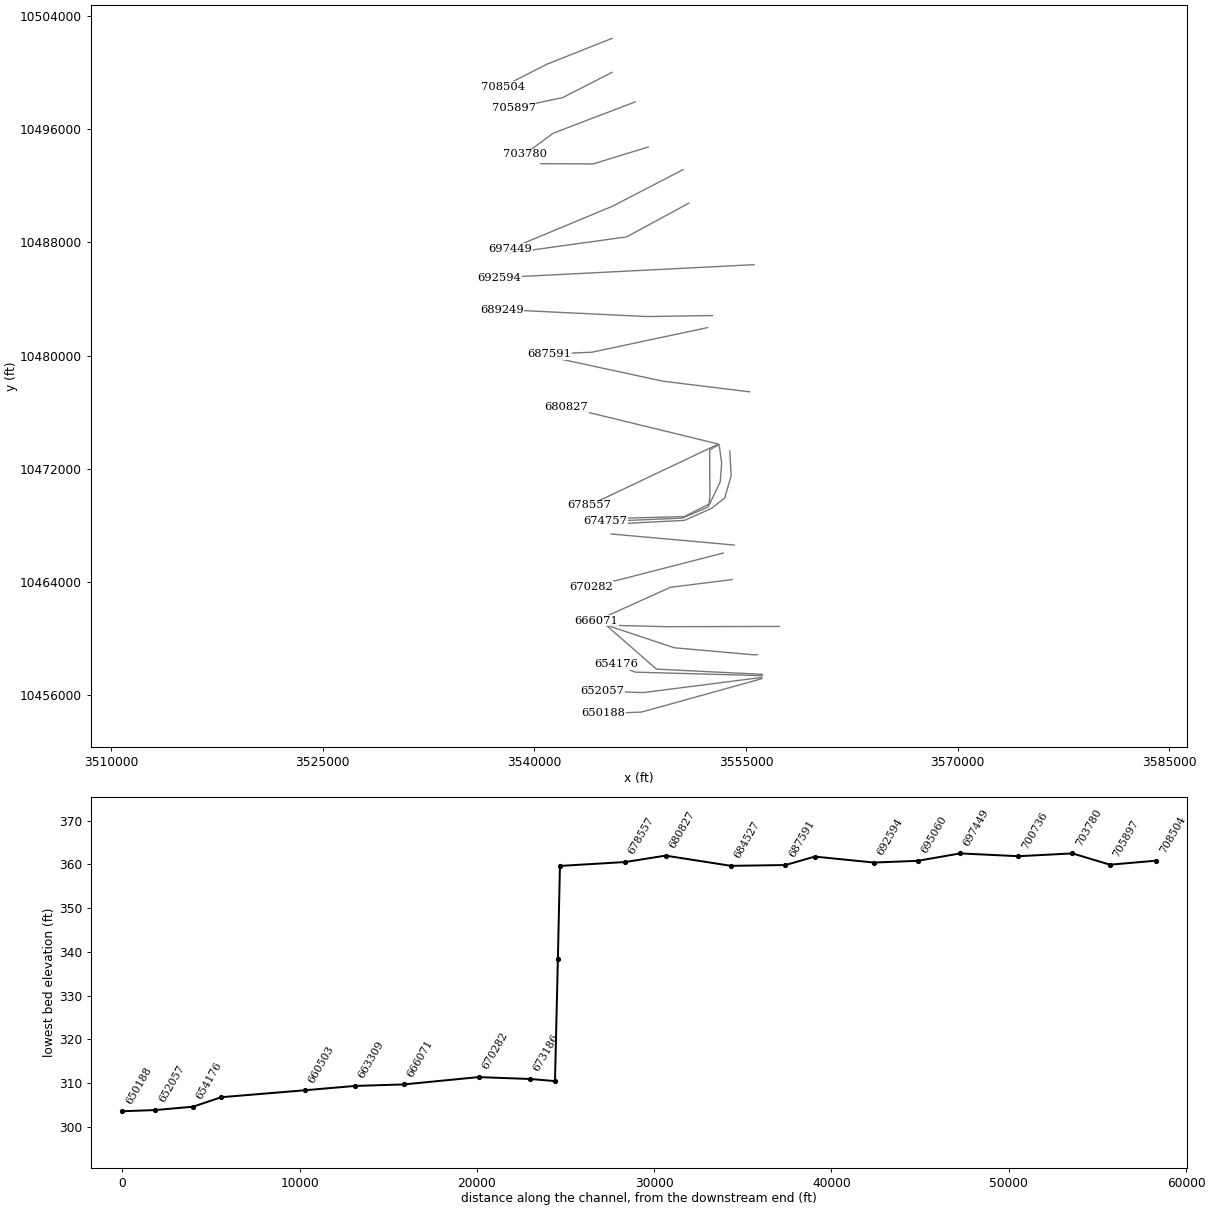
HEC-RAS study NAVASOTA RIVER.prj: NAVASOTA RIVER Base Level Engineering

--- NAVASOTA RIVER.g01 (geometry) --- (continued)

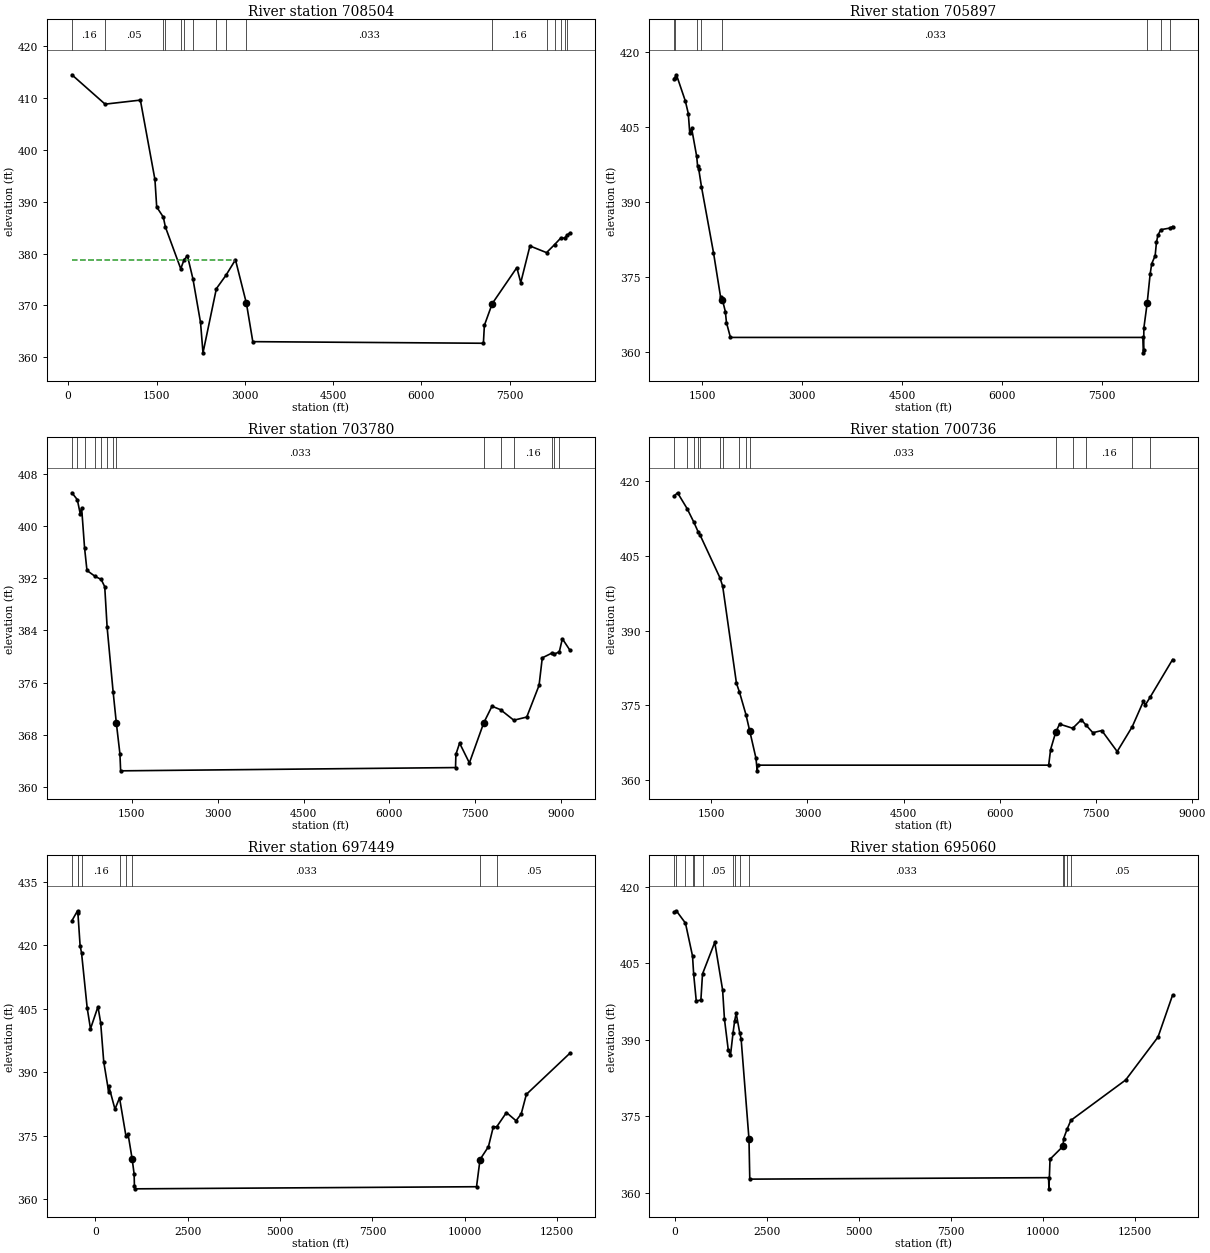
Type RM Length L Ch R = 1 ,708504  ,2607,2607,2607
BEGIN DESCRIPTION:
NAVASOTA RIVER 235
END DESCRIPTION:
XS GIS Cut Line= 3
      3545513.57     10502428.09      3540906.23     10500603.86
      3537778.56     10499018.41
#Sta/Elev= 30
    62.9  414.53   626.9  408.86  1226.1  409.64  1473.4  394.31  1503.4     389
  1615.8  387.05  1650.9  385.14  1911.9  377.07    1965  378.72    2025   379.6
  2118.7  375.13  2247.8   366.7  2289.6  360.84  2516.8  373.23  2681.2  375.84
  2841.1  378.81  3027.6  370.38  3135.7     363  7052.3  362.69    7069  366.15
  7202.6  370.35  7620.1  377.29  7686.9  374.41  7842.8  381.48  8124.8  380.19
  8260.5  381.73  8369.2  383.04  8432.4  382.99  8477.8  383.62  8524.8  383.99
#Mann= 16 ,-1 , 0
    62.9     .16       0   626.9     .05       0  1615.8      .1       0
  1650.9     .05       0  1911.9     .08       0    1965     .05       0
  2118.7    .033       0  2516.8     .05       0  2681.2      .1       0
  3027.6    .033       0  7202.6     .16       0  8124.8     .05       0
  8260.5     .08       0  8369.2     .05       0  8432.4     .16       0
  8477.8      .1       0
#XS Ineff= 2 , 0
       0  2817.8  378.76               0
Permanent Ineff=
       F       F
Bank Sta=3027.6,7202.6
XS Rating Curve= 0 ,0
Exp/Cntr=0.3,0.1

Type RM Length L Ch R = 1 ,705897  ,2117,2117,2117
BEGIN DESCRIPTION:
NAVASOTA RIVER 290
END DESCRIPTION:
XS GIS Cut Line= 3
      3545500.14     10500022.52      3542012.42     10498242.06
      3538536.13     10497507.28
#Sta/Elev= 30
  1084.1  414.68  1091.7  414.89  1114.5  415.49  1247.8  410.25  1292.3  407.74
  1314.5  403.78  1342.4  404.78  1418.2  399.17  1431.3  397.35  1447.9  396.72
  1489.8  393.12  1670.1  379.95  1775.6  371.13  1803.5  370.52  1847.9  368.16
  1864.5  365.96    1924     363  8107.5     363  8116.5  359.92  8119.8  360.42
  8121.9  364.85  8171.6  369.84  8216.2  375.66  8240.4  377.75  8291.5  379.34
  8310.6  381.98  8332.3   383.4  8375.3  384.53    8514  384.86  8553.1  385.16
#Mann= 8 ,-1 , 0
  1084.1      .1       0  1091.7     .05       0  1418.2      .1       0
  1489.8     .16       0  1803.5    .033       0  8171.6     .05       0
  8375.3     .05       0    8514     .16       0
Bank Sta=1803.5,8171.6
XS Rating Curve= 0 ,0
Exp/Cntr=0.3,0.1

Type RM Length L Ch R = 1 ,703780  ,3044,3044,3044
BEGIN DESCRIPTION:
NAVASOTA RIVER 234
END DESCRIPTION:
XS GIS Cut Line= 3
      3547148.38      10497936.4      3541332.37     10495722.85
      3539336.49     10494247.63
#Sta/Elev= 30
   451.2  405.05   545.8     404     597  401.84   621.5  402.72     673  396.59
   714.7  393.16   858.5  392.25   962.7  391.79    1025  390.68  1066.9  384.47
  1171.1  374.64  1228.3  369.78  1290.5   365.1  1302.9   362.5  7154.5     363
  7160.7  365.02  7225.5  366.74  7396.6  363.71  7647.1  369.84  7791.2  372.39
  7940.4  371.86  8172.3  370.25  8398.7  370.73  8613.8  375.58  8670.1  379.79
  8847.7  380.56  8869.9  380.34  8967.1   380.7  9020.9  382.71  9156.1  380.92
#Mann= 14 ,-1 , 0
   451.2     .05       0   545.8     .08       0     673      .1       0
   858.5     .15       0   962.7     .05       0  1066.9     .16       0
  1171.1     .05       0  1228.3    .033       0  7647.1     .16       0
  7940.4     .05       0  8172.3     .16       0  8847.7     .05       0
  8869.9     .15       0  8967.1     .05       0
Bank Sta=1228.3,7647.1
XS Rating Curve= 0 ,0
Exp/Cntr=0.3,0.1

Type RM Length L Ch R = 1 ,700736  ,3287,3287,3287
BEGIN DESCRIPTION:
NAVASOTA RIVER 142
END DESCRIPTION:
XS GIS Cut Line= 3
      3548067.87     10494749.83      3544168.85     10493552.91
      3540466.38     10493568.84
#Sta/Elev= 30
   921.4  417.04   970.4  417.63  1119.2  414.47  1221.4  411.83  1291.8  409.81
  1323.5  409.12  1634.3  400.53  1675.5  398.88  1890.7  379.41  1936.6  377.69
  2038.8  373.14    2099  369.79  2195.7  364.36  2213.8  361.86  2223.2     363
  6766.8     363  6796.8  366.14  6876.8   369.6  6936.8  371.24  7142.1   370.4
  7276.8  372.11  7353.8  370.98  7456.8  369.51  7596.8  369.94  7836.8  365.73
  8072.2  370.72  8246.8  375.81  8276.8  375.08  8352.4  376.65  8702.5  384.19
#Mann= 15 ,-1 , 0
   921.4     .05       0  1119.2     .08       0  1221.4     .05       0
  1291.8      .1       0  1323.5     .05       0  1634.3     .16       0
  1675.5     .05       0  1936.6     .08       0  2038.8     .05       0
    2099    .033       0  6876.8     .16       0  7142.1     .05       0
  7353.8     .16       0  8072.2     .05       0  8352.4     .16       0
Bank Sta=2099,6876.8
XS Rating Curve= 0 ,0
Exp/Cntr=0.3,0.1

Type RM Length L Ch R = 1 ,697449  ,2389,2389,2389
BEGIN DESCRIPTION:
NAVASOTA RIVER 291
END DESCRIPTION:
XS GIS Cut Line= 3
      3550549.61     10493154.24      3545542.11     10490566.77
      3538290.09     10487553.56
#Sta/Elev= 30
  -636.5   425.8  -483.7  428.15  -472.9  427.54  -414.2  419.94  -374.7  418.18
  -222.5  405.22  -132.8  400.28    69.8  405.51   142.7   401.7   225.7   392.5
   358.6  385.47   364.2   386.7   530.1  381.31   653.4  383.98     825  375.09
   884.5  375.42   995.3  369.55  1049.1  365.96  1056.1  363.28  1071.4   362.5
 10319.7     363 10414.4  369.42 10641.8  372.45 10771.8  377.06 10868.4  377.18
 11129.7  380.51   11390  378.58 11529.8  380.19 11668.7   384.8 12853.1  394.56
#Mann= 9 ,-1 , 0
  -636.5     .16       0  -483.7     .05       0  -472.9     .08       0
  -374.7     .16       0   653.4     .05       0     825     .16       0
   995.3    .033       0 10414.4     .08       0 10868.4     .05       0
Bank Sta=995.3,10414.4
XS Rating Curve= 0 ,0
Exp/Cntr=0.3,0.1

Type RM Length L Ch R = 1 ,695060  ,2466,2466,2466
BEGIN DESCRIPTION:
NAVASOTA RIVER 233
END DESCRIPTION:
XS GIS Cut Line= 3
      3550946.84     10490779.83      3546540.19     10488396.45
      3538107.09      10487232.1
#Sta/Elev= 30
    -9.9  414.97    41.9  415.27   290.2  412.85   482.1   406.4   512.7  402.86
   583.2  397.62   708.8  397.78   752.8   402.9  1085.5  409.09  1298.6  399.76
  1348.4  394.07  1451.8  388.01  1511.7  386.94  1582.5  391.41  1625.1  393.69
  1666.7  395.18  1763.1  391.35    1801  390.17  2014.1  370.58    2036  362.71
 10146.4     363 10156.3  360.81 10185.8  366.61 10540.1  369.16 10552.9  370.62
 10652.2  372.55 10751.4  374.22   12239  382.13 13116.9  390.54 13513.1  398.77
#Mann= 14 ,-1 , 0
    -9.9     .05       0    41.9     .16       0   290.2     .05       0
   482.1      .1       0   512.7     .15       0   752.8     .05       0
  1582.5     .16       0  1625.1     .05       0  1763.1     .16       0
  2014.1    .033       0 10540.1     .05       0 10552.9      .1       0
 10652.2     .08       0 10751.4     .05       0
Bank Sta=2014.1,10540.1
XS Rating Curve= 0 ,0
Exp/Cntr=0.3,0.1

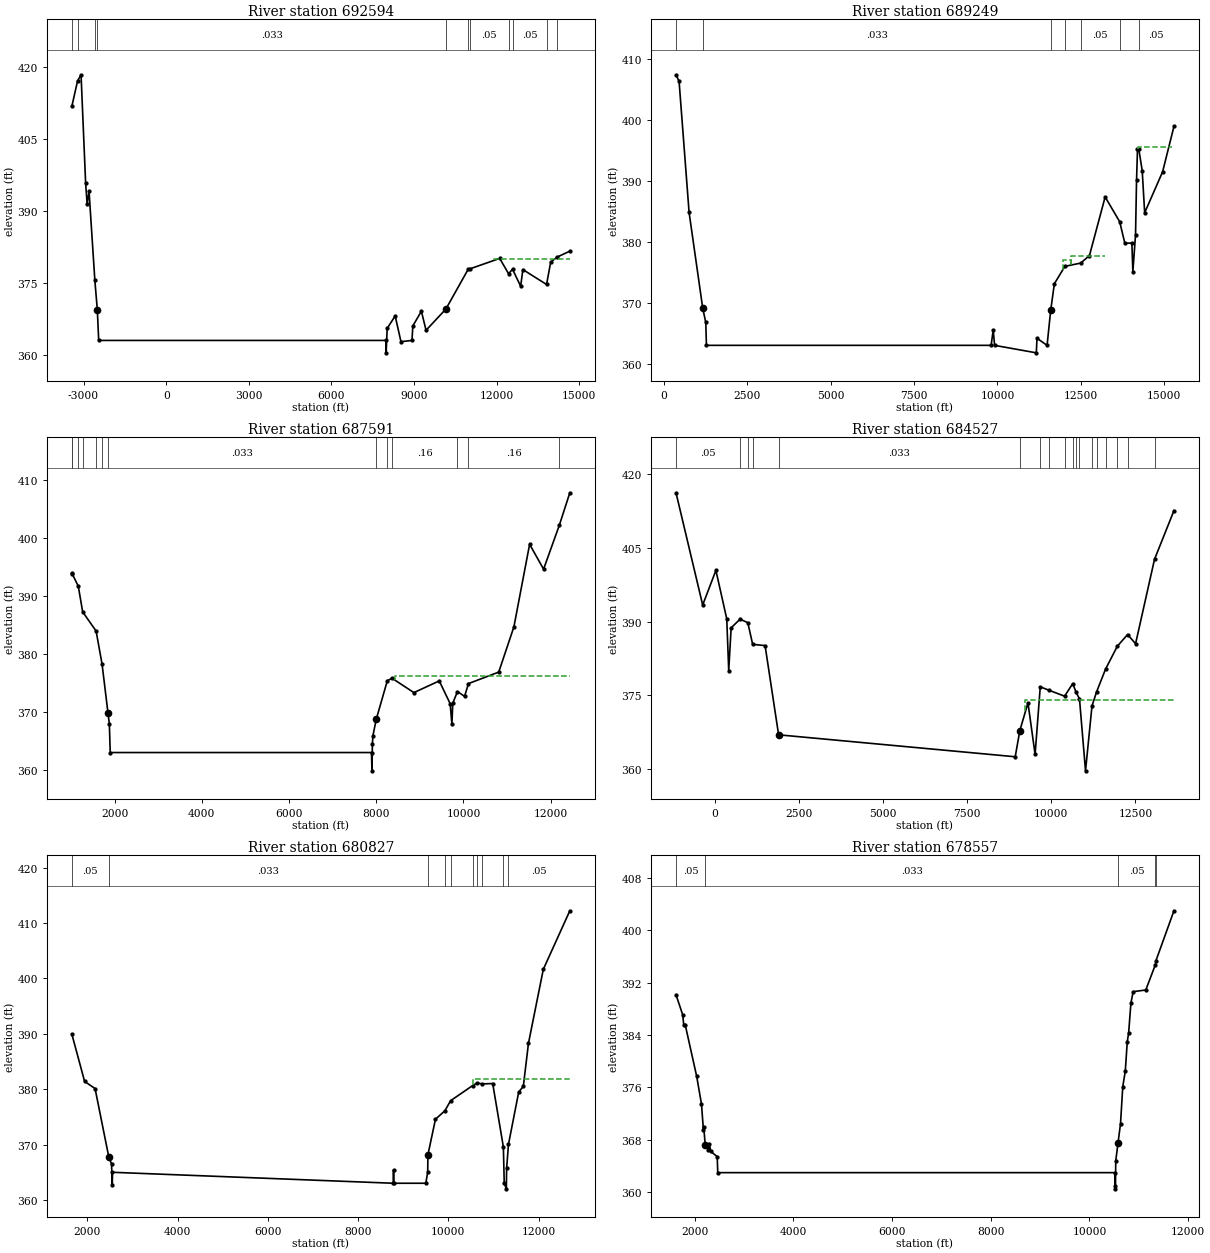
Type RM Length L Ch R = 1 ,692594  ,3345,3345,3345
BEGIN DESCRIPTION:
NAVASOTA RIVER 476
END DESCRIPTION:
XS GIS Cut Line= 2
      3555564.85     10486431.83      3537509.24     10485520.37
#Sta/Elev= 30
 -3424.1  411.89 -3217.8  417.17 -3090.9  418.45 -2925.1  395.86 -2870.6  391.53
 -2800.6  394.12 -2589.6  375.51 -2500.2  369.38 -2450.1     363  7981.4     363
  7986.1  360.41  8023.2  365.52  8313.6  368.11  8523.8  362.74  8924.4     363
  8954.4  366.02  9264.8   369.1    9435  365.12 10155.9  369.56 10961.1  377.82
 11026.2  377.94 12108.4  380.12 12430.8  376.93 12574.8  377.85 12869.4  374.31
 12949.5  377.79 13809.3  374.68 13960.8  379.37 14204.4  380.43 14654.5  381.63
#Mann= 11 ,-1 , 0
 -3424.1     .05       0 -3217.8     .16       0 -2589.6     .05       0
 -2500.2    .033       0 10155.9     .05       0 10961.1      .1       0
 11026.2     .05       0 12430.8      .1       0 12574.8     .05       0
 13809.3     .08       0 14204.4     .05       0
#XS Ineff= 2 , 0
       0                 11898.1       0  380.03
Permanent Ineff=
       F       F
Bank Sta=-2500.2,10155.9
XS Rating Curve= 0 ,0
Exp/Cntr=0.3,0.1

Type RM Length L Ch R = 1 ,689249  ,1658,1658,1658
BEGIN DESCRIPTION:
NAVASOTA RIVER 475
END DESCRIPTION:
XS GIS Cut Line= 3
      3552614.25     10482835.84      3547980.57     10482766.38
      3537701.95     10483258.73
#Sta/Elev= 30
   365.8  407.41     458  406.34     758  384.82    1168  369.05    1258  366.77
    1278     363  9810.8     363    9874  365.54  9914.1     363 11165.3  361.77
 11185.5  364.16 11487.7     363   11596  368.75 11706.1  373.11 12021.4  375.97
 12494.7   376.5 12757.3  377.73 13227.9  387.36 13664.1  383.29 13818.6  379.75
 14028.8   379.8 14058.8  375.11 14138.9  381.15   14169  390.07 14197.8  395.21
   14234   395.3 14339.2  391.67 14412.4  384.76 14949.9  391.48 15290.4  398.93
#Mann= 7 ,-1 , 0
   365.8     .05       0    1168    .033       0   11596     .05       0
 12021.4     .16       0 12494.7     .05       0 13664.1     .16       0
   14234     .05       0
#XS Ineff= 4 ,-1
 11956.4 12196.7  376.95 13227.9   14219  387.36   14219 15220.2  395.59
 12196.7 13227.9  377.69
Permanent Ineff=
       F       F       F       F
Bank Sta=1168,11596
XS Rating Curve= 0 ,0
Exp/Cntr=0.3,0.1

Type RM Length L Ch R = 1 ,687591  ,3064,3064,3064
BEGIN DESCRIPTION:
NAVASOTA RIVER 143
END DESCRIPTION:
XS GIS Cut Line= 3
      3552282.36      10481986.7      3544089.13     10480246.93
      3541050.93     10480116.72
#Sta/Elev= 30
  1022.3  393.98  1028.7  393.88  1169.5  391.72  1269.7  387.29    1578  383.98
  1714.8  378.25  1850.6  369.81  1881.3  367.96  1901.7     363  7892.4     363
  7902.1  359.84  7912.8  364.45  7923.1  365.85  8001.6  368.76    8254  375.39
  8361.3  375.84  8863.6  373.35  9445.3  375.37  9695.5  371.44  9735.5  367.89
  9755.6  371.53  9863.6  373.54 10025.8   372.7 10115.7  374.91 10808.9  376.89
 11156.8   384.7 11517.2  398.96 11837.5  394.67 12196.5  402.21 12439.2  407.86
#Mann= 13 ,-1 , 0
  1022.3     .16       0  1028.7     .08       0  1169.5     .05       0
  1269.7      .1       0    1578     .05       0  1714.8      .1       0
  1850.6    .033       0  8001.6     .16       0    8254     .05       0
  8361.3     .16       0  9863.6     .05       0 10115.7     .16       0
 12196.5     .05       0
#XS Ineff= 2 , 0
       0                    8424       0  376.27
Permanent Ineff=
       F       F
Bank Sta=1850.6,8001.6
XS Rating Curve= 0 ,0
Exp/Cntr=0.3,0.1

Type RM Length L Ch R = 1 ,684527  ,3700,3700,3700
BEGIN DESCRIPTION:
NAVASOTA RIVER 232
END DESCRIPTION:
XS GIS Cut Line= 3
      3555259.37      10477446.5      3549150.95     10478191.64
      3540696.98     10480008.97
#Sta/Elev= 30
 -1153.7  416.16  -360.6  393.36    32.3  400.39   354.7  390.55   413.3  380.04
   485.6  388.73   751.6  390.48   980.8  389.76    1125  385.36  1494.1  385.11
    1896  366.98  8928.6  362.52  9066.4  367.85  9308.1  373.47  9519.8     363
  9673.2  376.73  9923.3  376.06 10397.2  374.83 10637.1  377.38 10739.1  375.62
 10839.3  374.28 11018.4  359.66   11211  372.86   11351  375.77 11612.6  380.31
 11962.9  384.97 12268.8  387.36 12506.5  385.49 13069.2  402.64 13647.1  412.53
#Mann= 18 ,-1 , 0
 -1153.7     .05       0   751.6     .16       0   980.8     .05       0
    1125      .1       0    1896    .033       0  9066.4     .05       0
  9673.2     .08       0  9923.3     .05       0 10397.2     .16       0
 10637.1     .08       0 10739.1     .16       0 10839.3    .033       0
   11211     .16       0   11351     .05       0 11612.6     .16       0
 11962.9     .05       0 12268.8     .16       0 13069.2     .05       0
#XS Ineff= 2 , 0
       0                  9233.4       0     374
Permanent Ineff=
       F       F
Bank Sta=1896,9066.4
XS Rating Curve= 0 ,0
Exp/Cntr=0.3,0.1

Type RM Length L Ch R = 1 ,680827  ,2270,2270,2270
BEGIN DESCRIPTION:
NAVASOTA RIVER 231
END DESCRIPTION:
XS GIS Cut Line= 2
      3553006.55     10473765.34      3542280.86     10476368.63
#Sta/Elev= 30
  1655.3  389.92  1937.7  381.39  2169.4  380.11  2472.8  367.78  2534.5  366.48
  2550.6  362.75  2555.7  364.98  8779.6     363  8784.7  365.41  8791.1     363
  9500.1     363  9541.9  364.98    9547  368.14  9714.1  374.57  9924.5   376.1
 10048.8  377.91 10540.7  380.66 10643.5  381.13 10746.2  380.94 10982.9  381.02
 11219.6  369.54 11238.7     363 11285.4  361.99 11291.6  365.71 11332.8  370.04
 11559.2  379.48 11661.7   380.5 11775.3  388.27 12104.6  401.65 12692.4  412.23
#Mann= 10 ,-1 , 0
  1655.3     .05       0  2472.8    .033       0    9547      .1       0
  9924.5     .05       0 10048.8     .16       0 10540.7     .05       0
 10643.5     .16       0 10746.2     .05       0 11219.6    .033       0
 11332.8     .05       0
#XS Ineff= 2 , 0
       0                 10550.7       0  381.76
Permanent Ineff=
       F       F
Bank Sta=2472.8,9547
XS Rating Curve= 0 ,0
Exp/Cntr=0.3,0.1

Type RM Length L Ch R = 1 ,678557  ,3684,3684,3684
BEGIN DESCRIPTION:
NAVASOTA RIVER 230
END DESCRIPTION:
XS GIS Cut Line= 2
      3553006.58     10473735.83      3543888.74     10469423.94
#Sta/Elev= 30
  1624.7  390.14    1760  387.08  1782.8  385.46    1811  385.56  2044.1  377.67
  2140.7  373.46  2180.7  369.44  2186.2  369.99  2215.9  367.28  2282.8  366.46
    2300  367.44  2328.3  366.24  2459.3  365.44  2470.4     363 10514.6     363
 10523.1  360.53 10526.4  361.03 10531.9  364.81 10577.4  367.49 10628.4  370.48
 10673.9  376.11   10725  378.48   10765  382.96 10793.2  384.33 10838.8  388.87
 10884.3   390.6 11140.1  390.86 11335.4  394.73 11345.2  395.31 11710.7  402.94
#Mann= 5 ,-1 , 0
  1624.7     .05       0  2215.9    .033       0 10577.4     .05       0
 11335.4     .16       0 11345.2     .05       0
Bank Sta=2215.9,10577.4
XS Rating Curve= 0 ,0
Exp/Cntr=0.3,0.1

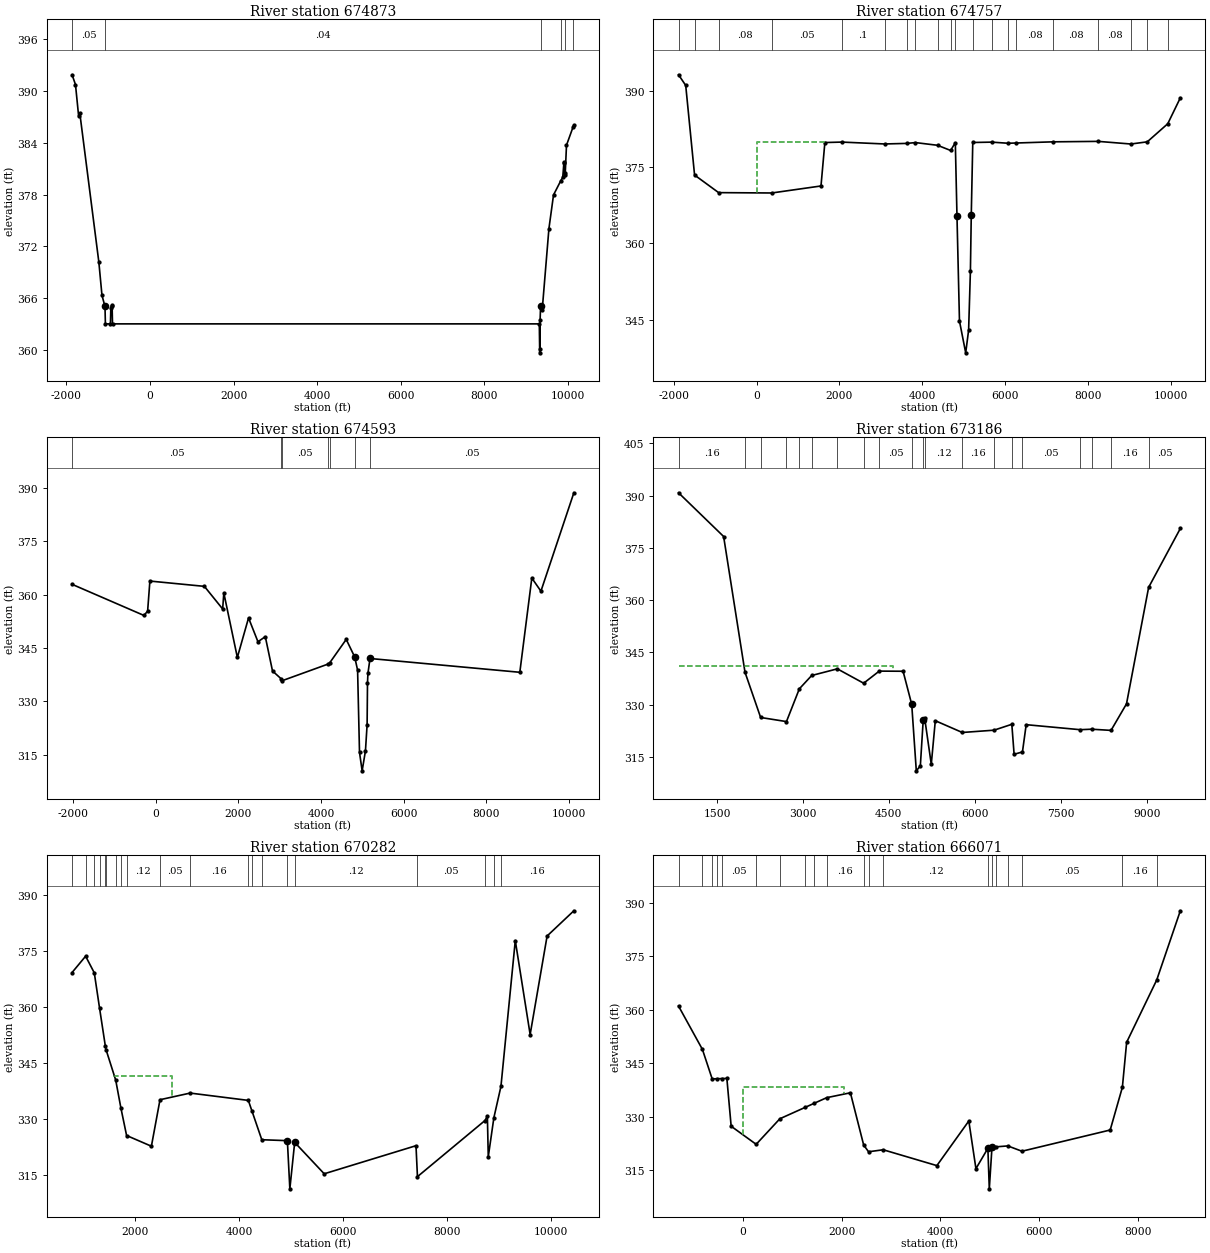
Type RM Length L Ch R = 1 ,674873  ,116,116,116
BEGIN DESCRIPTION:
NAVASOTA RIVER 229
END DESCRIPTION:
XS GIS Cut Line= 6
      3553048.62     10473696.87      3552426.56     10473343.07
      3552437.41     10469979.36       3552369.7      10469506.7
       3550619.7      10468631.7      3545136.07     10468485.18
#Sta/Elev= 30
 -1861.4   391.9 -1779.6  390.76 -1704.6  387.11 -1677.2  387.48 -1221.2  370.17
 -1146.1   366.3 -1074.3  365.02 -1064.3     363  -944.3     363  -934.3  364.83
  -914.3  365.15  -904.3  365.12  -894.3     363  9311.3     363    9321  359.64
  9324.3  360.14  9330.3   363.4  9341.3  365.02  9381.3  364.65  9541.4  374.06
  9651.4  377.96  9819.9  379.56  9871.5  379.99  9901.5   381.8  9911.5  381.72
  9918.7  380.32  9931.5  380.46  9961.5  383.73 10116.2  385.81 10137.6  386.04
#Mann= 6 ,-1 , 0
 -1861.4     .05       0 -1074.3     .04       0  9341.3     .05       0
  9819.9     .08       0  9918.7     .15       0 10116.2      .1       0
Bank Sta=-1074.3,9341.3
XS Rating Curve= 0 ,0
Exp/Cntr=0.3,0.1

Type RM Length L Ch R = 1 ,674757  ,164,164,164
BEGIN DESCRIPTION:
NAVASOTA RIVER 227
END DESCRIPTION:
XS GIS Cut Line= 6
      3553100.02     10473696.91      3553272.81     10472415.17
      3553173.86     10471081.83      3552317.95     10469309.27
      3550491.56     10468521.07      3545059.28      10468291.9
#Sta/Elev= 30
 -1882.4  393.21 -1709.2  391.12 -1495.5  373.47  -915.4  370.01   365.5  369.94
    1554  371.32  1647.6  379.87  2058.7  379.96  3088.4  379.59  3620.4   379.7
  3833.1  379.86  4365.1  379.33  4681.1  378.31  4794.5  379.85  4834.6  365.34
  4894.7  344.73  5044.8  338.47  5115.2  342.93  5158.7  354.66 5179.21  365.62
  5215.4  379.88  5671.8  379.95  6066.8  379.73  6264.4  379.78  7153.4  380.01
  8239.9   380.1  9030.1  379.58  9425.1  380.01    9919  383.57 10222.3  388.67
#Mann= 20 ,-1 , 0
 -1882.4     .05       0 -1495.5     .08       0  -915.4     .08       0
   365.5     .05       0  2058.7      .1       0  3088.4      .1       0
  3620.4      .1       0  3833.1     .08       0  4365.1     .08       0
  4681.1      .1       0  4794.5     .07       0  5215.4      .1       0
  5671.8     .05       0  6066.8     .05       0  6264.4     .08       0
  7153.4     .08       0  8239.9     .08       0  9030.1     .05       0
  9425.1     .05       0    9919     .05       0
#XS Ineff= 2 , 0
       0  1699.9  380.02               0
Permanent Ineff=
       F       F
Bank Sta=4834.6,5179.21
XS Rating Curve= 0 ,0
Exp/Cntr=0.3,0.1

Type RM Length L Ch R = 1 ,674593  ,1407,1407,1407
BEGIN DESCRIPTION:
NAVASOTA RIVER 228
END DESCRIPTION:
XS GIS Cut Line= 6
      3553848.87      10473263.6      3553946.09     10471527.53
       3553494.7     10469951.15       3552557.2     10469208.09
      3550633.59     10468360.87      3545176.18     10468082.57
#Sta/Elev= 30
 -2026.3  362.93  -287.5  354.18  -198.2  355.39  -143.4  363.85  1174.9  362.36
  1617.1     356  1645.9  360.48  1972.8  342.37  2243.6  353.48  2471.2  346.78
  2649.1  348.21  2823.4  338.56  3032.6  336.36  3054.3  335.81  4172.2  340.52
  4203.4  340.78  4607.1  347.44  4812.1   342.5  4882.2  338.79  4928.5  315.66
  4992.1  310.47  5072.4   316.1  5112.5  323.44  5121.8  335.21  5132.5  337.87
  5182.6  342.07  8807.3  338.19  9097.7   364.7  9317.9     361 10114.9  388.68
#Mann= 7 ,-1 , 0
 -2026.3     .05       0  3032.6     .08       0  3054.3     .05       0
  4172.2     .12       0  4203.4     .05       0  4812.1    .033       0
  5182.6     .05       0
#XS Ineff= 2 , 0
       0  4607.1  347.44               0
Permanent Ineff=
       F       F
Bank Sta=4812.1,5182.6
XS Rating Curve= 0 ,0
Exp/Cntr=0.3,0.1

Type RM Length L Ch R = 1 ,673186  ,2904,2904,2904
BEGIN DESCRIPTION:
NAVASOTA RIVER 129
END DESCRIPTION:
XS GIS Cut Line= 3
      3554166.03     10466618.79      3550011.66     10466993.11
      3545442.04     10467400.04
#Sta/Elev= 30
   828.8  390.83  1615.9  378.27  1988.8  339.29  2261.9  326.28  2712.7   325.1
  2937.5  334.51    3153  338.34  3600.6  340.25  4060.1  336.12  4332.2   339.6
  4748.5  339.56  4899.1  330.05  4979.2  310.95  5049.7  312.39  5099.9  325.58
  5124.4  326.16  5240.5  312.84  5310.8  325.35  5781.3  321.97  6336.1  322.63
  6646.4  324.32  6686.2  315.71    6832  316.38    6897  324.21  7839.4  322.77
  8038.6  322.91  8378.1  322.57  8648.2  330.19  9034.5  363.66  9587.7  380.57
#Mann= 20 ,-1 , 0
   828.8     .16       0  1988.8     .05       0  2261.9     .12       0
  2712.7     .05       0  2937.5     .16       0    3153     .05       0
  3600.6     .16       0  4060.1     .16       0  4332.2     .05       0
  4899.1    .033       0  5099.9     .05       0  5124.4     .12       0
  5781.3     .16       0  6336.1     .05       0  6646.4     .16       0
    6832     .05       0  7839.4     .12       0  8038.6     .16       0
  8378.1     .16       0  9034.5     .05       0
#XS Ineff= 2 , 0
       0  4577.9  341.07               0
Permanent Ineff=
       F       F
Bank Sta=4899.1,5099.9
XS Rating Curve= 0 ,0
Exp/Cntr=0.3,0.1

Type RM Length L Ch R = 1 ,670282  ,4211,4211,4211
BEGIN DESCRIPTION:
NAVASOTA RIVER 144
END DESCRIPTION:
XS GIS Cut Line= 2
       3553389.8     10466054.22       3544040.8     10463658.38
#Sta/Elev= 30
   784.9   369.3  1045.5  373.67  1212.4  369.21  1313.8  359.74  1423.9  349.69
    1438  348.66  1624.4  340.48  1725.4  332.93  1833.5  325.66  2310.7  322.79
  2476.1  335.24    3056  337.02  4174.9  335.06    4242  332.33  4433.9  324.53
  4925.8  324.28  4973.5  311.38  5066.6  323.82  5634.4  315.41  7399.7  322.93
  7427.7  314.64  8726.5  329.67  8772.6  330.86  8789.8  319.97  8897.9  330.44
  9033.6  338.81  9309.4  377.85  9595.2   352.7  9921.5  379.08   10436  385.83
#Mann= 20 ,-1 , 0
   784.9     .16       0  1045.5     .12       0  1212.4     .16       0
  1313.8     .12       0  1423.9     .16       0    1438     .12       0
  1624.4     .16       0  1725.4     .05       0  1833.5     .12       0
  2476.1     .05       0    3056     .16       0  4174.9     .12       0
    4242     .16       0  4433.9     .12       0  4925.8     .07       0
  5066.6     .12       0  7427.7     .05       0  8726.5     .16       0
  8897.9     .05       0  9033.6     .16       0
#XS Ineff= 3 ,-1
  7399.7  8772.6  322.93  8772.6  8993.7  330.86  1576.5  2708.3  341.72
Permanent Ineff=
       F       F       F
Bank Sta=4925.8,5066.6
XS Rating Curve= 0 ,0
Exp/Cntr=0.3,0.1

Type RM Length L Ch R = 1 ,666071  ,2762,2762,2762
BEGIN DESCRIPTION:
NAVASOTA RIVER 145
END DESCRIPTION:
XS GIS Cut Line= 3
      3554014.83     10464179.23       3549639.8     10463632.35
      3544379.42     10461262.58
#Sta/Elev= 30
 -1310.1  361.03  -825.9  348.87  -627.7  340.58  -528.5  340.63  -429.4  340.67
  -329.8  340.72  -242.7  327.29   264.5  322.21   745.4  329.39  1255.8  332.57
  1441.2  333.73  1695.4  335.31    2176  336.68  2445.3  322.01  2544.4  320.12
  2841.8  320.68    3930  316.23  4578.1  328.76  4722.5  315.38  4964.8  321.09
  4993.6  309.71  5048.7  321.56  5123.6   321.5  5369.1  321.76  5655.8  320.27
  7445.9  326.23    7693  338.23  7779.7  350.87  8389.2  368.34  8868.5  387.79
#Mann= 20 ,-1 , 0
 -1310.1     .05       0  -825.9     .08       0  -627.7      .1       0
  -528.5     .15       0  -429.4     .05       0   264.5     .12       0
   745.4     .16       0  1255.8      .1       0  1441.2     .05       0
  1695.4     .16       0  2445.3     .12       0  2544.4     .05       0
  2841.8     .12       0  4964.8     .07       0  5048.7     .12       0
  5123.6     .16       0  5369.1     .05       0  5655.8     .05       0
    7693     .16       0  8389.2     .05       0
#XS Ineff= 2 , 0
       0  2048.6  338.32               0
Permanent Ineff=
       F       F
Bank Sta=4964.8,5048.7
XS Rating Curve= 0 ,0
Exp/Cntr=0.3,0.1

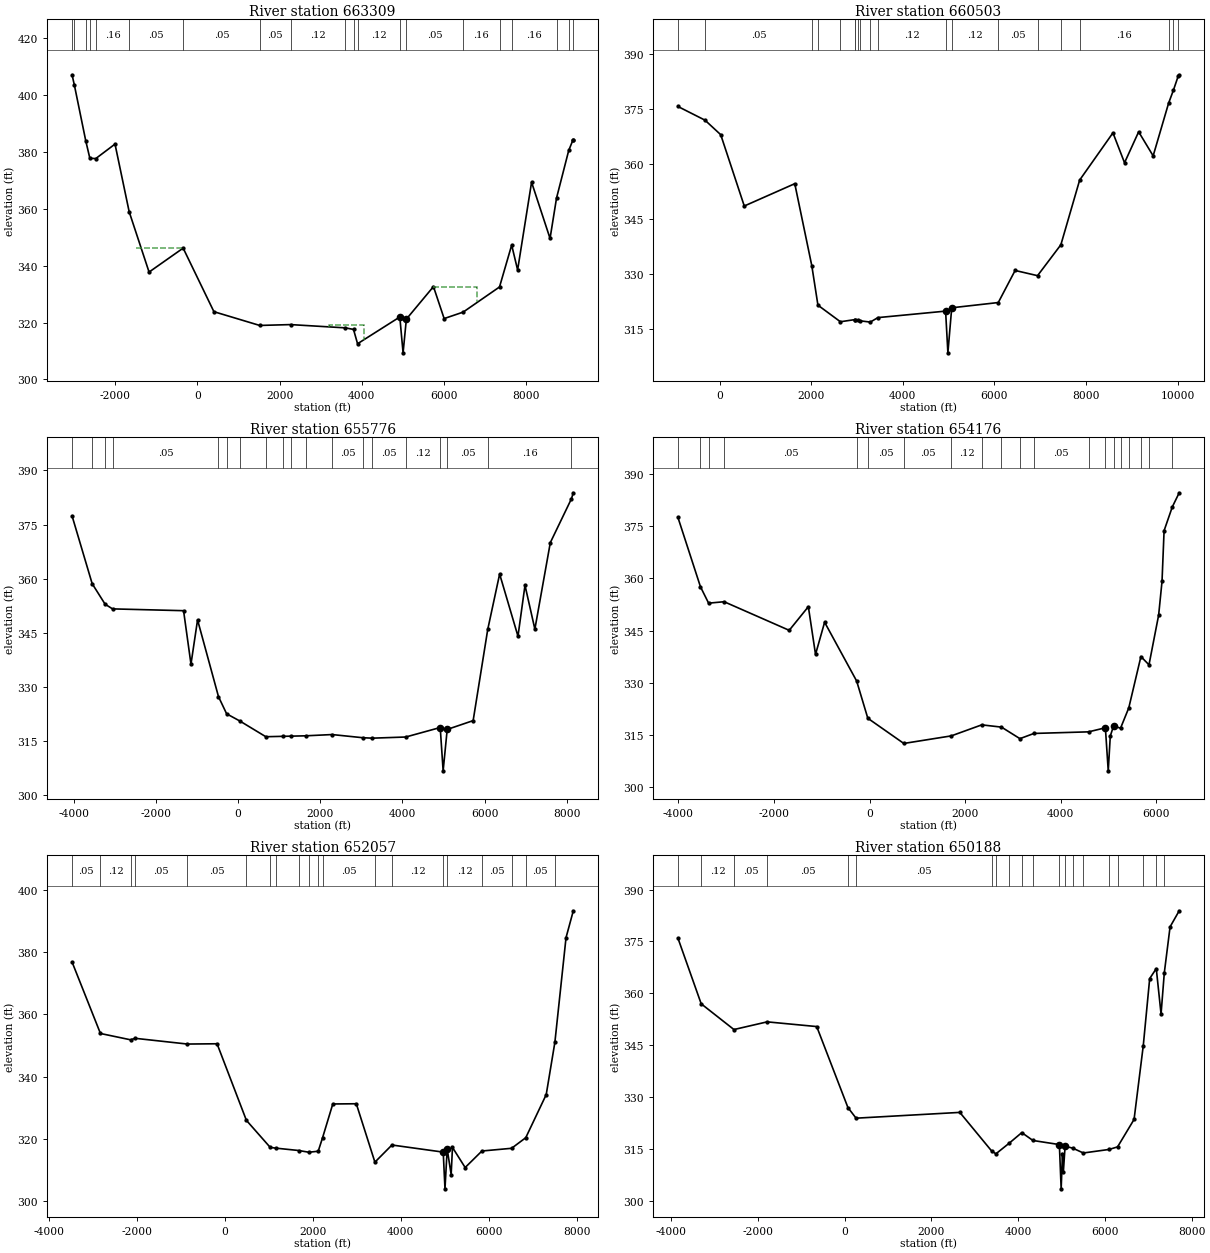
Type RM Length L Ch R = 1 ,663309  ,2806,2806,2806
BEGIN DESCRIPTION:
NAVASOTA RIVER 130
END DESCRIPTION:
XS GIS Cut Line= 3
       3557359.1     10460864.46      3549302.22     10460850.62
      3545145.34     10460955.67
#Sta/Elev= 30
 -3056.9  407.21 -3001.6  403.68 -2721.4  383.88 -2622.6  377.81 -2477.9  377.73
 -2009.9  382.82 -1664.8  359.01 -1179.9  337.78  -349.3  346.21   400.1  323.84
  1516.2     319  2267.8   319.3  3604.3  318.15    3802   317.6  3900.8  312.56
  4930.1  321.98  5009.9  309.36  5090.1  321.23  5750.3  332.67  6010.4  321.42
  6473.7  323.69  7359.8  332.54  7656.4  347.28    7801  338.52  8141.1  369.41
  8591.3  349.62  8749.2  363.82  9046.1  380.57  9145.1   384.1  9158.2  384.23
#Mann= 20 ,-1 , 0
 -3056.9     .16       0 -3001.6     .05       0 -2721.4     .07       0
 -2622.6     .05       0 -2477.9     .16       0 -1664.8     .05       0
  -349.3     .05       0  1516.2     .05       0  2267.8     .12       0
  3604.3     .07       0    3802     .05       0  3900.8     .12       0
  4930.1     .03       0  5090.1     .05       0  6473.7     .16       0
  7359.8     .05       0  7656.4     .16       0  8749.2     .05       0
  9046.1     .16       0  9145.1     .05       0
#XS Ineff= 3 ,-1
 -1489.9  -359.9  346.18  3210.1  4060.1  319.01  5750.3  6818.7  332.67
Permanent Ineff=
       F       F       F
Bank Sta=4930.1,5090.1
XS Rating Curve= 0 ,0
Exp/Cntr=0.3,0.1

Type RM Length L Ch R = 1 ,660503  ,4727,4727,4727
BEGIN DESCRIPTION:
NAVASOTA RIVER 131
END DESCRIPTION:
XS GIS Cut Line= 4
      3555803.79      10458870.3      3555522.71     10458864.25
      3549916.77     10459359.33      3545139.48     10460946.66
#Sta/Elev= 30
  -908.9  375.58  -318.3  371.85    25.4  367.88   539.3  348.43  1641.6  354.52
  2013.8  332.13  2147.3  321.38  2637.8  316.86  2945.7  317.43  2958.7   317.4
  3015.6  317.25  3058.3  317.13  3290.2  316.77  3456.6  317.99  4934.4  319.76
  4984.4  308.38  5068.1  320.67  6084.4   322.1  6452.1  330.85  6941.6  329.43
  7450.9  337.86  7861.1  355.51  8587.7  368.39  8840.6  360.23  9148.8  368.67
  9465.4  362.11  9802.4  376.47  9907.9  380.03 10013.5  383.91 10034.1  384.23
#Mann= 20 ,-1 , 0
  -908.9     .16       0  -318.3     .05       0  2013.8      .1       0
  2147.3     .05       0  2637.8      .1       0  2945.7     .05       0
  2958.7      .1       0  3015.6     .07       0  3058.3     .05       0
  3290.2     .07       0  3456.6     .12       0  4934.4     .07       0
  5068.1     .12       0  6084.4     .05       0  6941.6     .16       0
  7450.9     .05       0  7861.1     .16       0  9802.4     .05       0
  9907.9     .16       0 10013.5     .05       0
Bank Sta=4934.4,5068.1
XS Rating Curve= 0 ,0
Exp/Cntr=0.3,0.1

Type RM Length L Ch R = 1 ,655776  ,1600,1600,1600
BEGIN DESCRIPTION:
NAVASOTA RIVER 134
END DESCRIPTION:
XS GIS Cut Line= 3
      3556162.74     10457480.22      3548652.59     10457850.59
      3545125.93     10460924.88
#Sta/Elev= 30
 -4036.8  377.42   -3547  358.63 -3231.8  352.94 -3051.2  351.65 -1322.9  351.15
 -1142.7  336.35  -982.5   348.6  -473.1  327.33  -274.8  322.58    40.8  320.63
   678.8  316.24  1101.8  316.35  1298.5   316.4  1645.3  316.49    2291  316.84
  3040.4  315.96  3271.1  315.84  4083.5  316.16  4922.3  318.79  4993.3  306.79
  5092.3  318.26  5723.6   320.7  6078.6  345.96  6368.2   361.3  6814.4  344.08
  6985.3  358.18  7225.5  346.04  7601.4     370  8114.7  382.13    8161  383.81
#Mann= 19 ,-1 , 0
 -4036.8     .05       0   -3547     .05       0 -3231.8     .08       0
 -3051.2     .05       0  -473.1      .1       0  -274.8     .16       0
    40.8     .05       0   678.8     .05       0  1101.8     .12       0
  1298.5     .05       0  1645.3     .12       0    2291     .05       0
  3040.4     .07       0  3271.1     .05       0  4083.5     .12       0
  4922.3     .07       0  5092.3     .05       0  6078.6     .16       0
  8114.7     .05       0
Bank Sta=4922.3,5092.3
XS Rating Curve= 0 ,0
Exp/Cntr=0.3,0.1

Type RM Length L Ch R = 1 ,654176  ,2119,2119,2119
BEGIN DESCRIPTION:
NAVASOTA RIVER 132
END DESCRIPTION:
XS GIS Cut Line= 3
      3556148.73     10457389.58      3547144.04     10457637.44
      3545779.95     10458200.69
#Sta/Elev= 30
 -4008.1  377.54 -3536.7  357.57 -3366.7  352.87 -3041.8  353.28 -1680.6  345.05
 -1280.4  351.86 -1130.4  338.13  -940.3  347.38  -270.1  330.46   -36.8  319.75
     716   312.5  1709.7  314.68  2345.9  317.85  2759.1   317.2  3144.6  313.88
  3437.7  315.38  4580.4  315.84  4931.9  317.01  4991.7  304.62  5034.6  314.64
  5103.8  317.56  5249.1  316.89  5421.4  322.74    5675  337.51  5843.8  335.12
    6046  349.45  6116.4  359.12  6159.7  373.72  6330.9  380.54  6475.8  384.63
#Mann= 20 ,-1 , 0
 -4008.1     .05       0 -3536.7     .08       0 -3366.7     .05       0
 -3041.8     .05       0  -270.1     .16       0   -36.8     .05       0
     716     .05       0  1709.7     .12       0  2345.9     .05       0
  2759.1     .12       0  3144.6     .07       0  3437.7     .05       0
  4580.4     .12       0  4931.9     .03       0  5103.8     .05       0
  5249.1     .05       0  5421.4     .16       0    5675     .05       0
  5843.8     .16       0  6330.9     .05       0
Bank Sta=4931.9,5103.8
XS Rating Curve= 0 ,0
Exp/Cntr=0.3,0.1

Type RM Length L Ch R = 1 ,652057  ,1869,1869,1869
BEGIN DESCRIPTION:
NAVASOTA RIVER 133
END DESCRIPTION:
XS GIS Cut Line= 3
       3556121.7     10457263.21      3547722.18     10456191.61
      3544796.76      10456284.9
#Sta/Elev= 30
 -3467.6  376.88   -2822  353.86 -2135.3  351.82 -2036.1  352.31  -846.4  350.46
  -171.2  350.55   495.6   325.9  1037.4  317.19  1166.3  316.95  1684.2  316.19
  1916.1  315.63    2128  315.96  2227.2   320.3  2459.6  331.17  2993.9  331.24
  3416.9  312.44  3804.1  317.96  4969.8  315.67  5009.8  303.85  5060.1  316.69
  5150.1  308.45  5180.2  317.18  5468.4  310.71  5849.6  316.03  6524.1   316.9
  6845.9  320.31  7311.2  334.19    7508  351.03  7761.5  384.72  7926.9  393.36
#Mann= 20 ,-1 , 0
 -3467.6     .05       0   -2822     .12       0 -2135.3     .08       0
 -2036.1     .05       0  -846.4     .05       0   495.6     .05       0
  1037.4     .12       0  1166.3     .05       0  1684.2     .07       0
  1916.1     .07       0    2128     .12       0  2227.2     .05       0
  3416.9     .12       0  3804.1     .12       0  4969.8     .07       0
  5060.1     .12       0  5849.6     .05       0  6524.1      .1       0
  6845.9     .05       0    7508     .16       0
Bank Sta=4969.8,5060.1
XS Rating Curve= 0 ,0
Exp/Cntr=0.3,0.1

Type RM Length L Ch R = 1 ,650188  ,1691,1691,1691
BEGIN DESCRIPTION:
NAVASOTA RIVER 135
END DESCRIPTION:
XS GIS Cut Line= 3
       3556110.6     10457170.51      3547583.59     10454811.52
      3544871.74     10454722.87
#Sta/Elev= 30
 -3847.3  375.96 -3310.8     357 -2555.7  349.57   -1789  351.79  -646.4  350.43
      73  327.05     261  323.98  2653.5  325.65  3384.9  314.55  3486.3  313.69
  3790.7  316.74  4082.8  319.81  4340.2  317.54  4949.7  316.36  4990.9  303.58
  5021.5  313.77  5041.5  308.45  5081.5  315.87  5258.3  315.33  5501.7  313.93
  6094.3  314.95  6291.8  315.69  6672.4  323.62  6884.4  344.89  7032.6  364.29
  7184.7  367.17  7294.8  354.06  7369.8  365.95  7502.8  379.22  7713.3  383.86
#Mann= 20 ,-1 , 0
 -3847.3     .05       0 -3310.8     .12       0 -2555.7     .05       0
   -1789     .05       0      73      .1       0     261     .05       0
  3384.9     .07       0  3486.3      .1       0  3790.7     .05       0
  4082.8     .05       0  4340.2     .12       0  4949.7     .07       0
  5081.5     .12       0  5258.3     .12       0  5501.7     .05       0
  6094.3      .1       0  6291.8     .05       0  6884.4     .16       0
  7184.7     .05       0  7369.8     .16       0
Bank Sta=4949.7,5081.5
XS Rating Curve= 0 ,0
Exp/Cntr=0.3,0.1