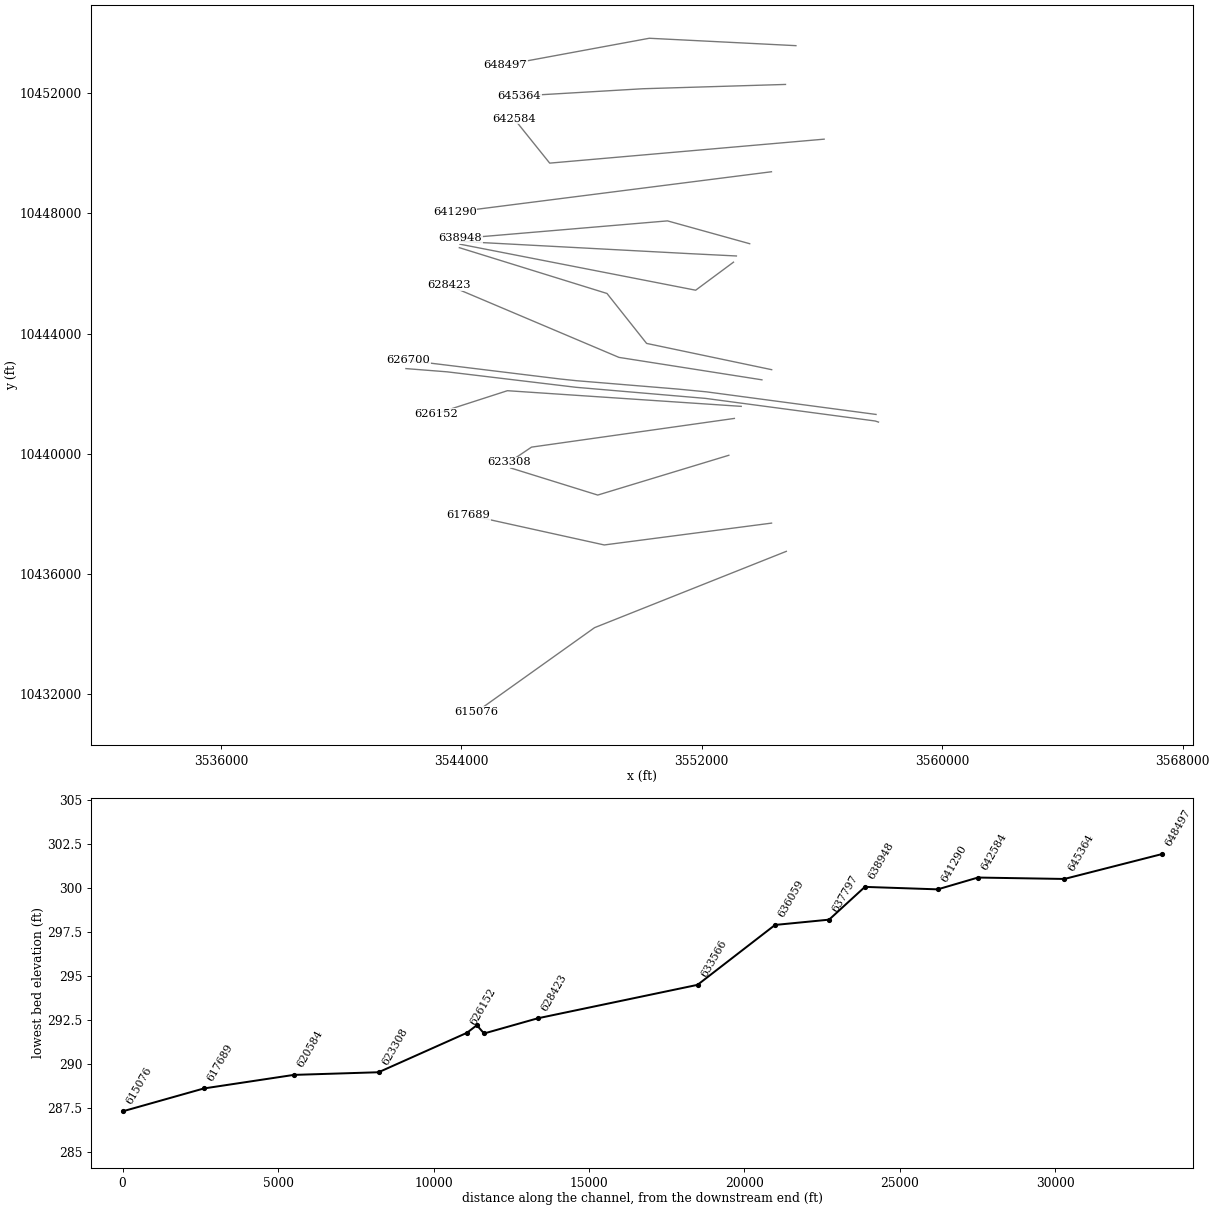
HEC-RAS study NAVASOTA RIVER.prj: NAVASOTA RIVER Base Level Engineering

--- NAVASOTA RIVER.g01 (geometry) --- (continued)

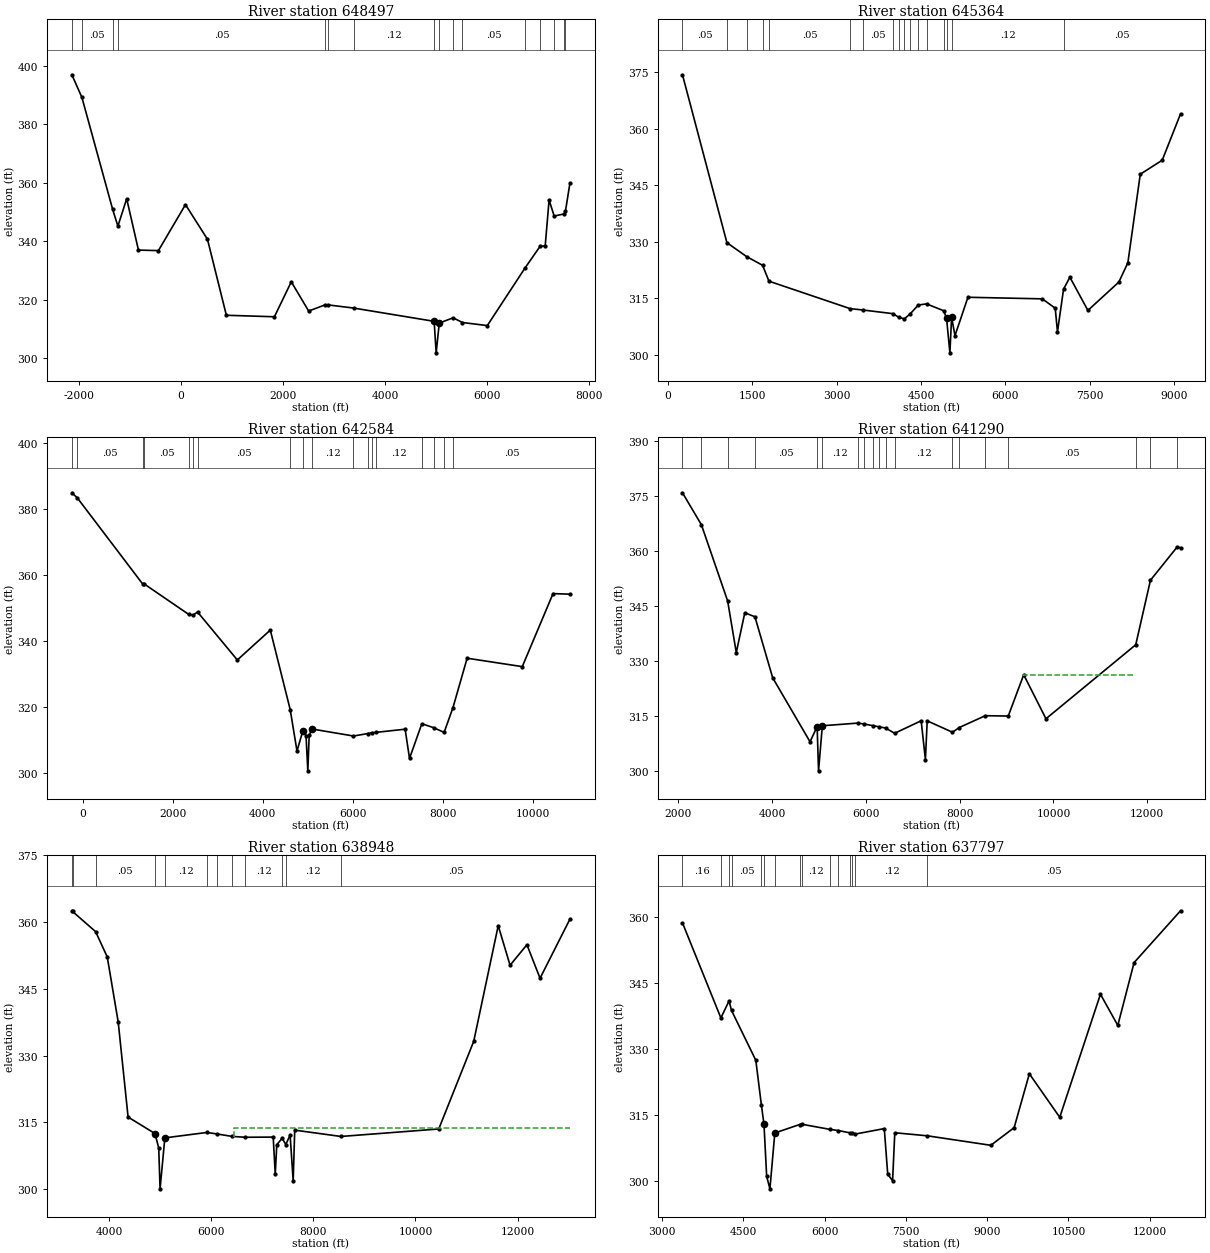
Type RM Length L Ch R = 1 ,648497  ,3133,3133,3133
BEGIN DESCRIPTION:
NAVASOTA RIVER 136
END DESCRIPTION:
XS GIS Cut Line= 3
      3555134.32     10453581.38      3550256.12     10453827.66
      3545465.73     10452942.48
#Sta/Elev= 30
 -2135.5   396.9 -1939.3  389.17 -1336.5   350.9 -1234.1  345.21 -1061.9  354.55
  -831.6  337.03  -440.3  336.84    89.5  352.56   520.1  340.73   890.6  314.76
  1831.8  314.25  2162.2  326.19  2502.6   316.2  2823.3  318.31    2888  318.29
  3385.3  317.22  4960.3  312.69  5000.2  301.93  5061.1  312.09  5331.5  313.89
  5515.5  312.29  6001.8  311.24  6741.2  330.92  7033.6  338.26    7136  338.47
  7212.2  354.14  7311.6  348.64  7511.2   349.4  7532.1  350.24  7620.4  359.91
#Mann= 16 ,-1 , 0
 -2135.5     .08       0 -1939.3     .05       0 -1336.5     .16       0
 -1234.1     .05       0  2823.3     .07       0    2888     .05       0
  3385.3     .12       0  4960.3     .07       0  5061.1     .12       0
  5331.5     .07       0  5515.5     .05       0  6741.2     .16       0
  7033.6     .05       0  7311.6     .07       0  7511.2     .16       0
  7532.1     .05       0
#XS Ineff= 2 , 0
       0  2162.2  326.19               0
Permanent Ineff=
       F       F
Bank Sta=4960.3,5061.1
XS Rating Curve= 0 ,0
Exp/Cntr=0.3,0.1

Type RM Length L Ch R = 1 ,645364  ,2780,2780,2780
BEGIN DESCRIPTION:
NAVASOTA RIVER 138
END DESCRIPTION:
XS GIS Cut Line= 3
       3554787.4      10452291.2      3550044.05     10452148.17
      3545937.37      10451906.3
#Sta/Elev= 30
   254.5  374.37  1044.9  329.78  1395.5  326.08  1679.1  323.78  1793.3  319.55
  3236.2  312.26  3458.7  311.91  4000.7  310.92    4102  309.94  4200.7  309.55
  4299.5  310.78  4450.3  313.22    4596  313.52  4899.6  311.71  4951.9  309.75
  5011.7  300.52    5042  309.94  5102.1  305.09  5332.5  315.28  6654.8  314.86
  6885.2  312.37  6925.3  306.11  7033.3  317.43  7145.7  320.61  7466.2  311.78
  8017.2  319.32  8177.4  324.44  8397.8  347.95  8788.5  351.68  9113.8  363.98
#Mann= 17 ,-1 , 0
   254.5     .05       0  1044.9     .16       0  1395.5     .05       0
  1679.1     .16       0  1793.3     .05       0  3236.2     .12       0
  3458.7     .05       0  4000.7     .07       0    4102     .05       0
  4200.7      .1       0  4299.5     .05       0  4450.3     .12       0
    4596     .07       0  4899.6     .12       0  4951.9     .07       0
    5042     .12       0  7033.3     .05       0
Bank Sta=4951.9,5042
XS Rating Curve= 0 ,0
Exp/Cntr=0.3,0.1

Type RM Length L Ch R = 1 ,642584  ,1294,1294,1294
BEGIN DESCRIPTION:
NAVASOTA RIVER 139
END DESCRIPTION:
XS GIS Cut Line= 3
      3556073.39     10450470.54      3546941.88       10449673.
       3545754.4     10451152.14
#Sta/Elev= 30
  -239.4  384.82    -117  383.24  1334.5  357.17  1368.8  357.19  2354.9  347.99
  2453.8  347.78  2552.6   348.7  3435.8  334.18  4168.2  343.23    4610  319.15
  4760.8  306.62  4891.3   312.7  4961.6  311.28  5001.5   300.6  5031.9  311.31
  5089.7  313.28  6015.8  311.15  6330.6  311.88    6417  312.11  6507.7  312.24
    7163  313.21  7260.3  304.37  7533.8  314.86  7794.9  313.68  8028.8  312.24
    8225  319.72  8540.2  334.71  9765.1  332.16 10448.4  354.28 10823.7  354.11
#Mann= 18 ,-1 , 0
  -239.4     .08       0    -117     .05       0  1334.5     .16       0
  1368.8     .05       0  2354.9      .1       0  2453.8     .15       0
  2552.6     .05       0    4610     .12       0  4891.3     .07       0
  5089.7     .12       0  6015.8     .05       0  6330.6     .12       0
    6417     .05       0  6507.7     .12       0  7533.8     .16       0
  7794.9     .05       0  8028.8     .16       0    8225     .05       0
Bank Sta=4891.3,5089.7
XS Rating Curve= 0 ,0
Exp/Cntr=0.3,0.1

Type RM Length L Ch R = 1 ,641290  ,2342,2342,2342
BEGIN DESCRIPTION:
NAVASOTA RIVER 146
END DESCRIPTION:
XS GIS Cut Line= 2
      3554320.32     10449386.05      3543786.75     10448044.94
#Sta/Elev= 30
  2090.7  375.97    2494  367.24  3054.3  346.37  3238.1  332.28  3419.6  343.14
  3635.3  342.07  4014.3  325.37  4810.7  307.87  4961.9  312.04  4991.9  299.93
  5072.8  312.26  5835.8  312.99  5963.9  312.73  6162.2  312.26  6291.3  311.95
    6420  311.64  6614.7   310.2  7179.7  313.62  7270.4  303.02  7308.7   313.6
  7847.6  310.48    7993  311.78  8547.8  315.01  9036.7  314.91  9366.2  326.21
  9840.7  314.17 11754.9  334.41 12068.1  352.05 12632.4  361.06 12709.3  360.96
#Mann= 19 ,-1 , 0
  2090.7     .05       0    2494     .05       0  3054.3     .16       0
  3635.3     .05       0  4961.9     .03       0  5072.8     .12       0
  5835.8     .12       0  5963.9     .07       0  6162.2     .07       0
  6291.3     .12       0    6420     .07       0  6614.7     .12       0
  7847.6     .16       0    7993     .05       0  8547.8     .16       0
  9036.7     .05       0 11754.9     .16       0 12068.1     .05       0
 12632.4     .16       0
#XS Ineff= 2 ,-1
  7179.7  9357.1  313.62  9357.1 11726.1  326.07
Permanent Ineff=
       F       F
Bank Sta=4961.9,5072.8
XS Rating Curve= 0 ,0
Exp/Cntr=0.3,0.1

Type RM Length L Ch R = 1 ,638948  ,1151,1151,1151
BEGIN DESCRIPTION:
NAVASOTA RIVER 161
END DESCRIPTION:
XS GIS Cut Line= 3
        3553596.     10446991.71      3550861.59     10447751.27
      3543973.14      10447167.3
#Sta/Elev= 30
  3272.5  362.55  3284.6   362.4  3737.1  357.86  3965.1  352.17  4179.5  337.55
    4373   316.2  4899.2  312.49  4972.8  309.25  4999.1  300.07  5092.8  311.52
  5916.8  312.74  6114.3   312.4  6404.7  311.86  6663.9  311.66  7213.9   311.7
    7254  303.39  7284.1  309.98  7388.9  311.43    7461  310.03  7545.1  312.15
  7605.3  301.87  7635.4  313.26  8541.3  311.84 10455.5  313.52 11140.1  333.22
 11619.6   359.2 11851.5  350.31 12181.6  354.92 12438.5  347.39 13023.6  360.67
#Mann= 12 ,-1 , 0
  3272.5     .05       0  3284.6     .16       0  3737.1     .05       0
  4899.2     .07       0  5092.8     .12       0  5916.8     .07       0
  6114.3     .12       0  6404.7     .07       0  6663.9     .12       0
  7388.9     .07       0    7461     .12       0  8541.3     .05       0
#XS Ineff= 2 , 0
       0                  6451.1       0  313.79
Permanent Ineff=
       F       F
Bank Sta=4899.2,5092.8
XS Rating Curve= 0 ,0
Exp/Cntr=0.3,0.1

Type RM Length L Ch R = 1 ,637797  ,1738,1738,1738
BEGIN DESCRIPTION:
NAVASOTA RIVER 162
END DESCRIPTION:
XS GIS Cut Line= 3
       3553154.1     10446583.67      3551533.22     10446664.66
      3543976.66     10447067.59
#Sta/Elev= 30
  3377.1  358.57  4086.1  336.99  4237.1  340.86    4282  338.69  4730.8  327.38
  4834.3  317.14    4881   312.9    4931  301.03  4990.9  298.21  5081.2  310.88
  5537.2   312.8  5573.6  312.88  6100.3   311.7  6255.8  311.44  6467.6  310.91
    6513  310.95  6569.6  310.65  7101.1  311.88  7164.2  301.57  7254.3  300.03
  7295.1  310.94  7898.1  310.24  9066.9  308.09  9497.5   312.1  9777.9  324.32
 10338.7  314.45 11089.8  342.37 11410.2   335.3 11710.6  349.55 12567.3  361.31
#Mann= 15 ,-1 , 0
  3377.1     .16       0  4086.1     .05       0  4237.1     .16       0
    4282     .05       0  4834.3     .12       0    4881     .07       0
  5081.2     .12       0  5537.2     .07       0  5573.6     .12       0
  6100.3     .07       0  6255.8     .12       0  6467.6     .05       0
    6513     .07       0  6569.6     .12       0  7898.1     .05       0
#XS Ineff= 2 ,-1
  7101.1  9777.9  311.88  9777.9 10739.3  324.32
Permanent Ineff=
       F       F
Bank Sta=4881,5081.2
XS Rating Curve= 0 ,0
Exp/Cntr=0.3,0.1

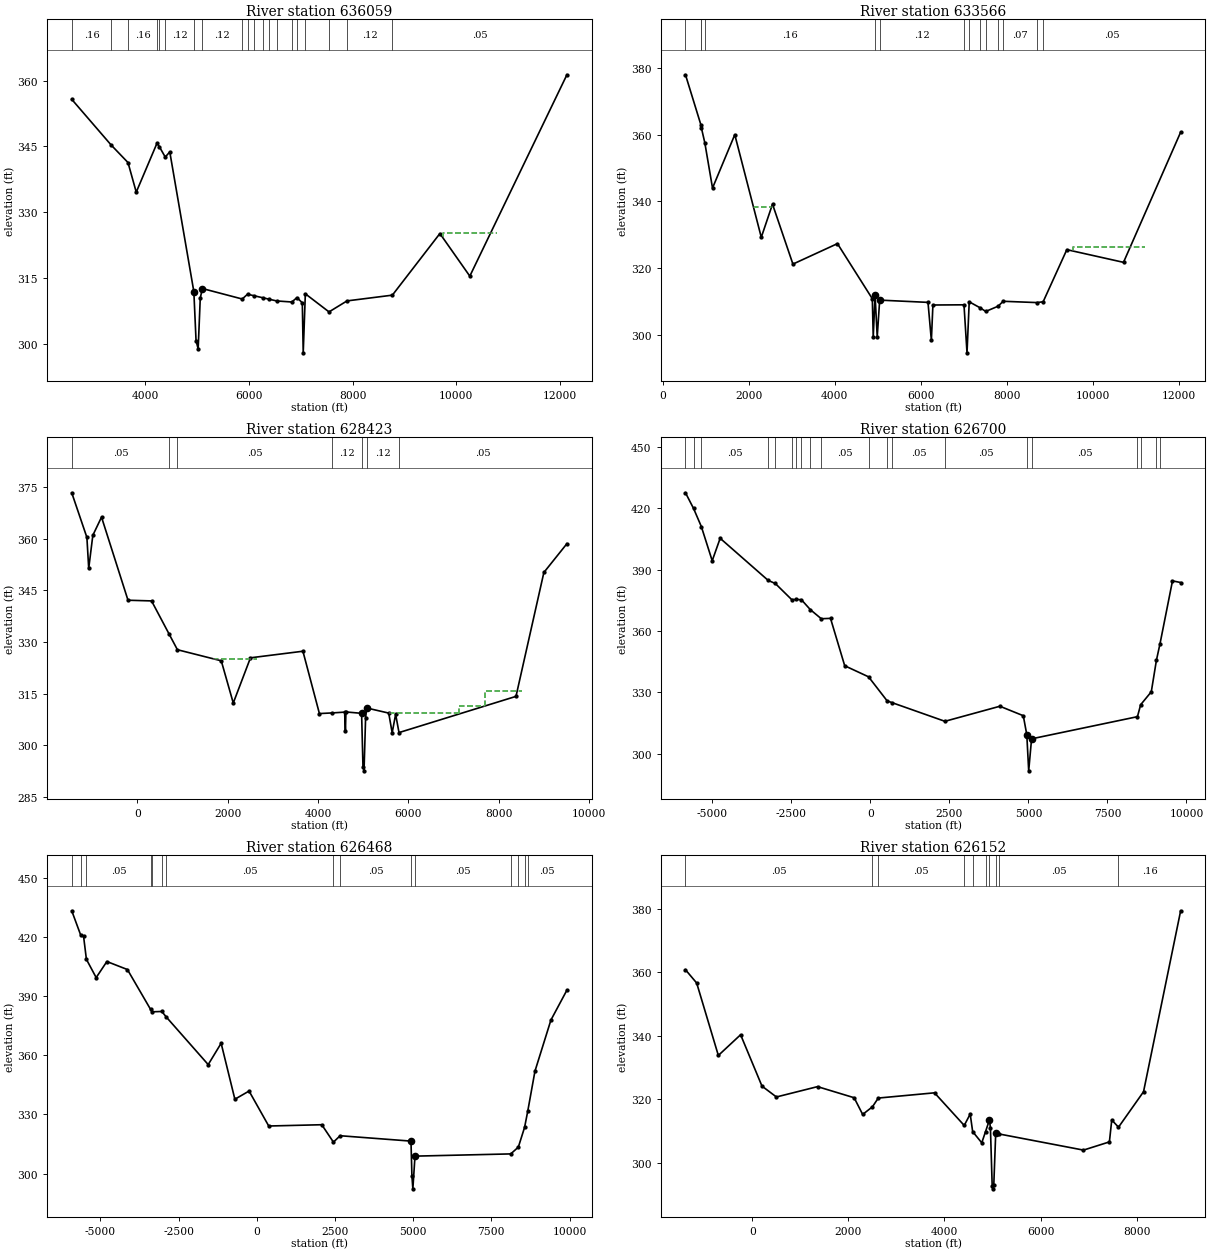
Type RM Length L Ch R = 1 ,636059  ,2493,2493,2493
BEGIN DESCRIPTION:
NAVASOTA RIVER 163
END DESCRIPTION:
XS GIS Cut Line= 3
      3553057.32     10446377.85      3551798.65      10445444.7
      3543958.18     10446975.75
#Sta/Elev= 30
  2577.9  355.75  3338.7  345.32  3663.8  341.32  3822.7  334.57  4224.7  345.78
  4267.2  344.97  4382.2  342.58  4470.1  343.75  4934.2  311.88  4976.7  300.69
  5017.5  298.82  5058.2  310.42  5099.1  312.58  5868.2  310.19  5969.7  311.28
  6091.1  310.95    6260  310.49    6389  310.14  6532.3  309.75  6825.2  309.51
  6924.1  310.51  7027.2  309.32  7044.8  297.91  7085.8  311.38  7542.6  307.25
  7890.2  309.76  8765.1  311.07  9682.3  325.13 10259.6  315.41 12133.3  361.35
#Mann= 20 ,-1 , 0
  2577.9     .16       0  3338.7     .12       0  3663.8     .16       0
  4224.7     .05       0  4267.2     .16       0  4382.2     .12       0
  4934.2     .07       0  5099.1     .12       0  5868.2     .07       0
  5969.7     .12       0  6091.1     .07       0    6260     .12       0
    6389     .05       0  6532.3     .07       0  6825.2     .12       0
  6924.1     .07       0  7085.8     .12       0  7542.6     .05       0
  7890.2     .12       0  8765.1     .05       0
#XS Ineff= 2 ,-1
  6924.1  9733.8  310.51  9733.8 10785.4  325.26
Permanent Ineff=
       F       F
Bank Sta=4934.2,5099.1
XS Rating Curve= 0 ,0
Exp/Cntr=0.3,0.1

Type RM Length L Ch R = 1 ,633566  ,5143,5143,5143
BEGIN DESCRIPTION:
NAVASOTA RIVER 164
END DESCRIPTION:
XS GIS Cut Line= 4
      3554327.51     10442800.62      3550166.11     10443674.53
       3548848.4     10445335.99       3543935.3     10446859.73
#Sta/Elev= 30
   532.9  378.05   890.5  363.05   903.4  362.07   982.3  357.64  1161.7  344.02
  1679.5  360.05  2295.9  329.22  2556.8  339.18  3031.6  321.17  4067.1  327.32
  4878.6  310.76  4899.4  299.24  4942.7  311.78  4992.3  299.29  5049.4  310.35
  6173.2  309.67  6251.7  298.22  6287.5  308.88  7010.4  308.94  7080.6  294.51
  7132.1  309.84  7385.7  308.04  7516.5  306.95  7803.9  308.52  7922.2     310
  8703.3  309.61  8851.3  309.85  9402.4  325.51 10720.3   321.7 12049.6  360.81
#Mann= 14 ,-1 , 0
   532.9     .05       0   890.5      .1       0   903.4     .05       0
   982.3     .16       0  4942.7     .05       0  5049.4     .12       0
  7010.4     .07       0  7132.1     .12       0  7385.7     .16       0
  7516.5     .05       0  7803.9     .12       0  7922.2     .07       0
  8703.3     .12       0  8851.3     .05       0
#XS Ineff= 4 ,-1
  2556.8  4067.1  327.32  2118.2  2556.8  338.31  6173.2    9538  309.67
    9538   11230  326.17
Permanent Ineff=
       F       F       F       F
Bank Sta=4942.7,5049.4
XS Rating Curve= 0 ,0
Exp/Cntr=0.3,0.1

Type RM Length L Ch R = 1 ,628423  ,1723,1723,1723
BEGIN DESCRIPTION:
NAVASOTA RIVER 147
END DESCRIPTION:
XS GIS Cut Line= 3
      3554003.49     10442462.94      3549246.57     10443209.46
        3543587.     10445605.23
#Sta/Elev= 30
 -1450.6  373.35 -1115.2  360.39 -1074.7  351.39  -983.6     361  -791.2  366.28
  -205.2  342.15     316  341.95   705.4  332.31   888.4  327.78  1859.3  324.56
    2125   312.3  2505.7  325.43  3666.6  327.34  4031.8  309.24  4321.1  309.43
  4589.8  309.66  4607.3  304.12  4618.9  309.71  4965.7  309.31  4995.9  293.87
  5019.4  292.61  5054.2  308.02  5077.9  310.86  5565.9  309.38  5642.4  303.66
  5718.9  309.03  5793.6  303.72    8383  314.23  9000.3  350.21  9510.3  358.57
#Mann= 7 ,-1 , 0
 -1450.6     .05       0   705.4     .16       0   888.4     .05       0
  4321.1     .12       0  4965.7     .07       0  5077.9     .12       0
  5793.6     .05       0
#XS Ineff= 4 ,-1
  1666.4  2641.1  325.22  5565.9  7115.8  309.38  7115.8  7694.7  311.32
  7694.7  8517.7  315.76
Permanent Ineff=
       F       F       F       F
Bank Sta=4965.7,5077.9
XS Rating Curve= 0 ,0
Exp/Cntr=0.3,0.1

Type RM Length L Ch R = 1 ,626700  ,232,232,232
BEGIN DESCRIPTION:
NAVASOTA RIVER 137
END DESCRIPTION:
XS GIS Cut Line= 6
      3557800.31     10441311.17      3552157.89     10442063.02
      3551192.55      10442156.3      3547839.06     10442433.24
      3547295.15     10442489.98      3542239.92     10443107.93
#Sta/Elev= 30
 -5851.5  427.44 -5595.6  419.77 -5350.2  410.97 -5005.9  394.27 -4754.4  405.23
 -3234.2  384.67 -3009.9  383.17 -2488.4  375.27 -2349.9  375.37 -2184.7  375.27
 -1900.5   370.4 -1555.3  365.98 -1262.8  366.15  -813.7  343.03   -59.5  337.63
   529.2  325.88     698  324.95  2356.4  315.92  4096.3  323.27  4836.3  318.65
  4947.2   309.4  5007.3  291.75  5098.3  307.37  8448.2  318.18  8549.8  324.01
  8886.3  330.33  9048.5  345.72  9161.6  353.74  9556.7  384.45  9815.3  383.65
#Mann= 20 ,-1 , 0
 -5851.5     .05       0 -5595.6     .08       0 -5350.2     .05       0
 -3234.2     .08       0 -3009.9     .05       0 -2488.4     .08       0
 -2349.9     .05       0 -2184.7     .08       0 -1900.5     .05       0
 -1555.3     .05       0   -59.5     .05       0   529.2     .08       0
     698     .05       0  2356.4     .05       0  4947.2     .03       0
  5098.3     .05       0  8448.2     .08       0  8549.8     .05       0
  9048.5     .08       0  9161.6     .05       0
Bank Sta=4947.2,5098.3
XS Rating Curve= 0 ,0
Exp/Cntr=0.3,0.1

Type RM Length L Ch R = 1 ,626468  ,316,316,316
BEGIN DESCRIPTION:
NAVASOTA RIVER 160
END DESCRIPTION:
XS GIS Cut Line= 6
      3557881.77     10441056.81      3557771.23      10441093.1
      3552131.76     10441844.56       3547818.6     10442214.18
      3543528.93     10442728.85      3542157.73      10442836.7
#Sta/Elev= 30
 -5915.7  433.26 -5631.7  421.04 -5537.9  420.37 -5446.7  408.63 -5134.4  399.37
 -4792.4  407.52 -4135.7  403.45 -3396.5  383.28 -3348.5  382.01 -3036.4  382.19
 -2889.5  379.31   -1553  355.24 -1139.4  366.05  -700.3  337.67  -246.6  341.82
   382.3  324.09  2078.3  324.74  2450.6  315.91  2665.2  319.16  4929.7  316.43
  4959.9  298.82  4989.9  292.22  5058.3  308.81  8119.1  309.94  8362.1  313.38
  8562.1  323.43  8661.6  331.49  8893.2   351.9  9404.1  377.85    9915     393
#Mann= 15 ,-1 , 0
 -5915.7      .1       0 -5631.7     .08       0 -5446.7     .05       0
 -3396.5     .08       0 -3348.5     .05       0 -3036.4     .08       0
 -2889.5     .05       0  2450.6     .08       0  2665.2     .05       0
  4929.7     .03       0  5058.3     .05       0  8119.1     .08       0
  8362.1     .05       0  8562.1     .08       0  8661.6     .05       0
Bank Sta=4929.7,5058.3
XS Rating Curve= 0 ,0
Exp/Cntr=0.3,0.1

Type RM Length L Ch R = 1 ,626152  ,2844,2844,2844
BEGIN DESCRIPTION:
NAVASOTA RIVER 148
END DESCRIPTION:
XS GIS Cut Line= 3
      3553314.48      10441580.2      3545534.58     10442101.03
      3543147.43     10441330.63
#Sta/Elev= 30
 -1388.9  360.86   -1156  356.68    -705  333.84  -241.7  340.37   203.4  324.17
   503.4  320.75  1359.6  324.01  2121.3  320.51  2298.7  315.24  2501.8  317.65
  2623.8  320.41  3793.9  322.06  4412.4  311.77  4536.7  315.37    4588  309.83
  4777.3   306.3  4856.3  309.85  4937.6  313.54  4957.7  310.99  4994.1  292.82
  5007.5  291.79  5027.8  293.11  5067.9  309.43  5143.9  309.07  6894.4     304
  7433.8  306.59  7482.8  313.51    7623  311.22    8144   322.4  8916.8  379.45
#Mann= 10 ,-1 , 0
 -1388.9     .05       0  2501.8     .08       0  2623.8     .05       0
  4412.4     .16       0    4588     .05       0  4856.3     .16       0
  4937.6     .07       0  5067.9     .16       0  5143.9     .05       0
    7623     .16       0
Bank Sta=4937.6,5067.9
XS Rating Curve= 0 ,0
Exp/Cntr=0.3,0.1

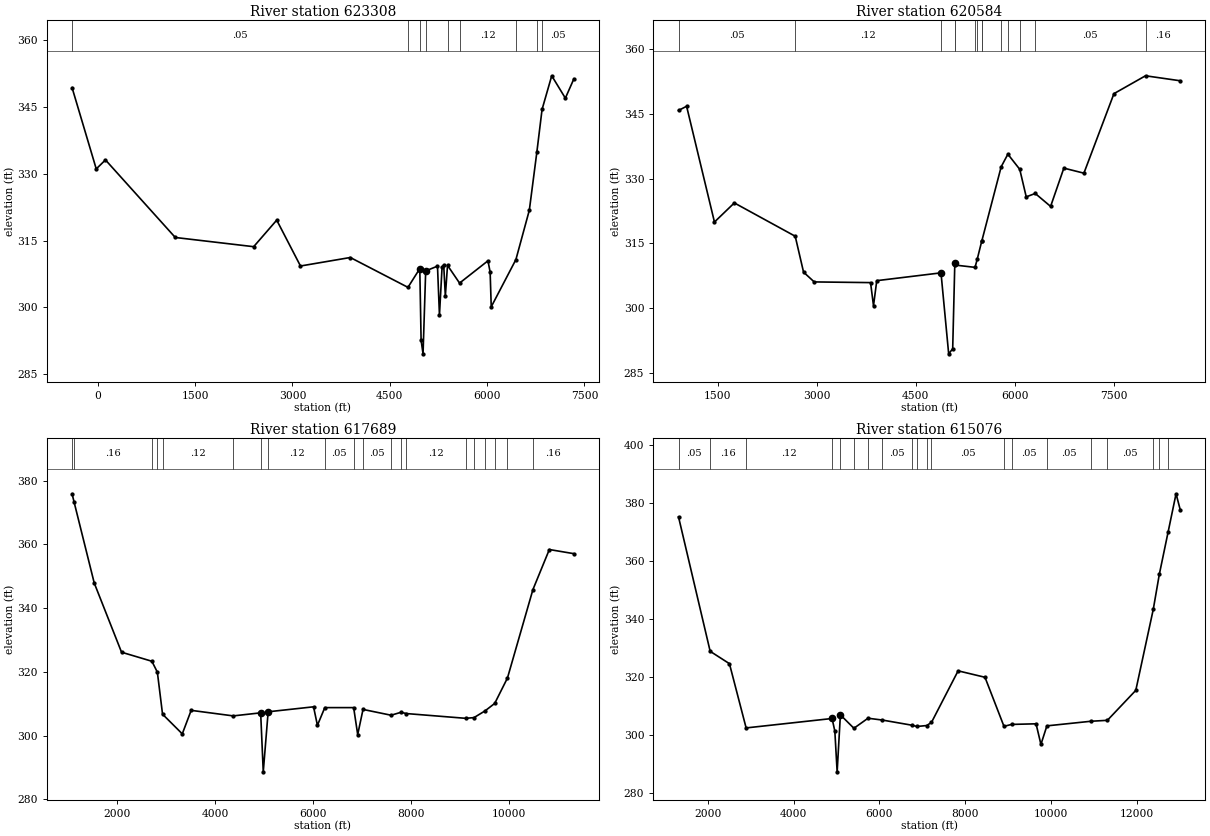
Type RM Length L Ch R = 1 ,623308  ,2724,2724,2724
BEGIN DESCRIPTION:
NAVASOTA RIVER 149
END DESCRIPTION:
XS GIS Cut Line= 3
      3553086.64     10441178.71      3546337.54     10440223.86
      3545577.98     10439713.87
#Sta/Elev= 30
    -395  349.37   -22.5  331.11   119.5  333.13  1195.3   315.7    2403  313.63
  2758.2   319.6  3124.2  309.29  3891.8   311.2  4780.2  304.49  4962.4   308.7
  4982.6   292.6  5012.6  289.55  5053.3  308.18  5235.1  309.26  5265.4  298.23
  5305.7  309.04  5330.8  309.53  5356.2  302.53  5389.6  309.43  5575.2  305.45
  6012.7  310.46  6046.3  307.91  6063.2  300.12  6443.4  310.74  6650.1  321.83
  6765.3   334.8  6846.5  344.49  6995.2  352.04  7205.2  347.01  7336.2  351.34
#Mann= 9 ,-1 , 0
    -395     .05       0  4780.2     .12       0  4962.4     .07       0
  5053.3     .12       0  5389.6     .05       0  5575.2     .12       0
  6443.4     .05       0  6765.3     .16       0  6846.5     .05       0
Bank Sta=4962.4,5053.3
XS Rating Curve= 0 ,0
Exp/Cntr=0.3,0.1

Type RM Length L Ch R = 1 ,620584  ,2895,2895,2895
BEGIN DESCRIPTION:
NAVASOTA RIVER 286
END DESCRIPTION:
XS GIS Cut Line= 3
      3552902.19     10439952.58      3548540.23      10438628.8
      3545643.09     10439529.41
#Sta/Elev= 30
   910.2  345.78  1032.2  346.75  1453.7  319.93  1754.3  324.36  2675.7  316.64
  2801.8  308.32    2963  306.06  3815.5   305.9  3860.1  300.54  3909.5  306.35
  4881.4  308.16  4997.5   289.4  5058.3  290.57  5090.4  310.38  5097.9  309.96
  5396.2  309.43    5429  311.28  5498.5  315.56  5499.1  315.55  5791.9  332.73
  5893.2  335.65  6072.9  332.14  6171.1  325.76  6307.2  326.55  6539.7  323.55
  6740.2  332.42  7043.7  331.25  7498.2  349.67  7975.7  353.81  8502.5  352.65
#Mann= 14 ,-1 , 0
   910.2     .05       0  2675.7     .12       0  4881.4     .07       0
  5090.4     .12       0  5097.9     .05       0  5396.2     .07       0
    5429     .05       0  5498.5     .07       0  5499.1     .12       0
  5791.9     .16       0  5893.2     .12       0  6072.9     .16       0
  6307.2     .05       0  7975.7     .16       0
Bank Sta=4881.4,5090.4
XS Rating Curve= 0 ,0
Exp/Cntr=0.3,0.1

Type RM Length L Ch R = 1 ,617689  ,2613,2613,2613
BEGIN DESCRIPTION:
NAVASOTA RIVER 287
END DESCRIPTION:
XS GIS Cut Line= 3
      3554323.69     10437695.65      3548757.24     10436968.65
      3544233.07     10437966.79
#Sta/Elev= 30
  1078.7  375.91  1121.8   373.2  1531.7  347.88  2088.8  326.18  2708.4  323.34
  2820.4  319.92  2926.2  306.72  3329.2  300.55  3510.8  307.93  4369.5  306.19
  4929.8  307.15  4982.9  288.63  5082.7  307.48  6009.9  309.04  6088.8  303.23
  6239.5  308.79  6828.7  308.79  6911.4  300.33    7020  308.22  7593.3   306.4
  7797.5  307.33  7899.6  306.93  9116.4  305.43  9285.8  305.65  9510.5  307.75
  9709.4  310.11  9969.6  318.09 10489.3  345.83 10824.6  358.41 11325.4  357.11
#Mann= 20 ,-1 , 0
  1078.7     .05       0  1121.8     .16       0  2708.4     .12       0
  2820.4     .16       0  2926.2     .12       0  4369.5     .12       0
  4929.8     .07       0  5082.7     .12       0  6239.5     .05       0
  6828.7     .12       0    7020     .05       0  7593.3     .16       0
  7797.5     .12       0  7899.6     .12       0  9116.4     .16       0
  9285.8     .16       0  9510.5     .05       0  9709.4     .16       0
  9969.6     .05       0 10489.3     .16       0
Bank Sta=4929.8,5082.7
XS Rating Curve= 0 ,0
Exp/Cntr=0.3,0.1

Type RM Length L Ch R = 1 ,615076  ,2203,2203,2203
BEGIN DESCRIPTION:
NAVASOTA RIVER 288
END DESCRIPTION:
XS GIS Cut Line= 3
      3554815.57     10436756.44      3548435.34     10434217.36
      3544507.36     10431417.87
#Sta/Elev= 30
    1321  375.21  2057.9  328.88  2506.8  324.62  2895.7  302.47    4898  305.72
  4962.5  301.37  5016.1  287.33  5091.7  306.98  5406.8  302.35  5735.1  305.81
  6070.8  305.18  6756.3  303.41  6875.3  302.97  7102.9  303.29  7214.4  304.38
  7834.5  322.15  8460.4  319.93  8902.8  303.02  9081.9  303.68  9650.4  303.89
  9763.7  296.79  9902.8  303.18 10930.4  304.77   11312  305.09 11973.8  315.42
 12380.6  343.31   12522  355.42 12728.5  370.13 12911.8  383.19 13011.4  377.56
#Mann= 20 ,-1 , 0
    1321     .05       0  2057.9     .16       0  2895.7     .12       0
    4898     .07       0  5091.7     .12       0  5406.8     .05       0
  5735.1     .12       0  6070.8     .05       0  6756.3     .16       0
  6875.3     .12       0  7102.9     .16       0  7214.4     .05       0
  8902.8     .12       0  9081.9     .05       0  9902.8     .05       0
 10930.4     .12       0   11312     .05       0 12380.6     .16       0
   12522     .05       0 12728.5     .05       0
#XS Ineff= 2 , 0
       0                  7834.5       0  322.15
Permanent Ineff=
       F       F
Bank Sta=4898,5091.7
XS Rating Curve= 0 ,0
Exp/Cntr=0.3,0.1