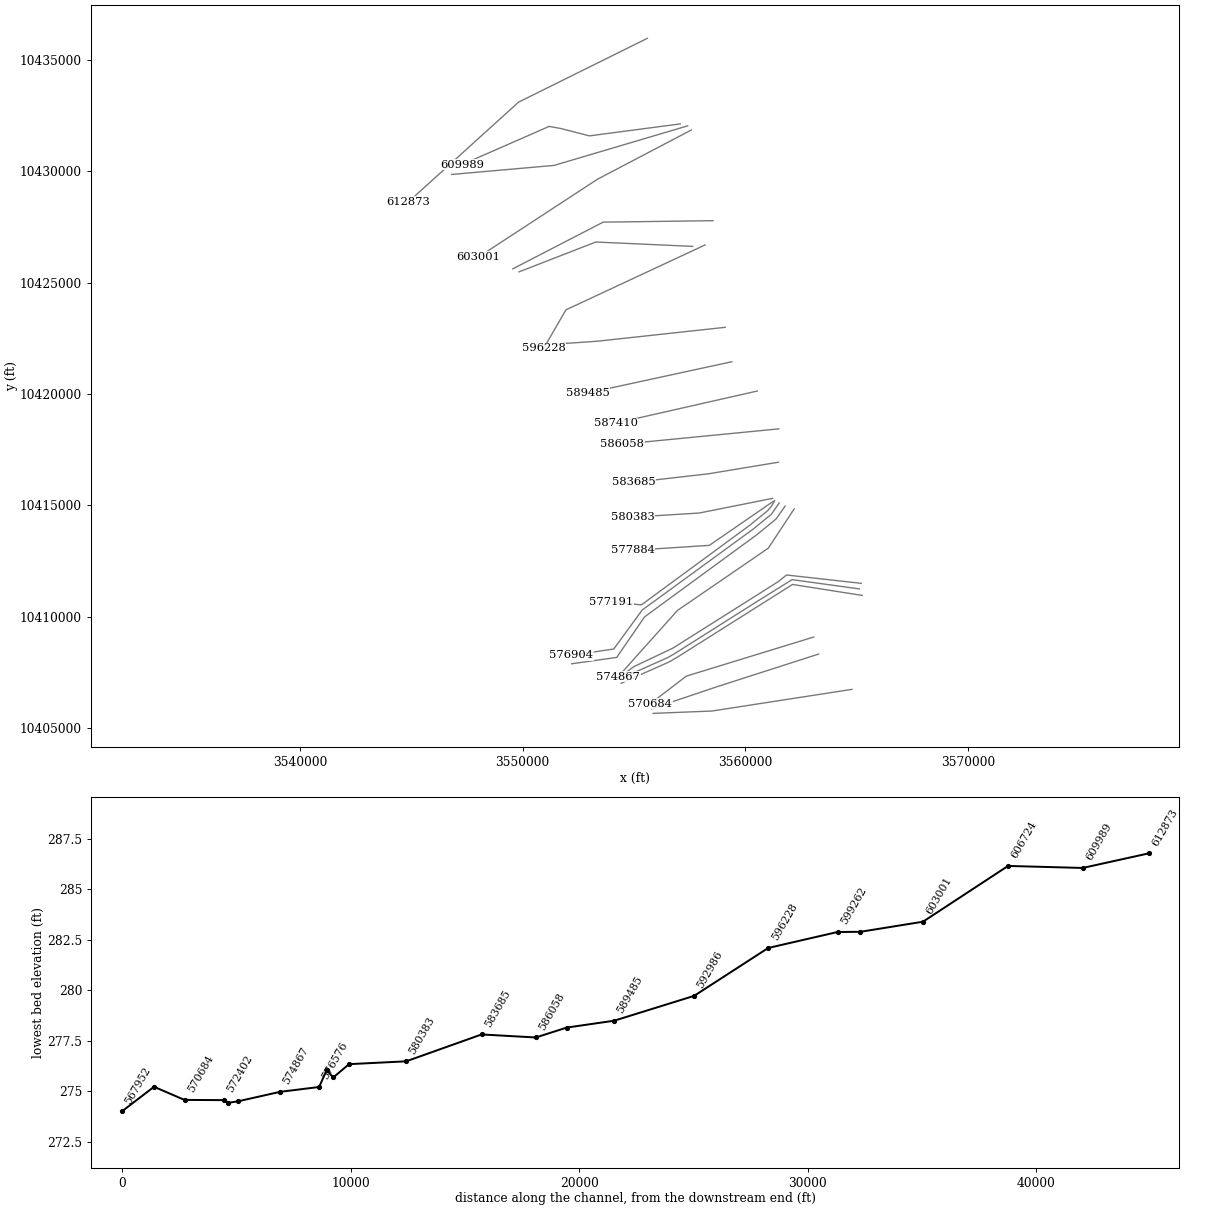
HEC-RAS study NAVASOTA RIVER.prj: NAVASOTA RIVER Base Level Engineering

--- NAVASOTA RIVER.g01 (geometry) --- (continued)

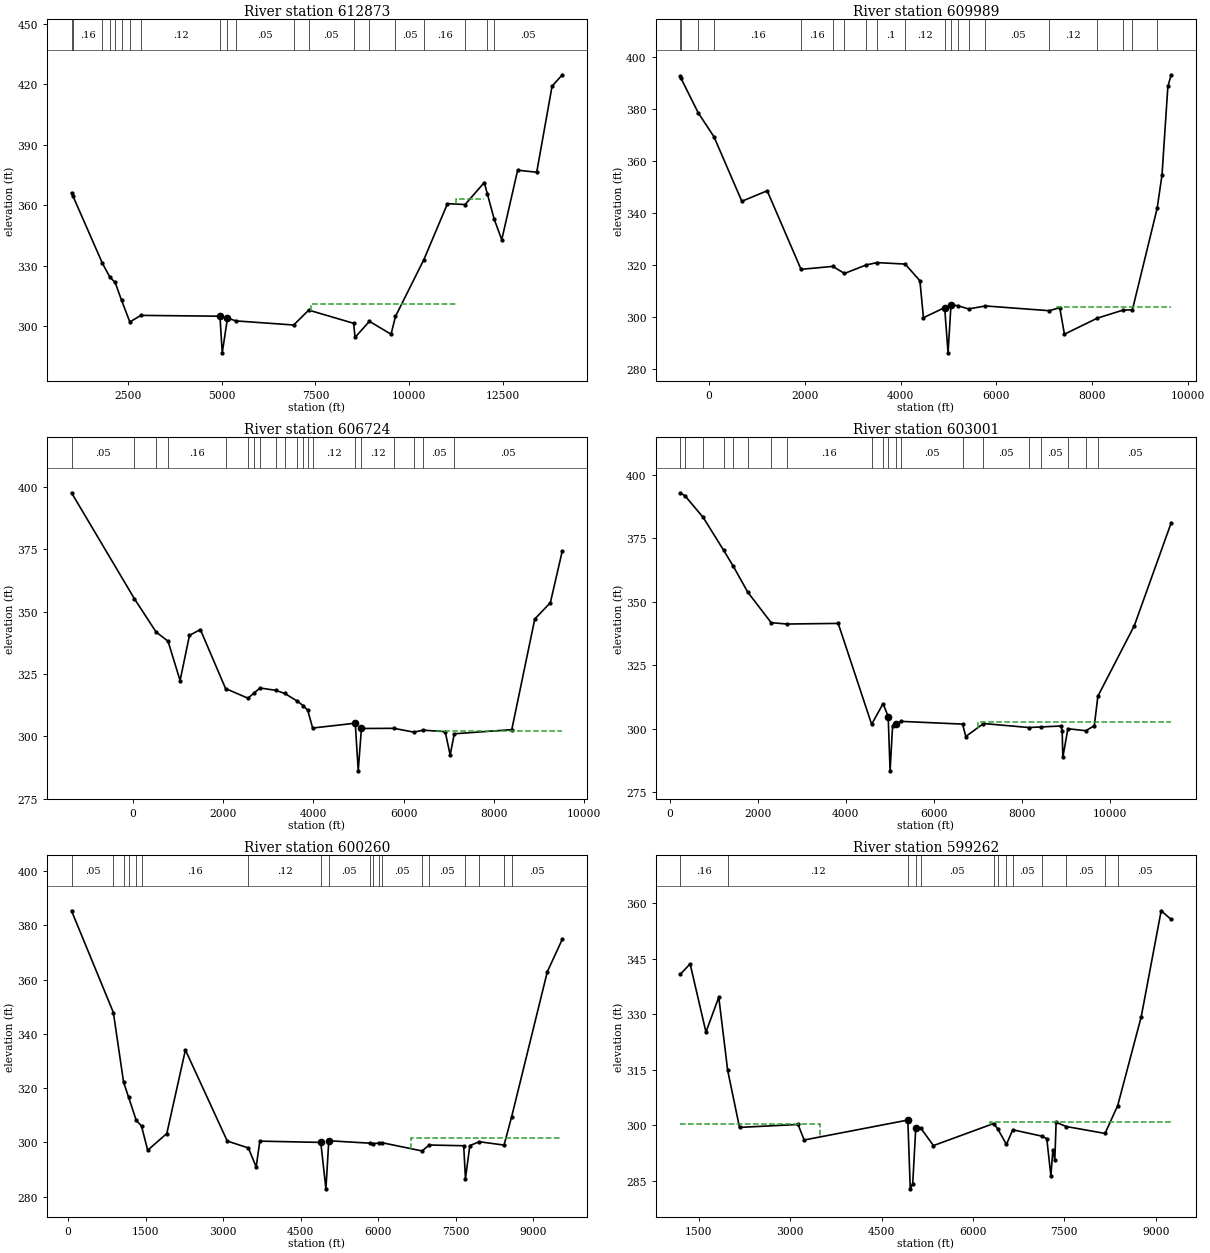
Type RM Length L Ch R = 1 ,612873  ,2884,2884,2884
BEGIN DESCRIPTION:
NAVASOTA RIVER 289
END DESCRIPTION:
XS GIS Cut Line= 3
      3555596.79     10435966.49      3549815.54     10433101.91
      3544870.92     10428625.98
#Sta/Elev= 30
   977.6  366.11  1014.3  364.56  1802.5  331.21  2007.1  324.15  2141.1  321.78
  2315.5  312.84  2536.3  302.09  2833.9  305.34  4945.8  304.93  5007.3  286.77
  5147.6  304.05  5372.6   302.6  6917.3  300.57  7319.9  307.95  8520.1  301.41
  8557.8  294.43  8942.5  302.39  9520.9  295.99  9638.7  304.82 10396.6  332.94
 11028.8  360.72 11499.8   360.3 12012.8   371.2   12093   365.7 12277.4  353.06
 12479.9  342.86   12905  377.31 13414.6  376.31 13825.5  418.97 14099.2  424.62
#Mann= 20 ,-1 , 0
   977.6     .05       0  1014.3     .16       0  1802.5     .16       0
  2007.1     .05       0  2141.1     .16       0  2315.5     .12       0
  2536.3     .12       0  2833.9     .12       0  4945.8     .07       0
  5147.6     .12       0  5372.6     .05       0  6917.3     .12       0
  7319.9     .05       0  8520.1     .12       0  8942.5     .12       0
  9638.7     .05       0 10396.6     .16       0 11499.8     .05       0
   12093     .16       0 12277.4     .05       0
#XS Ineff= 3 ,-1
    7373 11255.2  311.06 11255.2 12012.8  363.24 12012.8 12890.8   371.2
Permanent Ineff=
       F       F       F
Bank Sta=4945.8,5147.6
XS Rating Curve= 0 ,0
Exp/Cntr=0.3,0.1

Type RM Length L Ch R = 1 ,609989  ,3265,3265,3265
BEGIN DESCRIPTION:
NAVASOTA RIVER 165
END DESCRIPTION:
XS GIS Cut Line= 5
      3557077.66     10432124.48      3552997.84     10431586.29
      3551713.11     10431916.15      3551188.55      10432011.9
      3547282.33     10430299.67
#Sta/Elev= 30
  -595.2  392.76  -587.8  392.17  -223.7  378.67   105.1  369.43   687.2  344.52
  1215.9  348.57  1922.1  318.26  2585.7   319.4    2828  316.67  3286.9  319.99
  3511.4  320.86  4094.7  320.29  4402.2  313.86  4475.7   299.6  4918.5   303.5
  4989.4  286.05  5050.7  304.52  5189.4  304.24  5419.2  302.99  5770.4  304.14
  7103.5   302.3  7319.2   303.5  7417.5  293.24  8103.8  299.43  8633.6   302.5
  8835.5  302.65  9351.2  341.74  9453.3  354.67  9575.6  388.81  9644.6  393.32
#Mann= 20 ,-1 , 0
  -595.2      .1       0  -587.8     .05       0  -223.7     .05       0
   105.1     .16       0  1922.1     .16       0  2585.7     .05       0
    2828     .05       0  3286.9     .12       0  3511.4      .1       0
  4094.7     .12       0  4918.5     .07       0  5050.7     .12       0
  5189.4     .16       0  5419.2     .12       0  5770.4     .05       0
  7103.5     .12       0  8103.8     .05       0  8633.6     .07       0
  8835.5     .05       0  9351.2     .16       0
#XS Ineff= 2 , 0
       0                    7260       0  303.73
Permanent Ineff=
       F       F
Bank Sta=4918.5,5050.7
XS Rating Curve= 0 ,0
Exp/Cntr=0.3,0.1

Type RM Length L Ch R = 1 ,606724  ,3723,3723,3723
BEGIN DESCRIPTION:
NAVASOTA RIVER 166
END DESCRIPTION:
XS GIS Cut Line= 3
      3557409.29     10432036.25      3551408.46     10430259.35
      3546806.12     10429853.19
#Sta/Elev= 30
 -1362.6  397.68    32.5  355.15   511.5  341.85   776.7  338.14  1043.6  322.37
  1252.2  340.49  1493.1  342.82    2052  319.15  2549.2  315.28  2691.5  317.51
  2817.1  319.37  3160.4  318.45  3364.2  317.18  3636.3  314.18  3771.7  312.31
  3873.6   310.4  3982.2  303.32  4926.9  305.26  4992.3  286.15  5062.8  303.14
  5782.4   303.2  6224.2  301.68  6434.1  302.46    6920  301.87  7030.4   292.5
  7120.8  301.01  8395.7  302.67  8905.3  347.03  9251.6  353.63    9516  374.39
#Mann= 20 ,-1 , 0
 -1362.6     .05       0    32.5     .16       0   511.5     .05       0
   776.7     .16       0    2052     .05       0  2549.2     .16       0
  2691.5     .05       0  2817.1     .16       0  3160.4     .12       0
  3364.2     .16       0  3636.3     .05       0  3771.7      .1       0
  3873.6     .05       0  3982.2     .12       0  4926.9     .07       0
  5062.8     .12       0  5782.4     .05       0  6224.2     .07       0
  6434.1     .05       0  7120.8     .05       0
#XS Ineff= 2 , 0
       0                  6719.2       0  302.19
Permanent Ineff=
       F       F
Bank Sta=4926.9,5062.8
XS Rating Curve= 0 ,0
Exp/Cntr=0.3,0.1

Type RM Length L Ch R = 1 ,603001  ,2741,2741,2741
BEGIN DESCRIPTION:
NAVASOTA RIVER 167
END DESCRIPTION:
XS GIS Cut Line= 3
      3557574.25     10431850.45      3553361.89      10429641.1
      3548012.57     10426143.45
#Sta/Elev= 30
   243.4  392.82   351.4  391.56   762.6   383.1  1226.3  370.19    1445  363.91
    1773  353.73  2304.9  341.71  2657.9  341.17  3828.3  341.41  4587.7  301.69
  4847.1  309.85  4963.4  304.77  5006.7  283.39  5064.2  301.22  5136.6  301.71
  5265.1  302.85  6653.7  301.78    6726   296.9  7127.9  302.01    8156  300.44
  8431.7  300.66  8894.6  301.04  8915.6  298.93  8930.6  288.73  9045.5  299.97
    9454  299.17  9645.5  301.16  9726.1  312.76 10555.5  340.58 11391.3  380.99
#Mann= 20 ,-1 , 0
   243.4     .16       0   351.4     .16       0   762.6     .05       0
  1226.3     .05       0    1445     .05       0    1773     .05       0
  2304.9     .05       0  2657.9     .16       0  4587.7     .12       0
  4847.1     .12       0  4963.4     .07       0  5136.6     .12       0
  5265.1     .05       0  6653.7     .12       0  7127.9     .05       0
    8156     .07       0  8431.7     .05       0  9045.5     .07       0
    9454     .12       0  9726.1     .05       0
#XS Ineff= 2 , 0
       0                  6994.5       0  302.66
Permanent Ineff=
       F       F
Bank Sta=4963.4,5136.6
XS Rating Curve= 0 ,0
Exp/Cntr=0.3,0.1

Type RM Length L Ch R = 1 ,600260  ,998,998,998
BEGIN DESCRIPTION:
NAVASOTA RIVER 168
END DESCRIPTION:
XS GIS Cut Line= 3
       3558546.4     10427777.15      3553613.14     10427711.57
      3549556.52     10425614.93
#Sta/Elev= 30
    66.3  385.36   876.4  347.87  1073.9  322.21  1172.7  316.57  1317.5  308.21
  1421.2  306.02  1540.7  297.11  1910.8  303.28  2270.8  334.06  3080.9  300.51
    3489  297.95  3640.9  290.97  3710.9  300.47    4891     300  4990.8  282.89
  5046.2  300.61    5840  299.72  5900.2  299.54  6009.3  299.74  6071.4  299.91
  6849.9  296.86  6991.5  299.04  7657.7  298.77  7691.5  286.66  7776.3  298.82
  7958.7  300.25  8438.3  299.01  8586.6  309.52  9276.3  362.89  9566.4  374.89
#Mann= 19 ,-1 , 0
    66.3     .05       0   876.4     .08       0  1073.9     .05       0
  1172.7     .16       0  1317.5      .1       0  1421.2     .16       0
    3489     .12       0    4891     .03       0  5046.2     .05       0
    5840     .07       0  5900.2     .12       0  6009.3     .07       0
  6071.4     .05       0  6849.9     .07       0  6991.5     .05       0
  7691.5     .12       0  7958.7     .05       0  8438.3     .12       0
  8586.6     .05       0
#XS Ineff= 2 , 0
       0  2270.8  334.06  6641.6       0  301.46
Permanent Ineff=
       F       F
Bank Sta=4891,5046.2
XS Rating Curve= 0 ,0
Exp/Cntr=0.3,0.1

Type RM Length L Ch R = 1 ,599262  ,3034,3034,3034
BEGIN DESCRIPTION:
NAVASOTA RIVER 042
END DESCRIPTION:
XS GIS Cut Line= 3
      3557631.54     10426623.61      3553282.56     10426818.93
        3549832.     10425477.77
#Sta/Elev= 30
  1198.9   340.8  1358.5  343.59  1618.8  325.18    1829   334.6  1975.3  314.83
  2169.3  299.46  3130.3  300.25  3230.4  296.06  4932.1  301.44  4971.9  282.88
  5012.2  284.26  5062.2  299.29  5145.3  299.26  5352.5  294.55  6339.4   300.5
  6408.8  299.02  6550.2  294.87  6654.6  298.82  7131.1   297.1  7212.6   296.4
  7280.1  286.35  7312.3   293.4  7344.5  290.68  7365.9  300.82  7531.8   299.7
  8168.4  297.83  8376.5  305.34  8763.3  329.37  9089.8  357.92  9254.3  355.57
#Mann= 13 ,-1 , 0
  1198.9     .16       0  1975.3     .12       0  4932.1     .07       0
  5062.2     .12       0  5145.3     .05       0  6339.4     .07       0
  6408.8     .05       0  6550.2     .07       0  6654.6     .05       0
  7131.1     .12       0  7531.8     .05       0  8168.4     .12       0
  8376.5     .05       0
#XS Ineff= 2 , 0
       0  3495.5  300.33  6282.3       0   300.8
Permanent Ineff=
       F       F
Bank Sta=4932.1,5062.2
XS Rating Curve= 0 ,0
Exp/Cntr=0.3,0.1

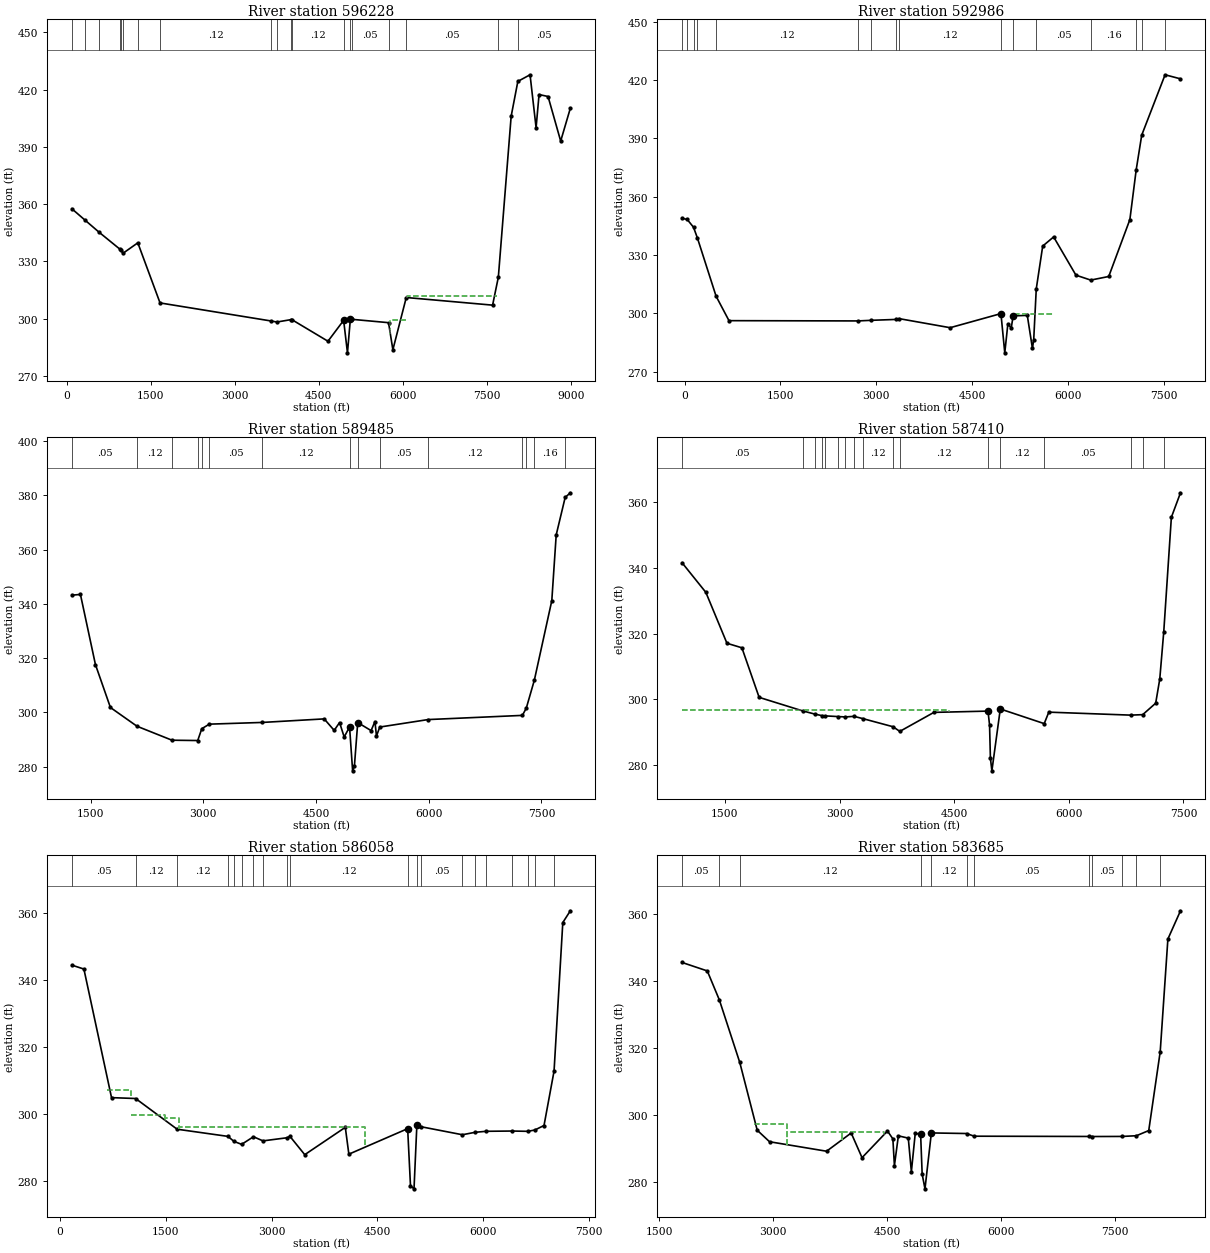
Type RM Length L Ch R = 1 ,596228  ,3242,3242,3242
BEGIN DESCRIPTION:
NAVASOTA RIVER 074
END DESCRIPTION:
XS GIS Cut Line= 3
      3558191.39     10426688.71      3551941.41     10423772.05
      3550938.81     10422040.28
#Sta/Elev= 30
    93.6  357.53   326.4  351.63   583.5  345.15   947.9  336.45   968.9  335.89
  1006.1  334.24  1270.1  339.71  1667.1  308.23  3646.1  298.79  3753.2  298.23
  3998.4  299.45  4016.4  299.54  4664.7  288.17  4944.5  299.11  5012.8  282.09
  5064.3  299.72  5087.4  299.66  5746.3  297.89  5823.4  283.72  6062.4  311.07
  7603.6  307.07  7706.2  321.75  7935.1  406.04  8054.4  424.27  8272.3  427.73
  8379.9  400.02    8433  417.38  8593.7  416.35    8819  393.01  8991.7  410.23
#Mann= 19 ,-1 , 0
    93.6     .16       0   326.4     .05       0   583.5     .16       0
   947.9     .12       0   968.9     .16       0  1006.1     .12       0
  1270.1     .16       0  1667.1     .12       0  3646.1     .07       0
  3753.2     .12       0  3998.4     .05       0  4016.4     .12       0
  4944.5     .07       0  5064.3     .12       0  5087.4     .05       0
  5746.3     .12       0  6062.4     .05       0  7706.2     .16       0
  8054.4     .05       0
#XS Ineff= 2 ,-1
  5777.6  6073.9  299.33  6073.9  7684.4  312.03
Permanent Ineff=
       F       F
Bank Sta=4944.5,5064.3
XS Rating Curve= 0 ,0
Exp/Cntr=0.3,0.1

Type RM Length L Ch R = 1 ,592986  ,3501,3501,3501
BEGIN DESCRIPTION:
NAVASOTA RIVER 112
END DESCRIPTION:
XS GIS Cut Line= 3
      3559092.44      10422988.2      3553345.93      10422363.2
      3551332.01     10422224.31
#Sta/Elev= 30
   -39.6  348.87      41  348.28   139.9  344.27   201.4  338.69   493.4   308.8
     695  296.26  2713.5  296.12  2916.1  296.43  3310.4  296.89  3352.9  297.32
  4155.3  292.64    4950  299.89  5010.1  279.72  5058.6  294.63  5110.9  292.44
  5141.1   298.7  5362.4  298.98  5442.9  282.01    5463  286.54  5502.8   312.6
  5603.8   334.6  5774.7  339.29  6123.6  319.64  6354.9  317.11  6636.7  318.96
  6967.5  348.21  7066.3  373.77  7152.7   391.6  7518.2  422.63  7759.5  420.54
#Mann= 16 ,-1 , 0
   -39.6     .05       0      41     .16       0   139.9     .12       0
   201.4     .16       0   493.4     .12       0  2713.5     .05       0
  2916.1     .12       0  3310.4     .07       0  3352.9     .12       0
    4950     .07       0  5141.1     .12       0  5502.8     .05       0
  6354.9     .16       0  7066.3     .05       0  7152.7     .16       0
  7518.2     .05       0
#XS Ineff= 2 ,-1
  5181.3  5774.7  299.47  5774.7  6897.4  339.29
Permanent Ineff=
       F       F
Bank Sta=4950,5141.1
XS Rating Curve= 0 ,0
Exp/Cntr=0.3,0.1

Type RM Length L Ch R = 1 ,589485  ,2075,2075,2075
BEGIN DESCRIPTION:
NAVASOTA RIVER 169
END DESCRIPTION:
XS GIS Cut Line= 2
      3559393.04     10421443.05      3552910.83     10420037.24
#Sta/Elev= 30
    1252  343.24  1365.5  343.52  1565.2  317.66  1764.6  301.84  2118.2  294.93
  2583.8  289.78  2926.3  289.66  2980.5  294.03  3080.7   295.7  3783.7  296.33
  4609.2  297.64  4742.2   293.4  4813.9  296.29  4875.2  290.97  4946.9  294.66
  4987.6  278.49  5011.5  280.33  5055.6  296.29  5233.4  293.32  5284.5  296.66
    5305  291.32  5348.4  294.63  5991.9  297.39  7246.5  298.93  7298.6   301.6
  7405.5  311.89    7638  341.23  7696.6  365.46  7815.9  379.28  7884.9  380.99
#Mann= 15 ,-1 , 0
    1252     .05       0  2118.2     .12       0  2583.8     .05       0
  2926.3     .12       0  2980.5     .07       0  3080.7     .05       0
  3783.7     .12       0  4946.9     .07       0  5055.6     .12       0
  5348.4     .05       0  5991.9     .12       0  7246.5     .16       0
  7298.6     .12       0  7405.5     .16       0  7815.9     .05       0
Bank Sta=4946.9,5055.6
XS Rating Curve= 0 ,0
Exp/Cntr=0.3,0.1

Type RM Length L Ch R = 1 ,587410  ,1352,1352,1352
BEGIN DESCRIPTION:
NAVASOTA RIVER 170
END DESCRIPTION:
XS GIS Cut Line= 2
      3560535.85     10420127.52      3554175.66     10418686.01
#Sta/Elev= 30
   939.5  341.63    1251  332.59  1527.1  317.06  1722.6  315.68  1948.2  300.56
  2516.3  296.44  2674.8  295.47  2775.2  294.96  2804.4  294.92  2976.1  294.71
  3076.5  294.59  3189.3  294.77  3304.6  294.08  3700.3   291.6  3788.5  290.18
  4234.8  295.98  4942.3  296.37  4962.8  292.18    4974  282.03  4993.3  278.15
  5103.4  297.02    5678  292.55    5738  296.05    6811  295.14  6966.7  295.29
  7136.4  298.78  7189.8  306.15  7241.9  320.52  7341.6  355.48    7461  362.96
#Mann= 17 ,-1 , 0
   939.5     .05       0  2516.3     .07       0  2674.8     .12       0
  2775.2     .07       0  2804.4     .05       0  2976.1     .07       0
  3076.5     .12       0  3189.3     .07       0  3304.6     .12       0
  3700.3     .07       0  3788.5     .12       0  4942.3     .07       0
  5103.4     .12       0    5678     .05       0    6811     .12       0
  6966.7     .05       0  7241.9     .16       0
#XS Ineff= 2 , 0
       0  4430.9  296.68               0
Permanent Ineff=
       F       F
Bank Sta=4942.3,5103.4
XS Rating Curve= 0 ,0
Exp/Cntr=0.3,0.1

Type RM Length L Ch R = 1 ,586058  ,2373,2373,2373
BEGIN DESCRIPTION:
NAVASOTA RIVER 171
END DESCRIPTION:
XS GIS Cut Line= 2
      3561501.53      10418428.3      3554465.49     10417740.26
#Sta/Elev= 30
   167.9  344.45   338.1  343.28     730  304.89  1071.2  304.63  1660.5  295.46
  2381.9  293.32  2465.1  291.84  2574.9  290.94  2742.8  293.21    2878  291.98
  3222.2  292.92  3259.9  293.34  3470.4  287.86  4045.7  296.02    4096  288.01
  4929.9  295.63  4970.1  278.59  5020.1  277.66  5060.5  296.68  5115.3  296.22
  5706.5  293.81    5886  294.54  6044.6  294.84  6413.6  294.92    6634  294.83
  6732.9  295.22  6863.9  296.57  7006.3  312.82  7130.4  357.17  7237.5  360.68
#Mann= 20 ,-1 , 0
   167.9     .05       0  1071.2     .12       0  1660.5     .12       0
  2381.9     .07       0  2465.1     .12       0  2574.9     .07       0
  2742.8     .07       0    2878     .12       0  3222.2     .05       0
  3259.9     .12       0  4929.9     .07       0  5060.5     .12       0
  5115.3     .05       0  5706.5     .07       0    5886     .05       0
  6044.6     .07       0  6413.6     .12       0    6634     .12       0
  6732.9     .05       0  7006.3     .16       0
#XS Ineff= 5 ,-1
   669.7  1011.6  307.18  1011.6  1493.6  299.61  1493.6  1684.5  298.86
  1684.5  4045.7  296.02  4045.7  4327.1     296
Permanent Ineff=
       F       F       F       F       F
Bank Sta=4929.9,5060.5
XS Rating Curve= 0 ,0
Exp/Cntr=0.3,0.1

Type RM Length L Ch R = 1 ,583685  ,3302,3302,3302
BEGIN DESCRIPTION:
NAVASOTA RIVER 175
END DESCRIPTION:
XS GIS Cut Line= 3
      3561487.33     10416930.42      3558333.51     10416408.57
      3554997.33     10416027.21
#Sta/Elev= 30
  1803.3  345.59  2135.4  343.05  2294.3  334.35  2562.6  315.64  2791.8  295.36
    2954  291.91    3704  289.07  4027.5  294.53  4170.3  287.14  4504.8  295.12
  4575.7  292.77    4596  284.78    4648  293.68  4778.4  292.99    4819  282.94
  4869.7  294.38  4940.6  294.18  4960.9  282.22  4997.9  277.81  5081.9  294.55
  5545.4  294.37  5644.4  293.57    7156  293.49  7193.6  293.47  7591.9   293.5
  7778.4  293.71  7940.4  295.26  8091.2  318.88  8192.1   352.6  8357.9  361.06
#Mann= 12 ,-1 , 0
  1803.3     .05       0  2294.3     .16       0  2562.6     .12       0
  4940.6     .07       0  5081.9     .12       0  5545.4     .16       0
  5644.4     .05       0    7156     .07       0  7193.6     .05       0
  7591.9     .07       0  7778.4     .05       0  8091.2     .16       0
#XS Ineff= 3 ,-1
  2751.2  3178.1  297.12  3178.1  3905.4   294.8  3905.4  4454.1   294.8
Permanent Ineff=
       F       F       F
Bank Sta=4940.6,5081.9
XS Rating Curve= 0 ,0
Exp/Cntr=0.3,0.1

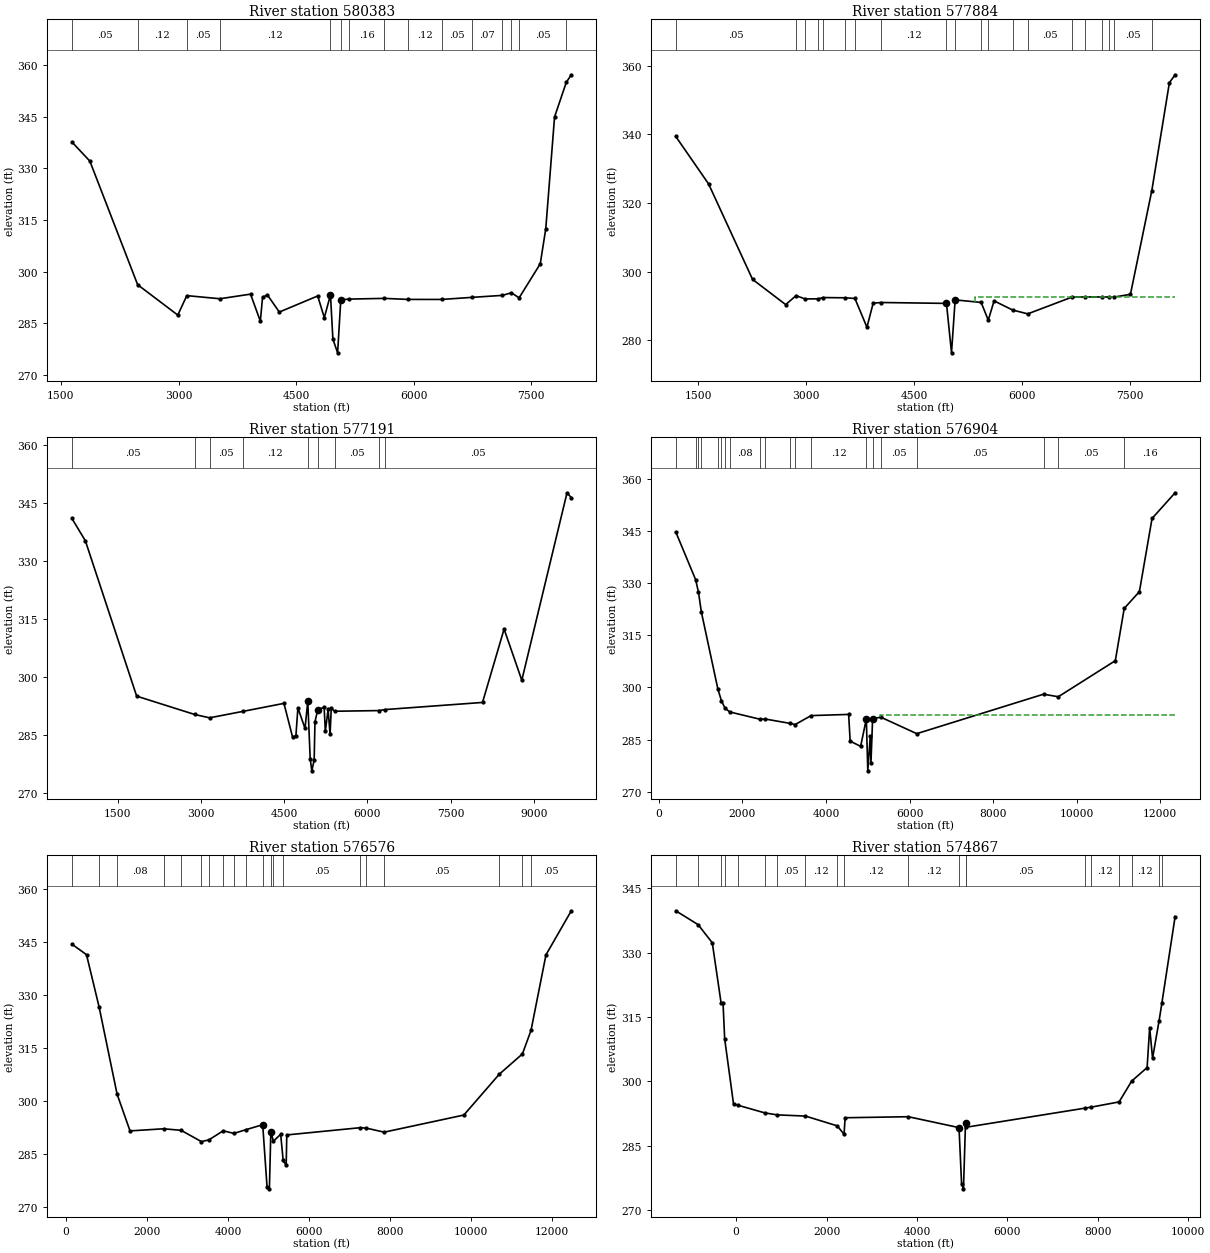
Type RM Length L Ch R = 1 ,580383  ,2499,2499,2499
BEGIN DESCRIPTION:
NAVASOTA RIVER 176
END DESCRIPTION:
XS GIS Cut Line= 3
      3561226.19     10415307.01      3557931.79     10414648.83
      3554926.92     10414463.28
#Sta/Elev= 30
  1640.5  337.64    1869   332.1  2478.5  296.25  2990.8  287.43  3105.6  293.08
  3527.6  292.17  3918.7  293.51  4043.8  285.65  4071.7  292.56  4132.9  293.31
  4285.8  288.31  4775.3  292.98    4860  286.67  4938.5  293.34  4969.1  280.48
  5029.5  276.48  5069.8  291.84  5171.9  292.07  5626.5  292.28  5925.5  291.98
  6357.1  291.97    6747  292.58    7131  293.15  7246.1   293.9  7344.8  292.44
  7614.7  302.32  7684.8  312.51  7796.9  344.92  7946.9  354.98  8010.6  357.15
#Mann= 15 ,-1 , 0
  1640.5     .05       0  2478.5     .12       0  3105.6     .05       0
  3527.6     .12       0  4938.5     .07       0  5069.8     .12       0
  5171.9     .16       0  5626.5     .05       0  5925.5     .12       0
  6357.1     .05       0    6747     .07       0    7131     .05       0
  7246.1     .07       0  7344.8     .05       0  7946.9     .16       0
Bank Sta=4938.5,5069.8
XS Rating Curve= 0 ,0
Exp/Cntr=0.3,0.1

Type RM Length L Ch R = 1 ,577884  ,693,693,693
BEGIN DESCRIPTION:
NAVASOTA RIVER 177
END DESCRIPTION:
XS GIS Cut Line= 3
      3561248.29     10415169.92      3558379.06     10413195.21
      3554932.91     10412972.99
#Sta/Elev= 30
    1191  339.41  1647.7  325.55  2257.9  297.75  2717.9   290.4  2862.5  293.01
  2989.1  292.04  3172.7  292.09  3235.9  292.45  3540.9  292.38  3679.5  292.19
  3846.8   283.8  3933.4  290.82  4045.4  291.01  4951.6  290.75  5021.5  276.34
  5071.9  291.77  5433.3  291.03  5532.1  285.86    5613  291.48  5871.9   288.8
    6081   287.7    6689  292.54  6878.5  292.63  7108.4  292.62  7211.2  292.61
  7284.6  292.61  7506.9  293.39  7803.9  323.63    8048  355.08  8127.4  357.38
#Mann= 20 ,-1 , 0
    1191     .05       0  2862.5     .12       0  2989.1     .07       0
  3172.7     .05       0  3235.9     .12       0  3540.9     .12       0
  3679.5     .05       0  4045.4     .12       0  4951.6     .07       0
  5071.9     .12       0  5433.3     .16       0  5532.1     .05       0
  5871.9     .07       0    6081     .05       0    6689     .12       0
  6878.5     .07       0  7108.4     .12       0  7211.2     .07       0
  7284.6     .05       0  7803.9     .16       0
#XS Ineff= 2 , 0
       0                  5342.4       0  292.55
Permanent Ineff=
       F       F
Bank Sta=4951.6,5071.9
XS Rating Curve= 0 ,0
Exp/Cntr=0.3,0.1

Type RM Length L Ch R = 1 ,577191  ,287,287,287
BEGIN DESCRIPTION:
NAVASOTA RIVER 174
END DESCRIPTION:
XS GIS Cut Line= 6
      3561316.79      10415206.3      3561161.75     10414942.06
      3561008.43     10414760.68      3560211.29     10414109.15
       3555327.7     10410521.18      3553975.27     10410664.23
#Sta/Elev= 30
   678.8  341.02   920.4  335.25  1844.4  295.02  2889.8  290.27  3158.8  289.41
  3752.5  291.06  4497.1  293.15  4654.1  284.33  4712.8  284.81  4748.4  291.99
  4876.5  286.66  4926.2  293.66  4970.2  278.79  4999.4  275.68  5041.4  278.51
    5056   288.4  5106.3  291.49  5221.5  292.13  5242.4  285.89  5292.6  291.59
  5328.2  285.11    5349  291.86  5410.6  291.11  6200.8  291.28  6322.6  291.55
  8073.5  293.39  8462.1  312.39  8781.1  299.14  9595.6  347.68  9672.9  346.41
#Mann= 9 ,-1 , 0
   678.8     .05       0  2889.8     .07       0  3158.8     .05       0
  3752.5     .12       0  4926.2     .07       0  5106.3     .12       0
  5410.6     .05       0  6200.8     .07       0  6322.6     .05       0
Bank Sta=4926.2,5106.3
XS Rating Curve= 0 ,0
Exp/Cntr=0.3,0.1

Type RM Length L Ch R = 1 ,576904  ,328,328,328
BEGIN DESCRIPTION:
NAVASOTA RIVER 172
END DESCRIPTION:
XS GIS Cut Line= 6
      3561520.54     10415099.59      3561169.29     10414595.91
      3560351.47     10413926.76      3555364.02     10410289.28
      3554090.72     10408542.02      3552176.86     10408255.59
#Sta/Elev= 30
   403.6  344.69   879.6  330.96     948  327.35  1016.9  321.67  1411.3  299.58
  1497.5  296.16    1579  294.14  1692.7  292.98  2428.1  290.85  2547.5  290.93
    3143  289.68  3261.7  289.35  3642.5  291.92  4541.5  292.26  4577.6  284.58
  4828.3  283.09  4964.4  290.94  4999.7  276.05  5058.7  285.95  5075.4  278.35
  5115.1  291.06  5315.2  291.44  6171.3  286.73    9206  298.07    9558  297.33
 10923.2  307.69 11136.1  322.71 11499.5  327.53 11802.2  348.55 12354.2  355.93
#Mann= 20 ,-1 , 0
   403.6     .05       0   879.6     .16       0     948     .05       0
  1016.9     .16       0  1411.3     .05       0  1497.5     .16       0
    1579     .05       0  1692.7     .08       0  2428.1     .12       0
  2547.5     .07       0    3143     .05       0  3261.7     .05       0
  3642.5     .12       0  4964.4     .07       0  5115.1     .12       0
  5315.2     .05       0  6171.3     .05       0    9206     .16       0
    9558     .05       0 11136.1     .16       0
#XS Ineff= 2 , 0
       0                  5301.5       0  292.07
Permanent Ineff=
       F       F
Bank Sta=4964.4,5115.1
XS Rating Curve= 0 ,0
Exp/Cntr=0.3,0.1

Type RM Length L Ch R = 1 ,576576  ,1709,1709,1709
BEGIN DESCRIPTION:
NAVASOTA RIVER 173
END DESCRIPTION:
XS GIS Cut Line= 6
      3561786.28     10414960.38      3561379.12       10414381.
      3560534.31     10413688.85      3555476.13     10409987.05
      3554220.93     10408164.41      3552202.73     10407877.96
#Sta/Elev= 30
   144.2  344.34   503.7  341.36     814  326.62    1258  301.99  1577.9  291.58
  2408.4  292.18  2838.8  291.74  3340.7  288.55  3525.3  289.05  3878.8  291.61
  4142.4  290.87    4442  291.93  4853.2  293.33  4959.8  275.87  5018.4  275.21
  5054.2  291.41    5116  288.66  5296.9  290.61  5358.6  283.23    5433  281.83
  5447.7  290.44  7257.7  292.48  7413.6  292.36  7851.2  291.22  9819.4  296.06
 10691.5  307.57 11264.6  313.32 11477.2  319.97 11846.3  341.32 12471.9  353.77
#Mann= 20 ,-1 , 0
   144.2     .05       0     814     .16       0    1258     .08       0
  2408.4     .05       0  2838.8     .12       0  3340.7     .07       0
  3525.3     .07       0  3878.8     .12       0  4142.4     .05       0
    4442     .05       0  4853.2     .07       0  5054.2     .05       0
    5116     .12       0  5358.6     .05       0  7257.7     .16       0
  7413.6     .16       0  7851.2     .05       0 10691.5     .05       0
 11264.6     .16       0 11477.2     .05       0
#XS Ineff= 2 , 0
       0                  5054.2       0  291.41
Permanent Ineff=
       F       F
Bank Sta=4853.2,5054.2
XS Rating Curve= 0 ,0
Exp/Cntr=0.3,0.1

Type RM Length L Ch R = 1 ,574867  ,1848,1848,1848
BEGIN DESCRIPTION:
NAVASOTA RIVER 320
END DESCRIPTION:
XS GIS Cut Line= 4
      3562191.76     10414832.06      3561029.26     10413068.16
       3556949.4     10410273.02      3554289.11     10407300.02
#Sta/Elev= 30
 -1337.1  339.74  -842.2  336.51  -528.6  332.28  -333.9  318.26  -290.7  318.17
  -254.5  309.89   -58.8  294.74      46  294.42   633.7  292.66     906   292.2
    1532  291.92  2235.8  289.64  2386.5  287.68  2410.2  291.53  3808.6  291.77
  4929.7  289.23  4986.7  276.11  5028.4  274.97  5073.4  290.31    5082  289.31
  7718.4  293.77  7854.9     294  8471.8  295.22  8749.1  300.06  9090.9  303.22
  9147.4  312.54  9211.7  305.39  9356.9  314.18  9418.6  318.31  9710.4  338.37
#Mann= 20 ,-1 , 0
 -1337.1     .05       0  -842.2     .16       0  -333.9     .15       0
  -254.5     .16       0      46     .12       0   633.7     .05       0
     906     .05       0    1532     .12       0  2235.8     .05       0
  2386.5     .12       0  3808.6     .12       0  4929.7     .07       0
  5073.4     .12       0    5082     .05       0  7718.4     .07       0
  7854.9     .12       0  8471.8     .05       0  8749.1     .12       0
  9356.9     .05       0  9418.6     .16       0
#XS Ineff= 2 , 0
       0                  9147.4       0  312.54
Permanent Ineff=
       F       F
Bank Sta=4929.7,5073.4
XS Rating Curve= 0 ,0
Exp/Cntr=0.3,0.1

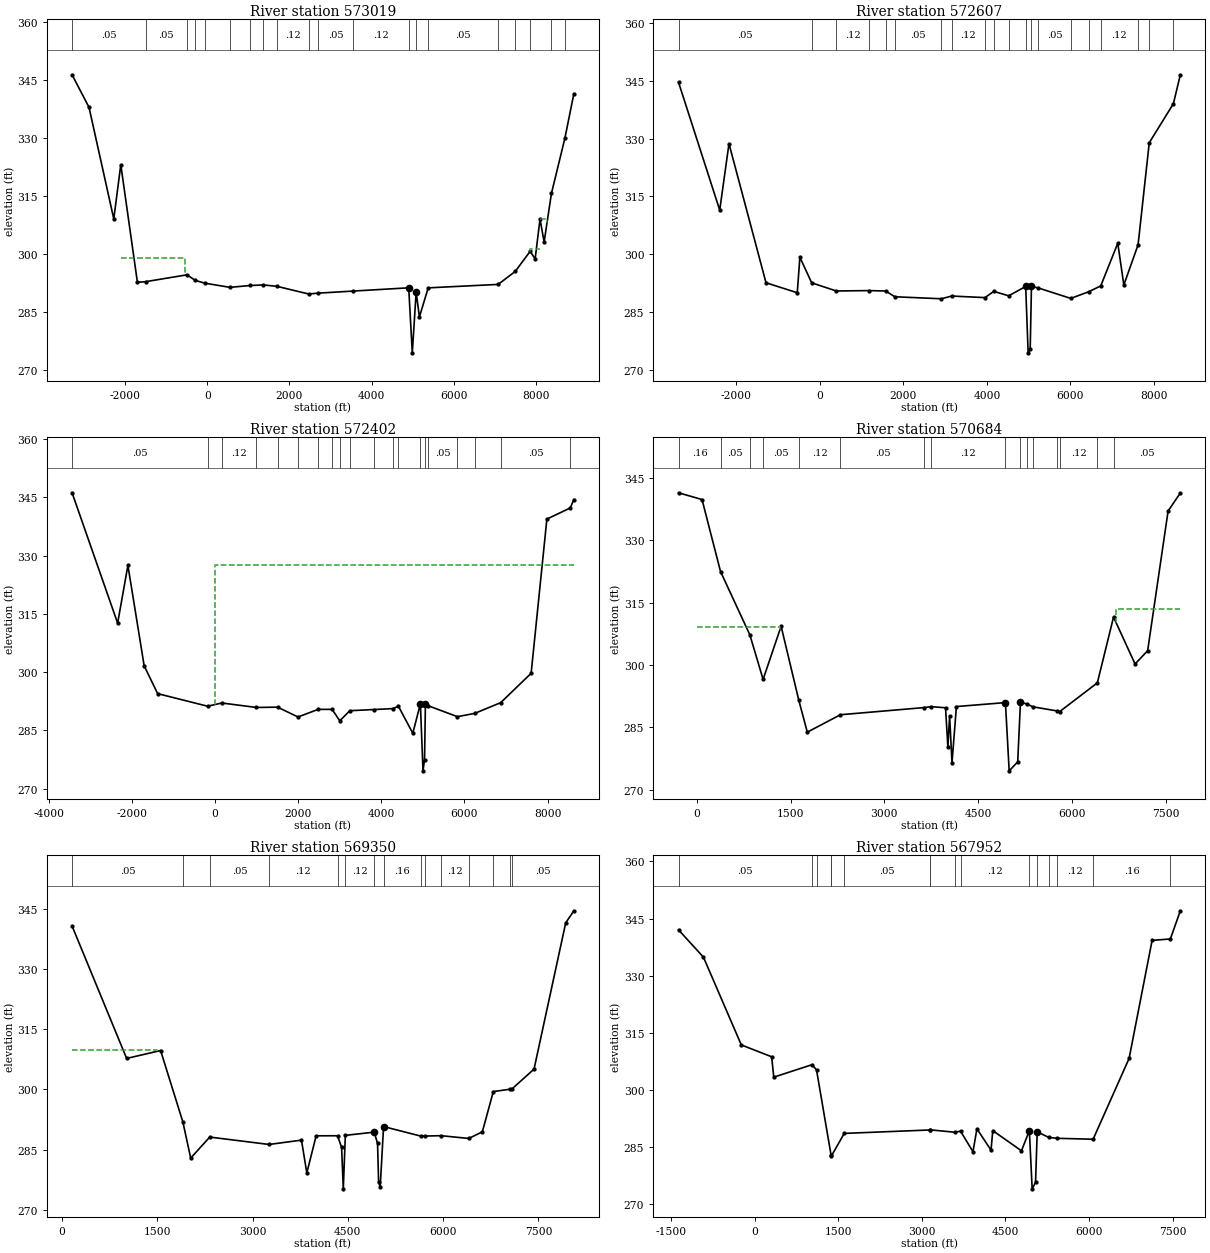
Type RM Length L Ch R = 1 ,573019  ,412,412,412
BEGIN DESCRIPTION:
NAVASOTA RIVER 180
END DESCRIPTION:
XS GIS Cut Line= 6
      3565202.67     10411489.94      3561848.53     10411864.93
      3561477.17     10411567.21      3556753.49     10408585.21
      3554984.31     10407745.28      3554312.49     10407246.36
#Sta/Elev= 30
   -3301  346.38 -2887.9  337.97 -2284.1  309.12 -2113.1  323.12 -1708.1  292.75
 -1510.5  292.89  -498.9  294.67  -299.2  293.24   -68.5  292.52   549.4  291.43
  1049.3  291.91  1363.7  292.05  1695.3  291.69  2468.9  289.71  2699.8  289.93
  3556.7  290.47  4906.9  291.31  4994.2   274.5  5088.5   290.2  5167.4  283.77
  5382.5   291.3  7087.9  292.19  7503.6  295.54    7868  300.73  7989.5  298.77
  8108.4   309.1  8208.6  303.16  8386.7   315.7  8713.4  329.91  8933.5  341.48
#Mann= 20 ,-1 , 0
   -3301     .05       0 -1510.5     .05       0  -498.9     .16       0
  -299.2     .12       0   -68.5     .05       0   549.4     .12       0
  1049.3     .12       0  1363.7     .16       0  1695.3     .12       0
  2468.9     .05       0  2699.8     .05       0  3556.7     .12       0
  4906.9     .07       0  5088.5     .12       0  5382.5     .05       0
  7087.9     .12       0  7503.6     .05       0    7868     .12       0
  8386.7     .05       0  8713.4     .16       0
#XS Ineff= 4 ,-1
 -2887.9 -2113.1  323.12 -2113.1  -539.5  299.02  7858.4  8108.4  301.39
  8108.4  8279.5   309.1
Permanent Ineff=
       F       F       F       F
Bank Sta=4906.9,5088.5
XS Rating Curve= 0 ,0
Exp/Cntr=0.3,0.1

Type RM Length L Ch R = 1 ,572607  ,205,205,205
BEGIN DESCRIPTION:
NAVASOTA RIVER 178
END DESCRIPTION:
XS GIS Cut Line= 6
      3565119.32     10411239.94      3562098.53      10411656.6
      3560535.75     10410682.06        3556884.     10408371.95
      3556536.67     10408166.63      3554342.33     10407186.52
#Sta/Elev= 30
 -3387.6  344.57 -2401.1  311.44 -2179.1  328.66 -1292.5   292.6  -543.7  290.01
  -481.2  299.21    -198  292.58   390.7  290.47  1179.6  290.57  1573.7  290.46
  1794.5  288.97  2906.4  288.45    3158  289.16  3952.3  288.75  4162.7  290.36
  4520.8  289.22  4927.5  291.64  4986.4  274.43  5035.4  275.33    5066  291.67
  5228.3  291.26  6007.8  288.54  6446.4  290.31  6725.7   291.8  7133.5  302.85
  7278.5  292.02  7619.6  302.44  7887.4  328.91  8465.5  339.03  8631.6  346.53
#Mann= 20 ,-1 , 0
 -3387.6     .05       0    -198     .16       0   390.7     .12       0
  1179.6     .16       0  1573.7     .16       0  1794.5     .05       0
  2906.4     .05       0    3158     .12       0  3952.3     .12       0
  4162.7     .07       0  4520.8     .12       0  4927.5     .07       0
    5066     .12       0  5228.3     .05       0  6007.8     .05       0
  6446.4     .05       0  6725.7     .12       0  7619.6     .16       0
  7887.4     .05       0  8465.5     .16       0
#XS Ineff= 3 ,-1
 -3198.6 -2179.1  328.66 -2179.1  -481.2  299.21  7133.5  7898.7  302.85
Permanent Ineff=
       F       F       F
Bank Sta=4927.5,5066
XS Rating Curve= 0 ,0
Exp/Cntr=0.3,0.1

Type RM Length L Ch R = 1 ,572402  ,1718,1718,1718
BEGIN DESCRIPTION:
NAVASOTA RIVER 179
END DESCRIPTION:
XS GIS Cut Line= 6
      3565244.41     10410948.26      3562117.59     10411439.92
      3556988.41     10408201.34      3556630.88     10407989.99
      3556465.93     10407911.11      3554423.29     10407003.64
#Sta/Elev= 30
 -3434.7  346.16 -2339.1  312.59 -2092.1  327.46 -1701.4  301.61 -1377.4  294.44
  -176.3   291.2     166  292.03   997.6  290.88  1506.1  290.96  1997.1  288.43
  2483.5  290.39  2817.8  290.39  3001.6  287.44  3242.6  290.04  3813.2  290.34
  4281.7  290.59  4411.1  291.21  4757.6  284.23  4939.8  291.82  5003.1  274.56
  5039.8  277.45    5061  291.78    5130  291.31  5830.7  288.51  6246.1  289.35
  6871.2  292.12  7602.6  299.67  7981.1  339.39  8543.1  342.25  8629.9  344.41
#Mann= 20 ,-1 , 0
 -3434.7     .05       0  -176.3      .1       0     166     .12       0
   997.6     .16       0  1506.1     .05       0  1997.1     .05       0
  2483.5     .12       0  2817.8     .05       0  3001.6     .07       0
  3242.6     .12       0  3813.2     .12       0  4281.7     .07       0
  4411.1     .12       0  4939.8     .07       0    5061     .12       0
    5130     .05       0  5830.7     .16       0  6246.1     .12       0
  6871.2     .05       0  8543.1     .16       0
#XS Ineff= 2 , 0
       0 -2092.1  327.46  7981.1       0  339.39
Permanent Ineff=
       F       F
Bank Sta=4939.8,5061
XS Rating Curve= 0 ,0
Exp/Cntr=0.3,0.1

Type RM Length L Ch R = 1 ,570684  ,1334,1334,1334
BEGIN DESCRIPTION:
NAVASOTA RIVER 321
END DESCRIPTION:
XS GIS Cut Line= 3
      3563071.54     10409079.44      3557348.53     10407323.27
      3555726.77     10406083.09
#Sta/Elev= 30
  -291.3  341.48    84.7  339.85   380.4  322.53   849.5   307.3  1061.7  296.57
  1349.8  309.37  1632.6  291.56  1768.8  283.88  2299.1  288.07  3643.6   289.8
  3745.7  290.02  3980.2  289.75  4018.1  280.28  4045.6  287.79  4083.6  276.48
  4154.3  290.04  4938.6  290.99  4998.5  274.57    5135  276.72  5178.8  291.04
  5277.7  290.69  5379.8  289.97  5766.5  288.98  5805.4  288.81  6409.2  295.74
  6668.2  311.57  7012.6  300.28  7213.8  303.47  7541.1   337.1  7736.7  341.42
#Mann= 16 ,-1 , 0
  -291.3     .16       0   380.4     .05       0   849.5     .16       0
  1061.7     .05       0  1632.6     .12       0  2299.1     .05       0
  3643.6     .07       0  3745.7     .12       0  4938.6     .07       0
  5178.8     .12       0  5277.7     .16       0  5379.8     .05       0
  5766.5     .07       0  5805.4     .12       0  6409.2     .16       0
  6668.2     .05       0
#XS Ineff= 2 , 0
       0  1329.4  309.27  6713.4       0  313.41
Permanent Ineff=
       F       F
Bank Sta=4938.6,5178.8
XS Rating Curve= 0 ,0
Exp/Cntr=0.3,0.1

Type RM Length L Ch R = 1 ,569350  ,1398,1398,1398
BEGIN DESCRIPTION:
NAVASOTA RIVER 322
END DESCRIPTION:
XS GIS Cut Line= 3
      3563289.88      10408314.7      3558681.72     10406832.39
       3555783.3     10405856.49
#Sta/Elev= 30
   159.3  340.73  1018.3  307.72    1553  309.69  1903.1  291.91  2026.8  282.88
  2326.2  288.12  3260.4  286.28  3770.5  287.36  3854.6  279.18  4001.4  288.44
    4338  288.45  4402.2  285.55  4428.8  275.22  4461.1  288.55  4915.6  289.35
  4968.1  286.53    4985   276.8  5010.1  275.79  5062.9  290.74    5652  288.35
  5708.9  288.37  5965.5  288.47  6403.6  287.78  6617.8  289.43  6790.4  299.46
  7049.8  300.04  7079.5  300.05  7431.4  305.06  7930.1  341.52  8058.3  344.52
#Mann= 15 ,-1 , 0
   159.3     .05       0  1903.1     .12       0  2326.2     .05       0
  3260.4     .12       0    4338     .07       0  4461.1     .12       0
  4915.6     .07       0  5062.9     .16       0    5652     .12       0
  5708.9     .05       0  5965.5     .12       0  6403.6     .16       0
  6790.4     .05       0  7049.8     .08       0  7079.5     .05       0
#XS Ineff= 2 , 0
       0  1501.6  309.85               0
Permanent Ineff=
       F       F
Bank Sta=4915.6,5062.9
XS Rating Curve= 0 ,0
Exp/Cntr=0.3,0.1

Type RM Length L Ch R = 1 ,567952  ,1160,1160,1160
BEGIN DESCRIPTION:
NAVASOTA RIVER 323
END DESCRIPTION:
XS GIS Cut Line= 3
      3564783.67     10406728.32      3558494.22     10405755.14
        3555856.     10405650.24
#Sta/Elev= 30
 -1364.3  342.03  -917.5  334.86    -238  311.81   306.9  308.69   344.7  303.34
  1031.8  306.62    1112  305.24  1373.7  282.79    1377  282.59    1609  288.57
  3143.8  289.47  3155.3   289.5  3596.7  288.87  3696.1  289.16  3919.4  283.76
  3990.2  289.78  4243.2  284.17  4274.7   289.3  4789.3     284  4931.3  289.29
  4981.6  274.01  5042.1  275.69  5072.2  288.97  5279.1  287.53  5430.2  287.28
  6075.4  287.04  6721.2  308.26  7133.8  339.26  7461.6  339.64  7640.3  347.04
#Mann= 16 ,-1 , 0
 -1364.3     .05       0  1031.8     .16       0    1112     .12       0
  1373.7     .07       0    1377     .12       0    1609     .05       0
  3143.8     .07       0  3155.3     .05       0  3596.7     .07       0
  3696.1     .12       0  4931.3     .07       0  5072.2     .12       0
  5279.1     .05       0  5430.2     .12       0  6075.4     .16       0
  7461.6     .05       0
Bank Sta=4931.3,5072.2
XS Rating Curve= 0 ,0
Exp/Cntr=0.3,0.1