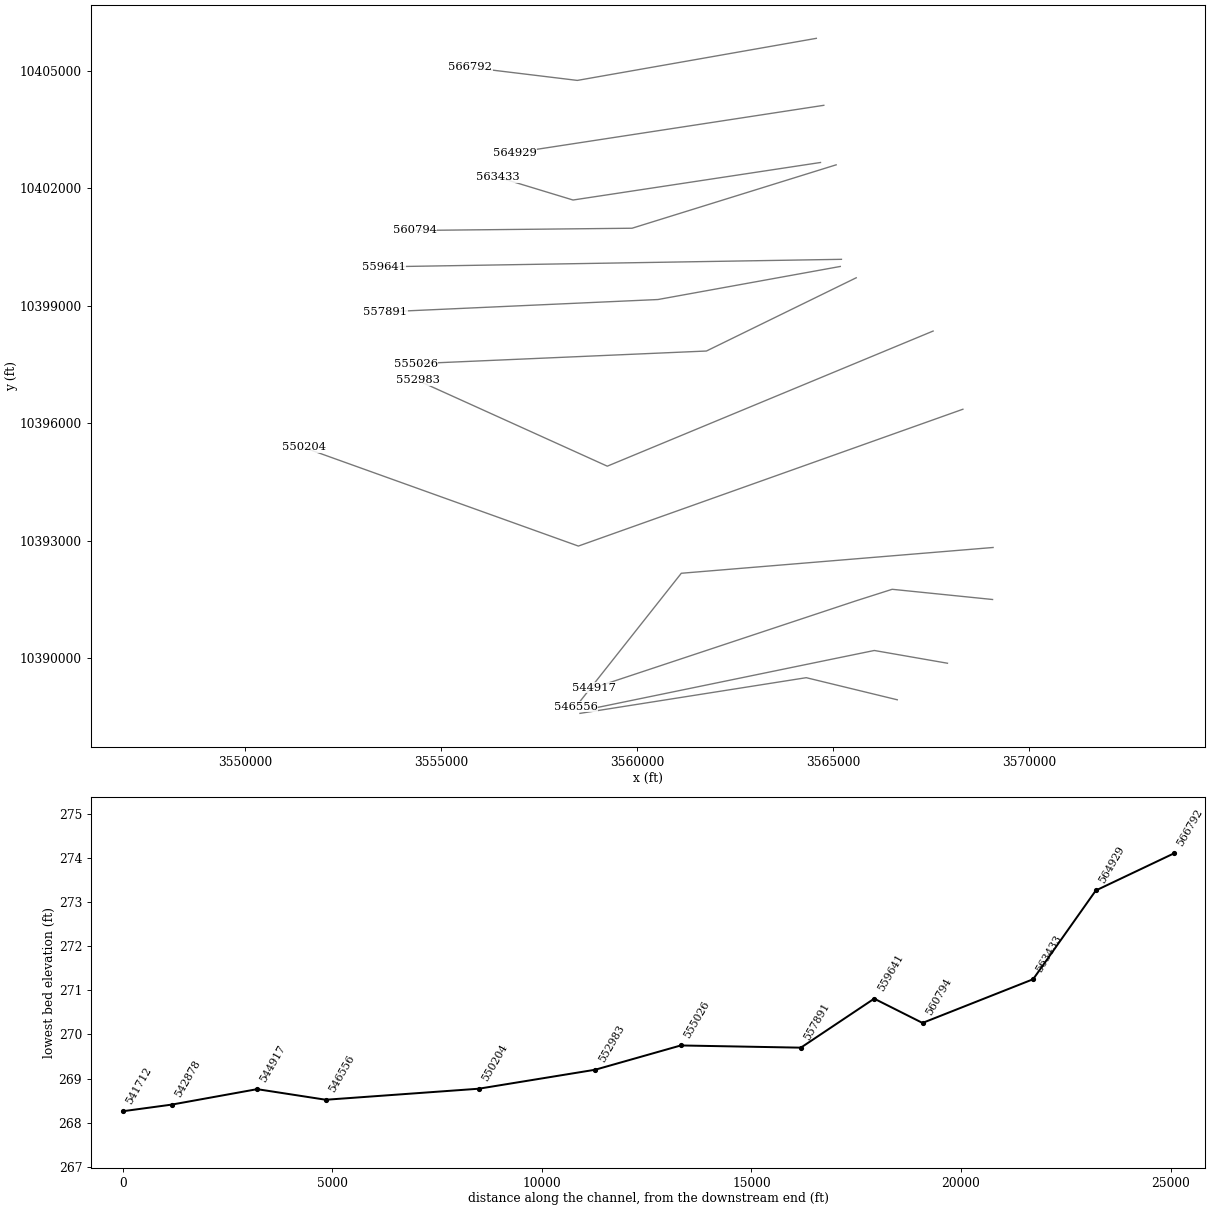
HEC-RAS study NAVASOTA RIVER.prj: NAVASOTA RIVER Base Level Engineering

--- NAVASOTA RIVER.g01 (geometry) --- (continued)

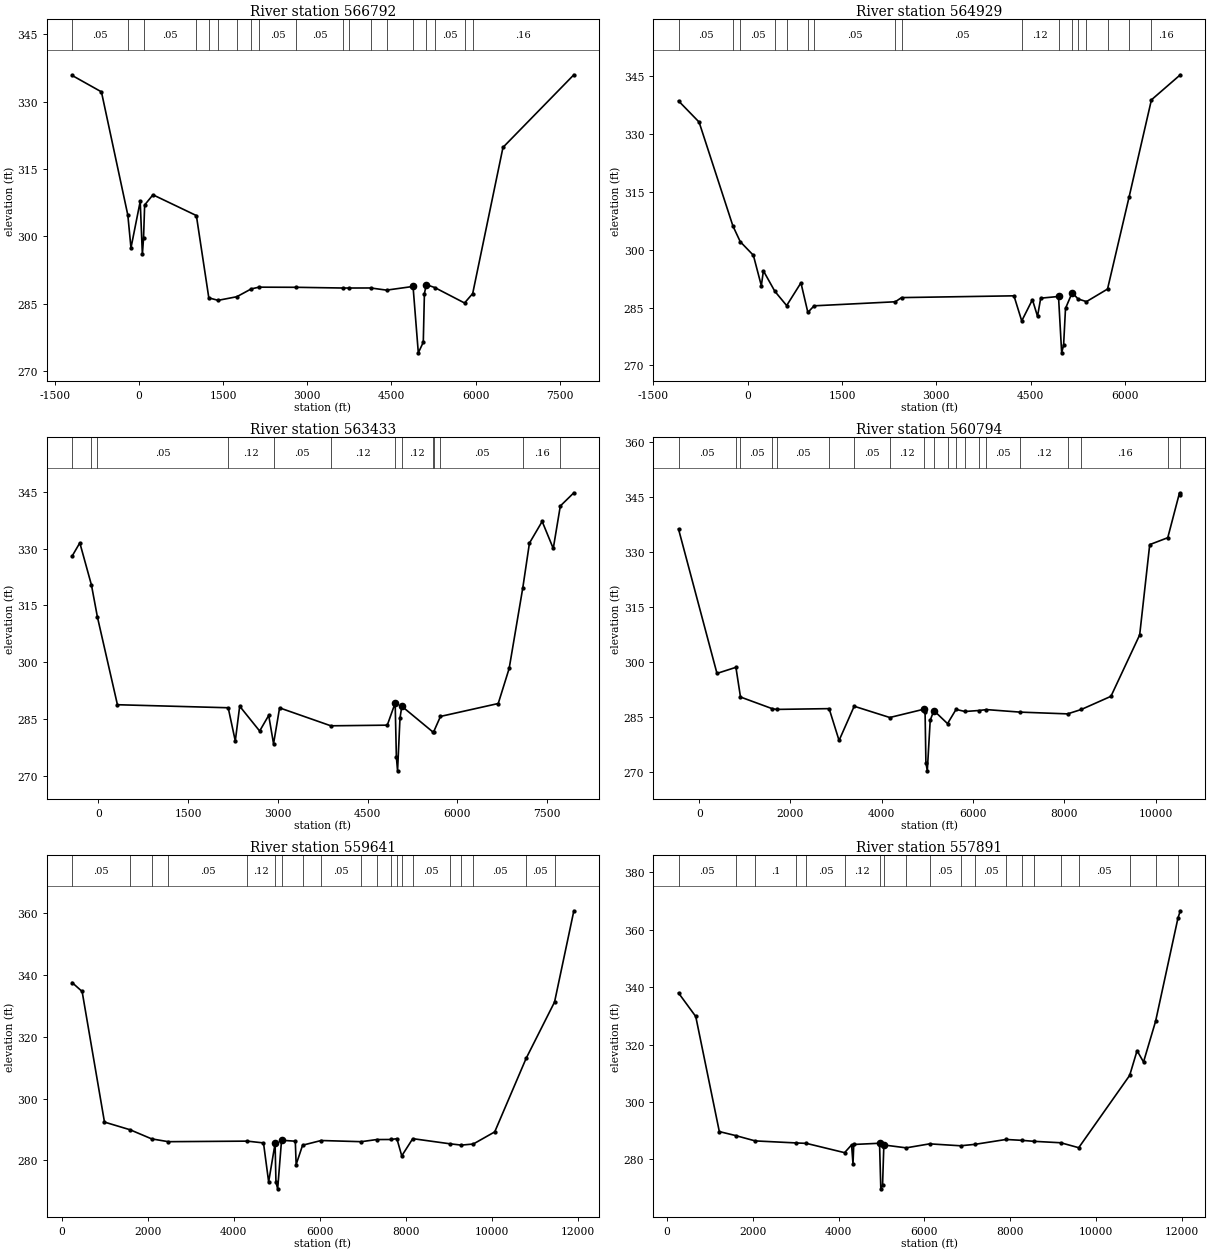
Type RM Length L Ch R = 1 ,566792  ,1863,1863,1863
BEGIN DESCRIPTION:
NAVASOTA RIVER 324
END DESCRIPTION:
XS GIS Cut Line= 3
      3564575.77     10405826.85      3558478.59     10404752.53
      3555748.54     10405083.99
#Sta/Elev= 30
 -1191.1  335.82  -667.9  332.16  -197.5  304.74  -141.5  297.45    23.1  307.79
    61.6  295.98    82.5  299.61   102.2  306.99   250.1  309.26  1023.7  304.64
  1245.5  286.33    1411  285.78  1743.8  286.58  2001.3  288.32  2139.3  288.71
  2801.4  288.68  3637.1  288.52  3736.7  288.52  4130.1  288.53  4413.5  288.05
  4884.7  288.87  4978.5   274.1    5067  276.46  5087.1  287.26  5119.7  289.28
  5270.7  288.63  5802.3  285.19  5947.4  287.29  6487.3  319.81  7750.1  335.96
#Mann= 19 ,-1 , 0
 -1191.1     .05       0  -197.5     .12       0    82.5     .05       0
  1023.7     .12       0  1245.5     .05       0    1411     .07       0
  1743.8     .05       0  2001.3     .07       0  2139.3     .05       0
  2801.4     .05       0  3637.1     .07       0  3736.7     .12       0
  4130.1     .05       0  4413.5     .12       0  4884.7     .07       0
  5119.7     .12       0  5270.7     .05       0  5802.3     .12       0
  5947.4     .16       0
Bank Sta=4884.7,5119.7
XS Rating Curve= 0 ,0
Exp/Cntr=0.3,0.1

Type RM Length L Ch R = 1 ,564929  ,1496,1496,1496
BEGIN DESCRIPTION:
NAVASOTA RIVER 325
END DESCRIPTION:
XS GIS Cut Line= 2
      3564766.73     10404116.77       3556876.6     10402905.91
#Sta/Elev= 30
 -1101.1  338.52  -774.2  333.04  -236.3  306.13  -119.6  302.06    89.4  298.53
     216  290.66   249.1   294.5   431.1   289.2   618.9   285.5   846.1  291.39
   956.2  283.73  1055.5  285.44  2347.4  286.49  2446.8  287.57  4234.9  288.03
  4358.4  281.53  4528.7  287.03  4609.6  282.72  4660.2  287.42  4943.5  287.86
  4993.8  273.26  5024.4  275.23  5054.8  284.77  5161.8  288.88  5253.8  287.22
  5388.1  286.53  5723.3  289.78    6066   313.6  6421.6   338.8  6881.4  345.29
#Mann= 17 ,-1 , 0
 -1101.1     .05       0  -236.3     .08       0  -119.6     .05       0
   431.1     .12       0   618.9     .07       0   956.2     .08       0
  1055.5     .05       0  2347.4     .12       0  2446.8     .05       0
  4358.4     .12       0  4943.5     .07       0  5161.8     .12       0
  5253.8     .05       0  5388.1     .12       0  5723.3     .16       0
    6066     .05       0  6421.6     .16       0
Bank Sta=4943.5,5161.8
XS Rating Curve= 0 ,0
Exp/Cntr=0.3,0.1

Type RM Length L Ch R = 1 ,563433  ,2639,2639,2639
BEGIN DESCRIPTION:
NAVASOTA RIVER 150
END DESCRIPTION:
XS GIS Cut Line= 3
      3564681.85      10402656.6      3558369.36     10401698.27
      3556452.68      10402281.6
#Sta/Elev= 30
  -440.7  327.97  -311.1  331.49  -116.7  320.35   -17.4  311.93   317.6  288.72
  2169.2  287.92  2287.8  279.14  2361.5  288.33    2695  281.77  2846.3   285.9
  2927.4  278.41  3028.4  287.89  3885.1  283.15  4828.7  283.32  4960.4  289.18
  4980.5  274.96  5000.4  271.25  5041.1  285.16  5071.5  288.32  5589.5  281.54
  5603.4  281.55  5717.8  285.63  6683.4  289.04  6866.1  298.31  7093.9  319.61
  7205.1  331.43  7417.9  337.16  7603.3  330.01  7721.2  341.24  7947.6  344.73
#Mann= 13 ,-1 , 0
  -440.7     .05       0  -116.7     .08       0   -17.4     .05       0
  2169.2     .12       0  2927.4     .05       0  3885.1     .12       0
  4960.4     .07       0  5071.5     .12       0  5589.5      .1       0
  5603.4     .12       0  5717.8     .05       0  7093.9     .16       0
  7721.2     .05       0
Bank Sta=4960.4,5071.5
XS Rating Curve= 0 ,0
Exp/Cntr=0.3,0.1

Type RM Length L Ch R = 1 ,560794  ,1153,1153,1153
BEGIN DESCRIPTION:
NAVASOTA RIVER 326
END DESCRIPTION:
XS GIS Cut Line= 3
      3565081.34     10402596.89      3559874.25     10400977.79
      3554331.34     10400921.02
#Sta/Elev= 30
    -453  336.21   389.5  296.84   804.4   298.5   904.6   290.4  1601.6  287.21
  1693.8  287.02    2847  287.23  3064.9  278.55  3396.1  287.88  4175.9  284.81
  4935.3  287.11  4949.9  286.19  4967.9  272.49  4998.3  270.26  5062.1  284.04
  5142.2  286.71  5441.6  283.14  5628.6  287.02  5823.7  286.45  6129.1  286.72
  6295.1  286.97    7031  286.28  8072.4   285.8  8373.5     287  9022.7  290.59
  9652.4  307.34  9872.4  331.98   10268  333.86 10525.7  346.12 10543.2   345.6
#Mann= 20 ,-1 , 0
    -453     .05       0   804.4     .08       0   904.6     .05       0
  1601.6      .1       0  1693.8     .05       0    2847     .12       0
  3396.1     .05       0  4175.9     .12       0  4935.3     .07       0
  5142.2     .12       0  5441.6     .16       0  5628.6     .05       0
  5823.7     .12       0  6129.1     .16       0  6295.1     .05       0
    7031     .12       0  8072.4     .05       0  8373.5     .16       0
   10268     .05       0 10525.7     .16       0
Bank Sta=4935.3,5142.2
XS Rating Curve= 0 ,0
Exp/Cntr=0.3,0.1

Type RM Length L Ch R = 1 ,559641  ,1750,1750,1750
BEGIN DESCRIPTION:
NAVASOTA RIVER 327
END DESCRIPTION:
XS GIS Cut Line= 2
      3565216.06     10400183.99      3553540.72     10399993.01
#Sta/Elev= 30
   235.4  337.53   469.4  334.64   989.5   292.4  1586.6  289.91  2087.2  286.97
  2475.5  286.06  4313.7  286.24  4689.9  285.66    4810  273.05  4959.7  285.48
    4980  272.95  5019.7  270.81    5110  286.52    5430  286.22    5450  278.68
  5599.8  284.92    6031  286.44  6963.7  286.06    7325  286.75  7663.6  286.77
  7793.8  287.04  7907.5  281.47  8163.2  287.04  9021.9  285.39  9293.8  284.95
  9572.1  285.31 10070.7  289.23 10800.7  312.98 11463.1  331.23 11912.3  360.74
#Mann= 20 ,-1 , 0
   235.4     .05       0  1586.6     .05       0  2087.2      .1       0
  2475.5     .05       0  4313.7     .12       0  4959.7     .07       0
    5110     .12       0  5599.8     .16       0    6031     .05       0
  6963.7     .16       0    7325     .05       0  7663.6     .12       0
  7793.8     .07       0  7907.5     .16       0  8163.2     .05       0
  9021.9     .07       0  9293.8     .12       0  9572.1     .05       0
 10800.7     .05       0 11463.1     .16       0
Bank Sta=4959.7,5110
XS Rating Curve= 0 ,0
Exp/Cntr=0.3,0.1

Type RM Length L Ch R = 1 ,557891  ,2865,2865,2865
BEGIN DESCRIPTION:
NAVASOTA RIVER 328
END DESCRIPTION:
XS GIS Cut Line= 3
      3565186.51     10400001.69      3560535.71     10399157.48
      3553586.03     10398842.89
#Sta/Elev= 30
   273.2  337.97     674  329.78  1222.9  289.66  1600.3  288.28  2057.2  286.41
  3014.3   285.7  3249.9  285.55  4139.4  282.31  4302.4  285.02  4335.4  278.38
  4353.2  285.17  4953.3  285.59  4983.1   269.7  5023.6  270.95  5053.7  284.99
  5574.3  283.99  6119.3  285.38  6838.8  284.71  7175.1  285.21  7897.5  286.91
    8261  286.61  8542.2  286.27  9174.4  285.76  9590.8  284.04 10777.4  309.25
 10949.7  317.87 11099.8  313.91 11380.5  328.09 11902.5  364.14 11956.8  366.63
#Mann= 20 ,-1 , 0
   273.2     .05       0  1600.3     .05       0  2057.2      .1       0
  3014.3      .1       0  3249.9     .05       0  4139.4     .12       0
  4953.3     .07       0  5053.7     .12       0  5574.3     .16       0
  6119.3     .05       0  6838.8      .1       0  7175.1     .05       0
  7897.5     .12       0    8261     .12       0  8542.2     .05       0
  9174.4     .12       0  9590.8     .05       0 10777.4     .16       0
 11380.5     .05       0 11902.5     .05       0
Bank Sta=4953.3,5053.7
XS Rating Curve= 0 ,0
Exp/Cntr=0.3,0.1

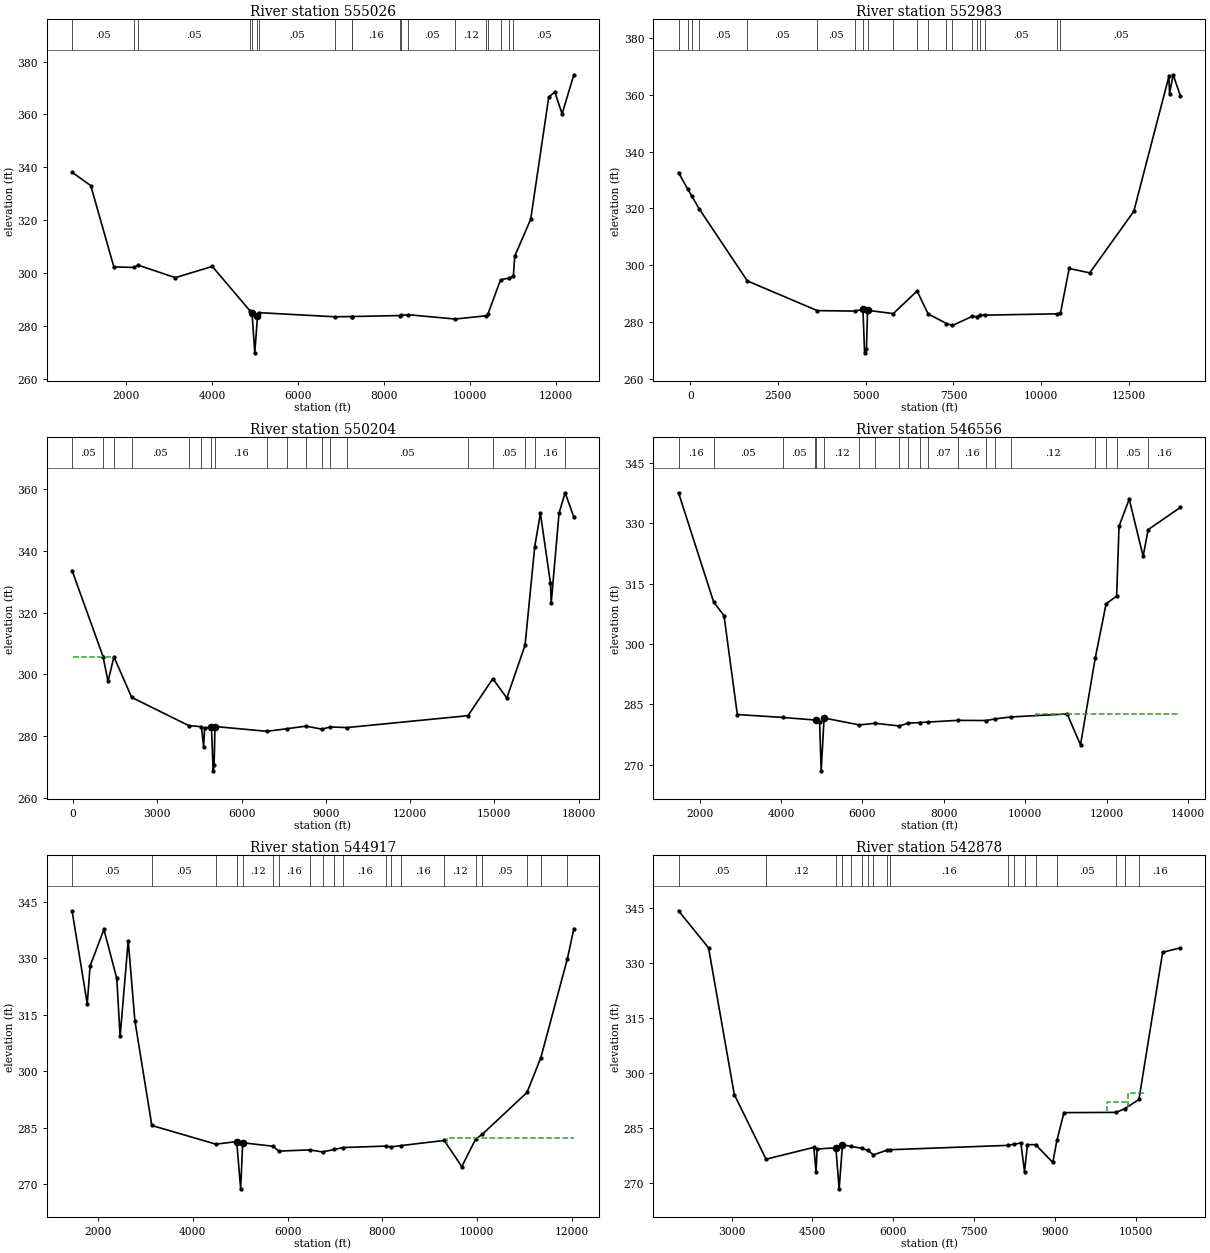
Type RM Length L Ch R = 1 ,555026  ,2043,2043,2043
BEGIN DESCRIPTION:
NAVASOTA RIVER 153
END DESCRIPTION:
XS GIS Cut Line= 3
      3565592.98     10399712.85      3561771.82     10397842.38
      3554358.69     10397518.63
#Sta/Elev= 30
   745.6  338.13  1180.8  333.06  1717.9  302.29  2181.9  302.09  2289.9  302.91
  3146.9  298.22  4007.7  302.47  4882.2  285.72  4932.9  284.78  4996.8  269.75
  5059.8  283.55  5089.6  284.97  6864.9   283.4    7255   283.5  7262.6   283.5
  8379.7  283.87  8404.4  283.91    8572  284.18    9656  282.55 10376.5  283.78
 10419.8  284.39 10716.1  297.43 10913.5  298.04 11012.3  298.72 11045.5   306.4
 11415.8  320.32 11836.2  366.58 11976.4  368.54 12146.5  360.25 12420.2  375.04
#Mann= 19 ,-1 , 0
   745.6     .05       0  2181.9     .08       0  2289.9     .05       0
  4882.2     .12       0  4932.9     .07       0  5059.8     .12       0
  5089.6     .05       0  6864.9     .16       0    7255     .05       0
  7262.6     .16       0  8379.7     .12       0  8404.4     .16       0
    8572     .05       0    9656     .12       0 10376.5     .07       0
 10419.8     .05       0 10716.1     .15       0 10913.5      .1       0
 11012.3     .05       0
Bank Sta=4932.9,5059.8
XS Rating Curve= 0 ,0
Exp/Cntr=0.3,0.1

Type RM Length L Ch R = 1 ,552983  ,2779,2779,2779
BEGIN DESCRIPTION:
NAVASOTA RIVER 152
END DESCRIPTION:
XS GIS Cut Line= 3
      3567554.74     10398352.51      3559243.06     10394901.97
      3554405.37     10397093.03
#Sta/Elev= 30
  -338.5  332.61   -73.1  326.72    42.3  324.28   252.8  319.83  1624.1   294.5
  3619.2  284.05  4683.7   283.9  4920.1  284.51  4967.6   269.2    5021  270.71
  5050.3  283.54  5074.2  284.12  5786.7  283.01  6463.6  290.96  6779.4   282.9
  7302.7  279.52  7473.4  278.83  8042.6  282.08  8164.2  281.89  8271.2  282.48
  8415.5  282.47   10442  282.92 10552.5  283.08 10801.2  298.88 11388.5  297.34
 12644.4  318.99 13646.3  366.48 13663.9  360.43 13767.2  367.04 13971.7  359.73
#Mann= 20 ,-1 , 0
  -338.5     .08       0   -73.1     .08       0    42.3     .05       0
   252.8     .05       0  1624.1     .05       0  3619.2     .05       0
  4683.7     .12       0  4920.1     .07       0  5074.2     .12       0
  5786.7     .05       0  6463.6     .15       0  6779.4     .16       0
  7302.7     .12       0  7473.4     .16       0  8042.6     .05       0
  8164.2     .07       0  8271.2     .05       0  8415.5     .05       0
   10442     .07       0 10552.5     .05       0
Bank Sta=4920.1,5074.2
XS Rating Curve= 0 ,0
Exp/Cntr=0.3,0.1

Type RM Length L Ch R = 1 ,550204  ,3648,3648,3648
BEGIN DESCRIPTION:
NAVASOTA RIVER 151
END DESCRIPTION:
XS GIS Cut Line= 3
      3568314.26     10396355.97      3558505.21     10392862.04
      3551496.42     10395379.13
#Sta/Elev= 30
   -30.6  333.66  1072.4  305.78  1249.9  297.71  1458.1  305.71  2090.8  292.56
  4132.8  283.38  4573.4  283.08  4653.1  276.47  4684.9  282.52  4929.1  283.07
  4992.5  268.77  5024.6  270.54  5056.5  283.13  6902.8  281.57  7632.1  282.43
  8297.2  283.25  8867.2  282.26  9158.2  282.99  9745.4  282.78 14059.9  286.64
 14945.1  298.62 15443.1  292.34 16092.2  309.47 16436.1  341.35 16638.4   352.2
 16996.6  329.52   17022  323.07 17302.5  352.29 17519.7  358.84 17829.2  350.94
#Mann= 19 ,-1 , 0
   -30.6     .05       0  1072.4     .16       0  1458.1     .05       0
  2090.8     .05       0  4132.8     .05       0  4573.4     .12       0
  4929.1     .07       0  5056.5     .16       0  6902.8     .05       0
  7632.1     .16       0  8297.2     .12       0  8867.2     .05       0
  9158.2     .16       0  9745.4     .05       0 14059.9     .16       0
 14945.1     .05       0 16092.2      .1       0 16436.1     .16       0
 17519.7     .05       0
#XS Ineff= 2 , 0
       0    1455  305.74               0
Permanent Ineff=
       F       F
Bank Sta=4929.1,5056.5
XS Rating Curve= 0 ,0
Exp/Cntr=0.3,0.1

Type RM Length L Ch R = 1 ,546556  ,1639,1639,1639
BEGIN DESCRIPTION:
NAVASOTA RIVER 154
END DESCRIPTION:
XS GIS Cut Line= 3
      3569084.62     10392825.87      3561131.08     10392167.59
      3558440.09     10388760.45
#Sta/Elev= 30
  1484.9  337.59  2348.1  310.43  2601.2  307.09  2928.8  282.51  4042.8  281.78
  4840.1  281.14  4848.9  281.13  4949.2  280.67  4987.6  268.52  5059.6  281.64
  5921.9  279.93  6317.2  280.33  6910.1  279.66  7107.8  280.34  7404.3  280.51
  7601.9  280.63  8339.3  281.06  9046.9  281.02  9261.8  281.43  9648.8  281.91
 11027.8  282.65 11356.3  274.98 11717.2  296.49   11985  310.02 12243.2  311.92
 12302.1  329.25 12552.1  336.03 12893.6  321.82 13017.9  328.45 13807.3  333.95
#Mann= 20 ,-1 , 0
  1484.9     .16       0  2348.1     .05       0  4042.8     .05       0
  4840.1     .12       0  4848.9     .07       0  5059.6     .12       0
  5921.9     .05       0  6317.2     .16       0  6910.1     .16       0
  7107.8     .12       0  7404.3     .16       0  7601.9     .07       0
  8339.3     .16       0  9046.9     .12       0  9261.8     .16       0
  9648.8     .12       0 11717.2     .16       0   11985     .15       0
 12243.2     .05       0 13017.9     .16       0
#XS Ineff= 2 , 0
       0                 10266.1       0  282.73
Permanent Ineff=
       F       F
Bank Sta=4848.9,5059.6
XS Rating Curve= 0 ,0
Exp/Cntr=0.3,0.1

Type RM Length L Ch R = 1 ,544917  ,2039,2039,2039
BEGIN DESCRIPTION:
NAVASOTA RIVER 329
END DESCRIPTION:
XS GIS Cut Line= 4
      3569070.88     10391497.75      3566510.13     10391758.16
      3565581.52     10391461.85      3558898.77     10389241.99
#Sta/Elev= 30
  1451.3  342.61  1771.7  317.89  1831.4  327.93  2123.5  337.64  2394.9  324.64
  2465.3  309.22  2636.2  334.68  2776.9  313.45  3134.5  285.59  4488.1  280.62
  4925.9  281.32  5009.7  268.76  5052.8     281  5692.5  280.07  5811.9  278.78
  6467.6   279.1  6736.9  278.56  6988.8  279.22  7171.4  279.73  8072.3  280.11
  8175.7   279.9  8397.3  280.25  9306.2  281.61  9676.1  274.66  9967.5  281.94
 10110.2  283.26 11053.3  294.36 11344.8  303.61   11903  329.76 12041.8  337.85
#Mann= 20 ,-1 , 0
  1451.3     .05       0  3134.5     .05       0  4488.1     .12       0
  4925.9     .07       0  5052.8     .12       0  5692.5     .12       0
  5811.9     .16       0  6467.6     .05       0  6736.9     .16       0
  6988.8     .05       0  7171.4     .16       0  8072.3     .05       0
  8175.7     .16       0  8397.3     .16       0  9306.2     .12       0
  9967.5     .16       0 10110.2     .05       0 11053.3     .08       0
 11344.8     .05       0   11903     .16       0
#XS Ineff= 2 , 0
       0                  9359.5       0  282.17
Permanent Ineff=
       F       F
Bank Sta=4925.9,5052.8
XS Rating Curve= 0 ,0
Exp/Cntr=0.3,0.1

Type RM Length L Ch R = 1 ,542878  ,1166,1166,1166
BEGIN DESCRIPTION:
NAVASOTA RIVER 330
END DESCRIPTION:
XS GIS Cut Line= 4
      3567920.69     10389870.15       3566054.4     10390195.66
      3564987.97     10389976.93      3558795.84     10388700.58
#Sta/Elev= 30
  2016.9  344.31  2573.6  334.19  3050.9  294.15  3640.4   276.5  4526.2  279.74
    4567  273.04  4587.4  279.27  4934.5  279.63  4995.1  268.41    5057  280.42
    5224  279.98  5416.2  279.48  5530.4  278.88  5630.5  277.69  5885.4  278.97
  5930.7  279.08  8132.3  280.28  8232.4  280.56  8364.9  280.94  8432.6  273.14
  8487.7  280.46  8638.4  280.47  8957.3  275.62  9033.7  281.65  9164.5  289.21
 10133.3  289.28   10289  290.26 10554.7   292.8 10994.7  332.98 11322.3  334.19
#Mann= 18 ,-1 , 0
  2016.9     .05       0  3640.4     .12       0  4934.5     .07       0
    5057     .16       0    5224     .12       0  5416.2     .16       0
  5530.4     .05       0  5630.5     .16       0  5885.4     .05       0
  5930.7     .16       0  8132.3     .05       0  8232.4     .16       0
  8432.6     .12       0  8638.4     .16       0  9033.7     .05       0
 10133.3     .16       0   10289     .05       0 10554.7     .16       0
#XS Ineff= 4 ,-1
  8364.9  9164.5  280.94  9164.5  9958.9  289.21  9958.9 10345.9     292
 10345.9   10642  294.55
Permanent Ineff=
       F       F       F       F
Bank Sta=4934.5,5057
XS Rating Curve= 0 ,0
Exp/Cntr=0.3,0.1

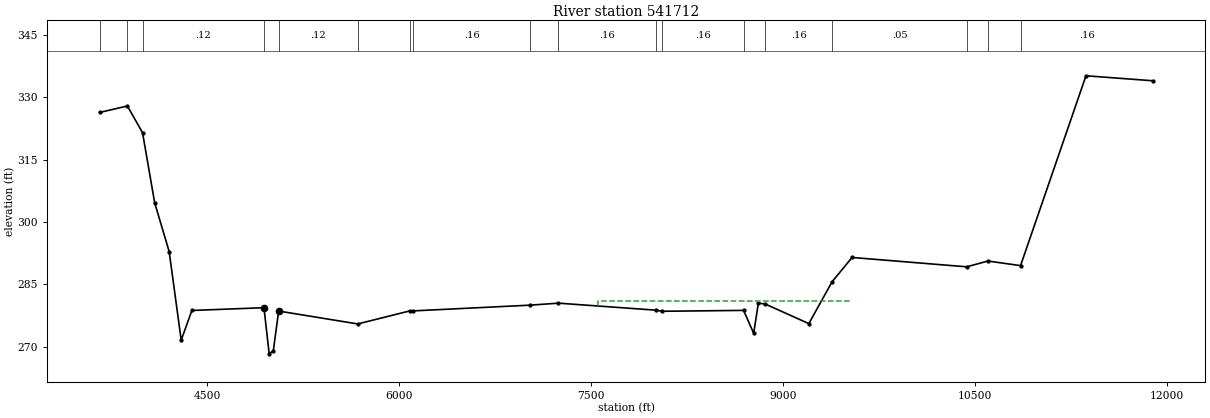
Type RM Length L Ch R = 1 ,541712  ,3047,3047,3047
BEGIN DESCRIPTION:
NAVASOTA RIVER 155
END DESCRIPTION:
XS GIS Cut Line= 3
      3566640.34     10388936.98      3564318.29     10389501.22
      3558546.41     10388589.87
#Sta/Elev= 30
  3658.1  326.32  3875.1  327.87  3993.5  321.46  4088.5  304.57  4201.7  292.86
  4295.7  271.55  4379.2  278.69  4942.7  279.36  4983.6  268.26  5015.9  268.99
  5057.6  278.55  5675.8  275.45  6080.8  278.57  6108.6  278.59  7023.9  279.97
  7244.1  280.45  8003.8  278.77  8057.8   278.5  8692.5  278.71  8771.1   273.2
  8807.7  280.44  8859.8  280.26  9202.5  275.53  9384.1  285.59  9540.5  291.44
 10436.6  289.19 10602.1  290.58 10857.6  289.48   11369  335.14 11891.1  333.94
#Mann= 18 ,-1 , 0
  3658.1     .05       0  3875.1     .16       0  3993.5     .12       0
  4942.7     .07       0  5057.6     .12       0  5675.8     .16       0
  6080.8     .05       0  6108.6     .16       0  7023.9     .12       0
  7244.1     .16       0  8003.8     .12       0  8057.8     .16       0
  8692.5     .12       0  8859.8     .16       0  9384.1     .05       0
 10436.6     .16       0 10602.1     .05       0 10857.6     .16       0
#XS Ineff= 2 ,-1
  7554.6  9540.5  280.97  9540.5 10974.2  291.44
Permanent Ineff=
       F       F
Bank Sta=4942.7,5057.6
XS Rating Curve= 0 ,0
Exp/Cntr=0.3,0.1