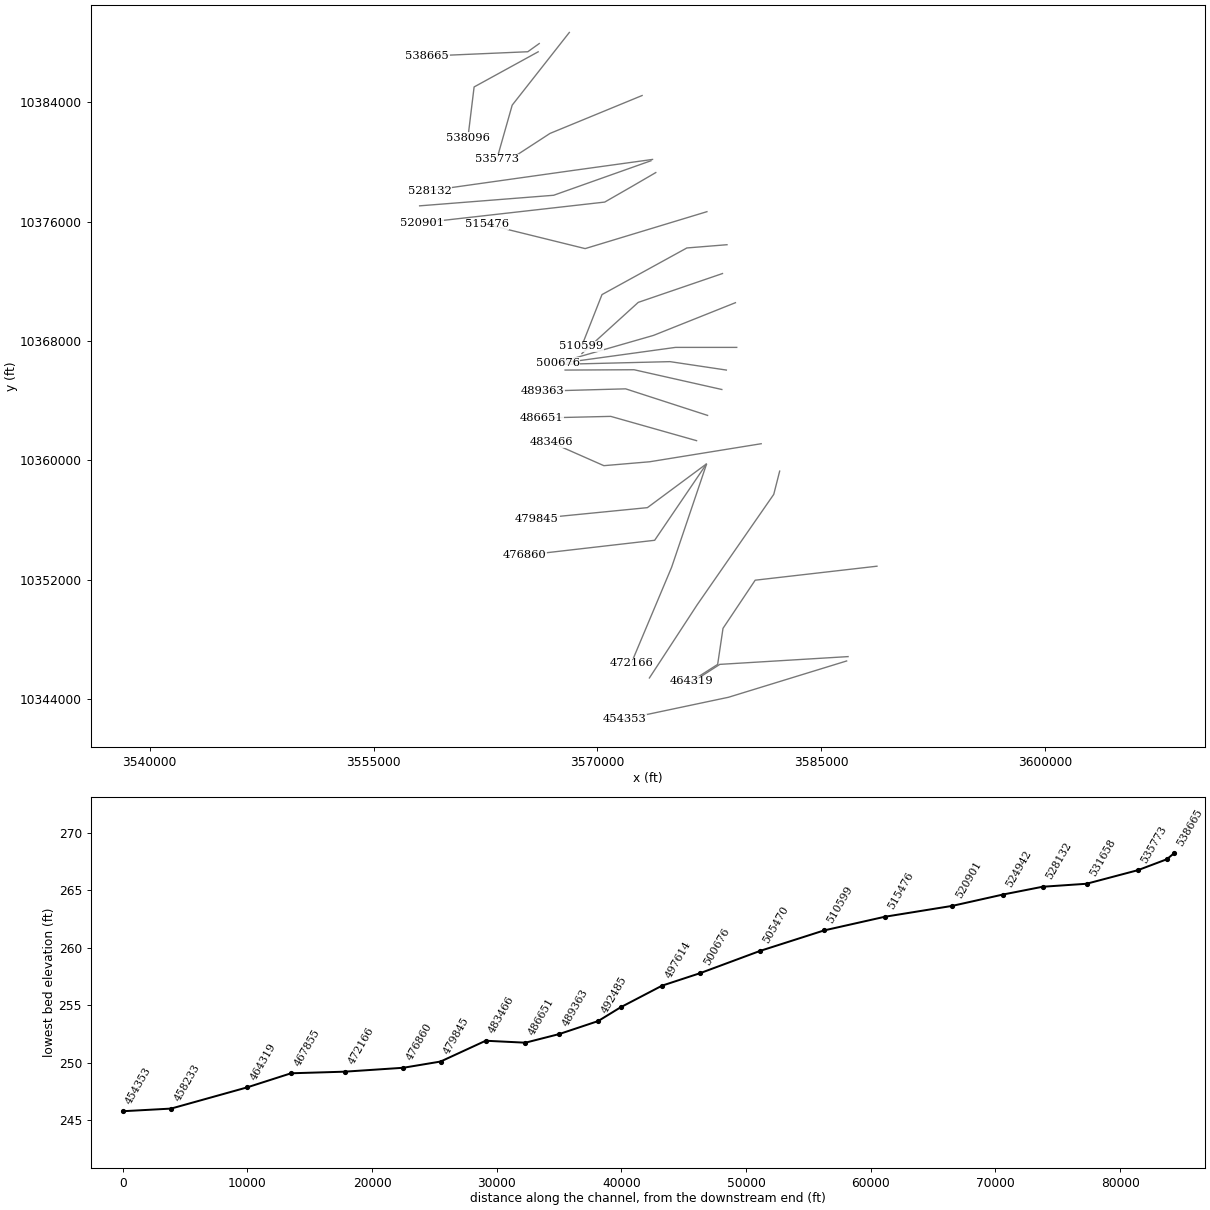
HEC-RAS study NAVASOTA RIVER.prj: NAVASOTA RIVER Base Level Engineering

--- NAVASOTA RIVER.g01 (geometry) --- (continued)

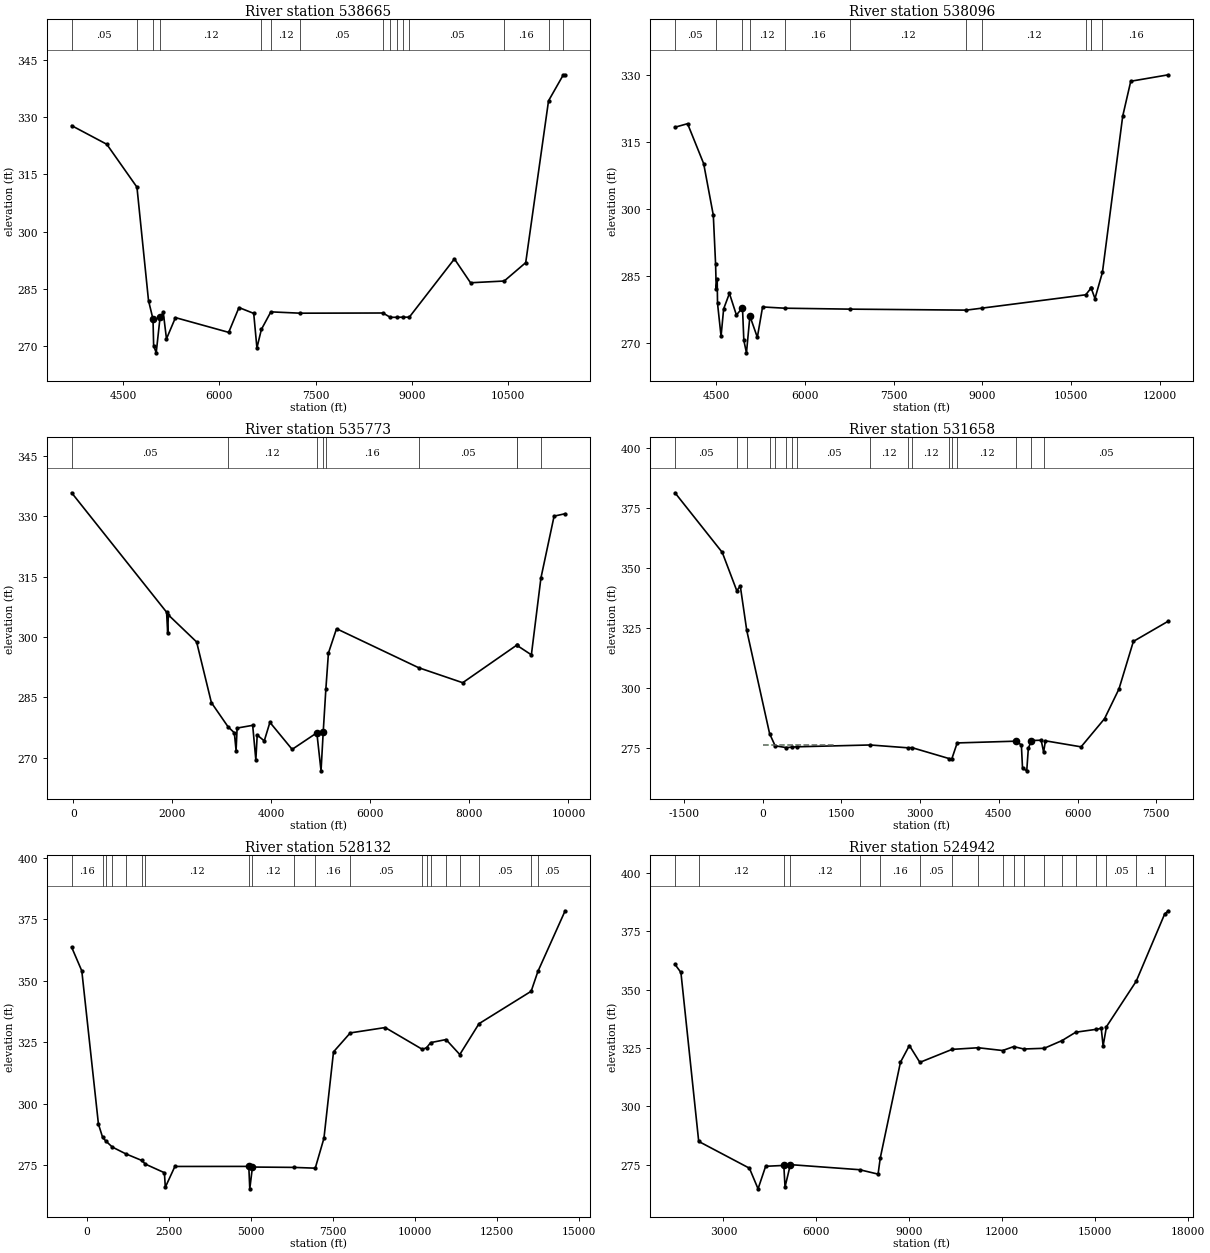
Type RM Length L Ch R = 1 ,538665  ,569,569,569
BEGIN DESCRIPTION:
NAVASOTA RIVER 331
END DESCRIPTION:
XS GIS Cut Line= 3
        3566105.     10387933.97      3565336.67     10387384.83
      3558587.52     10387091.86
#Sta/Elev= 30
  3694.2  327.81  4242.3  322.92    4713  311.67  4893.4  281.93  4963.5  277.04
  4973.5   270.1  5013.3  268.21  5073.6  277.51  5123.6  278.83  5173.7  271.88
  5313.8  277.45  6144.6  273.58  6304.7  280.09  6534.9  278.56    6585  269.49
  6654.3  274.35  6802.3  278.96  7259.3  278.61  8551.1  278.66  8666.4  277.52
  8765.2  277.54  8863.9  277.56  8962.6  277.57  9666.4  292.85  9918.1  286.59
 10443.6  287.05 10778.9  291.87 11134.8  334.32   11366  341.15 11394.1  340.98
#Mann= 15 ,-1 , 0
  3694.2     .05       0    4713     .12       0  4963.5     .07       0
  5073.6     .12       0  6654.3     .16       0  6802.3     .12       0
  7259.3     .05       0  8551.1     .12       0  8666.4     .07       0
  8765.2     .05       0  8863.9     .07       0  8962.6     .05       0
 10443.6     .16       0 11134.8     .05       0   11366     .16       0
#XS Ineff= 2 ,-1
  6304.7  9666.4  280.09  9666.4   10829  292.85
Permanent Ineff=
       F       F
Bank Sta=4963.5,5073.6
XS Rating Curve= 0 ,0
Exp/Cntr=0.3,0.1

Type RM Length L Ch R = 1 ,538096  ,2323,2323,2323
BEGIN DESCRIPTION:
NAVASOTA RIVER 157
END DESCRIPTION:
XS GIS Cut Line= 3
      3566031.84     10387379.69      3561740.17     10385025.52
      3561323.51     10381608.89
#Sta/Elev= 30
  3805.9   318.3  4018.4  319.09  4290.4  310.13  4453.4  298.56  4491.6  287.65
  4502.7  282.09  4518.8  284.19  4524.5  278.79  4584.2  271.42  4627.8  277.56
  4725.4  281.03  4843.5  276.18  4946.2  277.81    4969   270.5  5013.3   267.7
  5071.6  275.94  5197.1  271.18  5285.6  277.99  5662.3  277.71  6765.4   277.5
  8728.6  277.28  8988.9  277.72 10745.2  280.72 10831.7  282.18 10839.1  282.14
 10900.9  279.87 11026.9  285.75 11369.5  320.78 11505.4  328.61 12142.8  330.06
#Mann= 12 ,-1 , 0
  3805.9     .05       0  4491.6     .12       0  4946.2     .07       0
  5071.6     .12       0  5662.3     .16       0  6765.4     .12       0
  8728.6     .16       0  8988.9     .12       0 10745.2      .1       0
 10831.7     .05       0 10839.1     .12       0 11026.9     .16       0
Bank Sta=4946.2,5071.6
XS Rating Curve= 0 ,0
Exp/Cntr=0.3,0.1

Type RM Length L Ch R = 1 ,535773  ,4115,4115,4115
BEGIN DESCRIPTION:
NAVASOTA RIVER 156
END DESCRIPTION:
XS GIS Cut Line= 3
       3568120.4     10388676.59      3564292.25     10383806.77
      3563261.85     10380176.93
#Sta/Elev= 30
   -35.1  335.79  1882.6  306.14  1904.6  300.98  1917.8  305.47  2488.9  298.75
  2787.2  283.69  3123.2   277.7  3250.8  276.19    3286   271.8  3306.8  277.37
  3621.3  278.05  3685.4  269.43  3712.6  275.63  3855.4  274.19  3969.3  278.79
  4418.4  272.08  4917.2  276.19    5002  266.75  5045.6  276.31  5099.3  287.03
  5151.4     296  5314.9  302.04  6970.7  292.37  7863.4  288.63  8953.9  297.95
  8954.1  297.95  9250.4  295.55    9443   314.6  9709.3  329.99  9932.5  330.59
#Mann= 9 ,-1 , 0
   -35.1     .05       0  3123.2     .12       0  4917.2     .07       0
  5045.6     .12       0  5099.3     .16       0  6970.7     .05       0
  8953.9     .16       0  8954.1     .12       0    9443     .16       0
Bank Sta=4917.2,5045.6
XS Rating Curve= 0 ,0
Exp/Cntr=0.3,0.1

Type RM Length L Ch R = 1 ,531658  ,3526,3526,3526
BEGIN DESCRIPTION:
NAVASOTA RIVER 339
END DESCRIPTION:
XS GIS Cut Line= 3
      3572996.62     10384450.91      3566827.22     10381912.26
      3564536.01     10380422.04
#Sta/Elev= 30
 -1671.3  381.35  -770.5  356.53  -494.3  340.61  -426.6  342.47  -303.8  324.05
   131.8  281.06   236.9  275.99   447.2  275.25   552.3  275.42   653.4  275.58
  2047.7  276.34    2771  275.15  2841.4  275.25  3555.2  270.66  3601.4  270.37
  3706.5  277.19  4834.4  277.93  4929.8  276.33  4951.5  266.71    5032  265.57
  5062.5  274.92  5119.9  278.19    5307  278.32  5354.1  273.36  5387.8  278.07
  6067.8  275.56  6514.7  287.28  6789.4  299.65  7064.2  319.46  7733.2  327.94
#Mann= 17 ,-1 , 0
 -1671.3     .05       0  -494.3     .16       0  -303.8     .05       0
   131.8     .16       0   236.9     .12       0   447.2     .05       0
   552.3     .12       0   653.4     .05       0  2047.7     .12       0
    2771     .07       0  2841.4     .12       0  3555.2     .05       0
  3601.4     .07       0  3706.5     .12       0  4834.4     .07       0
  5119.9     .12       0  5354.1     .05       0
#XS Ineff= 2 , 0
       0  1340.4   276.5               0
Permanent Ineff=
       F       F
Bank Sta=4834.4,5119.9
XS Rating Curve= 0 ,0
Exp/Cntr=0.3,0.1

Type RM Length L Ch R = 1 ,528132  ,3190,3190,3190
BEGIN DESCRIPTION:
NAVASOTA RIVER 340
END DESCRIPTION:
XS GIS Cut Line= 3
       3573694.9     10380168.95      3568282.08      10379419.2
      3558786.25     10378081.41
#Sta/Elev= 30
  -464.5  363.53  -154.9  353.91   352.5  291.63   478.9  286.28   578.1  284.74
   776.5  282.29  1183.4  279.56  1669.4  276.88  1787.8  275.34  2365.1  271.86
  2392.6  265.95  2684.7  274.41  4939.4  274.43  4969.4  265.31  5050.5  274.17
  6307.9  274.03  6966.5  273.71  7231.8  285.88  7523.4  320.99  8034.6   328.7
  9099.6  330.88 10235.8     322   10365  322.72 10487.1  324.75 10956.7     326
 11375.6  319.91   11962  332.45 13553.1  345.63 13758.1  353.68 14589.6  378.35
#Mann= 20 ,-1 , 0
  -464.5     .16       0   478.9     .12       0   578.1     .05       0
   776.5     .16       0  1183.4     .12       0  1669.4     .08       0
  1787.8     .12       0  4939.4     .07       0  5050.5     .12       0
  6307.9     .12       0  6966.5     .16       0  8034.6     .05       0
 10235.8     .16       0   10365     .05       0 10487.1     .16       0
 10956.7     .16       0 11375.6     .16       0   11962     .05       0
 13553.1     .16       0 13758.1     .05       0
#XS Ineff= 2 , 0
       0  2684.7  274.41               0
Permanent Ineff=
       F       F
Bank Sta=4939.4,5050.5
XS Rating Curve= 0 ,0
Exp/Cntr=0.3,0.1

Type RM Length L Ch R = 1 ,524942  ,4041,4041,4041
BEGIN DESCRIPTION:
NAVASOTA RIVER 341
END DESCRIPTION:
XS GIS Cut Line= 3
      3573589.05     10380080.01      3567068.26     10377767.52
      3558089.05     10377059.18
#Sta/Elev= 30
  1437.4  360.87  1628.7  357.43  2202.8  284.97  3839.2  273.48  4118.3  264.63
  4362.6   274.3  4949.7  274.67  4988.6  265.43  5160.5  275.01  7396.4  272.83
  7991.3  270.94  8061.8  277.85  8713.4  318.92  9001.2   326.1  9339.5  318.87
   10380  324.44 11224.2  325.14 12009.3  323.95 12368.2  325.63 12694.5   324.6
 13354.2  324.91 13927.3  328.21 14370.6   331.8 15021.3  333.02 15193.4  333.46
 15253.6  325.93 15362.5  334.19 16321.5  353.65 17241.2  382.53 17363.2  383.88
#Mann= 19 ,-1 , 0
  1437.4     .16       0  2202.8     .12       0  4949.7     .07       0
  5160.5     .12       0  7396.4     .05       0  8061.8     .16       0
  9339.5     .05       0   10380     .05       0 11224.2     .16       0
 12009.3      .1       0 12368.2     .05       0 12694.5     .16       0
 13354.2     .05       0 13927.3     .16       0 14370.6     .05       0
 15021.3     .16       0 15362.5     .05       0 16321.5      .1       0
 17241.2     .16       0
#XS Ineff= 2 , 0
       0  4362.6   274.3               0
Permanent Ineff=
       F       F
Bank Sta=4949.7,5160.5
XS Rating Curve= 0 ,0
Exp/Cntr=0.3,0.1

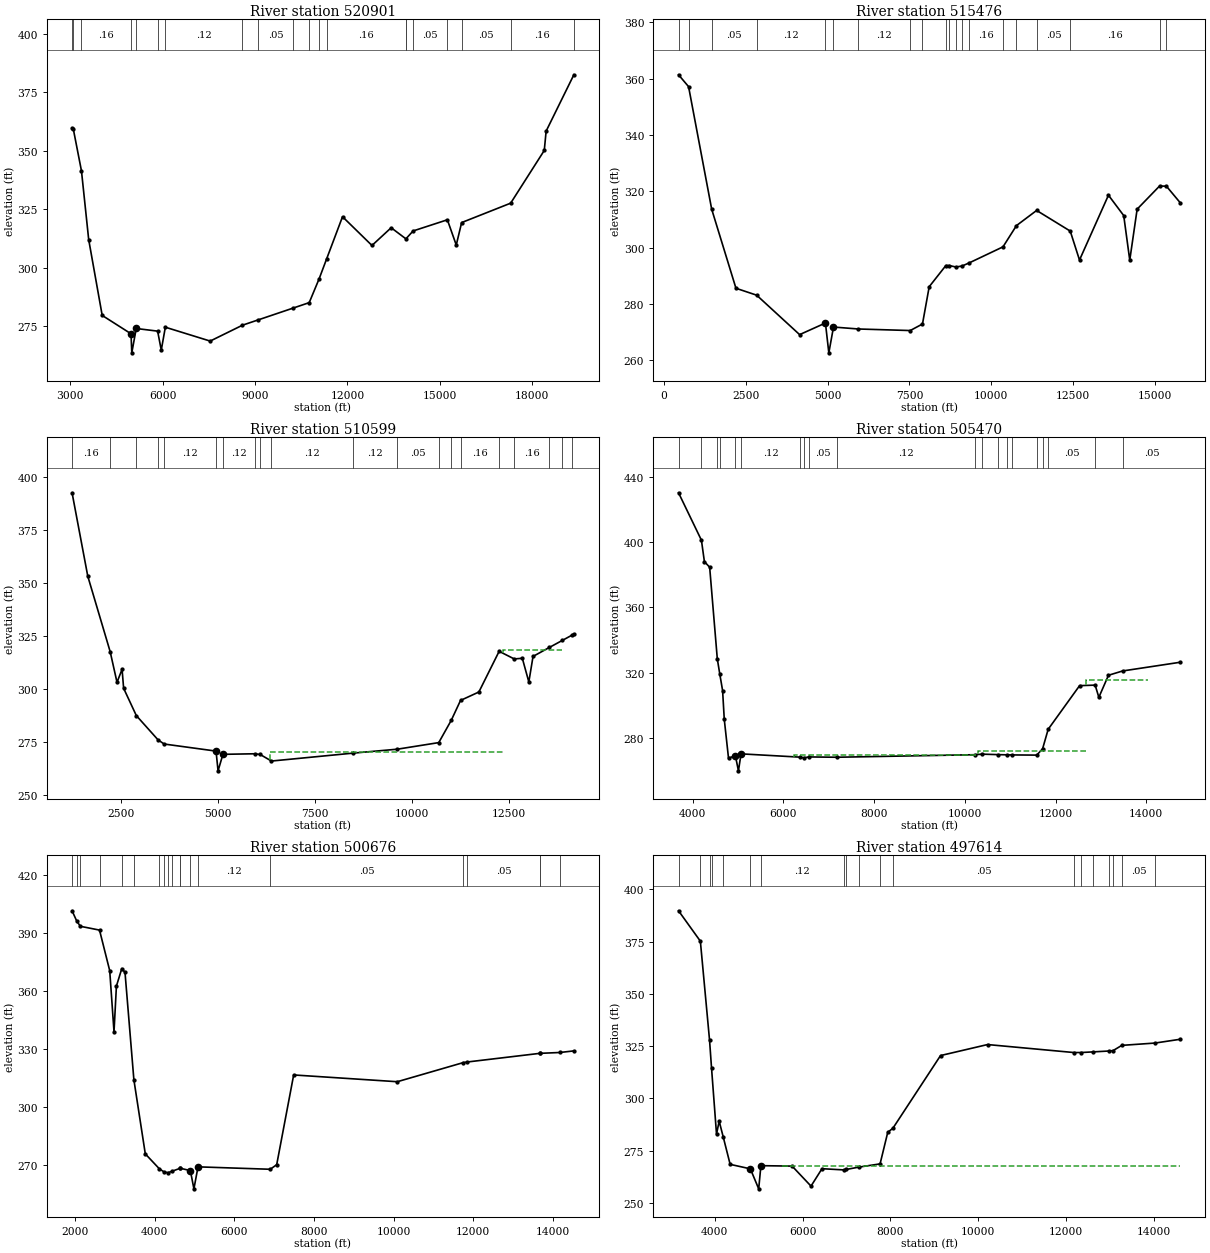
Type RM Length L Ch R = 1 ,520901  ,5425,5425,5425
BEGIN DESCRIPTION:
NAVASOTA RIVER 342
END DESCRIPTION:
XS GIS Cut Line= 4
       3573913.3     10379288.58      3572236.94     10378312.95
      3570491.76     10377311.54      3558227.58     10375922.28
#Sta/Elev= 30
  3060.4  359.62    3102  359.27  3365.7  341.44  3600.4  312.05  4038.9  279.65
  4974.7   271.8  4999.7  263.65  5143.9  274.06    5839  272.93  5956.9  264.81
  6089.3  274.61  7545.1  268.68  8593.9  275.47  9090.9  277.68 10243.5  282.81
 10761.2  285.12 11085.1  295.38 11323.9  303.73 11842.4  321.86 12798.5  309.56
 13422.5  317.14 13900.8   312.4 14134.8  315.77 15247.2  320.54 15535.9  309.75
 15710.5  319.35 17302.6  327.65 18394.1   350.2 18454.5  358.46 19354.7  382.55
#Mann= 20 ,-1 , 0
  3060.4     .16       0    3102     .05       0  3365.7     .16       0
  4974.7     .07       0  5143.9     .12       0    5839     .07       0
  6089.3     .12       0  8593.9     .05       0  9090.9     .05       0
 10243.5     .05       0 10761.2     .16       0 11085.1     .05       0
 11323.9     .16       0 13900.8     .16       0 13900.8      .1       0
 14134.8     .05       0 15247.2     .16       0 15710.5     .05       0
 17302.6     .16       0 19354.7     .16       0
Bank Sta=4974.7,5143.9
XS Rating Curve= 0 ,0
Exp/Cntr=0.3,0.1

Type RM Length L Ch R = 1 ,515476  ,4877,4877,4877
BEGIN DESCRIPTION:
NAVASOTA RIVER 043
END DESCRIPTION:
XS GIS Cut Line= 3
      3577339.99     10376667.88      3569180.27     10374193.93
      3562583.09     10375821.52
#Sta/Elev= 30
   451.3  361.34     758  357.13  1463.4  313.66  2204.6  285.61  2837.2  283.15
  4148.4  269.16  4936.6  273.28  5040.3   262.7  5182.7  271.85  5944.1  271.16
  7525.8  270.61  7899.9  272.93  8105.1  286.16    8614  293.67  8716.1  293.67
  8920.1  293.15    9108   293.5  9330.7  294.63 10358.4   300.3 10769.4  307.84
 11385.3  313.21 12411.6  305.89 12694.2  295.62 13578.2  318.62 14044.7  311.39
 14228.8  295.57 14454.3  313.67 15139.4  321.88 15347.7  321.82 15772.8   315.9
#Mann= 20 ,-1 , 0
   451.3     .05       0     758     .16       0  1463.4     .05       0
  2837.2     .12       0  4936.6     .07       0  5182.7     .12       0
  5944.1     .12       0  7525.8     .05       0  7899.9     .16       0
    8614      .1       0  8716.1     .15       0  8920.1     .16       0
    9108     .16       0  9330.7     .16       0 10358.4     .05       0
 10769.4     .16       0 11385.3     .05       0 12411.6     .16       0
 15139.4     .05       0 15347.7     .16       0
#XS Ineff= 2 , 0
       0  4936.6  273.28               0
Permanent Ineff=
       F       F
Bank Sta=4936.6,5182.7
XS Rating Curve= 0 ,0
Exp/Cntr=0.3,0.1

Type RM Length L Ch R = 1 ,510599  ,5129,5129,5129
BEGIN DESCRIPTION:
NAVASOTA RIVER 181
END DESCRIPTION:
XS GIS Cut Line= 4
      3578685.45     10374454.34      3575994.51     10374237.33
      3570308.74     10371112.33      3568941.57     10367640.13
#Sta/Elev= 30
  1249.8  392.39  1654.5  353.11  2230.7   317.6  2406.9  303.18  2537.3   309.3
  2577.4  300.36  2904.1  287.52  3463.3  276.09  3620.8  274.13  4956.4   270.8
  5008.5  261.51  5133.8  269.28  5947.1  269.54  6092.6  269.21    6383  266.12
  8476.8  269.83  9623.8   271.7 10690.7   274.8 11012.3  285.28 11251.2  294.65
 11723.6  298.62 12245.3  317.77 12635.3  314.17   12842   314.5 13009.9  303.34
 13118.2  315.37 13541.3  319.62   13872   322.9 14120.5  325.37 14169.1  325.85
#Mann= 20 ,-1 , 0
  1249.8     .16       0  2230.7     .12       0  2904.1     .05       0
  3463.3     .16       0  3620.8     .12       0  4956.4     .07       0
  5133.8     .12       0  5947.1     .12       0  6092.6     .07       0
    6383     .12       0  8476.8     .12       0  9623.8     .05       0
 10690.7     .12       0 11012.3     .05       0 11251.2     .16       0
 12245.3     .05       0 12635.3     .16       0 13541.3     .05       0
   13872     .16       0 14120.5     .05       0
#XS Ineff= 2 ,-1
  6356.7 12349.2  270.33 12349.2   13872  318.54
Permanent Ineff=
       F       F
Bank Sta=4956.4,5133.8
XS Rating Curve= 0 ,0
Exp/Cntr=0.3,0.1

Type RM Length L Ch R = 1 ,505470  ,4794,4794,4794
BEGIN DESCRIPTION:
NAVASOTA RIVER 159
END DESCRIPTION:
XS GIS Cut Line= 3
      3578381.64     10372522.91       3572739.3      10370591.5
      3568963.24     10367162.66
#Sta/Elev= 30
    3688  430.15  4192.7  401.08  4258.1  387.98  4374.5   384.5  4542.8  328.37
  4598.4  318.91  4659.6  308.94  4696.2  291.37  4790.1  267.48  4941.2  269.05
  5008.9  259.73  5066.4  270.14  6367.9  268.12  6446.8  267.71  6562.6  268.25
  7180.3  268.06 10230.6  269.62 10382.3  269.96 10733.3  269.66 10932.3  269.54
 11036.1  269.48   11587  269.37 11715.9  273.29 11838.5   285.2 12530.9  311.93
   12874  312.27 12955.9  304.79 13168.1  318.31 13481.2  320.95 14752.3  326.29
#Mann= 20 ,-1 , 0
    3688     .05       0  4192.7     .16       0  4542.8     .16       0
  4598.4     .12       0  4941.2     .07       0  5066.4     .12       0
  6367.9     .05       0  6446.8     .12       0  6562.6     .05       0
  7180.3     .12       0 10230.6     .05       0 10382.3     .16       0
 10733.3     .12       0 10932.3     .16       0 11036.1     .12       0
   11587     .16       0 11715.9     .05       0 11838.5     .05       0
   12874     .16       0 13481.2     .05       0
#XS Ineff= 3 ,-1
  6239.7 10286.7  269.23 10286.7 12679.6  271.83 12679.6 14038.5  315.21
Permanent Ineff=
       F       F       F
Bank Sta=4941.2,5066.4
XS Rating Curve= 0 ,0
Exp/Cntr=0.3,0.1

Type RM Length L Ch R = 1 ,500676  ,3062,3062,3062
BEGIN DESCRIPTION:
NAVASOTA RIVER 158
END DESCRIPTION:
XS GIS Cut Line= 3
      3579249.71     10370569.79      3573759.27     10368377.95
      3567336.42     10366533.56
#Sta/Elev= 30
  1930.4  401.58  2049.7  396.17  2139.9  393.55  2619.5  391.59  2875.4  370.61
    2983  339.02  3043.5  362.64  3178.6   371.7  3259.1   369.7  3481.7  314.22
  3768.3  275.88  4120.5  268.17  4235.7  266.58  4337.4  266.13  4434.2  266.86
  4643.7  268.43  4645.9  268.45  4899.6  267.22  4988.7   257.8  5091.3  269.17
  6904.7  267.92  7066.4   270.3  7492.1  316.69 10092.5  313.19 11751.5  323.09
 11853.1   323.4 13666.8  327.85 13682.6  327.87 14172.3   328.3 14524.6  329.13
#Mann= 20 ,-1 , 0
  1930.4     .05       0  2049.7     .16       0  2139.9     .05       0
  2619.5     .16       0  3178.6     .16       0  3481.7     .05       0
  4120.5     .07       0  4235.7     .12       0  4337.4     .07       0
  4434.2     .12       0  4643.7     .07       0  4645.9     .12       0
  4899.6     .07       0  5091.3     .12       0  6904.7     .05       0
 11751.5     .16       0 11853.1     .05       0 13666.8     .16       0
 13682.6     .05       0 14172.3     .16       0
#XS Ineff= 2 , 0
       0                  5091.3       0  269.17
Permanent Ineff=
       F       F
Bank Sta=4899.6,5091.3
XS Rating Curve= 0 ,0
Exp/Cntr=0.3,0.1

Type RM Length L Ch R = 1 ,497614  ,3322,3322,3322
BEGIN DESCRIPTION:
NAVASOTA RIVER 184
END DESCRIPTION:
XS GIS Cut Line= 3
      3579336.55       10367575.      3575234.96       10367575.
      3567986.87     10366576.76
#Sta/Elev= 30
  3178.9  389.78  3675.7  375.23    3885  327.76    3929  314.74  4043.3  282.87
  4103.3  289.11  4197.8  281.38  4353.3  268.43  4813.3  266.28  5003.1  256.71
  5053.3   267.8  5763.3  267.59  6193.3  258.01  6443.3  266.35  6935.6  265.77
  6991.8  265.97  7280.5   267.1  7764.9  268.65  7939.5  283.76    8057  285.72
  9140.7  320.49 10210.7  325.76   12174  321.94 12333.9  321.94 12620.4  322.26
 12972.9  322.67 13067.7  322.87 13265.7  325.37 14022.9  326.48   14597   328.3
#Mann= 19 ,-1 , 0
  3178.9     .05       0  3675.7     .16       0    3885     .12       0
    3929     .16       0  4197.8     .12       0  4813.3     .07       0
  5053.3     .12       0  6935.6     .05       0  6991.8     .16       0
  7280.5     .12       0  7764.9     .16       0    8057     .05       0
   12174     .16       0 12333.9     .05       0 12620.4     .16       0
 12972.9     .05       0 13067.7     .16       0 13265.7     .05       0
 14022.9     .16       0
#XS Ineff= 2 , 0
       0                  5533.3       0  267.66
Permanent Ineff=
       F       F
Bank Sta=4813.3,5053.3
XS Rating Curve= 0 ,0
Exp/Cntr=0.3,0.1

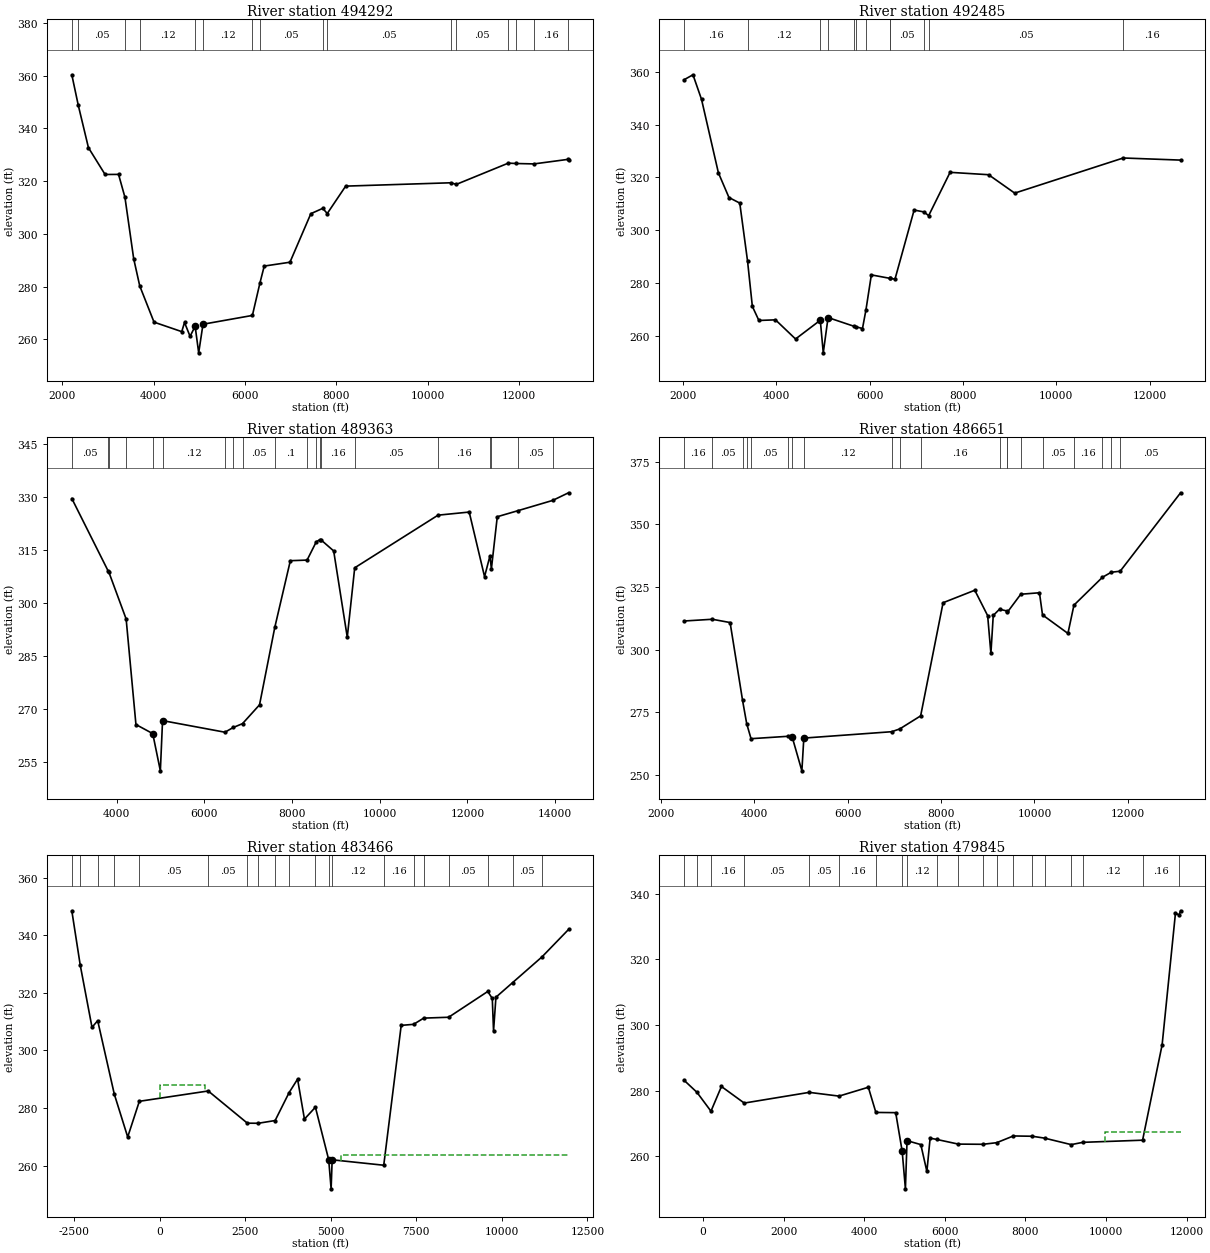
Type RM Length L Ch R = 1 ,494292  ,1807,1807,1807
BEGIN DESCRIPTION:
NAVASOTA RIVER 183
END DESCRIPTION:
XS GIS Cut Line= 3
      3578642.08      10366055.9      3574866.04     10366620.14
      3567813.04     10366446.53
#Sta/Elev= 30
  2210.3  360.39  2352.1  348.78  2574.3  332.71  2938.3  322.54  3233.4  322.57
  3373.2  313.88  3564.4  290.59  3697.3  280.23    4010  266.48  4616.7  262.88
  4677.4  266.36  4798.7   261.1  4909.9  264.92  4987.4  254.83  5081.8  265.69
  6163.2  269.03  6328.8  281.39  6422.3  287.77  6985.3  289.23  7442.6  307.66
  7703.1  309.68  7801.8  307.72  8205.1  318.12 10506.3  319.39 10628.5  318.79
 11765.2  326.85 11931.1  326.71 12325.8  326.55   13064  328.26 13083.4  328.17
#Mann= 16 ,-1 , 0
  2210.3     .16       0  2352.1     .05       0  3373.2     .16       0
  3697.3     .12       0  4909.9     .07       0  5081.8     .12       0
  6163.2     .16       0  6328.8     .05       0  7703.1      .1       0
  7801.8     .05       0 10506.3     .15       0 10628.5     .05       0
 11765.2     .16       0 11931.1     .05       0 12325.8     .16       0
   13064     .05       0
Bank Sta=4909.9,5081.8
XS Rating Curve= 0 ,0
Exp/Cntr=0.3,0.1

Type RM Length L Ch R = 1 ,492485  ,3122,3122,3122
BEGIN DESCRIPTION:
NAVASOTA RIVER 182
END DESCRIPTION:
XS GIS Cut Line= 3
      3578338.29     10364753.81      3572457.18     10366077.61
      3567835.99     10366055.91
#Sta/Elev= 30
  2016.8  356.94  2212.3  358.86  2395.6  349.55  2757.2  321.76  2983.8  312.41
  3215.5   310.3  3382.3  288.35  3485.3  271.21  3625.4  265.88  3980.9  266.12
  4411.4  258.87  4941.7  265.97  5005.7  253.63  5108.5  266.98  5668.5  263.66
  5712.2  263.46  5846.5  262.84  5920.4  269.84  6036.5  283.13  6438.2  281.81
  6446.7  281.79  6543.5  281.53  6953.5  307.67  7162.8  306.96    7265  305.54
  7724.6  321.94  8550.1  321.04  9110.1  314.07   11437  327.37 12666.3  326.57
#Mann= 12 ,-1 , 0
  2016.8     .16       0  3382.3     .12       0  4941.7     .07       0
  5108.5     .12       0  5668.5     .05       0  5712.2     .12       0
  5920.4     .05       0  6438.2     .16       0  6446.7     .05       0
  7162.8     .08       0    7265     .05       0   11437     .16       0
Bank Sta=4941.7,5108.5
XS Rating Curve= 0 ,0
Exp/Cntr=0.3,0.1

Type RM Length L Ch R = 1 ,489363  ,2712,2712,2712
BEGIN DESCRIPTION:
NAVASOTA RIVER 185
END DESCRIPTION:
XS GIS Cut Line= 3
      3577383.38     10363017.72      3571892.95     10364797.22
      3566337.44     10364645.32
#Sta/Elev= 30
  2978.7  329.49    3807  309.01  3821.1  308.76  4217.9  295.42  4441.2  265.59
  4824.4  263.03  4998.1   252.5  5048.3   266.7  6470.9  263.42  6661.4  264.76
  6871.8  265.84  7260.1  271.16  7608.2  293.06  7962.8  311.91  8344.6  312.08
    8555  317.27  8634.6  317.83  8657.7  317.84  8951.2  314.67  9261.3  290.28
  9430.9   309.9 11331.4  324.78 12042.4  325.66 12392.5  307.39 12516.2   313.3
 12548.4  309.59 12682.6  324.34 13165.4  326.09 13945.9  328.95 14307.9  331.11
#Mann= 20 ,-1 , 0
  2978.7     .05       0    3807     .16       0  3821.1     .05       0
  4217.9     .12       0  4824.4     .07       0  5048.3     .12       0
  6470.9     .07       0  6661.4     .12       0  6871.8     .05       0
  7608.2      .1       0  8344.6     .05       0    8555     .16       0
  8634.6     .05       0  8657.7     .16       0  9430.9     .05       0
 11331.4     .16       0 12516.2     .07       0 12548.4     .16       0
 13165.4     .05       0 13945.9     .16       0
Bank Sta=4824.4,5048.3
XS Rating Curve= 0 ,0
Exp/Cntr=0.3,0.1

Type RM Length L Ch R = 1 ,486651  ,3185,3185,3185
BEGIN DESCRIPTION:
NAVASOTA RIVER 186
END DESCRIPTION:
XS GIS Cut Line= 3
      3576645.53     10361325.01      3570894.68     10362952.61
      3566228.88      10362844.1
#Sta/Elev= 30
  2488.6  311.45  3097.5  312.15  3479.5  310.84  3746.9  279.78  3835.8  270.48
  3928.2  264.56  4716.8  265.51  4811.5  265.12  5017.4  251.75  5059.2   264.8
  6942.1  267.34  7115.5  268.46  7562.4  273.65  8043.3  318.74  8722.4  323.71
  8998.1   313.6  9068.1  298.53  9118.1  313.66  9252.2  316.15  9416.5  315.43
  9421.9  314.98  9707.8  322.12 10108.4  322.71 10173.8  313.89 10718.5  306.51
 10847.3  317.77 11457.3  328.87   11647  330.88 11838.3   331.3 13132.4  362.55
#Mann= 20 ,-1 , 0
  2488.6     .16       0  3097.5     .05       0  3746.9     .12       0
  3835.8     .16       0  3928.2     .05       0  4716.8     .12       0
  4811.5     .07       0  5059.2     .12       0  6942.1     .16       0
  7115.5     .05       0  7562.4     .16       0  9252.2     .05       0
  9416.5     .16       0  9421.9     .05       0  9707.8     .16       0
 10173.8     .05       0 10847.3     .16       0 11457.3     .05       0
   11647     .16       0 11838.3     .05       0
Bank Sta=4811.5,5059.2
XS Rating Curve= 0 ,0
Exp/Cntr=0.3,0.1

Type RM Length L Ch R = 1 ,483466  ,3621,3621,3621
BEGIN DESCRIPTION:
NAVASOTA RIVER 345
END DESCRIPTION:
XS GIS Cut Line= 4
      3580974.73     10361120.02      3573501.59       10359911.
      3570434.61     10359649.65      3566892.96     10361212.15
#Sta/Elev= 30
 -2570.3  348.52 -2324.2  329.64 -1980.1  308.03 -1814.2  310.35 -1327.9  284.79
  -936.7  269.93  -596.4  282.33  1416.9  285.92  2561.4  274.73  2881.5   274.7
  3372.8  275.65  3779.6  285.32  4028.8  290.03  4229.6  276.15  4550.3  280.28
  4938.7  262.03  5009.3  251.92  5039.6  262.01  6547.4  260.12  7057.8  308.71
    7419  309.07  7715.4  311.23    8444  311.53  9586.9  320.48  9720.3  318.07
  9756.9  306.78  9826.9  318.49 10315.7  323.58 11174.7  332.52 11949.1  342.02
#Mann= 20 ,-1 , 0
 -2570.3     .05       0 -2324.2     .16       0 -1814.2     .05       0
 -1327.9     .12       0  -596.4     .05       0  1416.9     .05       0
  2561.4     .05       0  2881.5     .16       0  3372.8     .05       0
  3779.6     .16       0  4550.3     .05       0  4938.7     .07       0
  5039.6     .12       0  6547.4     .16       0    7419     .05       0
  7715.4     .16       0    8444     .05       0  9586.9     .16       0
 10315.7     .05       0 11174.7     .05       0
#XS Ineff= 2 , 0
       0  1330.2  287.98  5291.2       0  263.76
Permanent Ineff=
       F       F
Bank Sta=4938.7,5039.6
XS Rating Curve= 0 ,0
Exp/Cntr=0.3,0.1

Type RM Length L Ch R = 1 ,479845  ,2985,2985,2985
BEGIN DESCRIPTION:
NAVASOTA RIVER 187
END DESCRIPTION:
XS GIS Cut Line= 3
      3577285.68      10359752.1      3573351.28     10356837.15
      3565956.31     10356108.07
#Sta/Elev= 30
    -478  283.22  -153.6   279.5   194.7  273.74   454.4  281.27  1020.4  276.22
  2633.3  279.48  3372.9  278.34  4100.2  281.04  4287.3  273.37  4779.5   273.3
  4940.3  261.53  5020.4  250.11  5060.8  264.78  5402.5  263.58  5553.2   255.4
  5633.6  265.54  5797.9  265.15  6332.5  263.73    6943  263.67  7285.7  264.16
  7699.9  266.21  8168.4  266.12  8473.1  265.55  9134.6  263.57  9426.3  264.27
 10906.6  264.92 11391.4  293.96   11723  334.12 11808.6  333.42 11849.4  334.76
#Mann= 20 ,-1 , 0
    -478     .16       0  -153.6     .05       0   194.7     .16       0
  1020.4     .05       0  2633.3     .05       0  3372.9     .16       0
  4287.3     .12       0  4940.3     .07       0  5060.8     .12       0
  5797.9     .12       0  6332.5     .12       0    6943     .07       0
  7285.7     .07       0  7699.9     .12       0  8168.4     .07       0
  8473.1     .05       0  9134.6     .12       0  9426.3     .12       0
 10906.6     .16       0 11808.6     .16       0
#XS Ineff= 2 , 0
       0                  9974.6       0  267.42
Permanent Ineff=
       F       F
Bank Sta=4940.3,5060.8
XS Rating Curve= 0 ,0
Exp/Cntr=0.3,0.1

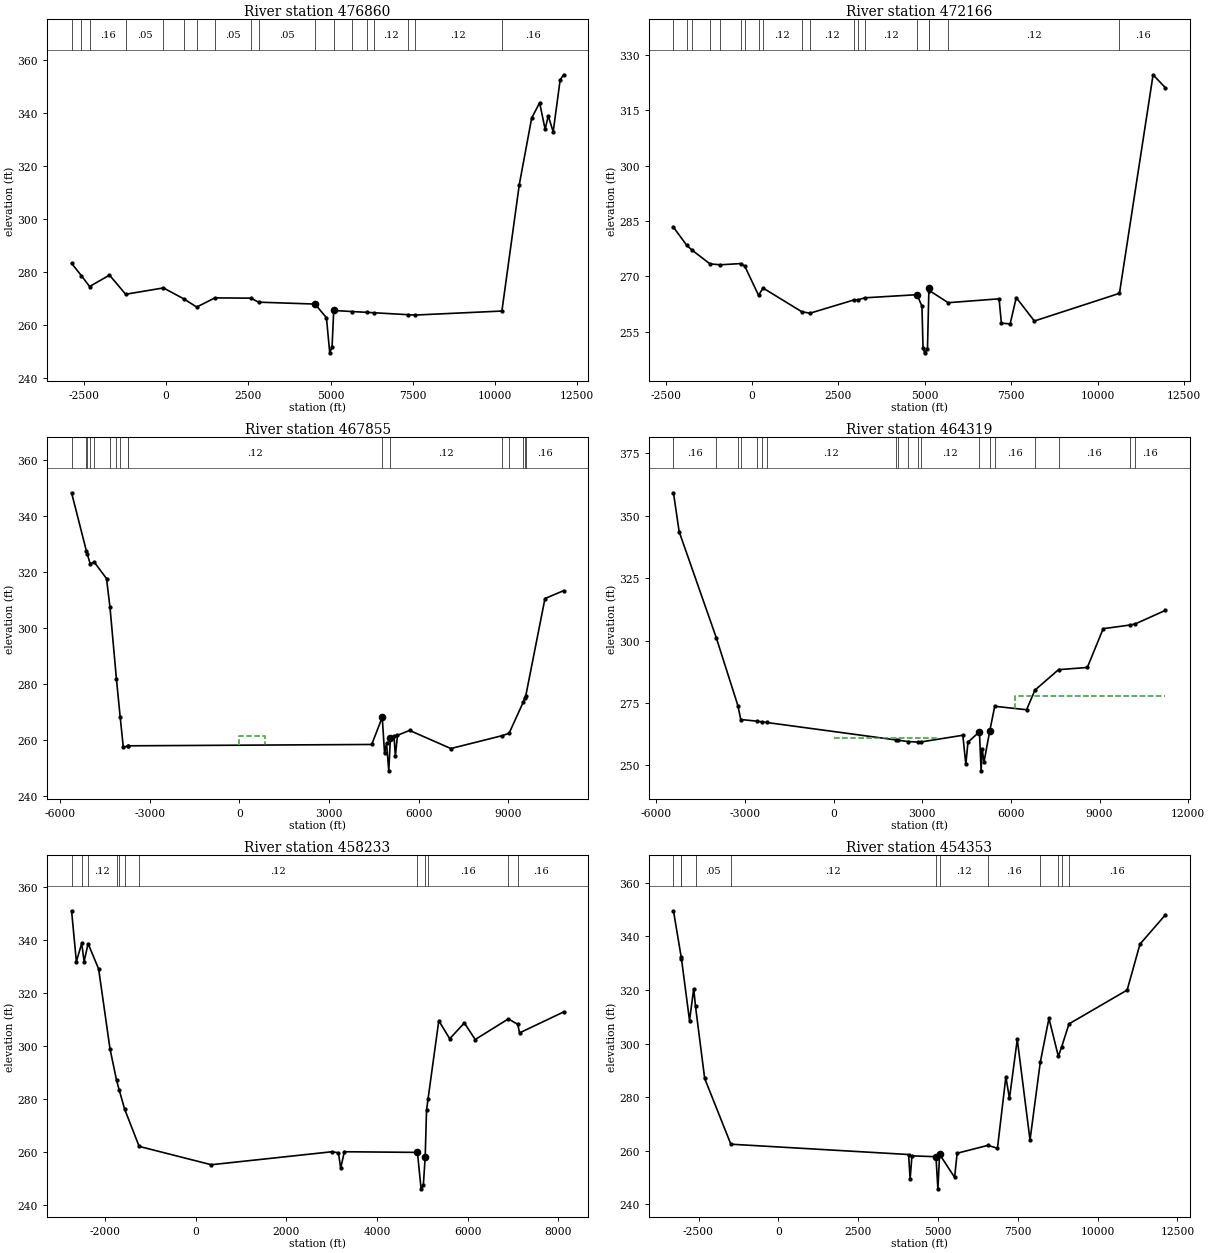
Type RM Length L Ch R = 1 ,476860  ,4694,4694,4694
BEGIN DESCRIPTION:
NAVASOTA RIVER 188
END DESCRIPTION:
XS GIS Cut Line= 3
      3577294.21     10359740.55      3573837.39     10354649.66
      3565087.35     10353642.71
#Sta/Elev= 30
 -2874.8  283.33 -2575.7  278.68 -2327.2  274.59 -1722.3   278.9 -1230.3  271.67
   -82.3  274.06   542.4   269.9   929.9  266.85  1483.5   270.3  2577.3  270.21
  2810.2  268.69  4528.5  267.97  4874.6  262.82    4975  249.57  5045.7  251.82
    5096  265.55  5646.5  265.16  6096.8  264.85  6325.9  264.69    7362  263.96
  7561.9  263.82 10210.2  265.34 10739.1  313.08 11115.5  338.16 11357.2  343.91
 11525.2  333.89 11619.3     339 11769.8  332.95 11981.1  352.57 12086.6  354.48
#Mann= 18 ,-1 , 0
 -2874.8     .16       0 -2575.7     .05       0 -2327.2     .16       0
 -1230.3     .05       0   -82.3     .05       0   542.4     .05       0
   929.9     .16       0  1483.5     .05       0  2577.3     .15       0
  2810.2     .05       0  4528.5    .033       0    5096     .12       0
  5646.5     .07       0  6096.8     .07       0  6325.9     .12       0
    7362     .07       0  7561.9     .12       0 10210.2     .16       0
#XS Ineff= 2 , 0
       0                    5096       0  265.55
Permanent Ineff=
       F       F
Bank Sta=4528.5,5096
XS Rating Curve= 0 ,0
Exp/Cntr=0.3,0.1

Type RM Length L Ch R = 1 ,472166  ,4311,4311,4311
BEGIN DESCRIPTION:
NAVASOTA RIVER 189
END DESCRIPTION:
XS GIS Cut Line= 3
      3577307.04     10359734.36      3574973.93     10352841.73
       3572274.9     10346420.51
#Sta/Elev= 30
 -2276.8   283.3 -1890.9  278.38 -1734.7  277.05 -1218.5  273.35  -916.9  273.11
  -315.1  273.45    -210  272.68   187.2  264.82   315.3  266.81  1433.6   260.4
  1672.3  259.97  2941.8  263.56  3075.4  263.63  3256.9  264.15  4772.4     265
  4915.6  261.88  4947.3  250.54  4992.2  249.23    5076   250.4  5117.4  266.79
  5131.4  266.11  5674.7  262.83  7147.9  263.88  7214.8  257.28  7468.6  257.08
  7645.7  264.22  8169.5  257.86 10632.7  265.37 11606.2  324.64 11965.4  321.09
#Mann= 19 ,-1 , 0
 -2276.8     .16       0 -1890.9     .05       0 -1734.7     .16       0
 -1218.5     .12       0  -916.9     .05       0  -315.1      .1       0
    -210     .05       0   187.2     .07       0   315.3     .12       0
  1433.6     .05       0  1672.3     .12       0  2941.8     .16       0
  3075.4     .05       0  3256.9     .12       0  4772.4    .033       0
  5117.4     .07       0  5131.4     .12       0  5674.7     .12       0
 10632.7     .16       0
Bank Sta=4772.4,5117.4
XS Rating Curve= 0 ,0
Exp/Cntr=0.3,0.1

Type RM Length L Ch R = 1 ,467855  ,3536,3536,3536
BEGIN DESCRIPTION:
NAVASOTA RIVER 191
END DESCRIPTION:
XS GIS Cut Line= 4
      3582214.64     10359284.28      3581817.52     10357726.16
      3576682.11     10350321.64      3573485.69     10345424.98
#Sta/Elev= 30
   -5619  348.31 -5126.2  327.65 -5094.6  326.49 -4996.4  322.96 -4857.2  323.51
 -4449.9  317.71 -4333.3  307.41 -4117.1  281.71 -3993.2  268.41 -3888.7  257.54
 -3717.6  258.01 -3715.3  258.02  4425.8   258.5  4777.8  268.21  4855.5  255.36
    4921  258.89  4996.7  249.09  5049.7  260.73  5173.5  261.54  5215.7  254.21
  5288.1  261.77  5692.6  263.51  7074.2  257.05  8789.7  261.64  9021.6  262.48
  9494.3  273.54  9549.3  275.21  9580.4  275.82 10223.8  310.58 10847.6  313.38
#Mann= 17 ,-1 , 0
   -5619     .16       0 -5126.2      .1       0 -5094.6     .05       0
 -4996.4     .16       0 -4857.2     .05       0 -4333.3     .16       0
 -4117.1     .05       0 -3993.2     .12       0 -3717.6     .07       0
 -3715.3     .12       0  4777.8     .07       0  5049.7     .12       0
  8789.7     .05       0  9021.6     .12       0  9494.3     .16       0
  9549.3     .12       0  9580.4     .16       0
#XS Ineff= 2 , 0
       0   847.1  261.44               0
Permanent Ineff=
       F       F
Bank Sta=4777.8,5049.7
XS Rating Curve= 0 ,0
Exp/Cntr=0.3,0.1

Type RM Length L Ch R = 1 ,464319  ,6086,6086,6086
BEGIN DESCRIPTION:
NAVASOTA RIVER 190
END DESCRIPTION:
XS GIS Cut Line= 5
      3588733.21     10352913.54       3580573.5     10351976.04
      3578417.73     10348750.87      3578058.61     10346332.27
      3576280.81     10345200.32
#Sta/Elev= 30
 -5416.3  359.14 -5223.9  343.58 -3970.7  301.22 -3234.6  273.89 -3140.1   268.4
 -2598.5  267.75 -2428.1  267.48 -2261.5  267.21  2098.7  260.25  2186.1  260.11
    2515  259.59  2863.4  259.36  2948.1   259.4  4373.1   262.1  4474.3   250.4
  4546.5  259.35  4934.7  263.47  4991.5  247.86  5027.8  256.72  5087.8  251.29
  5280.2  263.62  5452.3   273.7  6529.3  272.31  6812.9  280.16  7610.1  288.36
  8584.2  289.22  9121.5  304.75 10017.5   306.2 10202.6  306.64 11229.1   312.1
#Mann= 19 ,-1 , 0
 -5416.3     .16       0 -3970.7     .05       0 -3234.6     .16       0
 -3140.1     .05       0 -2598.5     .12       0 -2428.1     .07       0
 -2261.5     .12       0  2098.7     .05       0  2186.1     .12       0
    2515     .07       0  2863.4     .05       0  2948.1     .12       0
  4934.7     .07       0  5280.2     .12       0  5452.3     .16       0
  6812.9     .05       0  7610.1     .16       0 10017.5     .12       0
 10202.6     .16       0
#XS Ineff= 2 , 0
       0  3457.2  261.08    6154       0  277.83
Permanent Ineff=
       F       F
Bank Sta=4934.7,5280.2
XS Rating Curve= 0 ,0
Exp/Cntr=0.3,0.1

Type RM Length L Ch R = 1 ,458233  ,3880,3880,3880
BEGIN DESCRIPTION:
NAVASOTA RIVER 075
END DESCRIPTION:
XS GIS Cut Line= 3
      3586797.48     10346856.25      3578203.71     10346335.42
      3576315.47     10345123.21
#Sta/Elev= 30
 -2736.6  350.86   -2631  331.71 -2512.9  338.58 -2460.7  331.71 -2372.3  338.48
 -2140.1  328.93 -1889.7  298.86 -1743.5  286.88 -1683.7  283.14 -1565.2  276.02
 -1246.1  262.02   344.4  255.11  3009.3  260.01  3149.6   259.6  3199.6   253.8
  3279.8  260.01  4892.7  259.76  4972.6  246.02  5022.1  247.32  5063.1  257.91
  5093.1   275.6  5124.8  279.71  5363.6  309.43  5604.1   302.6  5927.3  308.58
  6166.4  302.32  6897.5  310.09  7105.3  308.05  7144.2  304.82  8116.8  312.71
#Mann= 12 ,-1 , 0
 -2736.6     .12       0 -2512.9     .16       0 -2372.3     .12       0
 -1743.5     .07       0 -1683.7     .12       0 -1565.2     .16       0
 -1246.1     .12       0  4892.7     .07       0  5063.1     .12       0
  5124.8     .16       0  6897.5     .12       0  7105.3     .16       0
Bank Sta=4892.7,5063.1
XS Rating Curve= 0 ,0
Exp/Cntr=0.3,0.1

Type RM Length L Ch R = 1 ,454353  ,1656,1656,1656
BEGIN DESCRIPTION:
NAVASOTA RIVER 344
END DESCRIPTION:
XS GIS Cut Line= 3
      3586700.86     10346563.66      3578781.57     10344130.67
      3571810.61     10342658.59
#Sta/Elev= 30
 -3284.6  349.57   -3044  332.41   -3034  331.67 -2781.3  308.61 -2650.4  320.47
 -2593.9  313.86 -2307.5  287.01 -1487.4  262.45  4078.9   258.6  4127.2  249.39
  4183.5  258.11  4936.7  257.77  4996.9  245.79  5050.6  258.65  5520.7  250.08
  5598.8  259.08  6565.6  262.02  6861.7  260.92  7125.3  287.58  7237.8  279.54
  7482.9  301.57  7881.6     264  8202.4  292.97  8474.4  309.41  8768.5  295.27
  8868.7  298.61  9101.9  307.35 10923.2  319.97   11326  337.14 12124.7  348.09
#Mann= 12 ,-1 , 0
 -3284.6     .16       0   -3044     .12       0   -3034     .16       0
 -2593.9     .05       0 -1487.4     .12       0  4936.7     .07       0
  5050.6     .12       0  6565.6     .16       0  8202.4      .1       0
  8768.5     .16       0  8868.7     .05       0  9101.9     .16       0
#XS Ineff= 2 , 0
       0                  7482.9       0  301.57
Permanent Ineff=
       F       F
Bank Sta=4936.7,5050.6
XS Rating Curve= 0 ,0
Exp/Cntr=0.3,0.1