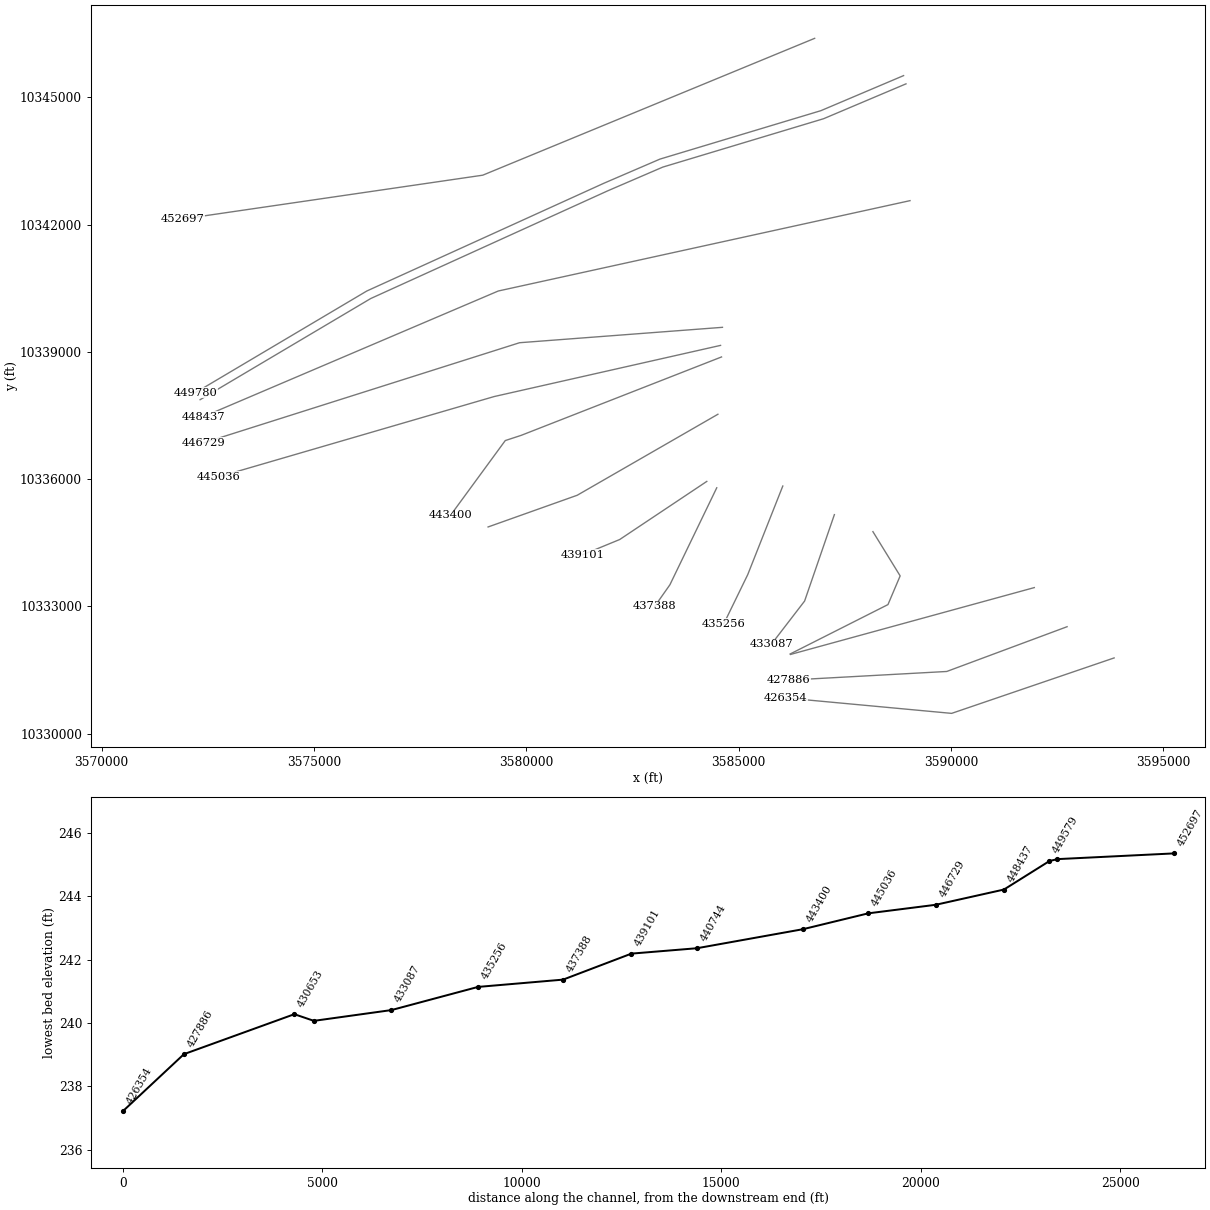
HEC-RAS study NAVASOTA RIVER.prj: NAVASOTA RIVER Base Level Engineering

--- NAVASOTA RIVER.g01 (geometry) --- (continued)

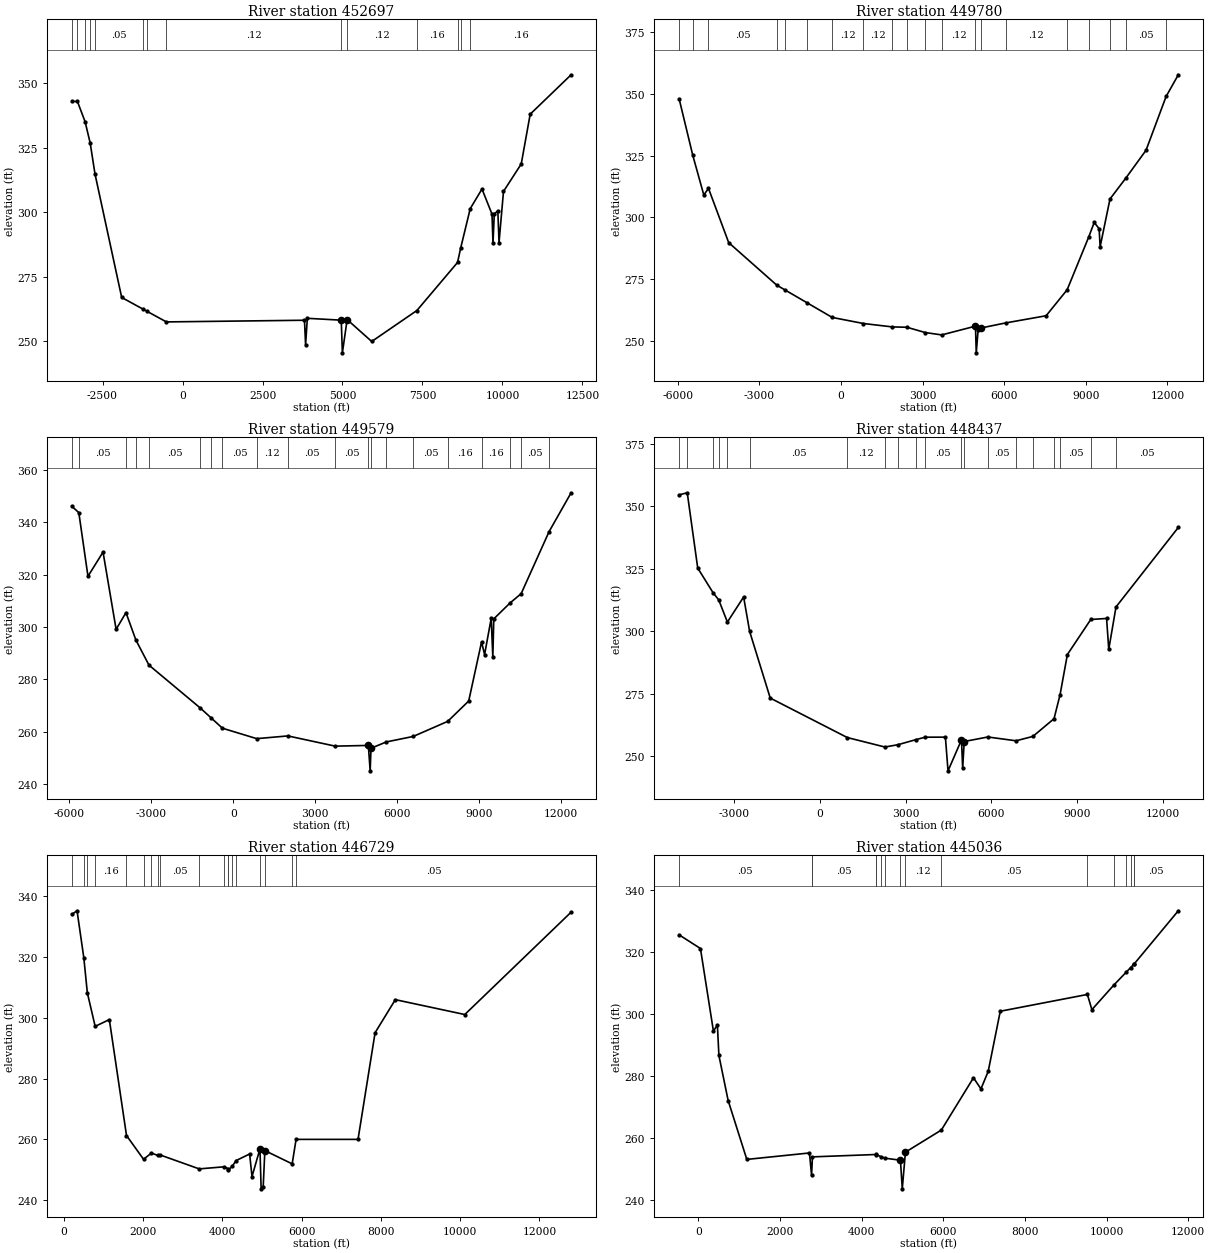
Type RM Length L Ch R = 1 ,452697  ,2917,2917,2917
BEGIN DESCRIPTION:
NAVASOTA RIVER 343
END DESCRIPTION:
XS GIS Cut Line= 3
      3586792.18     10346390.65      3578975.98     10343164.56
      3571906.14     10342130.94
#Sta/Elev= 30
 -3455.8  342.99 -3284.9  343.01 -3043.3  335.07 -2884.8   326.8 -2735.8  314.86
 -1901.1  266.86 -1222.8  262.25 -1109.6  261.48  -503.4  257.36  3811.9  258.01
  3846.7  248.48  3900.7  258.76  4960.9  258.04  4996.4  245.35  5145.4  258.27
  5913.5  249.76  7324.8  261.79  8595.2  280.45  8694.5   286.1  8992.3  301.36
  9359.7  308.98    9673  299.21  9703.4  287.83  9743.8  299.34  9854.9  300.49
  9891.9   288.2 10031.8  308.05 10586.2   318.7   10866  338.04   12145  353.35
#Mann= 14 ,-1 , 0
 -3455.8     .05       0 -3284.9     .16       0 -3043.3     .12       0
 -2884.8     .16       0 -2735.8     .05       0 -1222.8     .12       0
 -1109.6     .05       0  -503.4     .12       0  4960.9     .07       0
  5145.4     .12       0  7324.8     .16       0  8595.2     .05       0
  8694.5      .1       0  8992.3     .16       0
#XS Ineff= 2 , 0
       0                  9359.7       0  308.98
Permanent Ineff=
       F       F
Bank Sta=4960.9,5145.4
XS Rating Curve= 0 ,0
Exp/Cntr=0.3,0.1

Type RM Length L Ch R = 1 ,449780  ,201,201,201
BEGIN DESCRIPTION:
NAVASOTA RIVER 332
END DESCRIPTION:
XS GIS Cut Line= 6
      3588886.35     10345511.85      3586940.14      10344685.8
      3583149.73     10343543.98       3581832.1     10342976.08
      3576244.24     10340433.56      3572207.47      10338037.5
#Sta/Elev= 30
 -5946.3  347.95 -5444.3  325.07 -5039.6  309.04 -4867.4  311.71 -4124.3  289.76
 -2357.2  272.55 -2037.4   270.5 -1236.3  265.37  -319.2  259.49   826.5  257.04
  1890.4  255.66    2424  255.52  3099.1  253.38  3701.8  252.42  4944.5  255.97
  4972.8  245.17  5042.2  254.48  5162.9  255.26  6047.9  257.26    7541  260.18
  8312.9  270.68  9100.5  291.88  9307.8  297.91  9488.8   295.4  9525.8  288.12
  9888.1  307.43   10471  315.89 11212.6  327.14   11950   348.9 12398.3  357.68
#Mann= 20 ,-1 , 0
 -5946.3     .05       0 -5444.3     .05       0 -4867.4     .05       0
 -2357.2     .16       0 -2037.4     .05       0 -1236.3     .12       0
  -319.2     .12       0   826.5     .12       0  1890.4     .12       0
    2424     .12       0  3099.1     .12       0  3701.8     .12       0
  4944.5     .07       0  5162.9     .12       0  6047.9     .12       0
  8312.9     .16       0  9100.5     .16       0  9888.1     .16       0
   10471     .05       0   11950     .05       0
Bank Sta=4944.5,5162.9
XS Rating Curve= 0 ,0
Exp/Cntr=0.3,0.1

Type RM Length L Ch R = 1 ,449579  ,1142,1142,1142
BEGIN DESCRIPTION:
NAVASOTA RIVER 333
END DESCRIPTION:
XS GIS Cut Line= 6
      3588943.19     10345317.61      3587003.41     10344495.99
      3583216.23     10343355.32      3581914.35     10342793.77
      3576337.37     10340256.54      3572319.41     10337871.76
#Sta/Elev= 30
 -5906.8  346.05   -5655   343.7 -5319.7  319.38 -4767.6  328.62   -4289  299.14
 -3927.1   305.5 -3565.3  295.06 -3085.8  285.47 -1198.7  269.03  -803.4  265.27
  -394.3  261.38   860.3   257.4    2002  258.44  3735.5  254.54    4949  254.81
  5016.3  245.11  5046.7  253.72  5601.9  256.13  6592.5  258.24  7855.5  263.99
  8624.9  271.76  9095.3   294.3    9207  289.52  9449.9  303.36  9508.4  288.54
  9543.8  303.12 10146.8  309.27 10545.4  312.73 11568.9  336.43 12375.8  351.26
#Mann= 20 ,-1 , 0
 -5906.8     .08       0   -5655     .05       0 -3927.1     .05       0
 -3565.3     .05       0 -3085.8     .05       0 -1198.7     .05       0
  -803.4     .05       0  -394.3     .05       0   860.3     .12       0
    2002     .05       0  3735.5     .05       0    4949     .07       0
  5046.7     .08       0  5601.9     .12       0  6592.5     .05       0
  7855.5     .16       0  9095.3     .16       0 10146.8     .16       0
 10545.4     .05       0 11568.9     .05       0
Bank Sta=4949,5046.7
XS Rating Curve= 0 ,0
Exp/Cntr=0.3,0.1

Type RM Length L Ch R = 1 ,448437  ,1708,1708,1708
BEGIN DESCRIPTION:
NAVASOTA RIVER 346
END DESCRIPTION:
XS GIS Cut Line= 3
      3589037.95     10342564.11      3579340.95     10340434.01
      3572396.94     10337471.37
#Sta/Elev= 30
 -4928.2  354.62 -4643.8  355.45 -4277.2  325.34 -3741.4  315.49 -3540.8  312.58
 -3238.4  303.72 -2669.8  313.77 -2459.9     300 -1738.1  273.32   959.7  257.53
  2275.1  253.74  2729.9  254.65  3364.9   256.7  3686.3  257.67  4394.7  257.69
  4486.6  244.21  4957.9   256.6    5000  245.17  5053.1  255.94  5880.5  257.75
  6869.6  256.23  7457.9  257.98  8198.7  265.07  8410.5  274.71  8665.4  290.73
  9484.7  304.76 10038.4  305.17 10114.7  292.83 10368.4  309.78 12549.6  341.57
#Mann= 20 ,-1 , 0
 -4928.2     .05       0 -4643.8     .16       0 -3741.4     .05       0
 -3540.8     .12       0 -3238.4     .16       0 -2459.9     .05       0
   959.7     .12       0  2275.1     .05       0  2729.9     .05       0
  3364.9     .07       0  3686.3     .05       0  4957.9     .07       0
  5053.1     .12       0  5880.5     .05       0  6869.6     .07       0
  7457.9     .05       0  8198.7     .16       0  8410.5     .05       0
  9484.7     .16       0 10368.4     .05       0
Bank Sta=4957.9,5053.1
XS Rating Curve= 0 ,0
Exp/Cntr=0.3,0.1

Type RM Length L Ch R = 1 ,446729  ,1693,1693,1693
BEGIN DESCRIPTION:
NAVASOTA RIVER 347
END DESCRIPTION:
XS GIS Cut Line= 3
      3584620.81      10339577.9      3579842.69     10339214.82
       3572409.1      10336856.2
#Sta/Elev= 30
   208.1  333.99   337.2  335.15   507.5  319.72   596.5  308.19   794.1  297.14
  1151.6  299.38  1584.3  261.26  2014.6  253.44  2212.8  255.49  2374.5   254.7
    2424  254.91  3417.6  250.29  4053.6  250.98  4143.2   250.4  4152.4  249.94
  4251.1  251.15  4349.9  253.03  4689.7  255.18  4749.9  247.78  4950.4  256.85
  4980.5  243.73  5032.2  244.33    5074  256.31  5762.8  251.94  5861.7  259.99
  7424.1  259.99  7854.2  295.05  8364.8  305.93 10117.1  301.04 12798.8  334.69
#Mann= 19 ,-1 , 0
   208.1     .05       0   507.5     .16       0   596.5     .12       0
   794.1     .16       0  1584.3     .05       0  2014.6     .16       0
  2212.8     .12       0  2374.5     .07       0    2424     .05       0
  3417.6     .07       0  4053.6     .05       0  4143.2     .07       0
  4152.4     .12       0  4251.1     .07       0  4349.9     .12       0
  4950.4     .07       0    5074     .12       0  5762.8     .07       0
  5861.7     .05       0
Bank Sta=4950.4,5074
XS Rating Curve= 0 ,0
Exp/Cntr=0.3,0.1

Type RM Length L Ch R = 1 ,445036  ,1636,1636,1636
BEGIN DESCRIPTION:
NAVASOTA RIVER 348
END DESCRIPTION:
XS GIS Cut Line= 3
      3584575.79     10339151.95      3579243.73     10337945.72
      3572756.45     10336053.87
#Sta/Elev= 30
  -466.8  325.45    55.3  321.04   372.8   294.4     470  296.33   507.4  286.51
   733.5  271.97  1190.8  252.96  2725.1  255.04  2776.4  247.84  2798.1  253.78
  4347.2  254.54  4348.6  254.59    4483   253.8  4583.4  253.34    4953   252.7
    4998  243.46  5074.6  255.29  5954.8  262.44  6741.3  279.31  6924.5  275.72
  7102.4  281.39  7397.5  300.79  9531.1  306.21  9641.2   301.3 10172.9  309.16
 10478.1  313.35 10590.4  314.89 10674.9  316.05 10681.6  316.14 11757.5  333.22
#Mann= 16 ,-1 , 0
  -466.8     .05       0  2776.4     .07       0  2798.1     .05       0
  4347.2     .07       0  4348.6     .05       0    4483     .07       0
  4583.4     .12       0    4953     .07       0  5074.6     .12       0
  5954.8     .05       0  9531.1     .16       0 10172.9     .05       0
 10478.1      .1       0 10590.4     .05       0 10674.9      .1       0
 10681.6     .05       0
Bank Sta=4953,5074.6
XS Rating Curve= 0 ,0
Exp/Cntr=0.3,0.1

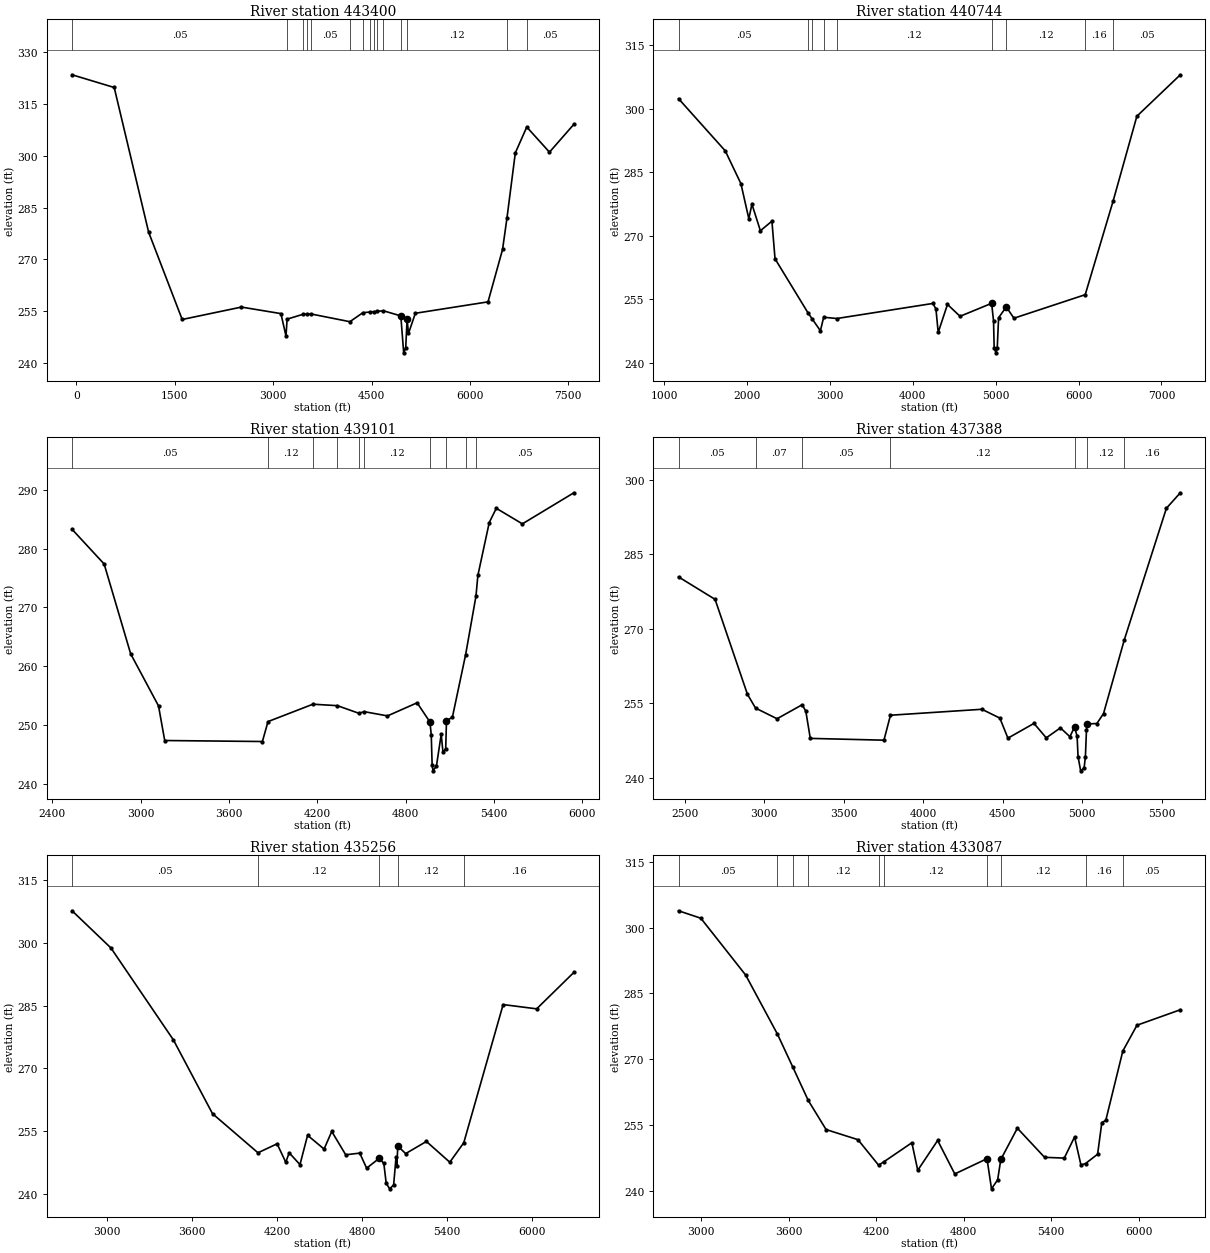
Type RM Length L Ch R = 1 ,443400  ,2656,2656,2656
BEGIN DESCRIPTION:
NAVASOTA RIVER 349
END DESCRIPTION:
XS GIS Cut Line= 4
      3584599.15     10338879.51      3579882.18     10337031.66
      3579505.79     10336908.34      3578213.54      10335141.7
#Sta/Elev= 30
     -66  323.41   576.5  319.73  1101.5  277.86  1612.9  252.61  2516.4   256.2
  3118.6  254.31  3195.8  247.81  3212.5  252.71  3452.1  254.09  3515.9  254.16
  3573.3  254.22  4169.7  251.97  4367.7  254.57  4472.2  254.76  4530.9  254.86
  4576.7  254.94  4681.2  255.13  4946.4  253.64  4990.3  242.96  5021.3  244.42
  5042.2  252.68  5063.2  248.57  5168.4  254.41  6276.2  257.71  6497.8  272.88
  6564.5   281.9  6692.4  300.82  6866.8  308.29  7213.3  301.02  7584.9  309.08
#Mann= 15 ,-1 , 0
     -66     .05       0  3212.5      .1       0  3452.1     .05       0
  3515.9      .1       0  3573.3     .05       0  4169.7     .12       0
  4367.7     .07       0  4472.2     .12       0  4530.9     .07       0
  4576.7     .05       0  4681.2     .12       0  4946.4     .07       0
  5042.2     .12       0  6564.5     .16       0  6866.8     .05       0
Bank Sta=4946.4,5042.2
XS Rating Curve= 0 ,0
Exp/Cntr=0.3,0.1

Type RM Length L Ch R = 1 ,440744  ,1643,1643,1643
BEGIN DESCRIPTION:
NAVASOTA RIVER 350
END DESCRIPTION:
XS GIS Cut Line= 3
      3584513.97     10337528.69      3581200.32      10335618.9
      3579101.49     10334871.61
#Sta/Elev= 30
  1175.4  302.41  1738.8  290.09  1927.8  282.34  2023.2  274.06  2060.6  277.49
  2162.6  271.21  2301.9  273.47  2339.3  264.58  2740.1  251.71  2787.7  250.37
  2886.6  247.57  2926.1  250.77  3084.8  250.47  4242.7  254.03  4280.1  252.74
  4307.4  247.18  4419.4   253.8  4570.9  250.99  4951.8  254.06  4974.9  249.91
  4982.6  243.42  5004.8  242.36  5019.3  243.41  5035.9  250.65  5128.4  253.21
    5221  250.54  6080.7   256.1  6417.4  278.23  6703.9  298.27  7227.9  308.06
#Mann= 9 ,-1 , 0
  1175.4     .05       0  2740.1     .07       0  2787.7     .12       0
  2926.1     .05       0  3084.8     .12       0  4951.8     .07       0
  5128.4     .12       0  6080.7     .16       0  6417.4     .05       0
Bank Sta=4951.8,5128.4
XS Rating Curve= 0 ,0
Exp/Cntr=0.3,0.1

Type RM Length L Ch R = 1 ,439101  ,1713,1713,1713
BEGIN DESCRIPTION:
NAVASOTA RIVER 351
END DESCRIPTION:
XS GIS Cut Line= 3
      3584251.84     10335945.42      3582200.76      10334575.5
      3581328.68     10334216.44
#Sta/Elev= 30
  2533.5  283.29  2751.5  277.39  2931.7   262.1  3120.9  253.24    3163  247.35
  3826.8  247.18  3864.8  250.57  4170.2  253.53  4336.4  253.28  4484.2  251.97
  4516.3  252.27  4676.8  251.54  4878.1  253.77  4965.1   250.5  4974.1  248.34
  4980.1  243.18  4986.1  242.19  5009.4  243.02  5041.8   248.4  5053.8  245.33
  5072.3  245.97  5077.7  250.75  5117.5  251.28  5207.6  261.95    5278  271.93
  5290.9  275.45  5368.2  284.45  5416.1  286.87  5593.3  284.22  5943.1  289.51
#Mann= 10 ,-1 , 0
  2533.5     .05       0  3864.8     .12       0  4170.2     .07       0
  4336.4     .12       0  4484.2     .07       0  4516.3     .12       0
  4965.1     .07       0  5077.7     .12       0  5207.6     .16       0
    5278     .05       0
Bank Sta=4965.1,5077.7
XS Rating Curve= 0 ,0
Exp/Cntr=0.3,0.1

Type RM Length L Ch R = 1 ,437388  ,2132,2132,2132
BEGIN DESCRIPTION:
NAVASOTA RIVER 352
END DESCRIPTION:
XS GIS Cut Line= 3
      3584486.28      10335794.9      3583383.05     10333508.22
      3583027.97     10333003.27
#Sta/Elev= 30
  2461.1  280.46  2690.8  275.94  2894.3  256.82  2945.4  254.02  3080.8  251.87
  3238.5  254.69  3261.6  253.41  3289.8  247.91  3753.1  247.55  3794.1  252.58
  4369.1  253.78  4482.1     252  4532.9  247.96  4696.7  250.93  4774.1  248.02
    4863  250.03  4922.8  248.25  4951.8   250.2    4968  248.35    4974  244.23
  4990.4  241.37  5012.2  241.96  5020.3  244.24  5027.1  249.69  5033.2  250.82
  5092.4  250.91  5134.2  252.91  5265.4  267.83  5529.7   294.3  5617.3  297.42
#Mann= 7 ,-1 , 0
  2461.1     .05       0  2945.4     .07       0  3238.5     .05       0
  3794.1     .12       0  4951.8     .07       0  5033.2     .12       0
  5265.4     .16       0
Bank Sta=4951.8,5033.2
XS Rating Curve= 0 ,0
Exp/Cntr=0.3,0.1

Type RM Length L Ch R = 1 ,435256  ,2169,2169,2169
BEGIN DESCRIPTION:
NAVASOTA RIVER 353
END DESCRIPTION:
XS GIS Cut Line= 3
      3586041.84     10335836.55      3585215.95     10333747.37
      3584650.34     10332584.87
#Sta/Elev= 30
  2753.5  307.69  3027.6  298.79  3468.3  276.78  3744.1  259.13  4064.8  249.77
  4199.7  251.92  4260.6  247.51    4285  249.76    4361  246.94  4414.7  253.95
    4531  250.66  4585.1  254.87  4683.6  249.29  4782.5  249.69  4831.2  246.08
  4920.4  248.46  4952.4  247.21  4969.1  242.52  4993.2  241.14  5021.6  242.06
  5038.6  248.73  5044.2   246.5  5050.9  251.39  5106.3  249.57  5252.7  252.48
  5417.8  247.51  5516.3  252.17  5793.9  285.24  6030.5  284.22  6292.8  292.94
#Mann= 5 ,-1 , 0
  2753.5     .05       0  4064.8     .12       0  4920.4     .07       0
  5050.9     .12       0  5516.3     .16       0
Bank Sta=4920.4,5050.9
XS Rating Curve= 0 ,0
Exp/Cntr=0.3,0.1

Type RM Length L Ch R = 1 ,433087  ,1944,1944,1944
BEGIN DESCRIPTION:
NAVASOTA RIVER 354
END DESCRIPTION:
XS GIS Cut Line= 3
      3587256.63     10335162.04      3586555.23     10333124.69
       3585772.4     10332105.92
#Sta/Elev= 30
  2845.3  303.87  2998.2  302.17  3305.2  289.21  3523.4  275.71  3628.7  268.19
    3734  260.61  3856.7  253.94  4075.2  251.63  4216.7  245.81  4254.5  246.62
  4444.6  250.93    4485  244.64  4621.4  251.45  4738.8  243.81  4959.6  247.29
  4990.5  240.41  5032.6  242.46  5054.3  247.11  5167.8  254.25  5354.3   247.6
  5489.3  247.43    5560  252.26  5603.5  245.85  5635.2  246.19  5717.7  248.31
  5746.7  255.52  5773.9  256.04  5890.6  271.86  5987.7  277.75  6284.8  281.28
#Mann= 10 ,-1 , 0
  2845.3     .05       0  3523.4     .12       0  3628.7     .16       0
    3734     .12       0  4216.7     .07       0  4254.5     .12       0
  4959.6     .07       0  5054.3     .12       0  5635.2     .16       0
  5890.6     .05       0
Bank Sta=4959.6,5054.3
XS Rating Curve= 0 ,0
Exp/Cntr=0.3,0.1

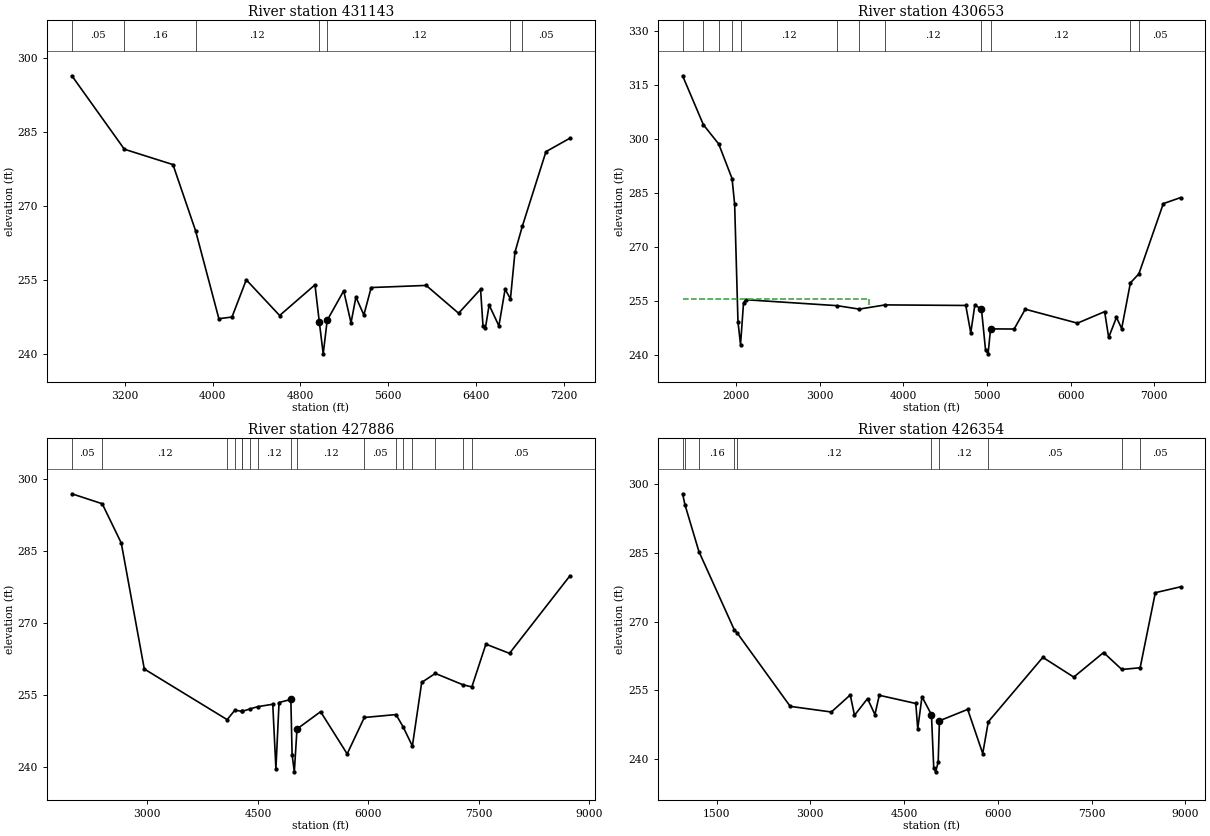
Type RM Length L Ch R = 1 ,431143  ,490,490,490
BEGIN DESCRIPTION:
NAVASOTA RIVER 356
END DESCRIPTION:
XS GIS Cut Line= 4
      3588164.04     10334761.32      3588805.55     10333717.81
      3588518.39     10333041.34      3586215.86     10331877.23
#Sta/Elev= 30
  2715.8  296.36  3194.4  281.49  3637.5  278.38  3843.6  264.99  4056.1  247.18
  4175.6  247.52  4305.9  255.05  4610.1  247.83  4932.3  254.04  4971.3  246.61
  5007.4  240.07  5043.7  246.85  5194.2  252.82    5261  246.35  5305.6  251.55
  5378.1  247.95  5444.9  253.49  5946.3  253.92  6241.7  248.29  6442.2  253.15
  6464.5  245.63  6486.8  245.34  6520.2  249.96  6609.3  245.73    6666  253.16
  6714.6  251.19  6755.7  260.63  6823.1  265.91  7038.4     281  7255.7  283.71
#Mann= 7 ,-1 , 0
  2715.8     .05       0  3194.4     .16       0  3843.6     .12       0
  4971.3     .07       0  5043.7     .12       0  6714.6     .16       0
  6823.1     .05       0
Bank Sta=4971.3,5043.7
XS Rating Curve= 0 ,0
Exp/Cntr=0.3,0.1

Type RM Length L Ch R = 1 ,430653  ,2767,2767,2767
BEGIN DESCRIPTION:
NAVASOTA RIVER 355
END DESCRIPTION:
XS GIS Cut Line= 2
      3591964.87     10333442.08      3586223.52     10331866.17
#Sta/Elev= 30
  1359.5   317.6  1608.1  303.98  1791.3  298.64    1951  289.01  1981.9  281.81
  2021.6  249.19  2052.3  242.87  2088.3  254.53  2119.4  255.32  3205.1  253.68
  3471.1  252.72  3782.8  253.89  4745.3  253.73  4805.2  246.12  4853.8  253.84
    4933  252.73  4981.4  241.45  5012.3  240.28  5041.6  247.22  5323.7  247.18
  5456.7  252.69  6080.7  248.81    6406  252.01    6454  244.83  6547.3  250.41
  6609.5   247.3    6714  260.02  6815.3  262.52  7107.3  282.05  7313.2  283.72
#Mann= 12 ,-1 , 0
  1359.5     .12       0  1608.1     .16       0  1791.3     .05       0
    1951     .16       0  2052.3     .12       0  3205.1     .05       0
  3471.1      .1       0  3782.8     .12       0    4933     .07       0
  5041.6     .12       0    6714     .16       0  6815.3     .05       0
#XS Ineff= 2 , 0
       0  3591.9  255.46               0
Permanent Ineff=
       F       F
Bank Sta=4933,5041.6
XS Rating Curve= 0 ,0
Exp/Cntr=0.3,0.1

Type RM Length L Ch R = 1 ,427886  ,1532,1532,1532
BEGIN DESCRIPTION:
NAVASOTA RIVER 357
END DESCRIPTION:
XS GIS Cut Line= 3
      3592737.08     10332519.95      3589902.86     10331464.68
      3586175.29     10331259.85
#Sta/Elev= 30
  1975.7  296.99  2387.6  294.91  2646.1  286.72  2958.5  260.46  4083.2   249.9
  4187.1  251.87  4286.1  251.64    4291  251.65  4394.9  252.14  4498.8  252.61
    4702  253.11  4744.7  239.66  4787.4  253.47  4947.5  254.12  4964.6  242.57
  4994.7  239.02  5030.8  247.95  5351.3  251.56  5711.8  242.76  5944.6  250.35
  6374.6  250.96  6471.2   248.4  6596.7   244.4  6723.4  257.66    6908  259.54
  7278.4   257.2  7403.8  256.72  7594.7  265.64  7915.1  263.72  8733.2  279.85
#Mann= 17 ,-1 , 0
  1975.7     .05       0  2387.6     .12       0  4083.2     .07       0
  4187.1     .05       0  4286.1     .12       0    4291     .07       0
  4394.9     .05       0  4498.8     .12       0  4947.5     .07       0
  5030.8     .12       0  5944.6     .05       0  6374.6     .12       0
  6471.2     .07       0  6596.7     .05       0    6908     .16       0
  7278.4     .12       0  7403.8     .05       0
#XS Ineff= 2 , 0
       0  4947.5  254.12               0
Permanent Ineff=
       F       F
Bank Sta=4947.5,5030.8
XS Rating Curve= 0 ,0
Exp/Cntr=0.3,0.1

Type RM Length L Ch R = 1 ,426354  ,1107,1107,1107
BEGIN DESCRIPTION:
NAVASOTA RIVER 358
END DESCRIPTION:
XS GIS Cut Line= 3
      3593844.98     10331784.08      3590017.57     10330476.83
      3586110.58     10330840.77
#Sta/Elev= 30
   955.5  297.91   992.7  295.55  1216.6   285.3  1781.7  268.25  1829.5  267.52
  2677.9  251.51  3336.2  250.28  3638.3     254  3706.2  249.56  3914.9   253.2
  4033.6  249.72  4102.8  253.93  4687.3  252.14  4718.6  246.62  4786.6  253.62
  4937.9  249.69  4974.5  238.13  5005.2  237.22  5045.7  239.35  5065.7  248.36
  5517.7  250.85  5758.7  241.22  5847.7  248.15  6720.5  262.21    7215   257.9
  7692.7  263.26  7984.7  259.56  8277.7  259.94  8520.6  276.32  8923.9   277.6
#Mann= 10 ,-1 , 0
   955.5     .16       0   992.7     .05       0  1216.6     .16       0
  1781.7     .05       0  1829.5     .12       0  4937.9     .07       0
  5065.7     .12       0  5847.7     .05       0  7984.7      .1       0
  8277.7     .05       0
Bank Sta=4937.9,5065.7
XS Rating Curve= 0 ,0
Exp/Cntr=0.3,0.1