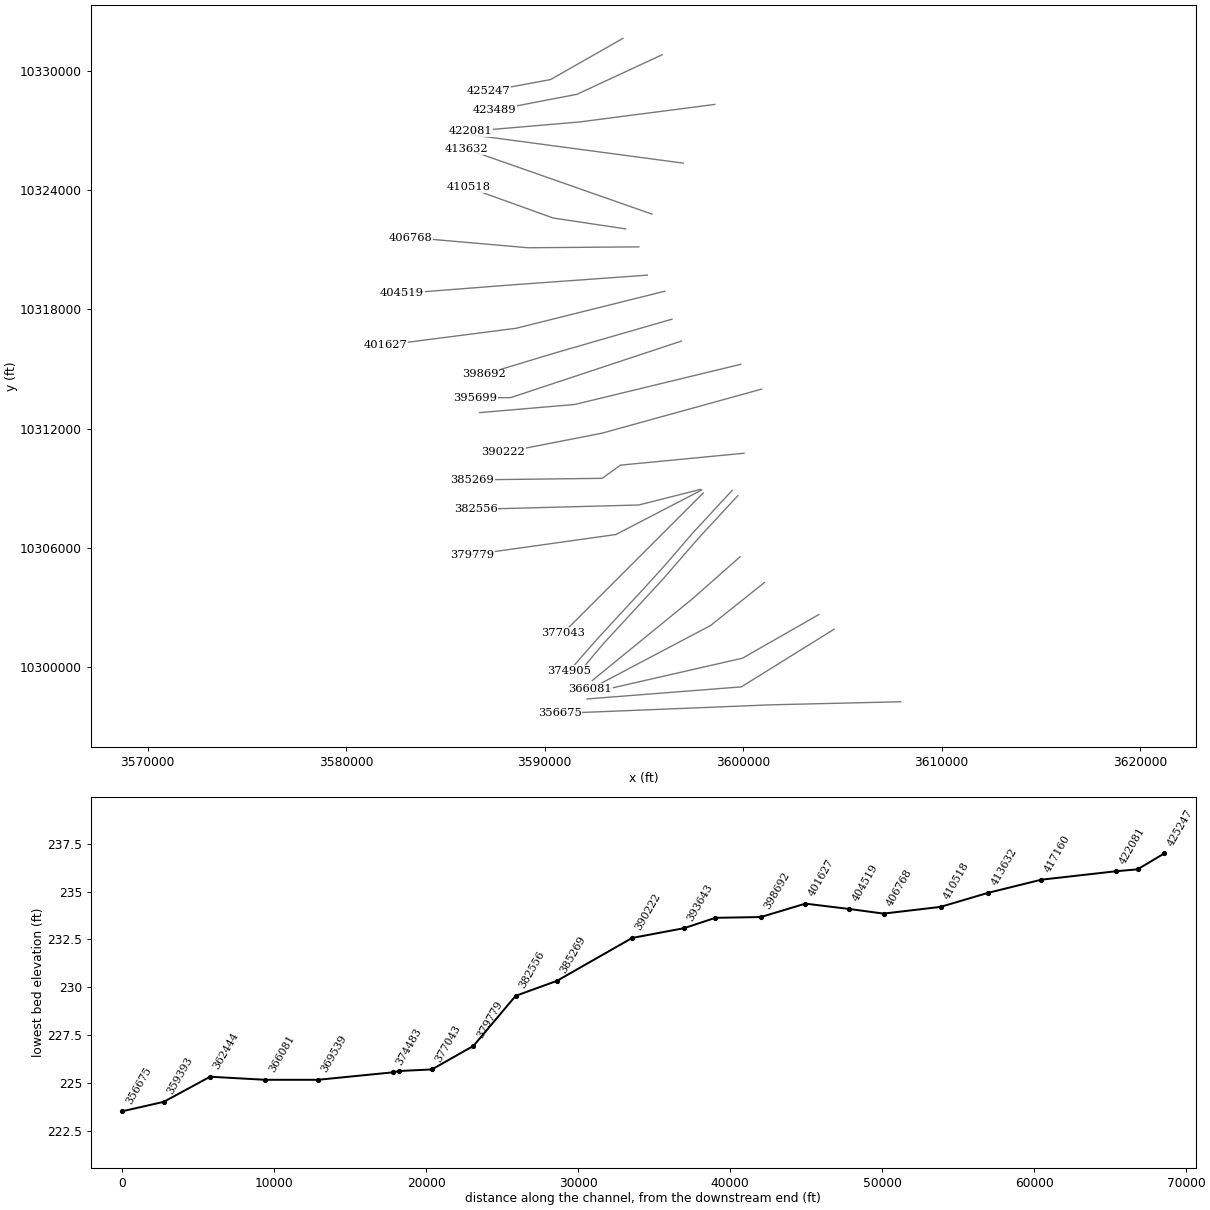
HEC-RAS study NAVASOTA RIVER.prj: NAVASOTA RIVER Base Level Engineering

--- NAVASOTA RIVER.g01 (geometry) --- (continued)

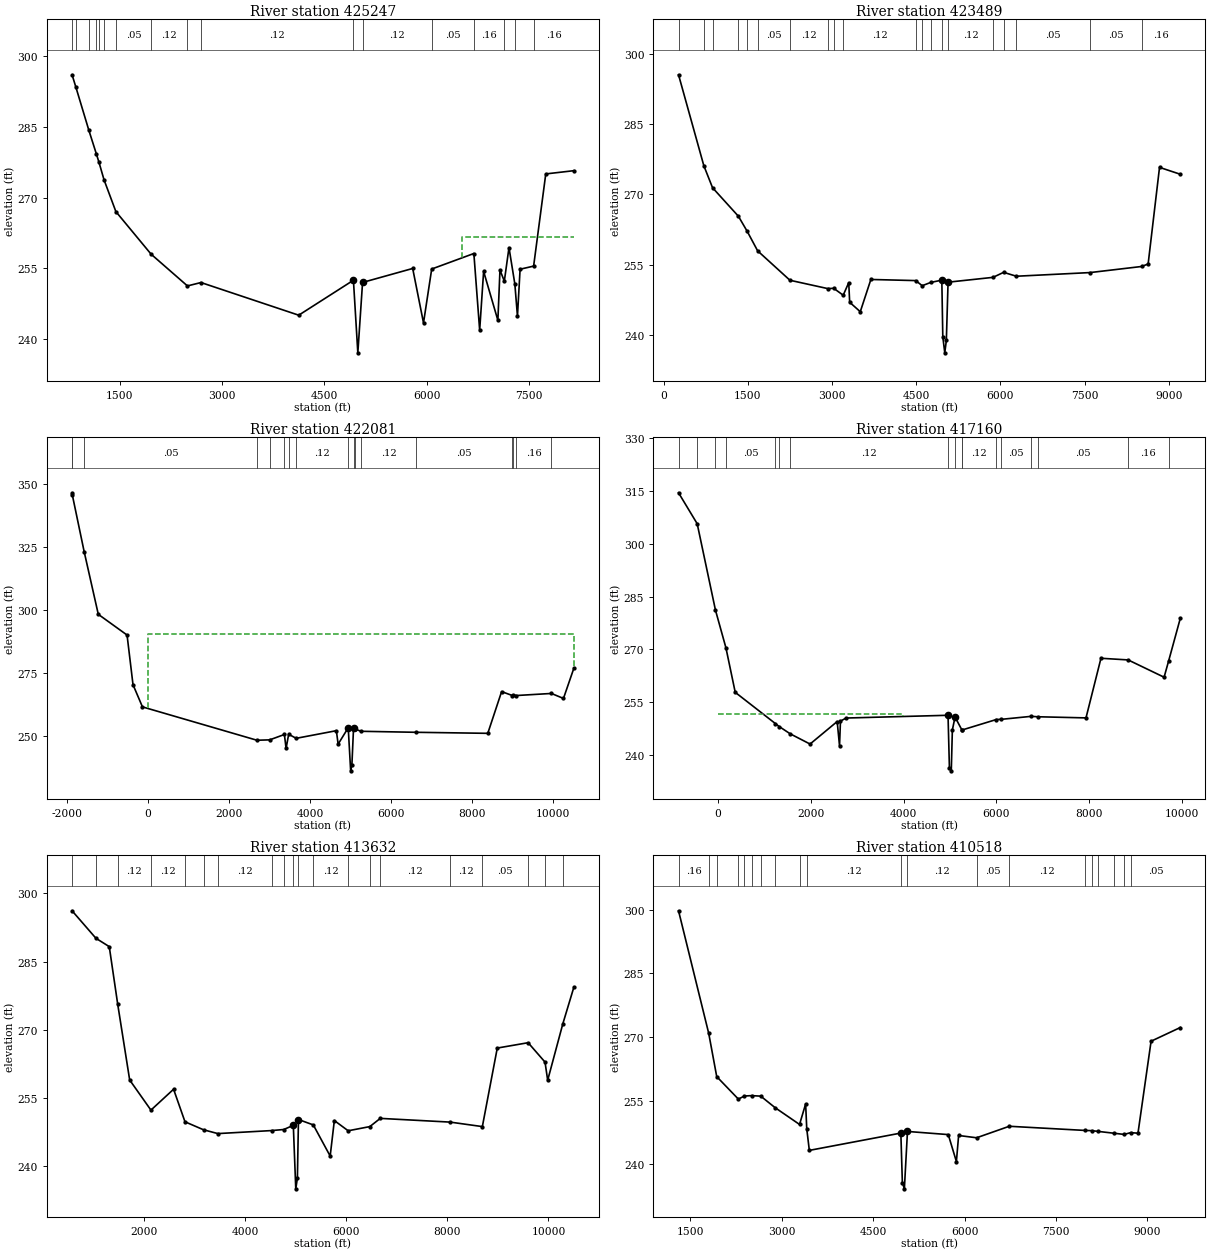
Type RM Length L Ch R = 1 ,425247  ,1758,1758,1758
BEGIN DESCRIPTION:
NAVASOTA RIVER 359
END DESCRIPTION:
XS GIS Cut Line= 3
      3593949.96     10331635.47      3590300.98      10329561.1
      3587197.34      10328985.3
#Sta/Elev= 30
   802.6  296.08   859.3  293.41  1048.7  284.28  1159.8  279.21  1197.8  277.44
    1271  273.76  1444.8     267  1961.2  257.95  2493.5  251.21  2691.9  251.93
  4124.5  244.99    4926  252.42  4990.6  236.99  5059.9  251.95  5794.6  254.92
  5953.1  243.35  6073.2   254.8  6691.1   258.1  6776.2  241.79  6834.1   254.3
  7043.1   243.9  7073.7  254.59  7137.6  252.22  7205.9  259.36  7291.8  251.61
    7330  244.77  7368.6  254.76  7566.9  255.42  7744.9  275.01  8156.6   275.7
#Mann= 17 ,-1 , 0
   802.6     .16       0   859.3     .05       0  1048.7     .16       0
  1159.8     .12       0  1197.8     .16       0    1271     .12       0
  1444.8     .05       0  1961.2     .12       0  2493.5     .05       0
  2691.9     .12       0    4926     .07       0  5059.9     .12       0
  6073.2     .05       0  6691.1     .16       0  7137.6     .05       0
  7291.8     .12       0  7566.9     .16       0
#XS Ineff= 2 , 0
       0                  6514.3       0  261.68
Permanent Ineff=
       F       F
Bank Sta=4926,5059.9
XS Rating Curve= 0 ,0
Exp/Cntr=0.3,0.1

Type RM Length L Ch R = 1 ,423489  ,1408,1408,1408
BEGIN DESCRIPTION:
NAVASOTA RIVER 360
END DESCRIPTION:
XS GIS Cut Line= 3
      3595922.23     10330809.11      3591629.14     10328818.12
      3587498.97     10328027.83
#Sta/Elev= 30
   267.7  295.47   718.2  276.08   873.3  271.38  1333.7   265.3    1491  262.07
  1676.9  257.91  2251.9  251.64  2923.1  249.87  3032.2  249.92  3200.5  248.45
  3299.2  251.13  3315.8  246.95  3504.6  244.93  3693.4  251.81  4492.6  251.57
  4607.5  250.48    4758  251.17  4957.1  251.67  4974.5   239.6  5009.8  236.16
  5037.7  238.81  5068.3  251.23  5868.6  252.26  6057.9  253.33  6284.7   252.5
  7597.4  253.28  8516.1  254.58  8631.8  255.12  8834.6  275.72  9205.1  274.25
#Mann= 20 ,-1 , 0
   267.7     .16       0   718.2     .05       0   873.3     .16       0
  1333.7     .12       0    1491     .16       0  1676.9     .05       0
  2251.9     .12       0  2923.1     .05       0  3032.2     .07       0
  3200.5     .12       0  4492.6     .07       0  4607.5     .12       0
    4758     .12       0  4957.1     .07       0  5068.3     .12       0
  5868.6     .12       0  6057.9     .05       0  6284.7     .05       0
  7597.4     .05       0  8516.1     .16       0
Bank Sta=4957.1,5068.3
XS Rating Curve= 0 ,0
Exp/Cntr=0.3,0.1

Type RM Length L Ch R = 1 ,422081  ,4921,4921,4921
BEGIN DESCRIPTION:
NAVASOTA RIVER 361
END DESCRIPTION:
XS GIS Cut Line= 3
      3598577.35     10328309.96      3591762.06     10327426.62
      3586276.67     10326958.87
#Sta/Elev= 30
 -1872.3  346.37 -1864.5   345.4 -1574.6  323.05 -1225.4  298.15  -515.8  289.93
    -369  270.23  -136.3  261.43  2687.1   248.2  3002.2  248.35  3365.2  250.48
  3406.7  244.95  3470.4  250.57  3656.4  248.96    4647  251.99  4690.5  246.65
  4939.5  253.15  4999.7  236.06  5030.1  238.38  5070.2  252.86  5098.7  252.74
  5253.1  251.75    6615  251.35  8382.2  250.94  8723.4   267.5  8990.8  265.92
  9000.6   266.2  9089.6  265.94  9951.7  266.76 10248.9  264.78 10505.3  276.77
#Mann= 17 ,-1 , 0
 -1872.3     .05       0 -1864.5     .16       0 -1574.6     .05       0
  2687.1     .12       0  3002.2     .05       0  3365.2     .12       0
  3470.4     .05       0  3656.4     .12       0  4939.5     .07       0
  5070.2     .12       0  5098.7     .16       0  5253.1     .12       0
    6615     .05       0  8990.8      .1       0  9000.6     .05       0
  9089.6     .16       0  9951.7     .05       0
#XS Ineff= 2 , 0
       0  -527.4  290.31               0
Permanent Ineff=
       F       F
Bank Sta=4939.5,5070.2
XS Rating Curve= 0 ,0
Exp/Cntr=0.3,0.1

Type RM Length L Ch R = 1 ,417160  ,3528,3528,3528
BEGIN DESCRIPTION:
NAVASOTA RIVER 362
END DESCRIPTION:
XS GIS Cut Line= 2
      3596984.48     10325355.53      3586255.12     10326787.56
#Sta/Elev= 30
  -853.5  314.39    -451  305.62   -56.6  281.13   168.5  270.49   369.6  257.86
  1237.7  248.99  1316.8  248.18  1556.4   246.1  1983.8  243.21    2569  249.59
  2619.4  242.69  2639.6   249.7  2760.6  250.58    4960  251.36  4990.2  236.29
  5030.3  235.62  5053.3  247.19  5111.3  250.86  5255.2   247.3  5257.8  247.17
  6002.4  250.16  6102.6   250.2  6755.7  251.06  6890.8  250.94  7936.1  250.62
    8259  267.51  8845.3  267.04  9620.9  262.14  9720.2  266.82    9971  278.85
#Mann= 17 ,-1 , 0
  -853.5     .05       0    -451     .16       0   -56.6     .12       0
   168.5     .05       0  1237.7      .1       0  1316.8     .05       0
  1556.4     .12       0    4960     .07       0  5111.3     .12       0
  5255.2     .16       0  5257.8     .12       0  6002.4     .07       0
  6102.6     .05       0  6755.7     .12       0  6890.8     .05       0
  8845.3     .16       0  9720.2     .05       0
#XS Ineff= 2 , 0
       0  3994.5  251.66               0
Permanent Ineff=
       F       F
Bank Sta=4960,5111.3
XS Rating Curve= 0 ,0
Exp/Cntr=0.3,0.1

Type RM Length L Ch R = 1 ,413632  ,3114,3114,3114
BEGIN DESCRIPTION:
NAVASOTA RIVER 363
END DESCRIPTION:
XS GIS Cut Line= 2
      3595407.03     10322792.26      3586042.93     10326069.15
#Sta/Elev= 30
   581.6  296.18  1053.6  290.12    1317  288.28  1483.2  275.65  1720.4  258.91
  2140.9  252.27  2588.5  256.87  2814.1   249.7  3180.4  247.94  3463.9   247.1
  4533.2  247.77  4767.4     248  4955.8  248.92  5004.5  234.93  5036.6   237.3
  5057.7   250.2  5351.1  249.01  5684.6  242.15  5767.1  249.97  6040.7  247.72
  6468.5  248.64  6675.1  250.45  8056.8  249.63  8693.4  248.64  8988.3  265.94
  9598.4  267.12  9932.4  262.85  9984.9  258.85 10285.1  271.31 10502.5  279.34
#Mann= 20 ,-1 , 0
   581.6     .05       0  1053.6      .1       0  1483.2     .12       0
  2140.9     .12       0  2814.1     .07       0  3180.4     .12       0
  3463.9     .12       0  4533.2     .05       0  4767.4     .12       0
  4955.8     .07       0  5057.7     .12       0  5351.1     .12       0
  6040.7     .12       0  6468.5     .07       0  6675.1     .12       0
  8056.8     .12       0  8693.4     .05       0  9598.4     .16       0
  9932.4     .05       0 10285.1     .16       0
Bank Sta=4955.8,5057.7
XS Rating Curve= 0 ,0
Exp/Cntr=0.3,0.1

Type RM Length L Ch R = 1 ,410518  ,3750,3750,3750
BEGIN DESCRIPTION:
NAVASOTA RIVER 391
END DESCRIPTION:
XS GIS Cut Line= 3
      3594085.16     10322046.58      3590432.23     10322593.21
      3586157.98      10324129.9
#Sta/Elev= 30
  1306.4  299.71    1802  270.82  1933.2  260.64  2287.9  255.35  2388.3  256.07
  2507.6  256.16  2655.6  256.04  2890.7  253.33  3292.5  249.37  3392.4  254.21
  3410.8  248.34  3453.1  243.26  4955.1  247.34  4979.9  235.69  5012.9   234.2
  5063.9  247.72  5733.4  246.98  5866.8  240.63  5903.4  246.77  6198.3  246.23
  6734.8  248.94  7978.7  247.96  8088.1  247.91  8194.6  247.73  8459.5  247.29
  8620.5  247.02  8726.9  247.44    8847  247.31  9062.2  268.98  9542.1  272.21
#Mann= 20 ,-1 , 0
  1306.4     .16       0    1802     .05       0  1933.2     .16       0
  2287.9     .07       0  2388.3     .12       0  2507.6     .16       0
  2655.6     .12       0  2890.7     .05       0  3292.5     .07       0
  3410.8     .12       0  4955.1     .07       0  5063.9     .12       0
  6198.3     .05       0  6734.8     .12       0  7978.7     .16       0
  8088.1     .12       0  8194.6     .07       0  8459.5     .12       0
  8620.5     .07       0  8726.9     .05       0
Bank Sta=4955.1,5063.9
XS Rating Curve= 0 ,0
Exp/Cntr=0.3,0.1

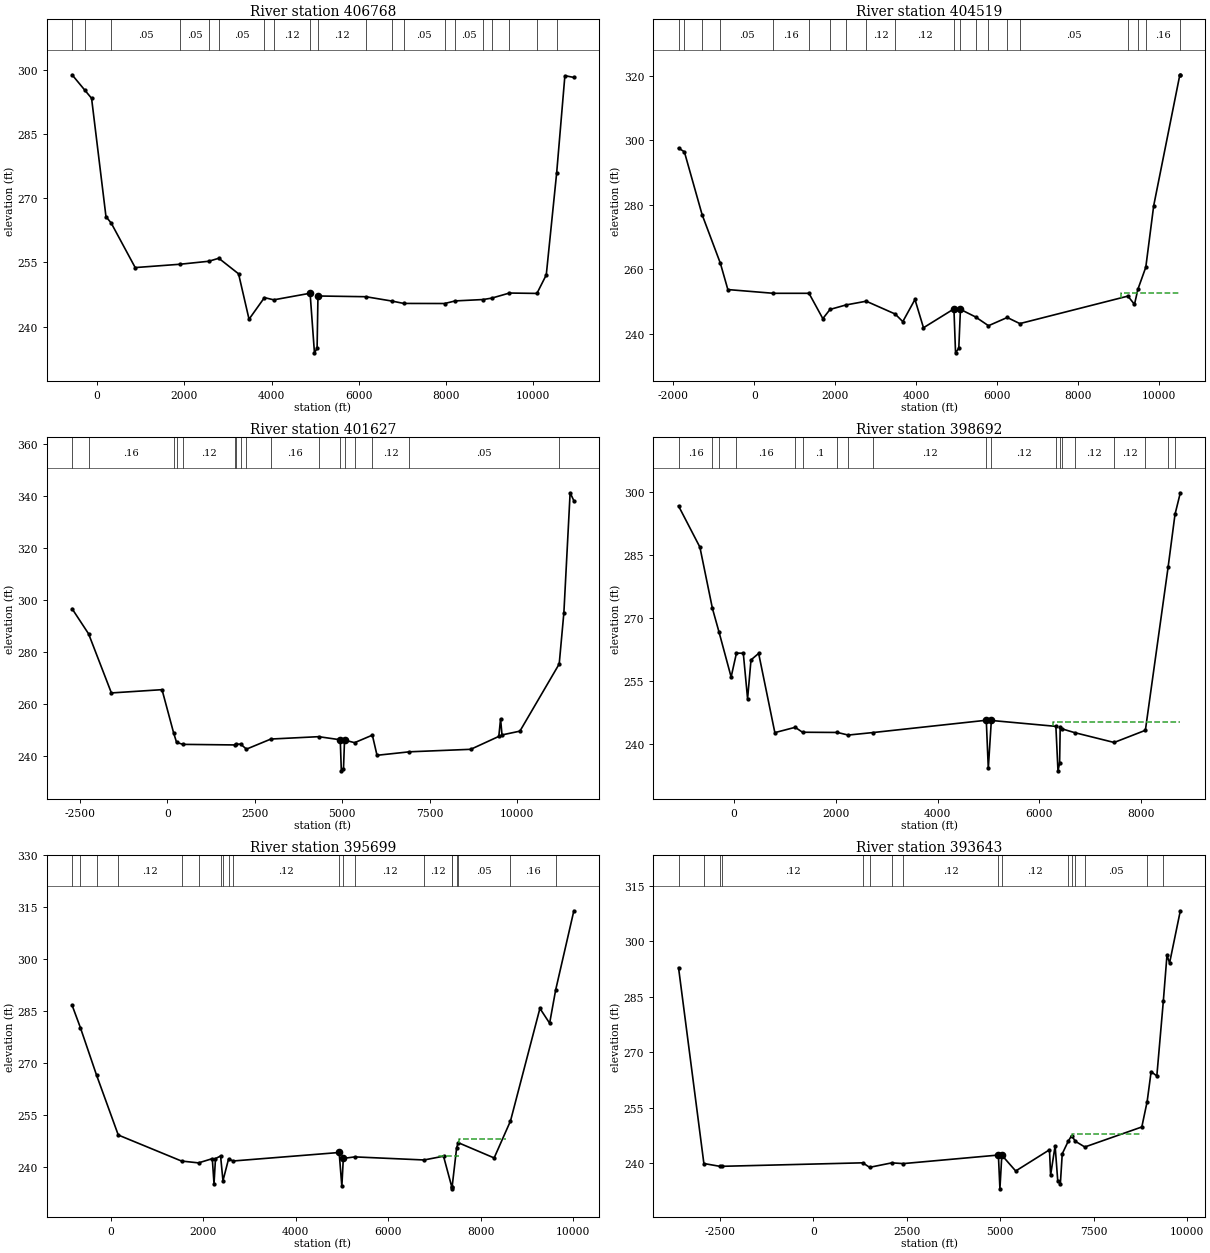
Type RM Length L Ch R = 1 ,406768  ,2249,2249,2249
BEGIN DESCRIPTION:
NAVASOTA RIVER 392
END DESCRIPTION:
XS GIS Cut Line= 3
      3594749.43     10321142.35      3589175.72     10321095.82
       3583267.3     10321611.68
#Sta/Elev= 30
  -573.9  298.85  -287.8  295.33  -126.6  293.35   203.4  265.69   322.7   264.2
   873.5  253.78  1901.3  254.56    2562  255.26  2790.1  255.96  3243.6  252.32
  3483.6  241.71  3836.4  246.76  4050.6  246.24  4883.6  247.78  4983.4  233.85
  5043.8   234.9  5063.9  247.14  6161.7  246.97  6755.7  245.96  7029.9   245.4
  7967.1  245.38  8212.9  245.99  8849.1  246.31  9048.1  246.64  9453.8  247.83
 10084.2  247.74 10298.4  252.07 10537.4  275.99 10725.3  298.64 10930.9  298.23
#Mann= 20 ,-1 , 0
  -573.9     .05       0  -287.8     .16       0   322.7     .05       0
  1901.3     .05       0    2562     .12       0  2790.1     .05       0
  3836.4     .12       0  4050.6     .12       0  4883.6     .07       0
  5063.9     .12       0  6161.7     .05       0  6755.7     .12       0
  7029.9     .05       0  7967.1     .12       0  8212.9     .05       0
  8849.1     .12       0  9048.1     .05       0  9453.8     .05       0
 10084.2     .16       0 10537.4     .05       0
Bank Sta=4883.6,5063.9
XS Rating Curve= 0 ,0
Exp/Cntr=0.3,0.1

Type RM Length L Ch R = 1 ,404519  ,2892,2892,2892
BEGIN DESCRIPTION:
NAVASOTA RIVER 393
END DESCRIPTION:
XS GIS Cut Line= 3
      3595177.03     10319719.32      3588324.94     10319226.32
      3582816.57     10318799.23
#Sta/Elev= 30
 -1869.8  297.58 -1725.5  296.42 -1287.4  276.93  -835.8  261.84  -651.7  253.71
     475  252.55  1352.7  252.55  1694.3   244.7  1872.6  247.55  2266.5  248.94
  2766.2   250.1  3480.9  246.13  3669.4  243.77  3970.2  250.63  4180.7  241.87
  4932.7  247.72  4972.5  234.09    5053  235.53  5093.1  247.57  5465.5  245.23
  5786.2   242.5  6249.2  245.05  6560.8  243.16  9230.6  251.68  9392.5  249.11
  9477.3  253.82  9671.9  260.64  9867.4  279.73 10511.4   320.2 10524.9  320.31
#Mann= 20 ,-1 , 0
 -1869.8     .16       0 -1725.5     .05       0 -1287.4     .16       0
  -835.8     .05       0     475     .16       0  1352.7     .12       0
  1872.6     .12       0  2266.5     .12       0  2766.2     .12       0
  3480.9     .12       0  4932.7     .07       0  5093.1     .12       0
  5465.5     .05       0  5786.2     .12       0  6249.2     .05       0
  6560.8     .05       0  9230.6     .16       0  9477.3     .05       0
  9671.9     .16       0 10511.4     .16       0
#XS Ineff= 2 , 0
       0                    9065       0   252.6
Permanent Ineff=
       F       F
Bank Sta=4932.7,5093.1
XS Rating Curve= 0 ,0
Exp/Cntr=0.3,0.1

Type RM Length L Ch R = 1 ,401627  ,2935,2935,2935
BEGIN DESCRIPTION:
NAVASOTA RIVER 394
END DESCRIPTION:
XS GIS Cut Line= 3
      3596055.18     10318908.21      3588566.61     10317045.76
      3582006.41     10316199.97
#Sta/Elev= 30
 -2716.7  296.73 -2244.8  287.06 -1593.5  264.33  -147.7  265.59   184.5  248.93
   268.7  245.29   452.2  244.55  1926.5  244.33  1963.4  244.56  2095.3  244.67
  2263.9  242.72  2962.6   246.6  4325.5  247.51  4942.8  246.32  4973.5  234.37
  5034.8  234.98    5065  246.21  5352.3   245.2  5859.6   248.1  5992.7  240.35
  6918.8  241.69  8669.2  242.65  9471.2  247.61  9521.6  254.37    9562  248.18
 10073.8  249.64 11196.1  275.48 11329.6  295.22 11507.9  341.31 11614.5  338.26
#Mann= 17 ,-1 , 0
 -2716.7     .05       0 -2244.8     .16       0   184.5     .12       0
   268.7     .16       0   452.2     .12       0  1926.5     .16       0
  1963.4     .12       0  2095.3     .16       0  2263.9     .12       0
  2962.6     .16       0  4325.5     .12       0  4942.8     .07       0
    5065     .12       0  5352.3     .05       0  5859.6     .12       0
  6918.8     .05       0 11196.1     .16       0
#XS Ineff= 2 , 0
       0                  9521.6       0  254.37
Permanent Ineff=
       F       F
Bank Sta=4942.8,5065
XS Rating Curve= 0 ,0
Exp/Cntr=0.3,0.1

Type RM Length L Ch R = 1 ,398692  ,2993,2993,2993
BEGIN DESCRIPTION:
NAVASOTA RIVER 395
END DESCRIPTION:
XS GIS Cut Line= 3
       3596415.6     10317501.61      3590561.12     10315813.14
       3586949.8     10314723.22
#Sta/Elev= 30
 -1093.1  296.61  -673.1  286.82  -426.8  272.26  -298.3   266.7   -59.1  255.97
    45.5  261.64   180.3  261.61   264.4  250.81   331.7  260.03   482.1  261.57
   800.4  242.75  1199.6  244.01  1344.3  242.84    2030  242.79  2242.6  242.17
  2724.3  242.76  4957.3  245.69  4996.9  234.23  5056.8  245.64  6325.5  244.24
  6366.9  233.67  6398.7  235.45  6410.6  244.15  6444.7  243.65  6693.7  242.75
  7470.7  240.41  8085.1   243.3  8533.2  282.18  8667.6  294.61  8772.2  299.74
#Mann= 19 ,-1 , 0
 -1093.1     .16       0  -426.8     .05       0  -298.3      .1       0
    45.5     .16       0  1199.6     .12       0  1344.3      .1       0
    2030      .1       0  2242.6     .05       0  2724.3     .12       0
  4957.3     .07       0  5056.8     .12       0  6325.5     .07       0
  6410.6     .12       0  6444.7     .05       0  6693.7     .12       0
  7470.7     .12       0  8085.1     .05       0  8533.2     .16       0
  8667.6     .05       0
#XS Ineff= 2 , 0
       0                  6273.5       0  245.16
Permanent Ineff=
       F       F
Bank Sta=4957.3,5056.8
XS Rating Curve= 0 ,0
Exp/Cntr=0.3,0.1

Type RM Length L Ch R = 1 ,395699  ,2056,2056,2056
BEGIN DESCRIPTION:
NAVASOTA RIVER 192
END DESCRIPTION:
XS GIS Cut Line= 3
      3596892.95     10316400.52       3588299.2     10313557.64
        3586498.     10313535.94
#Sta/Elev= 30
  -836.1   286.7    -656   280.2  -305.9  266.46   163.2  249.18  1531.1  241.66
  1899.1  241.13    2197  242.35    2234  235.07  2265.7  242.37  2376.2  243.12
  2427.6  235.97  2548.3  242.24  2650.7  241.68  4940.7  244.13  4998.9  234.32
  5030.6  242.43  5280.9  242.86    6776  241.97  7198.1  243.06  7377.5  234.13
  7380.3  233.63  7383.5  234.13  7481.5  245.48  7515.8  246.97  8292.8  242.56
  8646.5  253.25  9282.8  285.77  9492.9  281.48  9623.7  291.11   10017  313.97
#Mann= 20 ,-1 , 0
  -836.1     .16       0    -656     .12       0  -305.9     .16       0
   163.2     .12       0  1531.1     .05       0  1899.1     .12       0
  2376.2     .07       0  2427.6     .12       0  2548.3     .07       0
  2650.7     .12       0  4940.7     .07       0  5030.6     .12       0
  5280.9     .12       0    6776     .12       0  7377.5     .07       0
  7383.5     .12       0  7481.5     .07       0  7515.8     .05       0
  8646.5     .16       0  9623.7     .05       0
#XS Ineff= 2 ,-1
  7102.9  7538.5  243.26  7538.5  8552.8  247.95
Permanent Ineff=
       F       F
Bank Sta=4940.7,5030.6
XS Rating Curve= 0 ,0
Exp/Cntr=0.3,0.1

Type RM Length L Ch R = 1 ,393643  ,3421,3421,3421
BEGIN DESCRIPTION:
NAVASOTA RIVER 396
END DESCRIPTION:
XS GIS Cut Line= 3
      3599885.71     10315232.48      3591523.05     10313211.05
      3586726.11     10312800.27
#Sta/Elev= 30
 -3603.5  292.87 -2925.7  239.93 -2496.2  239.17 -2428.5  239.18    1324  240.12
  1505.3   238.9  2099.2  240.11  2405.9  239.91  4949.5  242.22  4990.4  233.09
  5041.1  242.19  5412.4  237.91  6315.7  243.64  6345.9  236.78  6466.3  244.72
  6536.5  235.26  6606.8   234.5    6657  242.56  6818.8  245.99  6908.3  247.49
  7007.1  245.94    7261   244.4  8784.7  249.81  8927.7  256.69  9033.6  264.76
  9186.2  263.58  9359.5  283.76  9457.2  296.19  9527.5  294.14  9814.5  308.23
#Mann= 16 ,-1 , 0
 -3603.5     .16       0 -2925.7     .12       0 -2496.2     .16       0
 -2428.5     .12       0    1324     .07       0  1505.3     .12       0
  2099.2     .07       0  2405.9     .12       0  4949.5     .07       0
  5041.1     .12       0  6818.8     .16       0  6908.3     .05       0
  7007.1     .12       0    7261     .05       0  8927.7     .16       0
  9359.5     .05       0
#XS Ineff= 2 ,-1
  6315.7    6930  243.64    6930  8784.7   247.8
Permanent Ineff=
       F       F
Bank Sta=4949.5,5041.1
XS Rating Curve= 0 ,0
Exp/Cntr=0.3,0.1

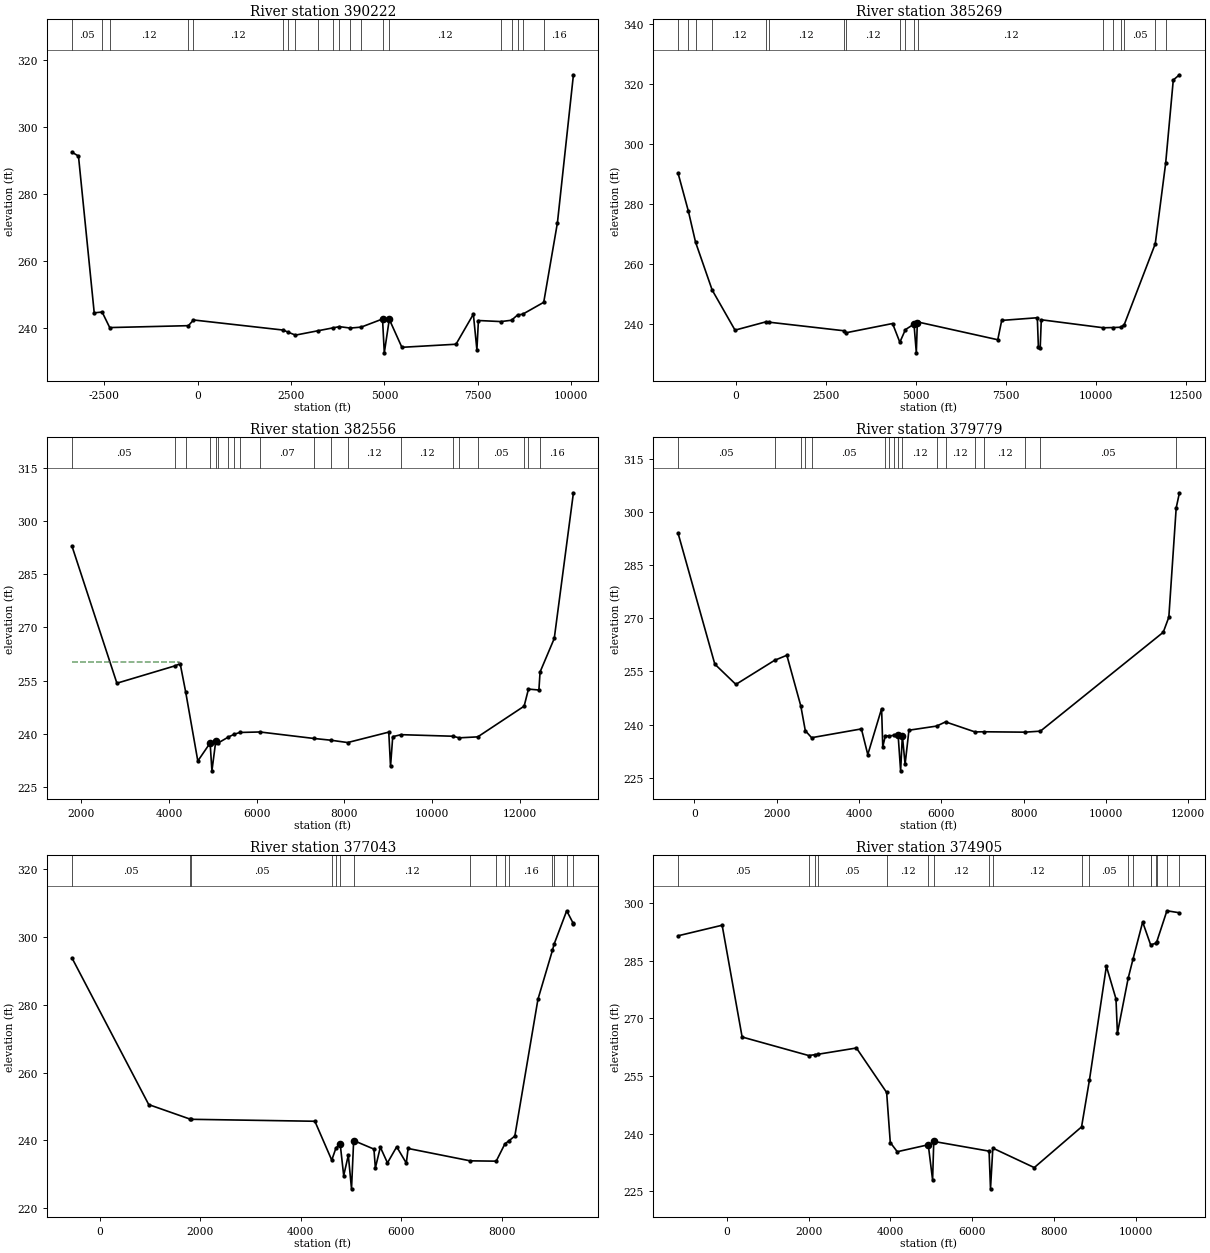
Type RM Length L Ch R = 1 ,390222  ,4953,4953,4953
BEGIN DESCRIPTION:
NAVASOTA RIVER 397
END DESCRIPTION:
XS GIS Cut Line= 3
      3600937.82     10313984.65      3592880.24     10311762.41
      3587917.03     10310794.56
#Sta/Elev= 30
 -3358.4  292.45 -3186.5  291.31 -2765.2  244.52 -2553.4  244.76 -2350.7  240.12
  -244.7  240.69  -109.4  242.39  2289.4  239.38  2420.1  238.76  2619.4  237.87
  3217.5  239.16  3626.6  240.04  3795.2   240.4  4086.5  239.97  4378.3  240.26
  4948.9  242.68  4996.2  232.58  5130.1  242.58  5466.8  234.23  6914.8  235.15
  7379.2  244.11  7473.9  233.49  7514.6  242.23  8114.8  241.91  8400.3  242.31
  8560.5  243.87  8700.3  244.12  9261.9  247.66  9628.3  271.38 10056.7  315.57
#Mann= 20 ,-1 , 0
 -3358.4     .05       0 -2553.4     .16       0 -2350.7     .12       0
  -244.7     .07       0  -109.4     .12       0  2289.4     .12       0
  2420.1     .07       0  2619.4     .12       0  3217.5     .07       0
  3626.6     .12       0  3795.2     .07       0  4086.5     .07       0
  4378.3     .12       0  4948.9     .07       0  5130.1     .12       0
  8114.8     .16       0  8400.3     .16       0  8560.5     .12       0
  8700.3     .05       0  9261.9     .16       0
#XS Ineff= 2 , 0
       0                  7379.2       0  244.11
Permanent Ineff=
       F       F
Bank Sta=4948.9,5130.1
XS Rating Curve= 0 ,0
Exp/Cntr=0.3,0.1

Type RM Length L Ch R = 1 ,385269  ,2713,2713,2713
BEGIN DESCRIPTION:
NAVASOTA RIVER 398
END DESCRIPTION:
XS GIS Cut Line= 4
       3600048.6     10310756.57      3593824.64     10310157.61
      3592900.16     10309493.55       3586350.7     10309415.43
#Sta/Elev= 30
 -1609.5  290.28 -1322.5  277.59 -1123.3  267.27  -661.1  251.29   -25.7  237.91
   844.7  240.72   917.8  240.57  2993.6  237.72  3054.2  237.02  4354.4  240.12
  4557.2  233.87  4712.1  238.09  4950.7  239.93  5015.5  230.34  5042.8  240.34
  5051.4  240.65  7279.6  234.71  7389.6  241.16  8379.7  242.05  8409.7  232.13
  8459.7  231.93  8489.7  241.37   10219   238.7 10483.8  238.78 10696.1  238.88
 10794.8   239.7 11658.8  266.72 11948.4  293.62   12160  321.36 12331.4  323.11
#Mann= 18 ,-1 , 0
 -1609.5     .16       0 -1322.5     .12       0 -1123.3     .05       0
  -661.1     .12       0   844.7     .07       0   917.8     .12       0
  2993.6     .07       0  3054.2     .12       0  4557.2     .07       0
  4712.1     .12       0  4950.7     .07       0  5051.4     .12       0
   10219     .07       0 10483.8     .12       0 10696.1     .16       0
 10794.8     .05       0 11658.8     .16       0 11948.4     .05       0
#XS Ineff= 2 , 0
       0                  8379.7       0  242.05
Permanent Ineff=
       F       F
Bank Sta=4950.7,5042.8
XS Rating Curve= 0 ,0
Exp/Cntr=0.3,0.1

Type RM Length L Ch R = 1 ,382556  ,2777,2777,2777
BEGIN DESCRIPTION:
NAVASOTA RIVER 338
END DESCRIPTION:
XS GIS Cut Line= 3
      3597851.17     10308936.01        3594741.       10308151.
      3586525.43     10307935.37
#Sta/Elev= 30
  1792.3  292.81  2814.4  254.25  4147.1  259.17  4256.3  259.77    4383   251.7
  4658.5  232.33  4939.1  237.41  4979.9  229.56  5068.9  238.07  5127.6  237.45
  5355.6  239.09  5481.9  239.83  5613.4  240.37  6074.1  240.51  7298.3  238.69
  7690.4  238.19  8072.6  237.53  9010.3  240.47  9050.3   230.8  9100.3  239.19
    9291  239.75 10472.3  239.31 10614.9  238.86 11037.8  239.13 12094.8  247.78
 12193.5  252.59 12431.5  252.33   12458   257.4 12781.6  266.86 13218.4   307.9
#Mann= 20 ,-1 , 0
  1792.3     .05       0  4147.1     .16       0    4383     .12       0
  4939.1     .07       0  5068.9     .12       0  5127.6     .07       0
  5355.6     .12       0  5481.9     .07       0  5613.4     .12       0
  6074.1     .07       0  7298.3     .12       0  7690.4     .07       0
  8072.6     .12       0    9291     .12       0 10472.3     .05       0
 10614.9     .12       0 11037.8     .05       0 12094.8     .08       0
 12193.5     .05       0   12458     .16       0
#XS Ineff= 2 , 0
       0  4235.7  260.25  9010.3       0  240.47
Permanent Ineff=
       F       F
Bank Sta=4939.1,5068.9
XS Rating Curve= 0 ,0
Exp/Cntr=0.3,0.1

Type RM Length L Ch R = 1 ,379779  ,2736,2736,2736
BEGIN DESCRIPTION:
NAVASOTA RIVER 337
END DESCRIPTION:
XS GIS Cut Line= 3
      3597919.75     10308907.65      3593591.75     10306666.34
      3586352.16     10305650.71
#Sta/Elev= 30
  -398.1  293.99   495.1  257.05  1006.9  251.33  1948.3  258.13  2245.7  259.55
  2585.2  245.23  2694.2  238.28    2847   236.3  4057.5  238.78  4212.5  231.54
  4548.4   244.5  4576.4  233.73  4640.1  236.84  4739.3  236.79  4838.4  236.96
  4950.1  236.95  5010.4  226.95  5052.8   236.9  5119.1  228.79  5212.6  238.41
  5886.7  239.58  6102.4  240.76  6820.3  237.92  7025.2  237.97  8042.3  237.86
  8407.8  238.15 11392.5  266.04 11528.3   270.3 11707.6  301.15 11786.3  305.39
#Mann= 17 ,-1 , 0
  -398.1     .05       0  1948.3     .16       0  2585.2     .07       0
  2694.2     .12       0    2847     .05       0  4640.1     .12       0
  4739.3     .05       0  4838.4     .12       0  4950.1     .07       0
  5052.8     .12       0  5886.7     .16       0  6102.4     .12       0
  6820.3     .05       0  7025.2     .12       0  8042.3      .1       0
  8407.8     .05       0 11707.6     .16       0
#XS Ineff= 2 , 0
       0  2245.7  259.55               0
Permanent Ineff=
       F       F
Bank Sta=4950.1,5052.8
XS Rating Curve= 0 ,0
Exp/Cntr=0.3,0.1

Type RM Length L Ch R = 1 ,377043  ,2138,2138,2138
BEGIN DESCRIPTION:
NAVASOTA RIVER 336
END DESCRIPTION:
XS GIS Cut Line= 2
      3597992.66      10308756.6      3590941.12     10301715.36
#Sta/Elev= 30
    -547  293.84   977.2  250.59  1788.2  246.36  1819.5  246.25  4279.4  245.67
  4614.7  234.19  4697.1  237.72  4781.4  239.09  4852.1  229.63    4944  235.64
  5007.4  225.72  5050.1  239.98  5453.2  237.45  5481.4  231.88  5580.4  238.02
  5721.9  233.38  5905.7  238.13  6096.6  233.32    6132  237.64  7365.1  233.99
  7883.3  233.89  8054.8  238.96  8137.7  239.93  8253.3  241.29  8712.9  281.68
  9002.1  296.18  9032.6   297.9  9284.5  307.81    9407  304.29  9418.1     304
#Mann= 15 ,-1 , 0
    -547     .05       0  1788.2     .16       0  1819.5     .05       0
  4614.7     .12       0  4697.1     .05       0  4781.4     .07       0
  5050.1     .12       0  7365.1     .05       0  7883.3     .12       0
  8054.8     .05       0  8137.7     .16       0  9002.1     .05       0
  9032.6     .16       0  9284.5     .05       0    9407     .16       0
Bank Sta=4781.4,5050.1
XS Rating Curve= 0 ,0
Exp/Cntr=0.3,0.1

Type RM Length L Ch R = 1 ,374905  ,422,422,422
BEGIN DESCRIPTION:
NAVASOTA RIVER 335
END DESCRIPTION:
XS GIS Cut Line= 6
      3599449.48     10308886.23      3597451.86     10306729.39
      3595961.58     10305003.56      3594932.81     10303875.15
      3592674.95       10301438.      3591238.82     10299796.47
#Sta/Elev= 30
 -1189.7  291.49  -112.7  294.24   375.5  265.15  2001.8  260.33  2144.4  260.54
  2228.1  260.66  3168.5  262.29  3906.7  250.72  3995.6  237.69  4166.2   235.3
  4923.5  237.11  5029.5  227.95  5057.9  237.98  6409.4  235.45  6444.3  225.64
  6501.3  236.23  7513.6  231.17  8669.2  241.76  8862.4     254  9275.7  283.56
  9510.2  275.07  9545.3  266.12  9808.8  280.48  9926.7  285.44 10162.2  295.07
 10357.3  289.12 10484.5  289.57 10500.9  289.75 10754.8     298 11060.8  297.48
#Mann= 19 ,-1 , 0
 -1189.7     .05       0  2001.8     .08       0  2144.4      .1       0
  2228.1     .05       0  3906.7     .12       0  4923.5     .07       0
  5057.9     .12       0  6409.4     .07       0  6501.3     .12       0
  8669.2     .16       0  8862.4     .05       0  9808.8     .16       0
  9926.7     .05       0 10357.3     .05       0 10357.3     .16       0
 10484.5     .05       0 10500.9     .16       0 10754.8     .05       0
 11060.8     .05       0
Bank Sta=4923.5,5057.9
XS Rating Curve= 0 ,0
Exp/Cntr=0.3,0.1

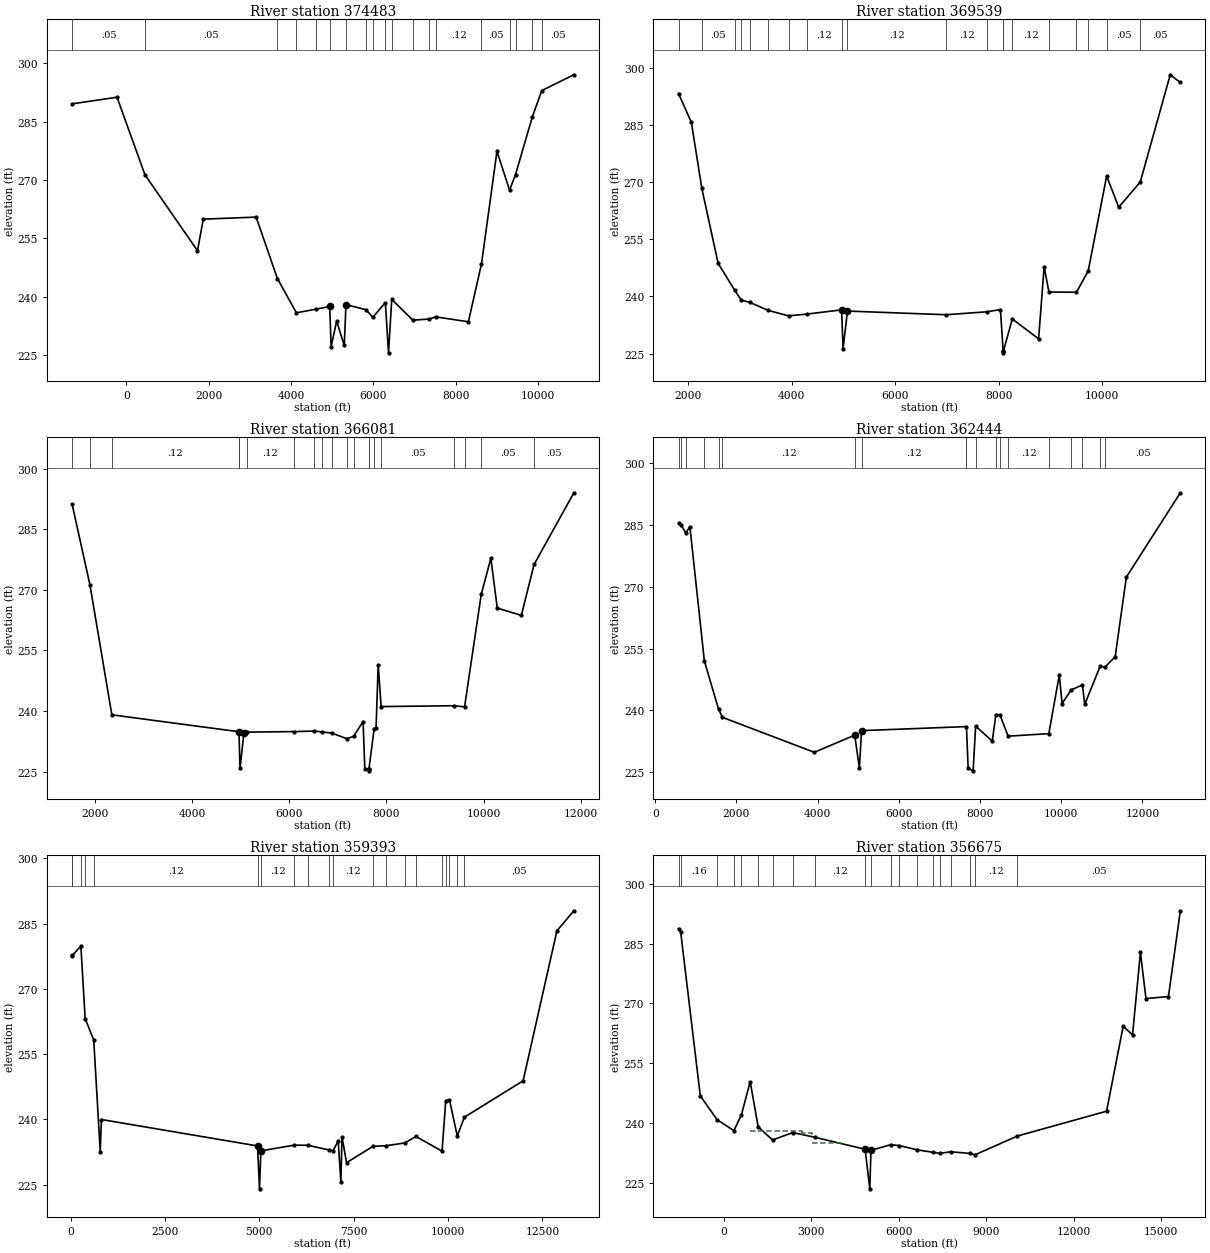
Type RM Length L Ch R = 1 ,374483  ,4944,4944,4944
BEGIN DESCRIPTION:
NAVASOTA RIVER 334
END DESCRIPTION:
XS GIS Cut Line= 6
       3599735.6     10308621.21      3597740.95     10306467.57
      3595954.58     10304412.79      3592964.76     10301176.96
      3592123.83     10300182.21      3591641.05     10299521.77
#Sta/Elev= 30
 -1315.1  289.54  -223.4  291.24   454.2  271.32  1730.1  251.82  1871.4  259.92
  3154.6  260.44  3670.5  244.66  4132.6  235.86  4600.3  236.77  4940.4  237.48
  4975.6  227.17    5110  233.72  5294.5  227.47  5336.4  237.95  5818.3  236.67
    5989  234.71  6291.9  238.49  6369.3  225.57  6447.3  239.31  6960.3  233.96
  7350.3  234.25  7516.3  234.81  8308.6  233.55  8626.8  248.42  9002.7  277.35
  9308.3  267.37  9452.8  271.37  9863.7  286.27 10090.8  292.95 10869.9  297.01
#Mann= 19 ,-1 , 0
 -1315.1     .05       0   454.2     .05       0  3670.5     .12       0
  4132.6     .12       0  4600.3     .12       0  4940.4     .07       0
  5336.4     .12       0  5818.3     .12       0    5989     .12       0
  6291.9     .07       0  6447.3     .07       0  6960.3     .12       0
  7350.3     .12       0  7516.3     .12       0  8626.8     .05       0
  9308.3     .16       0  9452.8     .05       0  9863.7     .05       0
 10090.8     .05       0
Bank Sta=4940.4,5336.4
XS Rating Curve= 0 ,0
Exp/Cntr=0.3,0.1

Type RM Length L Ch R = 1 ,369539  ,3458,3458,3458
BEGIN DESCRIPTION:
NAVASOTA RIVER 405
END DESCRIPTION:
XS GIS Cut Line= 3
      3599848.49     10305545.51      3597454.62     10303436.01
      3592405.99     10299322.93
#Sta/Elev= 30
  1809.3  293.21  2057.7  285.66  2259.7  268.33  2574.9  248.65  2898.3  241.54
  3026.6  238.98  3182.1  238.47  3534.5  236.36  3936.1  234.88    4298  235.36
  4962.7  236.46  4990.3  226.31  5076.2  236.14    6985  235.18    7769  235.95
  8033.4  236.54  8086.4  225.68  8089.1  225.18  8092.4  225.68  8263.4  234.07
  8771.6  228.85  8878.6  247.77  8971.1  241.14  9503.5  241.08  9731.1  246.69
 10087.2  271.57 10321.3  263.39 10737.9  270.02 11316.6  298.15   11512  296.13
#Mann= 20 ,-1 , 0
  1809.3     .05       0  2259.7     .05       0  2898.3     .05       0
  3026.6     .05       0  3182.1     .07       0  3534.5     .12       0
  3936.1     .12       0    4298     .12       0  4962.7     .07       0
  5076.2     .12       0    6985     .12       0    7769     .12       0
  8086.4     .07       0  8092.4     .07       0  8263.4     .12       0
  8971.1     .05       0  9503.5     .12       0  9731.1     .16       0
 10087.2     .05       0 10737.9     .05       0
Bank Sta=4962.7,5076.2
XS Rating Curve= 0 ,0
Exp/Cntr=0.3,0.1

Type RM Length L Ch R = 1 ,366081  ,3637,3637,3637
BEGIN DESCRIPTION:
NAVASOTA RIVER 408
END DESCRIPTION:
XS GIS Cut Line= 3
      3601071.69     10304246.23       3598359.8     10302085.71
      3592296.37     10298890.71
#Sta/Elev= 30
  1532.7  291.23  1899.7  271.26    2351  239.05  4965.8  234.86  4986.6  225.77
  5066.6  234.52  5121.4  234.77    6102  234.89  6517.4  235.04  6675.6  234.81
  6871.5  234.53  7180.6  233.16  7321.3  233.69    7518  237.38  7554.2  225.72
  7633.6  225.68  7636.4  225.18  7639.6  225.68  7746.4  235.64  7785.2  235.87
  7829.2  251.45    7889  241.09    9387   241.3  9605.8  241.01  9948.3  268.84
 10146.2  277.79 10278.4  265.47 10773.7  263.67 11035.6  276.27 11853.7  294.02
#Mann= 20 ,-1 , 0
  1532.7     .05       0  1899.7     .16       0    2351     .12       0
  4965.8     .07       0  4965.8     .07       0  5121.4     .12       0
    6102     .16       0  6517.4     .16       0  6675.6      .1       0
  6871.5     .05       0  7180.6     .05       0  7321.3     .05       0
  7633.6     .07       0  7639.6     .05       0  7746.4     .12       0
    7889     .05       0    9387     .07       0  9605.8     .12       0
  9948.3     .05       0 11035.6     .05       0
Bank Sta=4965.8,5066.6
XS Rating Curve= 0 ,0
Exp/Cntr=0.3,0.1

Type RM Length L Ch R = 1 ,362444  ,3051,3051,3051
BEGIN DESCRIPTION:
NAVASOTA RIVER 407
END DESCRIPTION:
XS GIS Cut Line= 3
      3603816.71     10302637.81      3599971.78     10300443.53
      3592235.68     10298678.93
#Sta/Elev= 30
     573  285.33   637.7  285.02   748.9  283.05   853.3  284.49  1209.2     252
    1558  240.33  1653.4  238.32  3917.3  229.84  4913.1  233.99  5028.1  226.02
  5081.7  235.09  7666.4  236.07  7707.5  225.96  7830.3  225.34  7892.1  236.18
  8302.4  232.54  8391.5     239  8491.9  238.89  8692.7  233.75  9695.1  234.36
  9953.7  248.58 10021.3  241.65 10245.8  244.97 10523.3  246.18 10579.4  241.45
 10961.9  250.77 11072.4  250.45 11329.8  253.01 11605.1  272.33 12934.8  292.78
#Mann= 19 ,-1 , 0
     573      .1       0   637.7     .15       0   748.9     .16       0
  1209.2     .12       0    1558     .05       0  1653.4     .12       0
  4913.1     .07       0  5081.7     .12       0  7666.4     .07       0
  7666.4     .07       0  7892.1     .12       0  8391.5     .15       0
  8491.9      .1       0  8692.7     .12       0  9695.1     .05       0
 10245.8     .16       0 10523.3     .05       0 10961.9     .16       0
 11072.4     .05       0
Bank Sta=4913.1,5081.7
XS Rating Curve= 0 ,0
Exp/Cntr=0.3,0.1

Type RM Length L Ch R = 1 ,359393  ,2718,2718,2718
BEGIN DESCRIPTION:
NAVASOTA RIVER 193
END DESCRIPTION:
XS GIS Cut Line= 3
      3604583.95      10301898.8      3599913.78     10298999.48
      3592136.54     10298391.88
#Sta/Elev= 30
    37.4   277.7    40.5  277.66   270.8  279.83   384.3  263.17   611.2  258.27
     784  232.61   814.7  239.97  4952.8  233.89  5004.6  224.03  5041.4  232.77
    5923  234.07  6293.9  234.04  6853.5  232.95    6950  232.76  7090.8  235.03
    7161  225.59  7191.1  235.96  7311.4  230.05  8010.3   233.8  8363.6  233.95
  8854.5  234.58  9150.8  236.07  9842.1  232.69  9940.9  244.31 10039.6  244.52
 10245.5  236.17 10434.7   240.5 11990.5  248.87 12886.2  283.35 13335.3  287.96
#Mann= 20 ,-1 , 0
    37.4     .12       0    40.5     .16       0   270.8     .08       0
   384.3     .05       0   611.2     .12       0  4952.8     .07       0
  5041.4     .12       0    5923     .05       0  6293.9     .05       0
  6853.5     .07       0    6950     .12       0  8010.3     .12       0
  8363.6     .05       0  8854.5      .1       0  9150.8     .05       0
  9842.1      .1       0  9940.9     .08       0 10039.6     .05       0
 10245.5     .16       0 10434.7     .05       0
Bank Sta=4952.8,5041.4
XS Rating Curve= 0 ,0
Exp/Cntr=0.3,0.1

Type RM Length L Ch R = 1 ,356675  ,3973,3973,3973
BEGIN DESCRIPTION:
NAVASOTA RIVER 406
END DESCRIPTION:
XS GIS Cut Line= 3
       3607947.8     10298250.65      3601399.73     10298095.53
      3590755.11     10297665.65
#Sta/Elev= 30
 -1549.9  288.77 -1477.4  287.98    -804  246.84  -227.4  240.87   347.3  238.12
   605.4  242.06   906.5  250.41  1180.8  239.04  1674.3  235.79  2365.2  237.64
  3118.5  236.47  4847.6  233.46  5007.4  223.54  5047.7  233.18  5720.9  234.61
  6016.9  234.38  6625.4  233.32  7168.2  232.71  7398.5  232.45  7793.3  232.83
  8429.4  232.42  8615.1  232.07 10063.1  236.77 13124.2     243 13694.7  264.31
   14015  262.12 14285.2  282.79 14475.3  271.24   15246  271.74 15653.3  293.24
#Mann= 20 ,-1 , 0
 -1549.9     .05       0 -1477.4     .16       0  -227.4     .05       0
   347.3     .05       0   605.4     .16       0  1180.8     .12       0
  1674.3     .05       0  2365.2     .12       0  3118.5     .12       0
  4847.6     .07       0  5047.7     .12       0  5720.9     .16       0
  6016.9     .05       0  6625.4     .12       0  7168.2      .1       0
  7398.5     .05       0  7793.3     .12       0  8429.4     .07       0
  8615.1     .12       0 10063.1     .05       0
#XS Ineff= 4 ,-1
  -958.8   906.5  250.41   906.5    2687  237.98    2687  3027.1  237.52
  3027.1  4027.4  235.06
Permanent Ineff=
       F       F       F       F
Bank Sta=4847.6,5047.7
XS Rating Curve= 0 ,0
Exp/Cntr=0.3,0.1