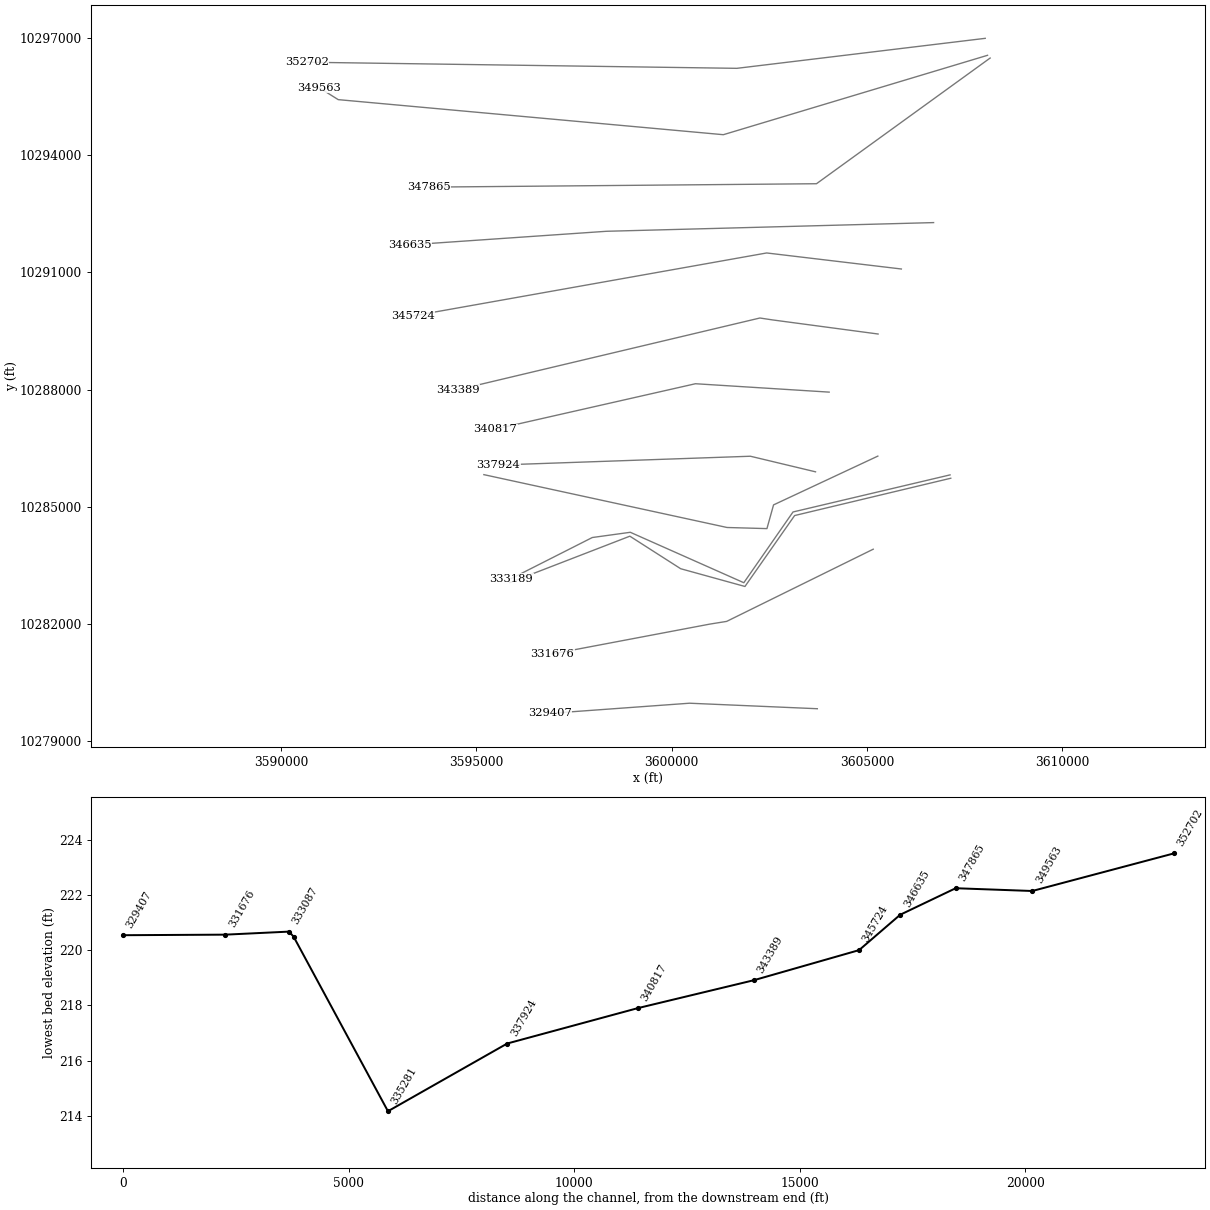
HEC-RAS study NAVASOTA RIVER.prj: NAVASOTA RIVER Base Level Engineering

--- NAVASOTA RIVER.g01 (geometry) --- (continued)

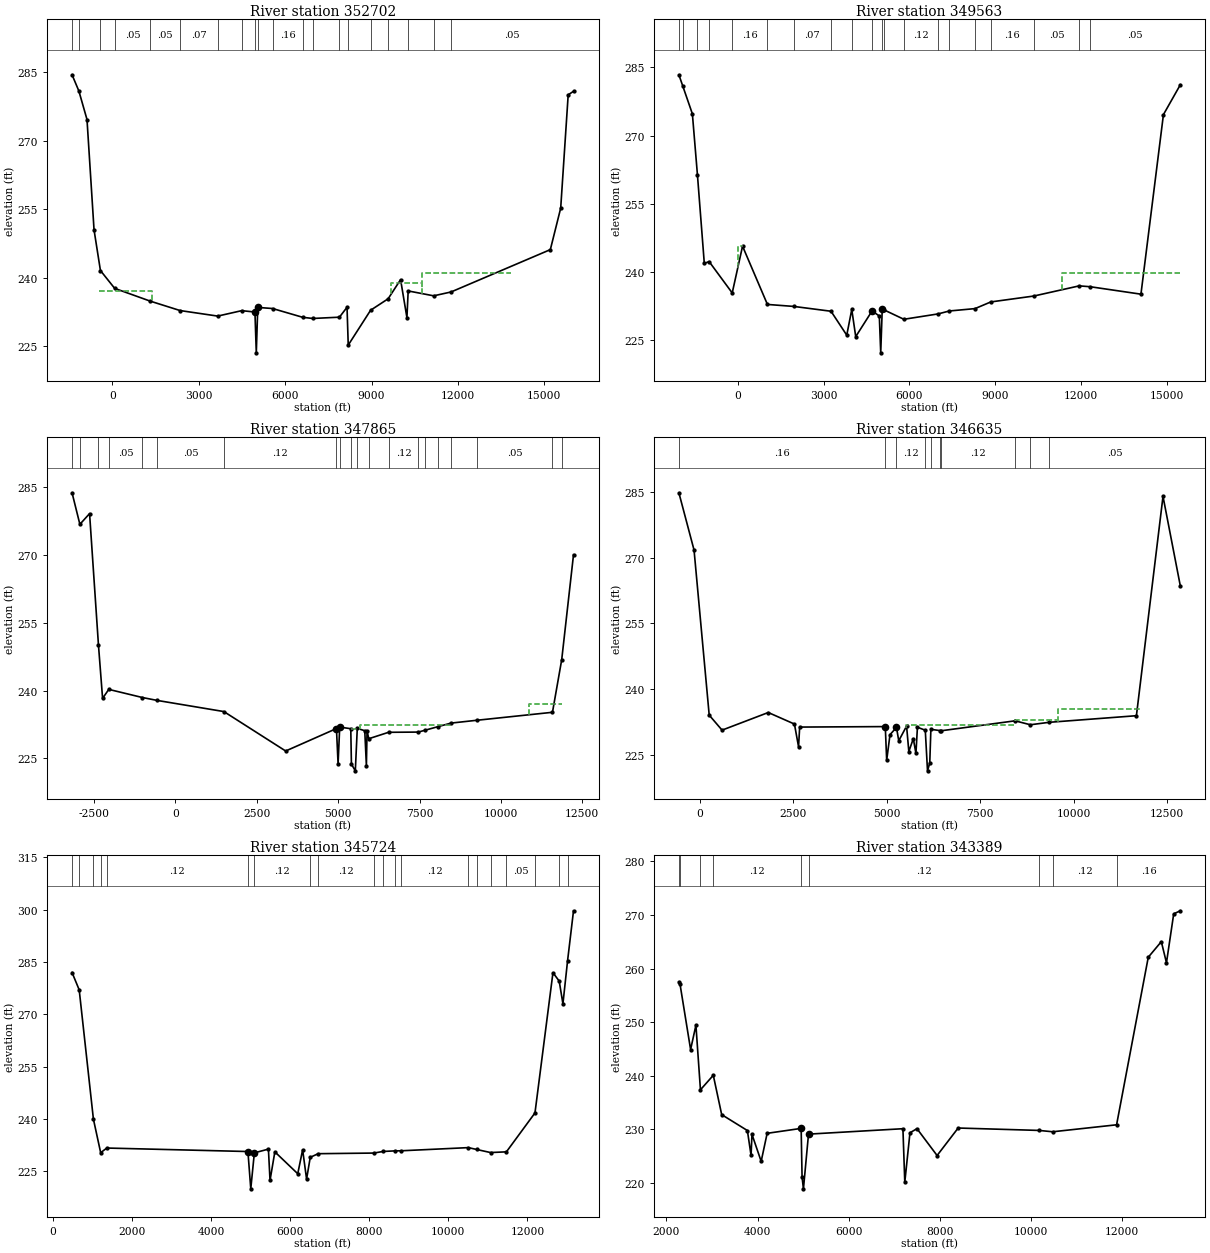
Type RM Length L Ch R = 1 ,352702  ,3139,3139,3139
BEGIN DESCRIPTION:
NAVASOTA RIVER 403
END DESCRIPTION:
XS GIS Cut Line= 3
      3608025.17     10296998.65      3601667.96     10296230.08
      3590657.18     10296386.64
#Sta/Elev= 30
 -1403.5  284.41 -1166.9  280.86  -884.3  274.61  -639.9  250.44    -418  241.53
    77.1  237.62  1314.4  234.82  2350.6  232.76  3655.2  231.55  4488.2  232.74
  4947.9  232.44  4995.1   223.5  5045.9  233.45  5558.6  233.21  6608.8  231.28
  6955.2  231.03  7881.6  231.31  8146.2  233.48  8188.3   225.2  8964.7  232.83
  9573.6  235.34 10006.4  239.54 10226.4  231.21 10269.9  237.06 11154.8  235.99
 11757.3  236.83 15206.9  246.11 15566.9   255.2   15827  280.02 16011.9  280.79
#Mann= 20 ,-1 , 0
 -1403.5     .05       0 -1166.9     .16       0    -418     .12       0
    77.1     .05       0  1314.4     .05       0  2350.6     .07       0
  3655.2     .07       0  4488.2     .12       0  4947.9     .07       0
  5045.9     .12       0  5558.6     .16       0  6608.8     .12       0
  6955.2     .05       0  7881.6     .05       0  8188.3     .12       0
  8964.7     .12       0  9573.6     .16       0 10269.9     .16       0
 11154.8     .16       0 11757.3     .05       0
#XS Ineff= 4 ,-1
  8146.2  9681.5  233.48  9681.5 10766.4  238.76 10766.4 13846.8  240.88
  -474.5  1358.6  237.07
Permanent Ineff=
       F       F       F       F
Bank Sta=4947.9,5045.9
XS Rating Curve= 0 ,0
Exp/Cntr=0.3,0.1

Type RM Length L Ch R = 1 ,349563  ,1698,1698,1698
BEGIN DESCRIPTION:
NAVASOTA RIVER 404
END DESCRIPTION:
XS GIS Cut Line= 4
      3608084.33     10296563.92       3601321.8     10294529.56
      3591463.91     10295428.16      3590975.67     10295734.61
#Sta/Elev= 30
 -2061.9  283.38 -1921.3  280.82 -1590.1  274.78 -1411.6  261.24   -1173  241.85
 -1003.9  242.24  -196.4  235.33   164.7  245.63  1034.7   232.8  1959.1  232.36
  3258.2   231.3  3809.2  226.03  3984.2  231.69  4122.5  225.71  4694.7  231.37
  4947.5  230.26    4997  222.14  5049.9  231.79  5109.3  231.61    5806  229.53
  7000.3  230.71  7398.4  231.36  8294.1  231.88    8846  233.35 10350.4  234.65
 11939.7  236.89   12324   236.7 14097.3  235.06 14883.8  274.61 15475.2  281.19
#Mann= 20 ,-1 , 0
 -2061.9     .05       0 -1921.3     .16       0 -1411.6     .12       0
 -1003.9     .05       0  -196.4     .16       0  1034.7     .05       0
  1959.1     .07       0  3258.2     .12       0  3984.2     .12       0
  4694.7     .07       0  5049.9     .12       0  5109.3      .1       0
    5806     .12       0  7000.3     .05       0  7398.4     .12       0
  8294.1     .16       0    8846     .16       0 10350.4     .05       0
 11939.7     .16       0   12324     .05       0
#XS Ineff= 2 , 0
       0   164.7  245.63 11345.9       0  239.65
Permanent Ineff=
       F       F
Bank Sta=4694.7,5049.9
XS Rating Curve= 0 ,0
Exp/Cntr=0.3,0.1

Type RM Length L Ch R = 1 ,347865  ,1230,1230,1230
BEGIN DESCRIPTION:
NAVASOTA RIVER 402
END DESCRIPTION:
XS GIS Cut Line= 3
      3608151.03     10296493.88      3603705.71     10293273.39
      3593789.09     10293186.58
#Sta/Elev= 30
 -3174.9  283.79 -2934.5  276.81 -2636.6  279.18 -2364.3  250.17 -2236.9  238.28
 -2046.7  240.27 -1013.7  238.47  -562.8  237.83  1489.4  235.36    3388  226.63
  4948.1   231.6  4998.1  223.79  5048.1  231.92  5388.1  231.57  5408.1  223.72
  5527.9  222.24  5588.1  231.64  5818.1  231.12  5868.1  223.37  5888.1  231.06
  5941.5  229.35  6549.1  230.77  7464.1  230.82  7669.9  231.23    8083  232.05
  8469.5  232.81  9256.9  233.43 11584.9   235.2 11869.1  246.86 12231.4  270.08
#Mann= 20 ,-1 , 0
 -3174.9     .05       0 -2934.5     .16       0 -2364.3     .16       0
 -2046.7     .05       0 -1013.7     .16       0  -562.8     .05       0
  1489.4     .12       0  4948.1     .07       0  5048.1     .12       0
  5388.1     .07       0  5588.1     .12       0  5941.5     .07       0
  6549.1     .12       0  7464.1     .12       0  7669.9     .16       0
    8083     .12       0  8469.5     .16       0  9256.9     .05       0
 11584.9     .05       0 11869.1     .16       0
#XS Ineff= 3 ,-1
  5388.1  5658.1  231.57  5658.1  8469.5  232.48 10878.3 11869.1  237.09
Permanent Ineff=
       F       F       F
Bank Sta=4948.1,5048.1
XS Rating Curve= 0 ,0
Exp/Cntr=0.3,0.1

Type RM Length L Ch R = 1 ,346635  ,911,911,911
BEGIN DESCRIPTION:
NAVASOTA RIVER 194
END DESCRIPTION:
XS GIS Cut Line= 4
      3606703.35     10292277.47      3601141.84     10292128.93
      3598333.92     10292055.04      3593299.17     10291707.81
#Sta/Elev= 30
  -563.5  284.88  -157.6  271.78     248  234.02   592.1  230.59  1828.6  234.62
  2528.8  231.98  2638.9  226.79  2668.9  231.29  4959.7   231.4  4997.4  223.68
  5085.8  229.55  5259.8  231.22  5319.8  228.16  5529.9  231.51  5589.9   225.7
    5710  228.64    5780  225.26    5820  231.25  6030.1  230.57  6089.9  221.28
  6150.1   223.1  6180.1  230.77  6413.4   230.5  6460.8  230.45  8431.8  232.72
  8843.2  231.82  9345.5  232.38 11679.9  233.89 12391.6  284.05 12855.6  263.55
#Mann= 10 ,-1 , 0
  -563.5     .16       0  4959.7     .07       0  5259.8     .12       0
  6030.1     .07       0  6180.1     .12       0  6413.4     .07       0
  6460.8     .12       0  8431.8     .05       0  8843.2     .12       0
  9345.5     .05       0
#XS Ineff= 3 ,-1
  5509.9  8422.2  231.73  9594.9 11840.3  235.35  8422.2  9594.9  232.84
Permanent Ineff=
       F       F       F
Bank Sta=4959.7,5259.8
XS Rating Curve= 0 ,0
Exp/Cntr=0.3,0.1

Type RM Length L Ch R = 1 ,345724  ,2335,2335,2335
BEGIN DESCRIPTION:
NAVASOTA RIVER 195
END DESCRIPTION:
XS GIS Cut Line= 3
      3605878.79     10291088.58      3602431.14     10291499.48
       3593368.6     10289884.89
#Sta/Elev= 30
   488.3  281.98   669.1  277.01  1028.1  239.98  1211.7  230.36  1367.2  231.69
  4934.5  230.69  5006.5     220    5097  230.31  5452.5  231.38  5493.2  222.42
    5615   230.6    6194  224.33  6317.5  231.18  6417.5  222.79  6510.1  229.03
  6710.1  230.07  8116.3  230.25  8350.4  230.71    8655  230.88    8802   230.9
 10507.9  231.81 10716.1  231.28 11067.1   230.4 11469.3   230.6 12191.3  241.75
 12645.8  281.93 12803.8  279.53 12897.9  273.01   13015  285.32 13165.6  299.67
#Mann= 20 ,-1 , 0
   488.3     .12       0   669.1     .16       0  1028.1     .12       0
  1211.7     .16       0  1367.2     .12       0  4934.5     .07       0
    5097     .12       0  6510.1     .07       0  6710.1     .12       0
  8116.3     .05       0  8350.4     .12       0    8655     .05       0
    8802     .12       0 10507.9     .05       0 10716.1     .07       0
 11067.1     .12       0 11469.3     .05       0 12191.3     .05       0
 12803.8     .16       0   13015     .05       0
Bank Sta=4934.5,5097
XS Rating Curve= 0 ,0
Exp/Cntr=0.3,0.1

Type RM Length L Ch R = 1 ,343389  ,2572,2572,2572
BEGIN DESCRIPTION:
NAVASOTA RIVER 196
END DESCRIPTION:
XS GIS Cut Line= 4
      3605283.04     10289422.63      3602579.41     10289784.19
      3602257.53     10289832.81      3594515.81     10287992.85
#Sta/Elev= 30
  2272.3  257.53    2297  257.13  2529.7   244.9  2646.5  249.45  2745.8  237.39
  3027.9   240.1  3212.2  232.76  3776.5  229.79  3857.2  225.15  3877.4  229.07
  4079.2  224.04  4210.3  229.27  4956.9  230.19  4977.1  221.15  5007.1  218.91
  5118.6  229.12  7191.5  230.13  7232.6  220.15  7346.2  229.37  7499.9  230.14
  7941.9  225.13  8404.4  230.26 10181.4  229.81 10480.5  229.56   11883  230.86
 12578.6  262.13 12865.3  265.04 12978.3   261.1 13137.2  270.23 13282.9   270.8
#Mann= 9 ,-1 , 0
  2272.3     .16       0    2297     .12       0  2745.8     .16       0
  3027.9     .12       0  4956.9     .07       0  5118.6     .12       0
 10181.4     .16       0 10480.5     .12       0   11883     .16       0
Bank Sta=4956.9,5118.6
XS Rating Curve= 0 ,0
Exp/Cntr=0.3,0.1

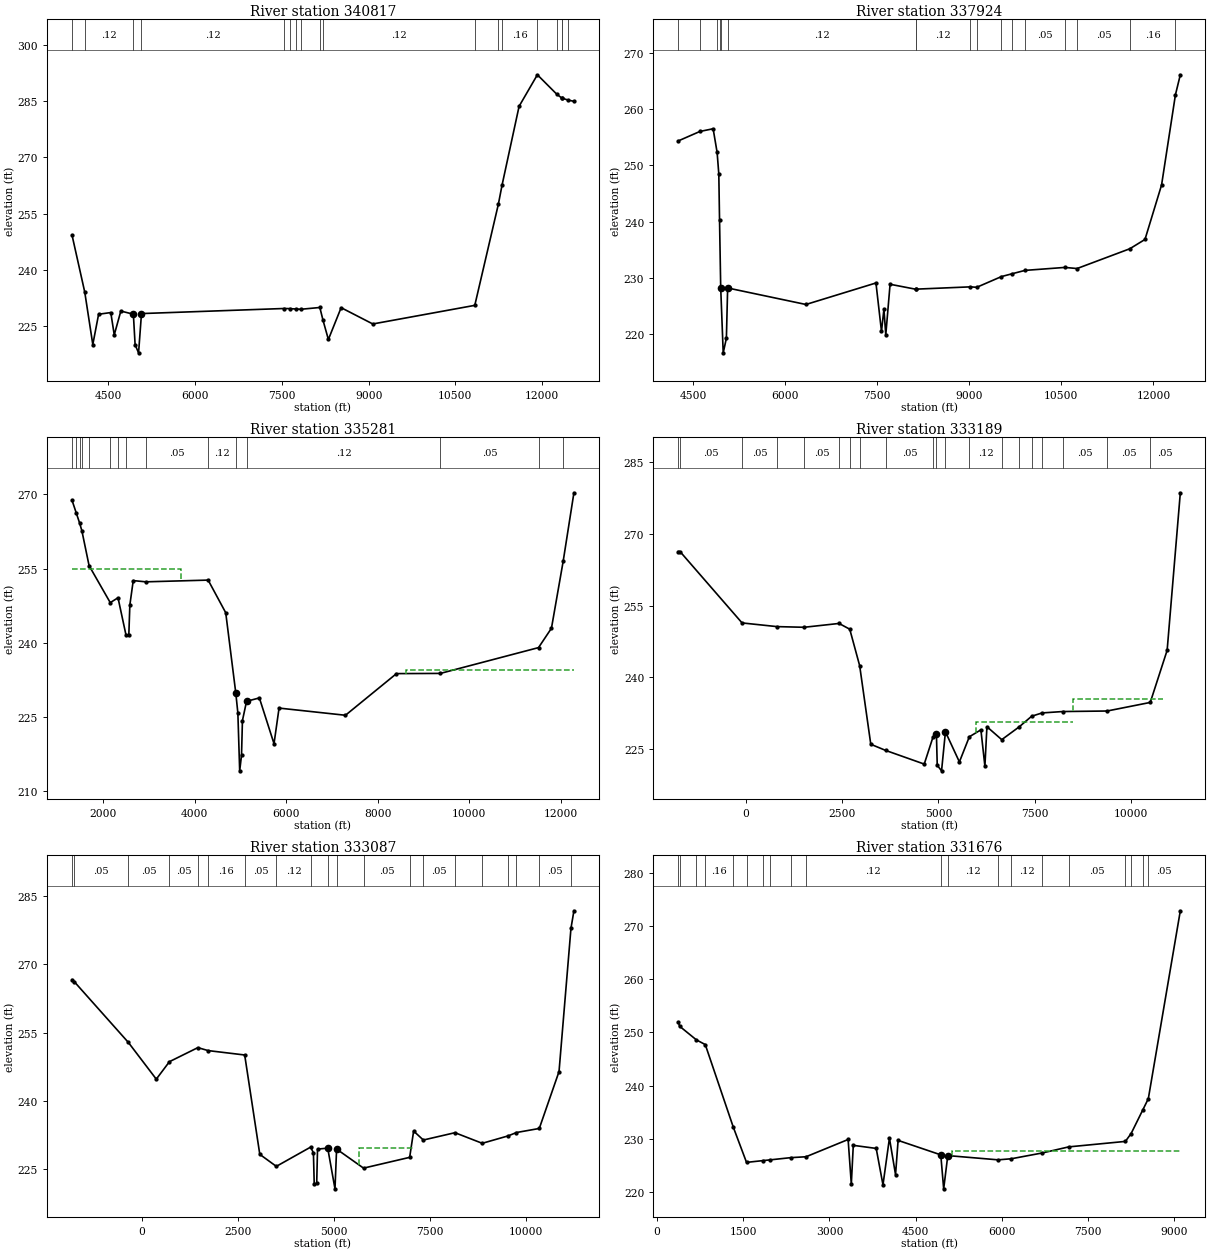
Type RM Length L Ch R = 1 ,340817  ,2893,2893,2893
BEGIN DESCRIPTION:
NAVASOTA RIVER 197
END DESCRIPTION:
XS GIS Cut Line= 4
      3604030.34     10287933.87      3602902.46      10288004.7
      3600608.22     10288148.79      3595486.91     10286985.64
#Sta/Elev= 30
  3869.9   249.2  4089.2  234.08  4228.5  220.12    4329  228.18  4539.4  228.63
  4599.6  222.69  4713.3  229.03  4930.2  228.19  4960.3  220.04  5020.1   217.9
  5070.5  228.36  7533.3  229.71  7633.7  229.68  7746.2  229.57  7831.4  229.51
  8155.7  229.98  8209.9  226.61  8303.3  221.46  8523.9  229.93  9071.6  225.59
 10835.8  230.55   11243  257.45 11307.9  262.61 11602.3  283.58 11918.3  291.97
   12251  286.84 12339.4  285.78 12351.4  285.72 12451.8  285.22 12550.5   284.9
#Mann= 18 ,-1 , 0
  3869.9     .05       0  4089.2     .12       0  4930.2     .07       0
  5070.5     .12       0  7533.3     .07       0  7633.7     .12       0
  7746.2     .07       0  7831.4     .12       0  8155.7     .07       0
  8209.9     .12       0 10835.8     .16       0   11243     .05       0
 11307.9     .16       0 11918.3     .05       0   12251      .1       0
 12339.4     .05       0 12351.4      .1       0 12451.8     .16       0
Bank Sta=4930.2,5070.5
XS Rating Curve= 0 ,0
Exp/Cntr=0.3,0.1

Type RM Length L Ch R = 1 ,337924  ,2643,2643,2643
BEGIN DESCRIPTION:
NAVASOTA RIVER 198
END DESCRIPTION:
XS GIS Cut Line= 3
      3603681.14     10285891.84      3602014.47     10286291.15
      3595556.65     10286065.47
#Sta/Elev= 30
    4262  254.37  4611.4  256.04  4826.6  256.52  4891.6   252.3  4919.1  248.45
    4931   240.2    4950  228.22  4990.8  216.62  5042.5  219.21  5063.1  228.17
  6338.4  225.23  7479.1  229.06  7569.2  220.45  7609.2   224.4  7639.2  219.82
  7709.3  228.83  8125.4  227.95  8130.8  227.96  9018.9  228.37  9120.9  228.29
  9524.1   230.2  9703.5  230.72  9907.1   231.3 10557.7  231.83 10755.3  231.63
 11614.2  235.15 11861.8  236.81   12132   246.5 12358.3  262.59 12437.6  266.13
#Mann= 17 ,-1 , 0
    4262     .16       0  4611.4     .05       0  4891.6     .16       0
    4931     .12       0    4950     .07       0  5063.1     .12       0
  8125.4     .07       0  8130.8     .12       0  9018.9     .05       0
  9120.9     .12       0  9524.1     .16       0  9703.5     .12       0
  9907.1     .05       0 10557.7     .07       0 10755.3     .05       0
 11614.2     .16       0 12358.3     .05       0
Bank Sta=4950,5063.1
XS Rating Curve= 0 ,0
Exp/Cntr=0.3,0.1

Type RM Length L Ch R = 1 ,335281  ,2092,2092,2092
BEGIN DESCRIPTION:
NAVASOTA RIVER 401
END DESCRIPTION:
XS GIS Cut Line= 5
       3605276.4     10286294.37      3602607.11     10285044.37
      3602437.84     10284436.73      3601417.01     10284465.37
      3595192.19     10285819.54
#Sta/Elev= 30
  1318.5  268.77  1411.5  266.19  1484.8  264.16  1532.6  262.65  1690.3   255.6
    2153  248.13  2322.7  249.11  2495.9  241.65  2558.7  241.53  2581.5  247.65
  2655.5  252.58  2930.6  252.33  4292.8  252.68  4677.4  246.09  4896.8  229.91
  4942.5  225.86  4982.3  214.17  5022.5  217.29  5042.5  224.32  5132.6  228.21
  5412.7  228.89  5732.8  219.65  5842.9  226.84  7294.3  225.39  8409.8   233.8
  9369.3  233.84 11514.8  239.05 11797.3  242.96   12053  256.45 12288.4  270.31
#Mann= 15 ,-1 , 0
  1318.5     .05       0  1411.5      .1       0  1484.8     .05       0
  1532.6     .16       0  1690.3     .05       0    2153     .16       0
  2322.7     .05       0  2495.9     .16       0  2930.6     .05       0
  4292.8     .12       0  4896.8     .07       0  5132.6     .12       0
  9369.3     .05       0 11514.8     .16       0   12053     .05       0
#XS Ineff= 2 , 0
       0  3693.2  254.85  8607.4       0  234.46
Permanent Ineff=
       F       F
Bank Sta=4896.8,5132.6
XS Rating Curve= 0 ,0
Exp/Cntr=0.3,0.1

Type RM Length L Ch R = 1 ,333189  ,102,102,102
BEGIN DESCRIPTION:
NAVASOTA RIVER 399
END DESCRIPTION:
XS GIS Cut Line= 6
      3607124.92     10285813.28      3603105.45     10284863.12
      3601846.22     10283050.22      3598940.68     10284342.54
      3597967.77     10284208.49      3595890.73     10283155.46
#Sta/Elev= 30
 -1746.9  266.28 -1707.6  266.28   -97.1  251.37   808.4   250.6  1513.5  250.46
  2419.6  251.26  2697.9  250.06  2955.1  242.44  3243.3  226.04  3630.5  224.75
  4630.6   221.9  4861.4  227.62  4947.1  228.13  4968.1  221.64  5080.1  220.49
  5180.8  228.64  5543.3  222.35  5800.9   227.6  6101.1  229.05    6205  221.46
  6257.5   229.7  6642.4     227  7097.4  229.69  7418.2  231.89    7689  232.58
  8225.8  232.87  9376.1  232.98   10496  234.77 10934.3  245.66 11276.3  278.54
#Mann= 20 ,-1 , 0
 -1746.9     .16       0 -1707.6     .05       0   -97.1     .05       0
   808.4     .05       0  1513.5     .05       0  2419.6     .05       0
  2697.9     .05       0  2955.1     .05       0  3630.5     .05       0
  4861.4     .08       0  4947.1     .07       0  5180.8     .08       0
  5800.9     .12       0  6642.4     .08       0  7097.4     .05       0
  7418.2     .05       0    7689     .12       0  8225.8     .05       0
  9376.1     .05       0   10496     .05       0
#XS Ineff= 2 ,-1
  5961.6  8498.6  230.64  8498.6 10814.9  235.51
Permanent Ineff=
       F       F
Bank Sta=4947.1,5180.8
XS Rating Curve= 0 ,0
Exp/Cntr=0.3,0.1

Type RM Length L Ch R = 1 ,333087  ,1411,1411,1411
BEGIN DESCRIPTION:
NAVASOTA RIVER 400
END DESCRIPTION:
XS GIS Cut Line= 6
      3607143.31     10285727.37      3603146.36     10284771.46
      3601874.92     10282954.12      3600230.19     10283408.82
       3598928.9     10284242.54      3595858.77     10283054.21
#Sta/Elev= 30
 -1817.9  266.64 -1762.3  266.22    -352  252.86   376.6  244.78   719.1  248.62
  1459.9  251.71  1725.6  251.06  2680.2  250.09  3073.6  228.25  3504.6  225.61
  4397.6  229.84  4470.9  228.59  4492.3  221.67  4556.4  221.86    4578  229.41
  4843.8  229.61  5032.9  220.67  5074.9  229.41  5777.5  225.22  6978.6  227.59
  7082.4  233.37    7335   231.4  8159.6  233.01  8869.7  230.68  9545.3  232.31
  9761.6  233.05 10356.3  233.94 10870.8  246.45 11181.6  277.92 11258.8  281.79
#Mann= 20 ,-1 , 0
 -1817.9     .08       0 -1762.3     .05       0    -352     .05       0
   719.1     .05       0  1459.9     .05       0  1725.6     .16       0
  2680.2     .05       0  3504.6     .12       0  4397.6     .08       0
  4843.8     .07       0  5074.9     .12       0  5777.5     .05       0
  6978.6     .05       0    7335     .05       0  8159.6     .05       0
  8869.7     .05       0  9545.3     .08       0  9761.6     .05       0
 10356.3     .05       0 11181.6     .08       0
#XS Ineff= 2 ,-1
  5665.7  7082.4  229.71  7082.4 10616.4  233.37
Permanent Ineff=
       F       F
Bank Sta=4843.8,5074.9
XS Rating Curve= 0 ,0
Exp/Cntr=0.3,0.1

Type RM Length L Ch R = 1 ,331676  ,2269,2269,2269
BEGIN DESCRIPTION:
NAVASOTA RIVER 409
END DESCRIPTION:
XS GIS Cut Line= 4
      3605158.25     10283909.37      3601406.83     10282059.38
      3600970.15     10281988.95      3596938.24     10281224.73
#Sta/Elev= 30
   374.9     252   392.8  251.19   687.1   248.6     841  247.72  1328.1  232.18
  1558.4  225.54  1848.7  225.88  1965.5  226.01  2325.7  226.43  2593.4   226.6
  3325.6  229.85  3381.1  221.44  3415.4  228.75    3814  228.17  3931.9  221.31
  4044.2   230.1  4150.4  223.23    4195  229.68  4937.2  226.96  4987.6  220.56
  5059.1  226.82  5933.7  226.02  6162.7  226.22  6700.4  227.31  7163.4  228.46
    8148  229.49  8247.8  230.97  8447.3  235.34  8547.1  237.53  9103.7  272.91
#Mann= 20 ,-1 , 0
   374.9     .05       0   392.8     .16       0   687.1     .05       0
     841     .16       0  1328.1     .12       0  1558.4     .05       0
  1848.7     .12       0  1965.5     .12       0  2325.7     .16       0
  2593.4     .12       0  4937.2     .07       0  5059.1     .12       0
  5933.7     .16       0  6162.7     .12       0  6700.4     .05       0
  7163.4     .05       0    8148     .16       0  8247.8     .12       0
  8447.3      .1       0  8547.1     .05       0
#XS Ineff= 2 , 0
       0                  5130.3       0  227.69
Permanent Ineff=
       F       F
Bank Sta=4937.2,5059.1
XS Rating Curve= 0 ,0
Exp/Cntr=0.3,0.1

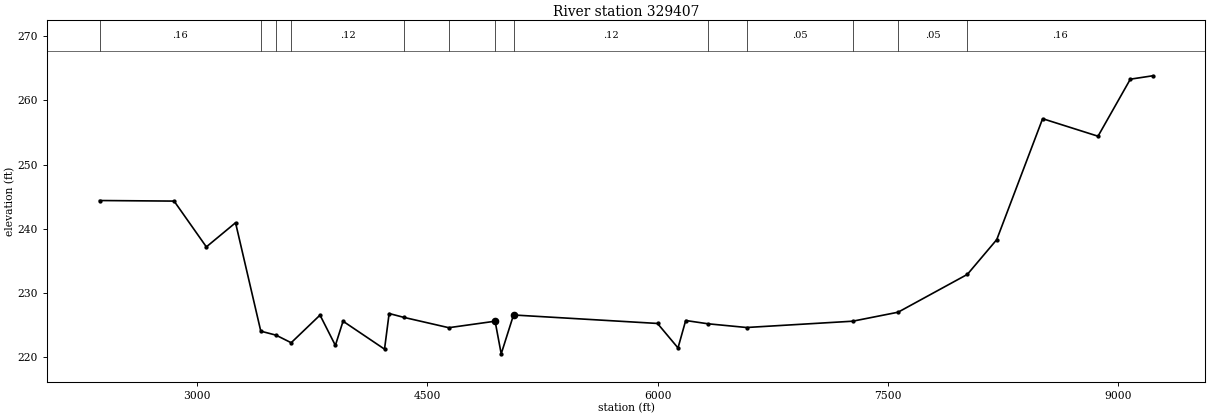
Type RM Length L Ch R = 1 ,329407  ,1755,1755,1755
BEGIN DESCRIPTION:
NAVASOTA RIVER 199
END DESCRIPTION:
XS GIS Cut Line= 3
      3603727.74     10279821.73      3600456.31     10279963.02
      3596876.34     10279702.66
#Sta/Elev= 30
  2362.6  244.41  2848.7  244.32  3058.9  237.19  3249.1  240.95  3413.6  224.07
  3512.6  223.45  3611.7  222.27  3799.6  226.57  3899.7  221.85  3949.7  225.62
    4220  221.27    4250  226.82  4345.4  226.22  4638.8  224.61  4940.6  225.62
  4980.4  220.54  5060.7  226.59    5999  225.27  6132.6  221.46  6182.7  225.73
  6327.7  225.22  6579.4  224.64  7270.5  225.62  7566.7  227.02  8018.3  232.91
  8209.8  238.32  8508.8  257.15  8869.8  254.42  9080.3   263.3  9226.5  263.83
#Mann= 13 ,-1 , 0
  2362.6     .16       0  3413.6     .12       0  3512.6     .05       0
  3611.7     .12       0  4345.4     .07       0  4638.8     .12       0
  4940.6     .07       0  5060.7     .12       0  6327.7      .1       0
  6579.4     .05       0  7270.5     .16       0  7566.7     .05       0
  8018.3     .16       0
Bank Sta=4940.6,5060.7
XS Rating Curve= 0 ,0
Exp/Cntr=0.3,0.1