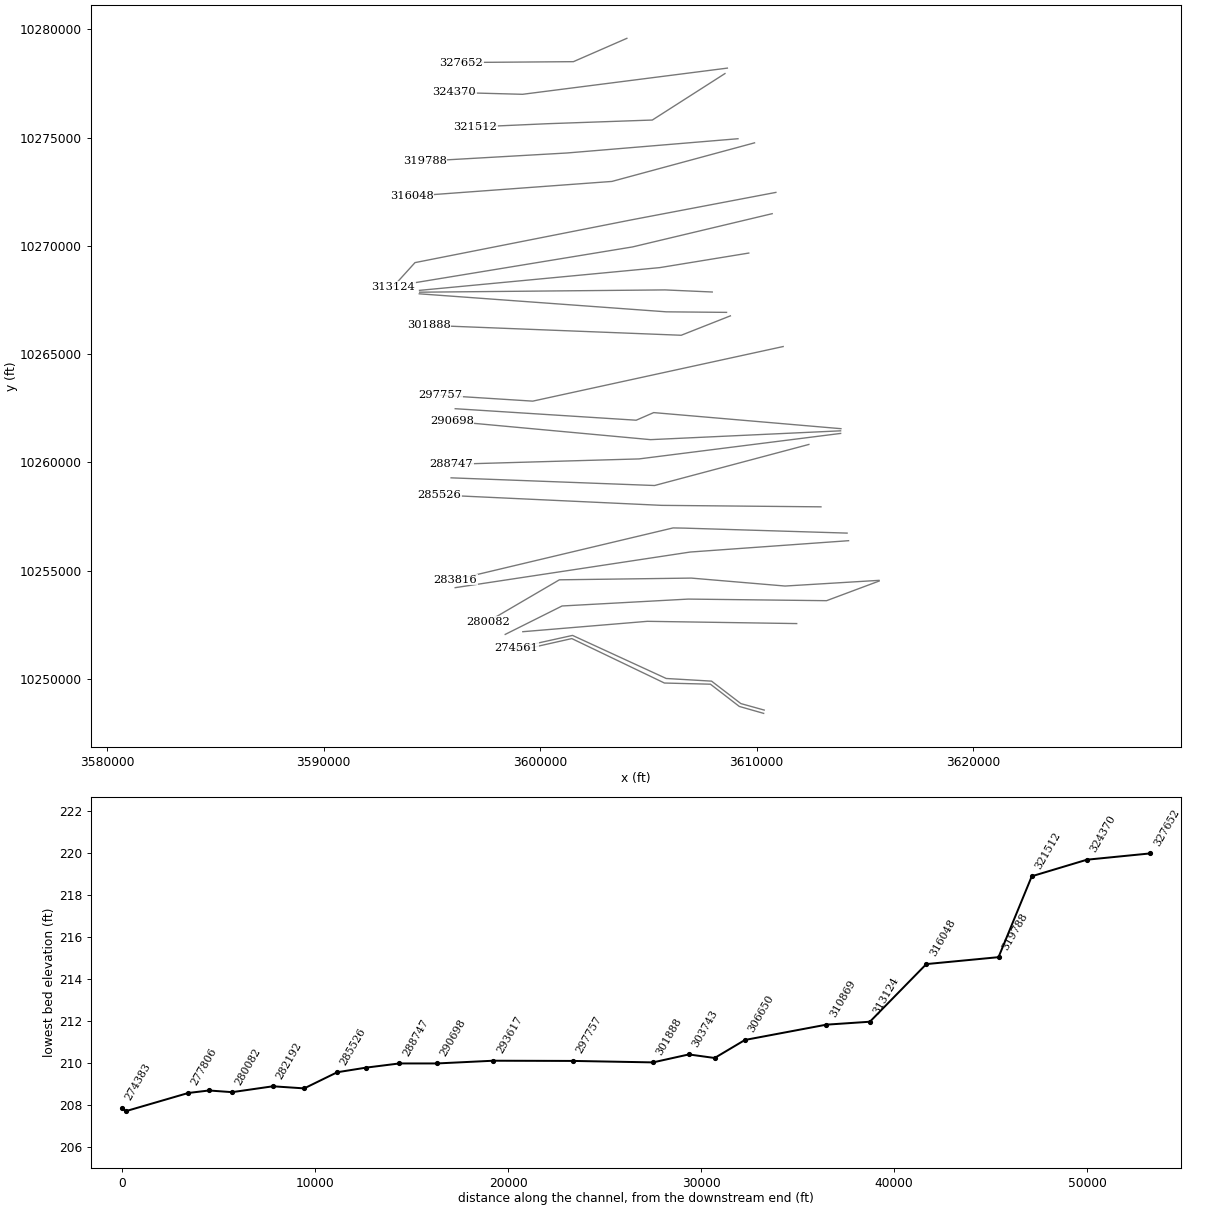
HEC-RAS study NAVASOTA RIVER.prj: NAVASOTA RIVER Base Level Engineering

--- NAVASOTA RIVER.g01 (geometry) --- (continued)

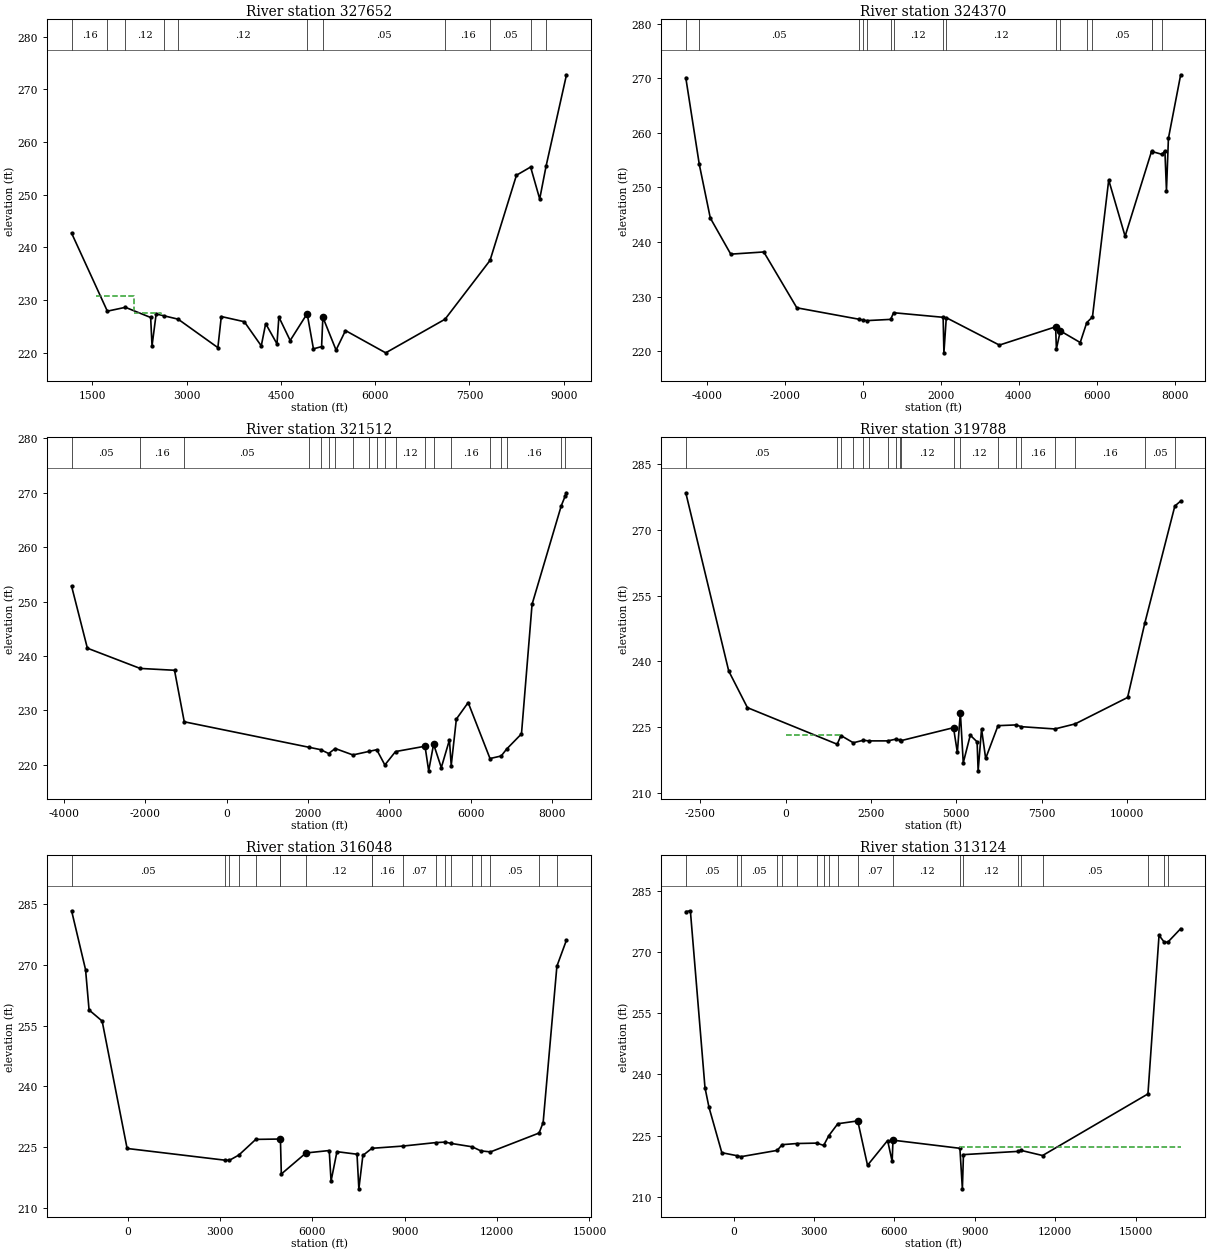
Type RM Length L Ch R = 1 ,327652  ,3282,3282,3282
BEGIN DESCRIPTION:
NAVASOTA RIVER 200
END DESCRIPTION:
XS GIS Cut Line= 3
      3604005.06     10279582.02      3601537.04     10278504.69
       3596355.9     10278465.64
#Sta/Elev= 30
    1169  242.72  1737.9  227.91  2025.1  228.64  2426.9  226.71  2448.8  221.32
  2514.3  227.38  2646.4  227.01    2864  226.39  3496.3  220.99  3550.9  226.89
  3916.8  225.91  4186.9  221.32  4256.9  225.54  4436.9   221.7  4466.9   226.8
  4646.9  222.34  4916.9  227.44  5016.9  220.76  5146.9  221.18  5166.9  226.76
  5376.9  220.53  5526.9  224.23  6166.7     220  7110.8  226.38  7826.6  237.54
    8247  253.71  8472.5  255.27    8617  249.21  8718.6  255.45  9043.2  272.78
#Mann= 11 ,-1 , 0
    1169     .16       0  1737.9     .05       0  2025.1     .12       0
  2646.4      .1       0    2864     .12       0  4916.9     .07       0
  5166.9     .05       0  7110.8     .16       0  7826.6     .05       0
  8472.5     .16       0  8718.6     .05       0
#XS Ineff= 2 ,-1
    1553  2165.1  230.86  2165.1  2590.7  227.64
Permanent Ineff=
       F       F
Bank Sta=4916.9,5166.9
XS Rating Curve= 0 ,0
Exp/Cntr=0.3,0.1

Type RM Length L Ch R = 1 ,324370  ,2858,2858,2858
BEGIN DESCRIPTION:
NAVASOTA RIVER 410
END DESCRIPTION:
XS GIS Cut Line= 3
      3608645.54     10278207.08      3599189.83     10276997.98
      3596038.16     10277082.22
#Sta/Elev= 30
 -4532.7  270.11 -4186.2  254.21 -3904.2   244.4   -3380  237.78 -2533.1  238.18
 -1686.1  227.95   -88.3  225.85     1.5  225.73   100.6   225.6   718.1  225.83
   794.3  227.05    2064  226.21  2083.9   219.7  2144.7  226.14  3505.7  221.12
  4947.3  224.47  4967.5  220.41  5067.8  223.72  5577.9  221.59  5745.7  225.24
  5891.7  226.27  6308.2  251.36  6728.3  241.06  7405.4  256.59  7424.8  256.57
  7674.1  256.06  7748.7  256.71  7788.7  249.41  7838.7  258.99  8152.8  270.64
#Mann= 16 ,-1 , 0
 -4532.7     .16       0 -4186.2     .05       0   -88.3     .12       0
     1.5     .07       0   100.6     .12       0   718.1     .16       0
   794.3     .12       0    2064     .07       0  2144.7     .12       0
  4947.3     .07       0  5067.8     .12       0  5745.7     .16       0
  5891.7     .05       0  7405.4     .16       0  7424.8     .05       0
  7674.1     .16       0
Bank Sta=4947.3,5067.8
XS Rating Curve= 0 ,0
Exp/Cntr=0.3,0.1

Type RM Length L Ch R = 1 ,321512  ,1724,1724,1724
BEGIN DESCRIPTION:
NAVASOTA RIVER 411
END DESCRIPTION:
XS GIS Cut Line= 4
      3608534.43      10277955.2      3605180.27     10275809.38
      3600352.65     10275640.52      3596996.18     10275490.97
#Sta/Elev= 30
 -3812.4  252.82 -3424.6  241.44 -2126.8  237.72 -1281.1  237.38 -1041.6  227.92
    2019  223.25  2313.6   222.8    2511  222.09  2671.1  223.01  3106.9  221.83
  3497.7  222.47  3692.5  222.79  3892.4  219.99  4154.8  222.45  4880.5  223.43
  4970.3  218.91  5091.4  223.81  5280.8   219.5    5481  224.58  5524.7  219.89
  5651.2  228.42  5941.5  231.45  6478.7  221.17  6754.1  221.64  6885.3  222.89
  7252.8   225.7    7513  249.49  8231.7   267.6    8332  269.46  8359.8  269.98
#Mann= 20 ,-1 , 0
 -3812.4     .05       0 -2126.8     .16       0 -1041.6     .05       0
    2019      .1       0  2313.6     .12       0    2511     .07       0
  2671.1     .07       0  3106.9     .05       0  3497.7     .12       0
  3692.5     .07       0  3892.4     .12       0  4154.8     .12       0
  4880.5     .07       0  5091.4     .12       0  5524.7     .16       0
  6478.7     .12       0  6754.1     .05       0  6885.3     .16       0
  8231.7     .05       0    8332     .16       0
Bank Sta=4880.5,5091.4
XS Rating Curve= 0 ,0
Exp/Cntr=0.3,0.1

Type RM Length L Ch R = 1 ,319788  ,3740,3740,3740
BEGIN DESCRIPTION:
NAVASOTA RIVER 412
END DESCRIPTION:
XS GIS Cut Line= 3
      3609135.88     10274946.66      3601238.89     10274288.18
       3594680.1     10273913.13
#Sta/Elev= 30
 -2924.4  278.45 -1666.3   237.8 -1119.2  229.46    1509  221.12  1621.1  223.09
  1982.1  221.45  2279.7  222.03  2427.6  221.88  2989.9  221.88  3243.2   222.3
  3341.9  222.06  3388.3  221.95  4916.5  224.89  5029.3  219.24    5117  228.35
  5202.1  216.89  5407.4  223.17  5607.8  221.66  5637.6  215.05    5738  224.59
  5858.2  217.87  6219.7  225.35  6745.3  225.52    6902  225.12    7883   224.6
  8478.8  225.75   10015  231.78 10516.3  248.65   11399  275.43 11569.5  276.56
#Mann= 19 ,-1 , 0
 -2924.4     .05       0    1509     .07       0  1621.1     .05       0
  1982.1     .12       0  2279.7     .05       0  2427.6     .12       0
  2989.9     .07       0  3243.2     .12       0  3341.9     .07       0
  3388.3     .12       0  4916.5     .07       0    5117     .12       0
  6219.7     .16       0  6745.3     .12       0    6902     .16       0
    7883     .12       0  8478.8     .16       0 10516.3     .05       0
   11399     .16       0
#XS Ineff= 2 , 0
       0    1605  223.25               0
Permanent Ineff=
       F       F
Bank Sta=4916.5,5117
XS Rating Curve= 0 ,0
Exp/Cntr=0.3,0.1

Type RM Length L Ch R = 1 ,316048  ,2924,2924,2924
BEGIN DESCRIPTION:
NAVASOTA RIVER 430
END DESCRIPTION:
XS GIS Cut Line= 3
      3609900.08      10274757.1      3603313.98     10272974.81
      3594085.84     10272295.52
#Sta/Elev= 30
   -1823  283.32 -1369.3  268.78 -1255.3  258.85  -830.8  256.11   -19.7  224.68
    3148   221.8  3306.2  221.77  3610.8  223.06  4160.2  226.92  4960.5  227.01
  4989.7  218.38  5790.7  223.57    6546  224.17  6605.4  216.63  6796.7  223.89
  7448.5  223.26  7508.4  214.72    7639  222.96  7932.8  224.72  8937.3  225.27
 10006.1  226.13 10317.6  226.25 10495.4  225.94 11190.9  225.09 11469.7  224.09
 11783.3  223.83   13363  228.49 13494.8  231.08 13941.5  269.65 14253.1   276.1
#Mann= 19 ,-1 , 0
   -1823     .05       0    3148     .12       0  3306.2     .05       0
  3610.8     .16       0  4160.2     .12       0  4960.5     .05       0
  4960.5     .07       0  5790.7     .12       0  7932.8     .12       0
  7932.8     .16       0  8937.3     .07       0 10006.1     .05       0
 10317.6     .07       0 10495.4     .05       0 11190.9     .16       0
 11469.7     .12       0 11783.3     .05       0   13363     .16       0
 13941.5     .05       0
Bank Sta=4960.5,5790.7
XS Rating Curve= 0 ,0
Exp/Cntr=0.3,0.1

Type RM Length L Ch R = 1 ,313124  ,2255,2255,2255
BEGIN DESCRIPTION:
NAVASOTA RIVER 431
END DESCRIPTION:
XS GIS Cut Line= 4
      3610886.09     10272468.47       3604220.9     10271201.16
      3594221.94     10269226.04      3593221.91     10268121.85
#Sta/Elev= 30
 -1784.6  279.88 -1613.4  280.08   -1068  236.75  -919.3  231.96  -439.2  220.82
   141.2  220.07   269.3  219.84    1626  221.39  1812.7  222.79  2356.4  223.07
    3105  223.17    3361   222.6    3549  224.96  3888.6  227.92  4632.3  228.61
  4996.8  217.74  5746.9  223.81  5916.2  218.67  5946.7  223.89  8444.1   221.9
  8536.4  211.97  8576.6  220.35 10601.2  221.14 10711.6  221.41 11529.1  220.13
 15460.8  235.22 15874.6  274.07 16059.5  272.48 16196.9  272.35 16681.9   275.7
#Mann= 20 ,-1 , 0
 -1784.6     .05       0   141.2     .07       0   269.3     .05       0
    1626     .16       0  1812.7     .05       0  2356.4     .16       0
    3105     .05       0    3361     .16       0    3549     .12       0
  3888.6     .16       0  4632.3     .07       0  5946.7     .12       0
  8444.1     .07       0  8576.6     .12       0 10601.2     .07       0
 10711.6     .12       0 11529.1     .05       0 15460.8     .05       0
 16059.5     .08       0 16196.9     .05       0
#XS Ineff= 2 , 0
       0                    8434       0  222.31
Permanent Ineff=
       F       F
Bank Sta=4632.3,5946.7
XS Rating Curve= 0 ,0
Exp/Cntr=0.3,0.1

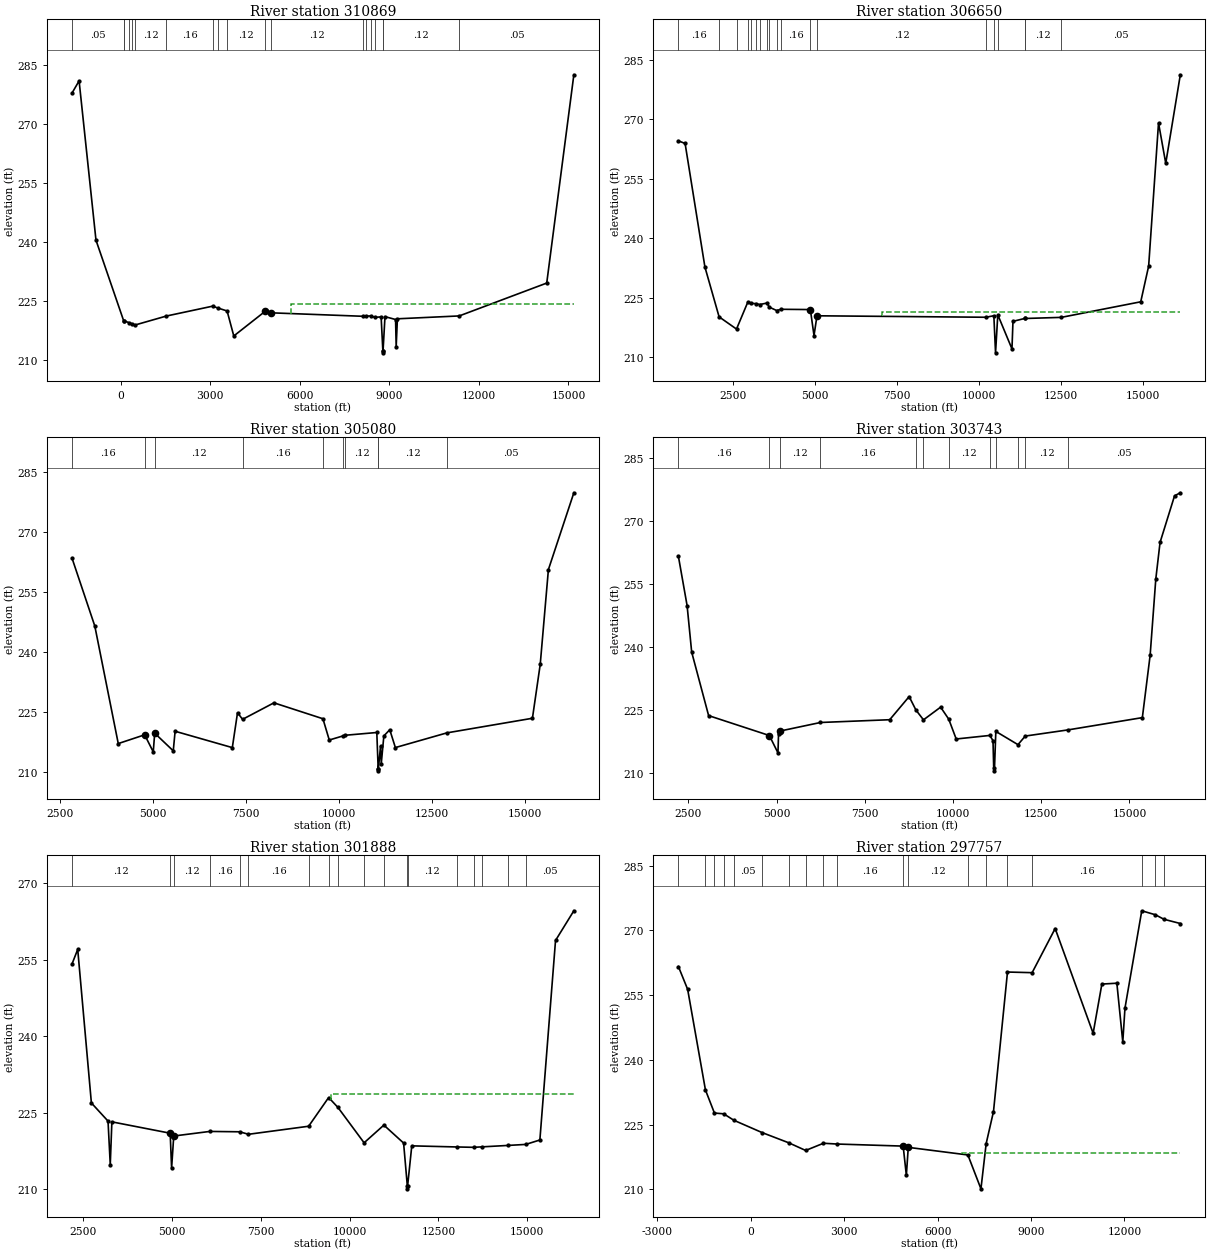
Type RM Length L Ch R = 1 ,310869  ,4219,4219,4219
BEGIN DESCRIPTION:
NAVASOTA RIVER 432
END DESCRIPTION:
XS GIS Cut Line= 3
      3610715.09     10271485.83      3604266.23      10269950.5
      3594220.22     10268299.32
#Sta/Elev= 30
 -1629.1  277.89 -1389.6  281.02  -824.2  240.49   101.8  220.01   114.2  219.98
   287.9  219.49   388.4  219.21     489  218.92  1532.4  221.19  3079.9   223.7
  3256.1  223.24  3567.3  222.48  3791.3  216.12  4839.3  222.38  5044.7  222.01
  8113.3  221.13  8235.7  221.17  8395.1  221.22  8513.8  220.84  8725.9  220.99
  8784.1  212.33  8786.9  211.83  8790.1  212.33  8855.2  221.04  9209.9  220.31
  9230.1  213.42  9270.7  220.49   11342  221.22 14272.2  229.58 15180.8  282.57
#Mann= 19 ,-1 , 0
 -1629.1     .05       0   101.8     .07       0   114.2     .05       0
   287.9     .12       0   388.4     .05       0     489     .12       0
  1532.4     .16       0  3079.9     .12       0  3256.1     .16       0
  3567.3     .12       0  4839.3     .07       0  5044.7     .12       0
  8113.3     .07       0  8235.7     .12       0  8395.1     .07       0
  8513.8     .12       0  8784.1     .07       0  8790.1     .12       0
   11342     .05       0
#XS Ineff= 2 , 0
       0                  5723.7       0  224.27
Permanent Ineff=
       F       F
Bank Sta=4839.3,5044.7
XS Rating Curve= 0 ,0
Exp/Cntr=0.3,0.1

Type RM Length L Ch R = 1 ,306650  ,1570,1570,1570
BEGIN DESCRIPTION:
NAVASOTA RIVER 433
END DESCRIPTION:
XS GIS Cut Line= 3
      3609633.47     10269667.25       3605525.1     10268995.66
      3594430.32     10267945.16
#Sta/Elev= 30
   837.1   264.6  1041.1  263.93  1645.4  232.75  2078.1  220.18  2608.9   217.1
  2957.7  223.99  3062.7  223.58  3212.3  223.51  3315.3  223.29  3547.7  223.68
  3598.6  222.68  3831.5  221.78  3969.6  222.09  4861.2  222.02  4972.6  215.47
  5063.3  220.45 10216.1  220.08 10457.3  220.46   10509   211.1 10577.8   220.7
 11009.8   212.1 11040.7  219.05 11407.4  219.79 11415.6  219.77 12513.7  220.05
 14937.2  223.98 15178.6  233.01 15479.7  269.11   15700  258.93 16144.4  281.27
#Mann= 19 ,-1 , 0
   837.1     .16       0  2078.1     .12       0  2608.9     .16       0
  2957.7     .12       0  3062.7     .05       0  3212.3      .1       0
  3315.3     .05       0  3547.7     .16       0  3598.6     .05       0
  3831.5      .1       0  3969.6     .16       0  4861.2     .07       0
  5063.3     .12       0 10216.1     .07       0 10457.3     .07       0
 10577.8     .12       0 11407.4     .05       0 11415.6     .12       0
 12513.7     .05       0
#XS Ineff= 2 , 0
       0                    7032       0  221.32
Permanent Ineff=
       F       F
Bank Sta=4861.2,5063.3
XS Rating Curve= 0 ,0
Exp/Cntr=0.3,0.1

Type RM Length L Ch R = 1 ,305080  ,1337,1337,1337
BEGIN DESCRIPTION:
NAVASOTA RIVER 434
END DESCRIPTION:
XS GIS Cut Line= 3
      3607947.71     10267869.12      3605764.06     10267966.13
      3594436.86     10267860.44
#Sta/Elev= 30
  2814.2  263.49  3429.9  246.45    4061  217.06  4771.7  219.25  5003.5  214.98
    5042  219.66    5542  215.24    5592  220.14    7132  216.05  7272.1  224.78
  7408.1  223.12  8252.1  227.25  9571.5  223.27  9742.2  217.95 10113.6  218.98
 10162.6  219.13 11022.2  219.83 11059.2  210.74   11062  210.24 11065.2  210.74
 11122.2  216.38 11142.2  212.04 11212.2  218.98 11371.4  220.52 11522.2  216.06
 12910.9  219.74 15212.4  223.39 15422.4  236.87 15642.4  260.58 16327.7  279.79
#Mann= 10 ,-1 , 0
  2814.2     .16       0  4771.7     .07       0    5042     .12       0
  7408.1     .16       0  9571.5     .12       0 10113.6     .07       0
 10162.6     .12       0 11059.2     .07       0 11065.2     .12       0
 12910.9     .05       0
#XS Ineff= 2 , 0
       0                  8252.1       0  227.25
Permanent Ineff=
       F       F
Bank Sta=4771.7,5042
XS Rating Curve= 0 ,0
Exp/Cntr=0.3,0.1

Type RM Length L Ch R = 1 ,303743  ,1855,1855,1855
BEGIN DESCRIPTION:
NAVASOTA RIVER 435
END DESCRIPTION:
XS GIS Cut Line= 3
      3608608.07     10266929.01      3605829.08     10266953.66
      3594419.28     10267785.78
#Sta/Elev= 30
  2220.9  261.58  2466.9  249.85  2596.9  238.74  3076.6  223.59    4797  218.84
  5041.5  214.69  5057.1  219.14  5107.3  219.92  6245.7  221.95  8206.8  222.61
  8757.5  228.13    8950  224.92  9163.7  222.58  9649.3  225.61  9879.7  222.74
 10090.5  218.01   11043  218.86 11133.2  217.61 11153.3  211.12 11173.1  210.41
 11213.4  219.82 11840.5  216.66 12047.2  218.71 13257.8  220.18 15364.4  223.11
   15585  237.98 15745.4   256.2 15865.8  264.92 16276.8  276.05 16440.1  276.77
#Mann= 12 ,-1 , 0
  2220.9     .16       0    4797     .07       0  5107.3     .12       0
  6245.7     .16       0    8950     .05       0  9163.7     .16       0
  9879.7     .12       0   11043     .07       0 11213.4     .12       0
 11840.5     .05       0 12047.2     .12       0 13257.8     .05       0
#XS Ineff= 2 , 0
       0                  8757.5       0  228.13
Permanent Ineff=
       F       F
Bank Sta=4797,5107.3
XS Rating Curve= 0 ,0
Exp/Cntr=0.3,0.1

Type RM Length L Ch R = 1 ,301888  ,4131,4131,4131
BEGIN DESCRIPTION:
NAVASOTA RIVER 201
END DESCRIPTION:
XS GIS Cut Line= 3
      3608784.46     10266767.72      3606513.61     10265871.88
      3594847.07     10266330.21
#Sta/Elev= 30
  2191.7  254.14  2354.1  257.04  2738.4  226.89  3206.5  223.33  3269.2  214.79
  3314.7  223.18  4954.6  220.95  4994.6  214.09  5054.7   220.4  6068.5   221.3
  6909.1  221.23  7157.2  220.74  8848.7  222.32  9411.8  227.96  9674.4     226
 10408.8  219.07   10965  222.54 11519.7  219.02 11625.5  210.53 11628.3  210.03
 11631.5  210.53 11749.9  218.47 13026.5  218.25 13486.2  218.18 13721.1  218.27
 14450.8  218.55 14954.4  218.75 15352.6  219.62   15793  258.79 16308.4  264.62
#Mann= 18 ,-1 , 0
  2191.7     .12       0  4954.6     .07       0  5054.7     .12       0
  6068.5     .16       0  6909.1     .05       0  7157.2     .16       0
  8848.7     .05       0  9411.8     .16       0  9674.4     .12       0
 10408.8     .12       0   10965     .12       0 11625.5     .07       0
 11631.5     .12       0 13026.5     .05       0 13486.2     .05       0
 13721.1     .07       0 14450.8     .07       0 14954.4     .05       0
#XS Ineff= 2 , 0
       0  3314.7  223.18  9468.1       0  228.62
Permanent Ineff=
       F       F
Bank Sta=4954.6,5054.7
XS Rating Curve= 0 ,0
Exp/Cntr=0.3,0.1

Type RM Length L Ch R = 1 ,297757  ,4140,4140,4140
BEGIN DESCRIPTION:
NAVASOTA RIVER 202
END DESCRIPTION:
XS GIS Cut Line= 3
      3611221.95     10265351.05      3599659.44     10262830.21
      3595388.63     10263101.04
#Sta/Elev= 30
 -2320.5   261.6 -2023.8  256.31 -1452.8  233.01 -1164.7  227.66  -866.4  227.48
    -541  225.99   360.9  223.15  1223.7  220.76  1764.7  218.99  2335.6  220.66
  2772.3  220.48  4894.9     220  4997.3  213.23  5058.7  219.71  6972.6  217.95
    7392   210.1  7559.9  220.59    7795  228.01  8244.3  260.33  9035.5  260.18
  9774.9  270.41 10993.9  246.14 11274.5  257.54 11755.4  257.74 11945.8  244.13
   12016  251.97   12555  274.52 12994.5  273.59 13267.7  272.55   13793  271.57
#Mann= 19 ,-1 , 0
 -2320.5     .05       0 -1452.8     .16       0 -1164.7     .12       0
  -866.4     .05       0    -541     .05       0   360.9     .05       0
  1223.7     .16       0  1764.7     .12       0  2335.6     .16       0
  2772.3     .16       0  4894.9     .07       0  5058.7     .12       0
  6972.6     .07       0  7559.9     .05       0  8244.3     .05       0
  9035.5     .16       0   12555     .05       0 12994.5     .16       0
 13267.7     .05       0
#XS Ineff= 2 , 0
       0                  6767.9       0   218.3
Permanent Ineff=
       F       F
Bank Sta=4894.9,5058.7
XS Rating Curve= 0 ,0
Exp/Cntr=0.3,0.1

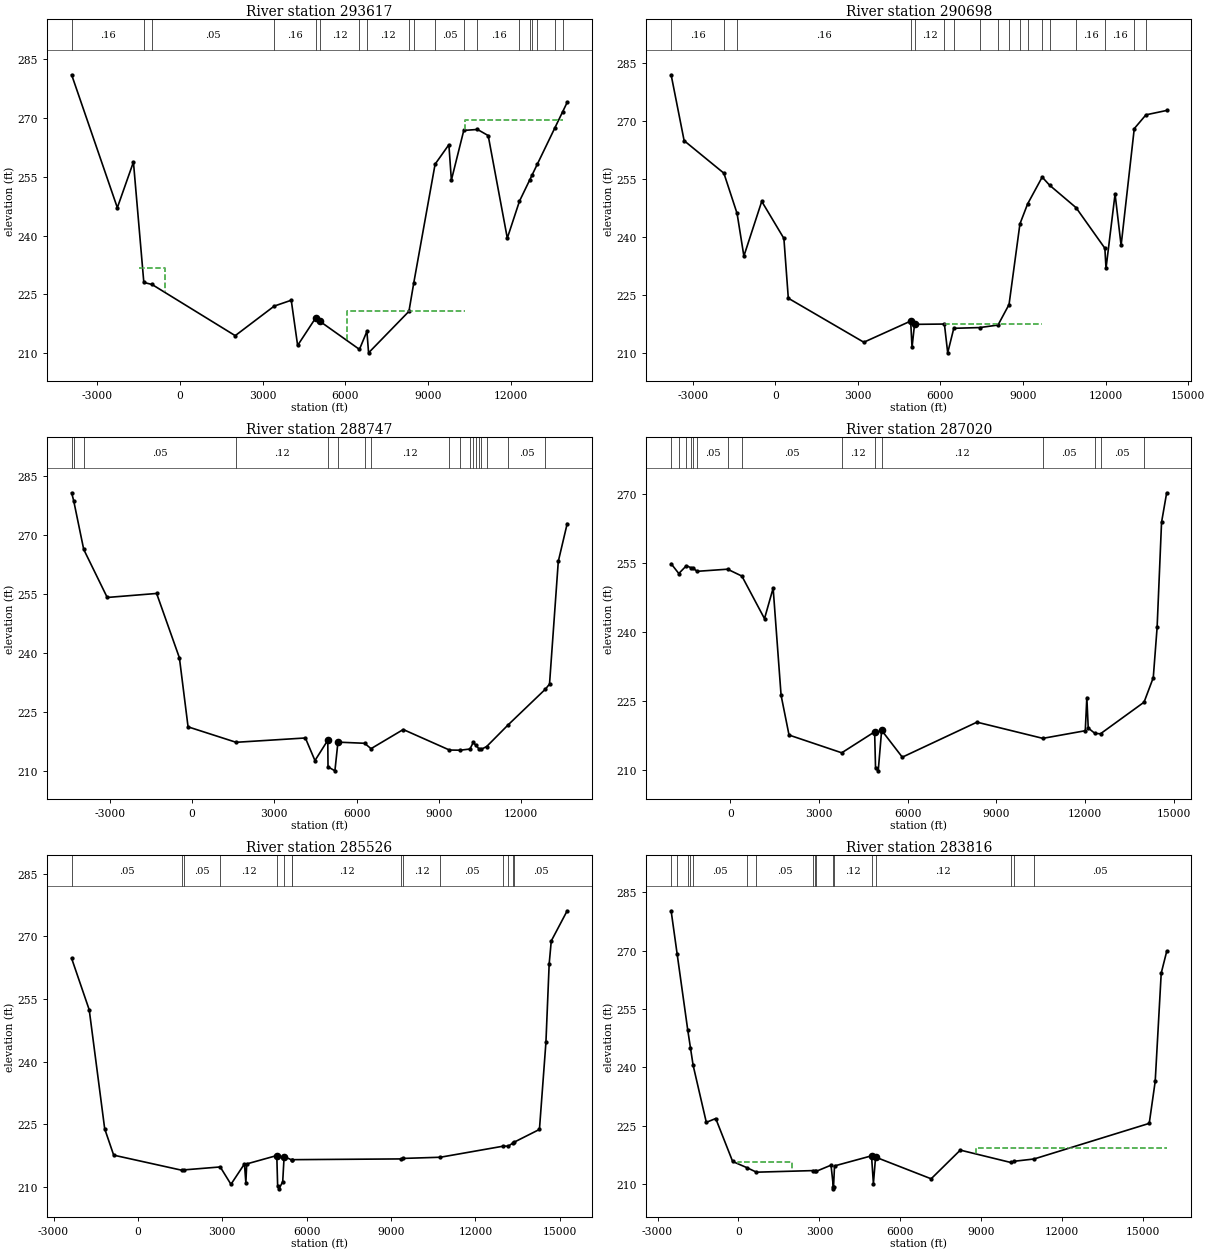
Type RM Length L Ch R = 1 ,293617  ,2919,2919,2919
BEGIN DESCRIPTION:
NAVASOTA RIVER 436
END DESCRIPTION:
XS GIS Cut Line= 4
      3613890.08     10261558.36      3605243.14      10262300.9
      3604435.85     10261949.33       3596079.5     10262480.61
#Sta/Elev= 30
   -3908     281   -2254  247.11 -1671.8  258.75 -1295.4  228.05 -1001.5  227.55
  2011.7  214.49  3423.8  222.03  4039.1  223.52    4270     212  4930.9   219.1
  5076.9  218.14  6506.8  210.99  6777.3  215.58  6837.2  210.11  8298.1  220.69
  8474.3  228.01  9244.6  258.21  9743.3  263.18  9833.5  254.14 10281.9  266.81
 10777.4  267.06 11166.1   265.5 11857.5  239.35 12297.8  248.78 12662.5   254.1
 12761.7  255.55 12947.3  258.26 13576.8  267.44 13863.9  271.63 14024.5  273.97
#Mann= 19 ,-1 , 0
   -3908     .16       0 -1295.4     .12       0 -1001.5     .05       0
  3423.8     .16       0  4930.9     .07       0  5076.9     .12       0
  6506.8     .07       0  6777.3     .12       0  8298.1     .05       0
  8474.3     .16       0  9244.6     .05       0 10281.9     .05       0
 10777.4     .16       0 12297.8     .05       0 12662.5     .05       0
 12761.7     .16       0 12947.3     .05       0 13576.8     .16       0
 13863.9     .16       0
#XS Ineff= 5 ,-1
   -3908 -1671.8  258.75  -540.6  4039.1  223.52 -1474.8  -540.6  231.62
  6045.8 10344.5  220.71 10344.5 13863.9  269.36
Permanent Ineff=
       F       F       F       F       F
Bank Sta=4930.9,5076.9
XS Rating Curve= 0 ,0
Exp/Cntr=0.3,0.1

Type RM Length L Ch R = 1 ,290698  ,1951,1951,1951
BEGIN DESCRIPTION:
NAVASOTA RIVER 437
END DESCRIPTION:
XS GIS Cut Line= 3
      3613874.48      10261459.4      3605099.64     10261051.93
      3595921.35     10261899.05
#Sta/Elev= 30
 -3784.3  281.83 -3311.4   264.8 -1867.5   256.4   -1388  245.99   -1141  234.98
  -492.3  249.12   312.5  239.54   472.7  224.09  3215.6  212.72  4917.4  218.19
  4967.5  211.38  5057.8  217.34  6143.4  217.42  6262.6  209.98  6483.8  216.32
  7427.1  216.51  8090.2  217.16  8491.3  222.47  8886.3  243.29  9165.6  248.46
  9694.9  255.39  9963.6   253.3 10924.6   247.5 11971.6  237.01 12013.6  231.81
 12342.5  251.03 12561.8  237.72 13039.7  267.92 13464.5  271.48 14217.3  272.61
#Mann= 18 ,-1 , 0
 -3784.3     .16       0 -1867.5     .05       0   -1388     .16       0
  4917.4     .07       0  5057.8     .12       0  6143.4     .07       0
  6483.8     .12       0  7427.1     .05       0  8090.2     .12       0
  8491.3     .16       0  8886.3     .05       0  9165.6     .05       0
  9694.9     .16       0  9963.6     .05       0 10924.6     .16       0
 11971.6     .16       0 13039.7      .1       0 13464.5     .16       0
#XS Ineff= 3 ,-1
 -1789.8  -492.3  249.12  6132.3  9694.9  217.44  9694.9 13099.9  255.39
Permanent Ineff=
       F       F       F
Bank Sta=4917.4,5057.8
XS Rating Curve= 0 ,0
Exp/Cntr=0.3,0.1

Type RM Length L Ch R = 1 ,288747  ,1727,1727,1727
BEGIN DESCRIPTION:
NAVASOTA RIVER 438
END DESCRIPTION:
XS GIS Cut Line= 3
       3613876.2      10261339.1      3604565.26     10260162.34
      3595887.94     10259913.32
#Sta/Elev= 30
   -4385  280.71 -4309.9  278.68 -3944.3   266.3 -3087.5  254.08 -1286.5   255.1
  -456.2  238.73  -140.5  221.17  1610.7  217.24  4136.3  218.34  4485.6  212.59
  4952.8  217.76  4961.8     211    5213  209.98  5323.3  217.28    6297  216.99
  6529.5  215.62  7704.3  220.49    9389  215.27  9785.2  215.23 10136.1  215.53
 10257.7  217.22 10356.4  216.44   10455  215.65 10553.7  215.48 10744.7  216.16
 11519.8  221.62   12884  230.74 13036.5  232.05 13356.6  263.26 13680.9  272.86
#Mann= 18 ,-1 , 0
   -4385     .05       0 -4309.9     .16       0 -3944.3     .05       0
  1610.7     .12       0  4952.8     .07       0  5323.3     .12       0
    6297     .07       0  6529.5     .12       0    9389     .07       0
  9785.2     .12       0 10136.1     .05       0 10257.7     .07       0
 10356.4     .12       0   10455     .07       0 10553.7     .12       0
 10744.7     .16       0 11519.8     .05       0   12884     .16       0
#XS Ineff= 2 , 0
       0                  7704.3       0  220.49
Permanent Ineff=
       F       F
Bank Sta=4952.8,5323.3
XS Rating Curve= 0 ,0
Exp/Cntr=0.3,0.1

Type RM Length L Ch R = 1 ,287020  ,1494,1494,1494
BEGIN DESCRIPTION:
NAVASOTA RIVER 203
END DESCRIPTION:
XS GIS Cut Line= 3
      3612409.47     10260830.22      3605284.44     10258934.38
      3595888.56     10259288.55
#Sta/Elev= 30
 -2008.3   254.8 -1748.4  252.67 -1491.1  254.37 -1325.9   253.9 -1267.6  253.81
   -1124  253.15   -98.5  253.61   387.2  252.11    1153  242.86  1445.2  249.49
  1714.2   226.2  1983.3  217.56  3767.3   213.7  4880.7  218.26  4911.8  210.38
  5002.5  209.78    5118  218.59  5817.3  212.75  8344.6  220.36   10574  216.84
 12011.7   218.5 12064.3  225.72 12111.8  219.08 12339.5  217.91 12527.2  217.84
   14001   224.7 14313.3  230.03 14443.4  240.96 14593.5   263.8 14767.2  270.22
#Mann= 15 ,-1 , 0
 -2008.3     .16       0 -1748.4     .05       0 -1491.1     .16       0
 -1325.9      .1       0 -1267.6     .16       0   -1124     .05       0
   -98.5     .16       0   387.2     .05       0  3767.3     .12       0
  4880.7     .07       0    5118     .12       0   10574     .05       0
 12339.5     .16       0 12527.2     .05       0   14001     .16       0
Bank Sta=4880.7,5118
XS Rating Curve= 0 ,0
Exp/Cntr=0.3,0.1

Type RM Length L Ch R = 1 ,285526  ,1710,1710,1710
BEGIN DESCRIPTION:
NAVASOTA RIVER 439
END DESCRIPTION:
XS GIS Cut Line= 3
      3612967.69     10257949.65      3605610.71      10258017.8
      3595356.37      10258496.5
#Sta/Elev= 30
 -2357.3  264.71 -1731.7   252.4 -1181.7  223.93  -861.7  217.62  1561.4  214.01
  1649.3   214.1  2927.5   214.8  3308.5  210.64  3788.5  215.53  3838.6     211
  3868.6  215.52  4938.6  217.53  4968.6  210.28  5018.4  209.56  5148.8  211.27
  5198.8  217.28  5470.1  216.48  5494.4  216.54  9351.7  216.72  9430.8  216.84
 10753.4  217.12 12998.5  219.78 13170.4  219.77 13349.5   220.6 13374.4  220.71
 14278.7  223.78 14508.9  244.58 14624.7  263.38 14699.2  268.88 15265.5   276.1
#Mann= 15 ,-1 , 0
 -2357.3     .05       0  1561.4     .16       0  1649.3     .05       0
  2927.5     .12       0  4938.6     .07       0  5198.8     .12       0
  5470.1     .07       0  5494.4     .12       0  9351.7     .07       0
  9430.8     .12       0 10753.4     .05       0 12998.5     .16       0
 13170.4     .05       0 13349.5     .16       0 13374.4     .05       0
Bank Sta=4938.6,5198.8
XS Rating Curve= 0 ,0
Exp/Cntr=0.3,0.1

Type RM Length L Ch R = 1 ,283816  ,1624,1624,1624
BEGIN DESCRIPTION:
NAVASOTA RIVER 440
END DESCRIPTION:
XS GIS Cut Line= 4
      3614174.41     10256736.85      3606682.32     10256966.15
      3606138.61     10256976.04      3596095.38     10254587.72
#Sta/Elev= 30
 -2495.6  280.23 -2274.2  269.22 -1878.6  249.55 -1779.7  245.05 -1680.7  240.55
 -1191.3  225.87  -842.5  226.86  -215.7  215.82   318.8  214.21   666.6  213.07
  2770.1  213.48  2842.1  213.32  2869.9  213.26  3429.5  214.87  3516.5  209.29
  3519.3  208.79  3522.5  209.29  3559.5  214.68  4930.2  217.27    5000  210.13
  5080.2  216.94  7139.5  211.37  8219.5  218.74 10085.9  215.57 10222.7  215.88
 10952.6  216.46 15220.6  225.61 15441.7  236.39 15664.9  264.21 15867.1  269.77
#Mann= 17 ,-1 , 0
 -2495.6     .05       0 -2274.2     .08       0 -1878.6     .05       0
 -1779.7     .08       0 -1680.7     .05       0   318.8     .07       0
   666.6     .05       0  2770.1     .08       0  2842.1     .05       0
  2869.9     .12       0  3516.5     .07       0  3522.5     .12       0
  4930.2     .07       0  5080.2     .12       0 10085.9     .07       0
 10222.7     .12       0 10952.6     .05       0
#XS Ineff= 2 , 0
       0  1998.8  215.58  8783.1       0  219.39
Permanent Ineff=
       F       F
Bank Sta=4930.2,5080.2
XS Rating Curve= 0 ,0
Exp/Cntr=0.3,0.1

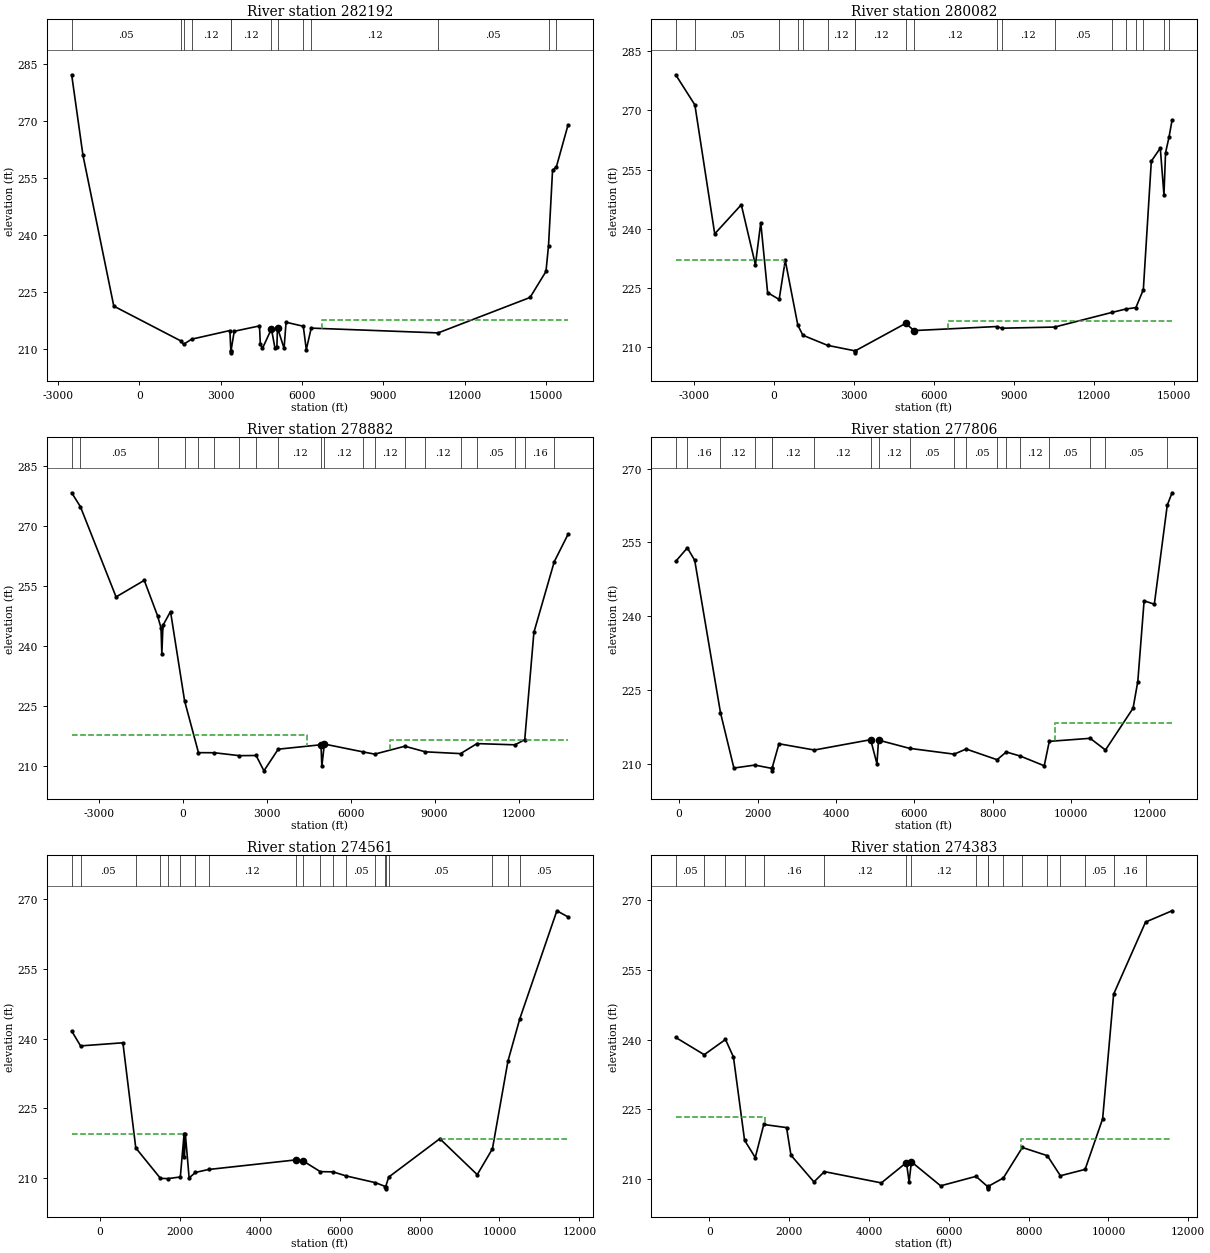
Type RM Length L Ch R = 1 ,282192  ,2110,2110,2110
BEGIN DESCRIPTION:
NAVASOTA RIVER 441
END DESCRIPTION:
XS GIS Cut Line= 3
      3614241.88     10256386.38      3606933.03     10255863.11
      3596077.65     10254217.24
#Sta/Elev= 30
 -2494.5   282.1 -2078.4  260.92  -940.8  221.19  1531.5  212.03  1630.2  211.14
  1933.1  212.49  3340.2  214.76  3376.3  209.39    3379  208.89  3382.3  209.39
  3500.6  214.57    4433  215.98    4463  211.28  4543.2  210.07  4872.8   215.2
  5005.3  210.05    5074  210.46    5097  215.53  5338.9  210.04  5412.7  216.95
  6047.7  215.89    6159  209.75  6339.9   215.4 11021.6  214.14 14411.4  223.47
 14998.9  230.32   15093  237.15 15241.6  256.94 15383.5  257.88 15812.5  268.89
#Mann= 13 ,-1 , 0
 -2494.5     .05       0  1531.5      .1       0  1630.2     .07       0
  1933.1     .12       0  3376.3     .07       0  3382.3     .12       0
  4872.8     .07       0    5097     .12       0  6047.7     .07       0
  6339.9     .12       0 11021.6     .05       0   15093     .16       0
 15383.5     .05       0
#XS Ineff= 2 , 0
       0    4433  215.98  6742.3       0  217.66
Permanent Ineff=
       F       F
Bank Sta=4872.8,5097
XS Rating Curve= 0 ,0
Exp/Cntr=0.3,0.1

Type RM Length L Ch R = 1 ,280082  ,1200,1200,1200
BEGIN DESCRIPTION:
NAVASOTA RIVER 442
END DESCRIPTION:
XS GIS Cut Line= 5
      3615646.79     10254555.17      3611310.89     10254292.58
      3606977.46     10254659.73      3600888.61     10254580.21
      3597576.62     10252643.01
#Sta/Elev= 30
 -3692.8  279.04 -2973.9  271.41 -2229.4  238.75 -1232.2  246.12  -702.6  230.91
  -502.3  241.58    -245  223.86   187.6  222.13   416.4  232.02   888.5  215.61
  1076.9  213.07  2002.7  210.51  3035.4  209.11  3038.1  208.61  3041.4  209.11
  4935.1  216.08  5245.4  214.25  8343.2  215.27  8549.3  214.85 10520.7  215.14
 12666.1  218.84   13195  219.71 13569.8  220.07 13848.5  224.61 14148.1  257.16
 14484.4  260.47 14621.9   248.6 14681.9   259.3 14810.3  263.19 14926.3  267.55
#Mann= 19 ,-1 , 0
 -3692.8     .05       0 -2973.9     .05       0   187.6     .16       0
   888.5     .05       0  1076.9     .12       0  2002.7     .12       0
  3035.4     .07       0  3041.4     .12       0  4935.1     .05       0
  5245.4     .12       0  8343.2     .07       0  8549.3     .12       0
 10520.7     .05       0 12666.1     .08       0   13195     .05       0
 13569.8     .16       0 13848.5     .05       0 14621.9     .05       0
 14810.3     .16       0
#XS Ineff= 2 , 0
          380.39  232.15 6531.27           216.6
Permanent Ineff=
       F       F
Bank Sta=4935.1,5245.4
XS Rating Curve= 0 ,0
Exp/Cntr=0.3,0.1

Type RM Length L Ch R = 1 ,278882  ,1076,1076,1076
BEGIN DESCRIPTION:
NAVASOTA RIVER 443
END DESCRIPTION:
XS GIS Cut Line= 5
      3615652.22     10254522.83      3613224.65     10253616.33
      3606839.87     10253690.11      3601013.61     10253371.88
       3598388.6     10252059.37
#Sta/Elev= 30
 -3976.5  278.29 -3664.9  274.82 -2388.9  252.22 -1381.4  256.37  -905.5   247.5
  -782.6  244.46  -752.6  237.93  -712.6  245.09  -442.6  248.57    59.5  226.24
   556.6  213.24  1122.2  213.22  2018.4  212.49  2617.6  212.53  2897.4  208.69
  3407.7  214.11  4937.8  215.22  4967.8  209.81  5057.9  215.39  6455.3  213.41
  6857.6  212.87  7935.4  214.85  8667.8  213.45  9926.8     213 10515.2  215.51
   11876   215.2   12222   216.5 12549.4  243.35 13276.5  261.03 13769.8  267.89
#Mann= 20 ,-1 , 0
 -3976.5     .05       0 -3664.9     .05       0  -905.5     .16       0
    59.5     .12       0   556.6     .12       0  1122.2     .12       0
  2018.4     .12       0  2617.6    .033       0  3407.7     .12       0
  4937.8     .07       0  5057.9     .12       0  6455.3     .07       0
  6857.6     .12       0  7935.4     .12       0  8667.8     .12       0
  9926.8     .12       0 10515.2     .05       0   11876     .05       0
   12222     .16       0 13276.5     .05       0
#XS Ineff= 2 , 0
         4450.61  217.74 7414.28           216.5
Permanent Ineff=
       F       F
Bank Sta=4937.8,5057.9
XS Rating Curve= 0 ,0
Exp/Cntr=0.3,0.1

Type RM Length L Ch R = 1 ,277806  ,3245,3245,3245
BEGIN DESCRIPTION:
NAVASOTA RIVER 204
END DESCRIPTION:
XS GIS Cut Line= 3
      3611846.95     10252559.38      3604951.11     10252663.54
      3599201.07     10252184.37
#Sta/Elev= 30
   -88.5  251.13   208.8  253.88     397  251.33  1054.5  220.36  1396.5  209.14
    1930  209.74  2363.6  209.07  2366.4  208.57  2369.6  209.07  2546.6  214.07
  3448.4   212.8  4886.9   214.9  5046.9  209.99  5086.9  214.81  5878.2  213.14
  7017.8  211.96  7322.8     213  8112.9  210.83  8347.3   212.4  8705.4  211.57
  9315.8   209.6    9445  214.56 10487.9  215.18 10878.1   212.8   11583   221.3
 11703.4  226.71 11864.6  243.12 12125.5  242.43 12454.5  262.52 12578.1  265.07
#Mann= 19 ,-1 , 0
   -88.5     .16       0   208.8     .16       0  1054.5     .12       0
    1930     .12       0  2363.6     .07       0  2369.6     .12       0
  3448.4     .12       0  4886.9     .07       0  5086.9     .12       0
  5878.2     .05       0  7017.8     .12       0  7322.8     .05       0
  8112.9     .07       0  8347.3     .12       0  8705.4     .12       0
    9445     .05       0 10487.9     .16       0 10878.1     .05       0
 12454.5     .05       0
#XS Ineff= 2 , 0
         2548.38  214.03 9586.09           218.2
Permanent Ineff=
       F       F
Bank Sta=4886.9,5086.9
XS Rating Curve= 0 ,0
Exp/Cntr=0.3,0.1

Type RM Length L Ch R = 1 ,274561  ,178,178,178
BEGIN DESCRIPTION:
NAVASOTA RIVER 428
END DESCRIPTION:
XS GIS Cut Line= 6
      3610346.34     10248565.41      3609268.45      10248865.1
      3607914.84     10249901.78      3605822.51     10250024.17
      3601495.83     10252013.11       3598912.9     10251441.96
#Sta/Elev= 30
  -704.8  241.64  -482.1  238.44   577.3  239.11   899.2   216.5  1517.5  209.95
    1704   209.9  2014.1  210.25  2108.6   219.5    2114  214.56  2139.7  219.52
  2234.5  210.05  2393.9  211.23  2720.3  211.86  4901.1  213.92  5079.6  213.74
  5517.1   211.4  5835.9  211.35  6161.9  210.48    6895  209.03  7147.9   208.2
  7150.6   207.7  7153.9   208.2  7229.6  210.23  8508.6  218.48  9444.9  210.75
  9825.5  216.31 10213.8  235.18 10508.6  244.24 11437.8   267.5 11717.2  266.18
#Mann= 20 ,-1 , 0
  -704.8     .16       0  -482.1     .05       0   899.2     .16       0
  1517.5     .05       0    1704     .12       0  2014.1     .12       0
  2393.9     .12       0  2720.3     .12       0  4901.1     .07       0
  5079.6     .12       0  5517.1     .05       0  5835.9     .12       0
  6161.9     .05       0    6895     .08       0  7147.9     .07       0
  7153.9     .07       0  7229.6     .05       0  9825.5     .05       0
 10213.8     .16       0 10508.6     .05       0
#XS Ineff= 2 , 0
         2139.59  219.52 8510.32          218.47
Permanent Ineff=
       F       F
Bank Sta=4901.1,5079.6
XS Rating Curve= 0 ,0
Exp/Cntr=0.3,0.1

Type RM Length L Ch R = 1 ,274383  ,2404,2404,2404
BEGIN DESCRIPTION:
NAVASOTA RIVER 429
END DESCRIPTION:
XS GIS Cut Line= 6
      3610321.07     10248413.01      3609196.53     10248733.19
        3607864.     10249760.46      3605739.87      10249814.1
      3601463.09     10251866.45       3598910.8     10251291.97
#Sta/Elev= 30
  -845.6  240.48    -131  236.76   401.8  240.04   601.3  236.27   880.2  218.32
  1148.2  214.59  1361.8  221.72  1932.3  221.05  2042.7   215.1  2618.8  209.34
  2880.8  211.56  4308.7  209.13  4936.9  213.52  5003.8  209.33  5061.4  213.67
  5794.4   208.5  6680.7  210.54  6969.5  208.35  6972.3  207.85  6975.5  208.35
  6981.8  208.36  7365.1  210.18  7842.1  216.76  8468.4     215  8795.5  210.67
  9414.6  212.04  9854.4  222.94 10129.8  249.81 10929.8  265.35 11594.4  267.78
#Mann= 19 ,-1 , 0
  -845.6     .05       0    -131     .05       0   401.8     .05       0
   880.2     .05       0  1361.8     .16       0  2880.8     .12       0
  4936.9     .07       0  5061.4     .12       0  6680.7     .12       0
  6969.5     .07       0  6975.5     .08       0  6981.8     .12       0
  7365.1     .05       0  7842.1     .16       0  8468.4     .05       0
  8795.5     .05       0  9414.6     .05       0 10129.8     .16       0
 10929.8     .05       0
#XS Ineff= 2 , 0
         1383.04  223.27  7800.4          218.53
Permanent Ineff=
       F       F
Bank Sta=4936.9,5061.4
XS Rating Curve= 0 ,0
Exp/Cntr=0.3,0.1