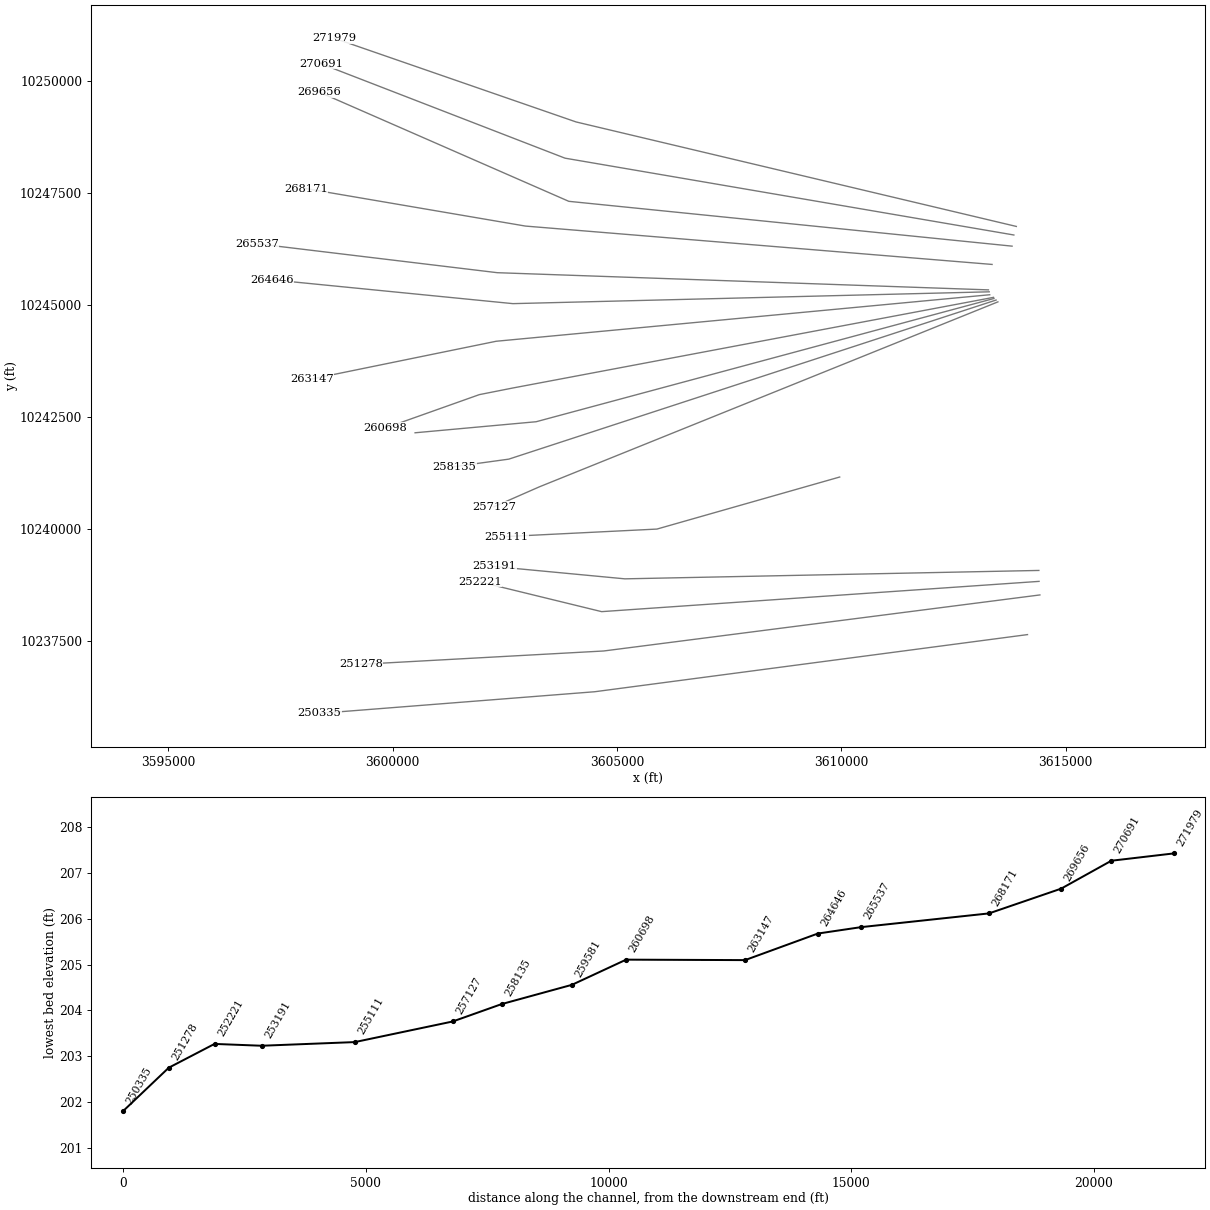
HEC-RAS study NAVASOTA RIVER.prj: NAVASOTA RIVER Base Level Engineering

--- NAVASOTA RIVER.g01 (geometry) --- (continued)

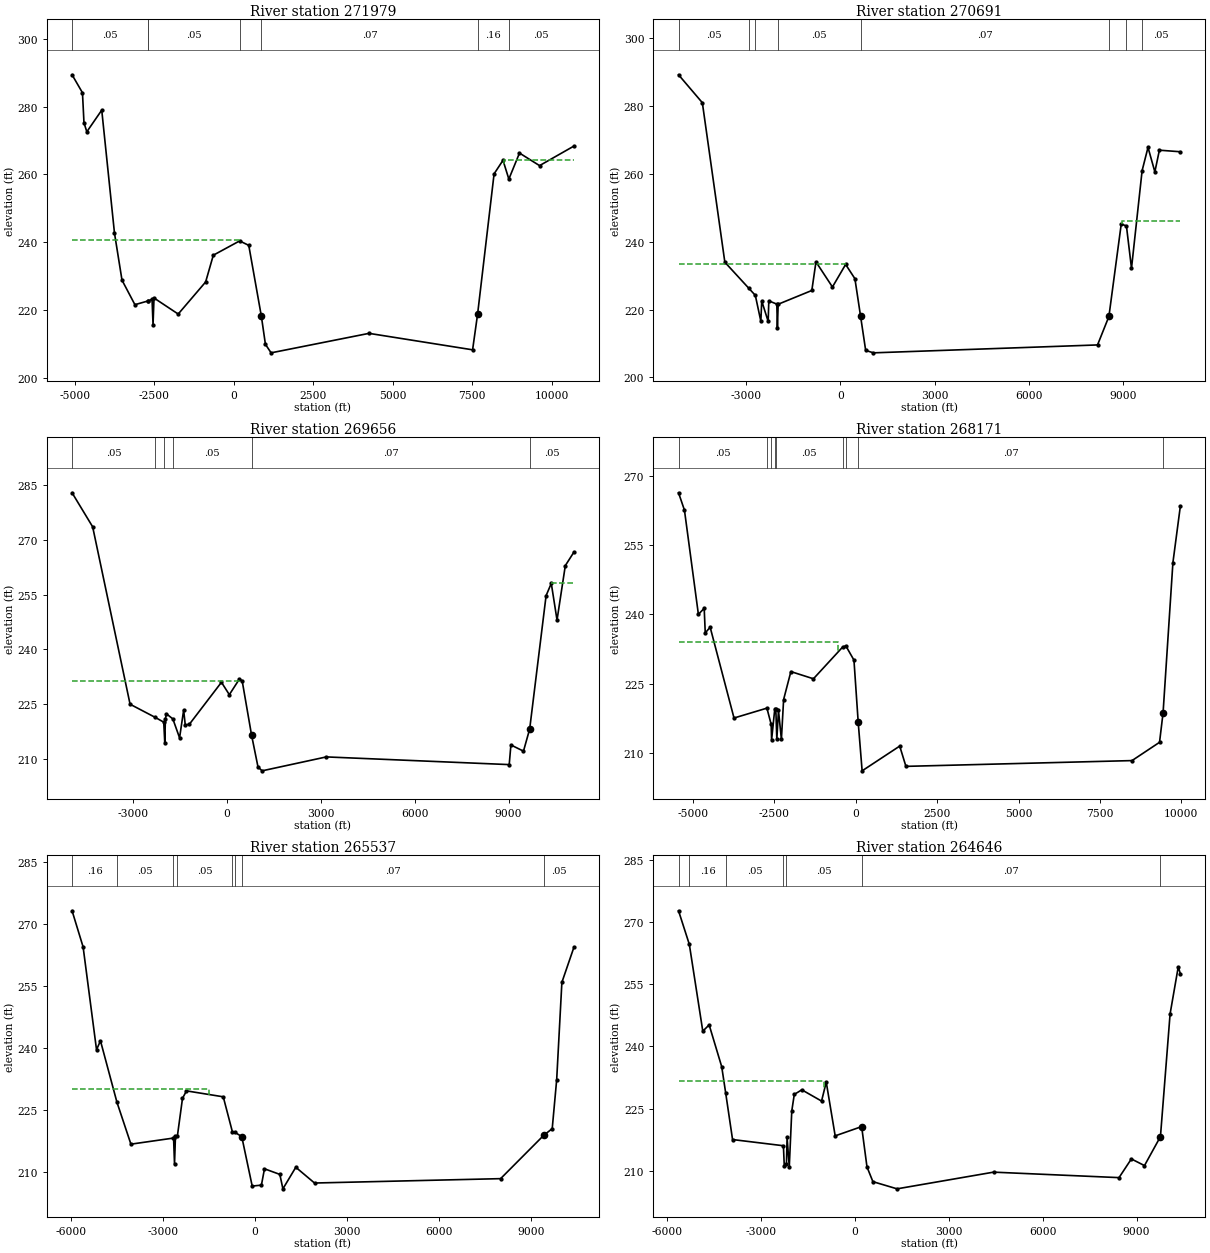
Type RM Length L Ch R = 1 ,271979  ,1288,1288,1288
BEGIN DESCRIPTION:
NAVASOTA RIVER 444
END DESCRIPTION:
XS GIS Cut Line= 3
      3613900.27     10246749.72      3604086.72     10249081.22
      3598702.18     10250946.91
#Sta/Elev= 30
 -5086.7  289.37 -4759.7  284.08   -4712  275.23 -4622.5  272.57 -4153.3  278.95
 -3752.4  242.71   -3516  228.85   -3110  221.62   -2705   222.7 -2702.8  222.67
 -2570.4  223.21 -2539.6  215.74 -2509.1  223.59 -1748.1  218.86  -884.7  228.32
  -643.6   236.2   184.2  240.41     472   239.1     869  218.17   995.5  209.95
  1174.3  207.43  4254.4  213.17  7513.1  208.32  7670.2  218.83  8189.2  260.18
  8469.5  264.17  8653.5  258.64  8988.4   266.3  9619.2   262.6 10698.6  268.35
#Mann= 7 ,-1 , 0
 -5086.7     .05       0   -2705     .16       0 -2702.8     .05       0
   184.2     .16       0     869     .07       0  7670.2     .16       0
  8653.5     .05       0
#XS Ineff= 2 , 0
          191.17  240.82 8506.88          264.15
Permanent Ineff=
       F       F
Bank Sta=869,7670.2
XS Rating Curve= 0 ,0
Exp/Cntr=0.3,0.1

Type RM Length L Ch R = 1 ,270691  ,1035,1035,1035
BEGIN DESCRIPTION:
NAVASOTA RIVER 445
END DESCRIPTION:
XS GIS Cut Line= 3
      3613845.48     10246558.73      3603839.87     10248273.01
      3598406.06     10250377.74
#Sta/Elev= 30
 -5151.4  289.27   -4393  281.03 -3676.8     234 -2912.4   226.3   -2706  224.22
 -2530.4  216.58   -2502  222.57   -2297  216.52 -2276.7   222.6 -2021.6  221.64
 -2002.8  214.67   -1979   221.6  -907.1  225.66  -775.2   234.1  -250.7  226.69
   169.6  233.34   464.8  229.14   645.2  218.08   807.6  207.99  1054.8  207.27
    8191   209.6  8553.2     218  8945.4  245.25    9111  244.69  9272.4  232.22
  9610.4  261.01  9798.2  267.86 10016.2  260.64 10160.4  267.03 10827.2  266.57
#Mann= 8 ,-1 , 0
 -5151.4     .05       0 -2912.4      .1       0   -2706     .16       0
   -1979     .05       0   645.2     .07       0  8553.2     .05       0
    9111     .16       0  9610.4     .05       0
#XS Ineff= 2 , 0
          170.69  233.35  8970.2          246.17
Permanent Ineff=
       F       F
Bank Sta=645.2,8553.2
XS Rating Curve= 0 ,0
Exp/Cntr=0.3,0.1

Type RM Length L Ch R = 1 ,269656  ,1485,1485,1485
BEGIN DESCRIPTION:
NAVASOTA RIVER 446
END DESCRIPTION:
XS GIS Cut Line= 3
      3613805.69     10246309.89      3603924.47       10247310.
      3598352.25     10249750.93
#Sta/Elev= 30
 -4931.7  282.93 -4274.8   273.6 -3080.4  224.93 -2276.9  221.32 -2005.9  220.01
 -1973.1   214.4   -1953  220.86 -1922.8  222.31 -1715.3  220.91 -1500.7  215.71
   -1370  223.34 -1319.8  219.24 -1187.2  219.44  -163.9  230.95    87.4  227.55
   401.3  231.73   496.2   231.4   795.9  216.51    1002  207.74  1132.5  206.66
  3183.6  210.48  9020.2  208.37  9074.1  213.76  9475.5  212.06  9673.4  218.14
 10197.1  254.71   10363  258.08 10546.2  248.02 10810.6  262.95 11083.4  266.63
#Mann= 6 ,-1 , 0
 -4931.7     .05       0 -2276.9     .05       0 -2005.9     .16       0
 -1715.3     .05       0   795.9     .07       0  9673.4     .05       0
#XS Ineff= 2 , 0
          497.98   231.410362.56          258.12
Permanent Ineff=
       F       F
Bank Sta=795.9,9673.4
XS Rating Curve= 0 ,0
Exp/Cntr=0.3,0.1

Type RM Length L Ch R = 1 ,268171  ,2634,2634,2634
BEGIN DESCRIPTION:
NAVASOTA RIVER 449
END DESCRIPTION:
XS GIS Cut Line= 3
      3613359.66     10245901.83      3602957.02     10246757.92
      3598060.18     10247594.54
#Sta/Elev= 30
 -5437.8  266.35 -5255.9  262.58 -4828.2  240.02 -4650.1  241.32 -4617.5     236
   -4467  237.23 -3734.5  217.56 -2724.5   219.7   -2593  216.16 -2580.6  212.83
 -2481.8   219.6   -2451  219.51 -2420.1  212.91 -2369.9  219.23 -2279.6  212.94
 -2211.7  221.57 -1988.6  227.62 -1296.3  226.06  -400.1  232.93  -300.7  233.18
   -52.1   230.1    78.3  216.64   198.5  206.12  1352.6  211.48  1543.3  207.09
  8484.7  208.34  9329.5   212.3  9438.3  218.71  9740.2  251.23  9967.8  263.41
#Mann= 9 ,-1 , 0
 -5437.8     .05       0 -2724.5     .16       0   -2593     .05       0
 -2481.8     .12       0   -2451     .05       0  -400.1     .16       0
  -300.7     .05       0    78.3     .07       0  9438.3     .05       0
#XS Ineff= 2 , 0
         -532.53  233.99
Permanent Ineff=
       F       F
Bank Sta=78.3,9438.3
XS Rating Curve= 0 ,0
Exp/Cntr=0.3,0.1

Type RM Length L Ch R = 1 ,265537  ,891,891,891
BEGIN DESCRIPTION:
NAVASOTA RIVER 450
END DESCRIPTION:
XS GIS Cut Line= 3
      3613278.51     10245334.12      3602330.72     10245717.56
      3596972.03     10246363.64
#Sta/Elev= 30
 -5954.5  273.23 -5594.8  264.47 -5157.6  239.55 -5028.9  241.71 -4492.4  226.82
 -4036.9  216.65 -2677.3   218.1 -2646.1  218.14 -2616.1   211.8   -2586  218.52
 -2523.8  218.55 -2355.9  227.76 -2225.8  229.57 -1027.9  228.13  -730.6  219.66
  -648.1  219.52  -424.7  218.48   -84.5  206.49   215.7  206.72   315.7  210.68
   816.1  209.32   915.9  205.82  1336.4  211.05  1946.7  207.23  8010.3  208.29
  9417.7  218.81  9692.4  220.41  9838.1  232.32 10007.3  255.88 10397.5  264.34
#Mann= 8 ,-1 , 0
 -5954.5     .16       0 -4492.4     .05       0 -2677.3     .12       0
 -2523.8     .05       0  -730.6     .16       0  -648.1     .05       0
  -424.7     .07       0  9417.7     .05       0
#XS Ineff= 2 , 0
        -1490.22  229.91
Permanent Ineff=
       F       F
Bank Sta=-424.7,9417.7
XS Rating Curve= 0 ,0
Exp/Cntr=0.3,0.1

Type RM Length L Ch R = 1 ,264646  ,1499,1499,1499
BEGIN DESCRIPTION:
NAVASOTA RIVER 451
END DESCRIPTION:
XS GIS Cut Line= 3
      3613296.32     10245290.86       3602677.7     10245027.04
       3597306.2     10245559.28
#Sta/Elev= 30
 -5621.9  272.65   -5277  264.55 -4847.4  243.65 -4644.6  245.17 -4243.2  235.09
 -4118.1  228.84 -3897.2  217.55 -2273.9  216.06 -2246.6  211.29 -2176.5  211.62
 -2156.6  218.07 -2086.6  210.97 -2006.6  224.44 -1926.5  228.42 -1686.5  229.53
 -1056.3  226.82  -906.2  231.38  -620.9  218.44   224.1  220.67   394.2  210.96
   583.2  207.41  1354.2  205.68  4435.4   209.7  8440.7  208.38  8834.3  212.88
  9253.4  211.28  9763.2  218.26   10071  247.81 10331.6  259.14 10397.8  257.49
#Mann= 7 ,-1 , 0
 -5621.9     .16       0   -5277     .16       0 -4118.1     .05       0
 -2273.9     .12       0 -2176.5     .05       0   224.1     .07       0
  9763.2     .16       0
#XS Ineff= 2 , 0
          -967.5  231.72
Permanent Ineff=
       F       F
Bank Sta=224.1,9763.2
XS Rating Curve= 0 ,0
Exp/Cntr=0.3,0.1

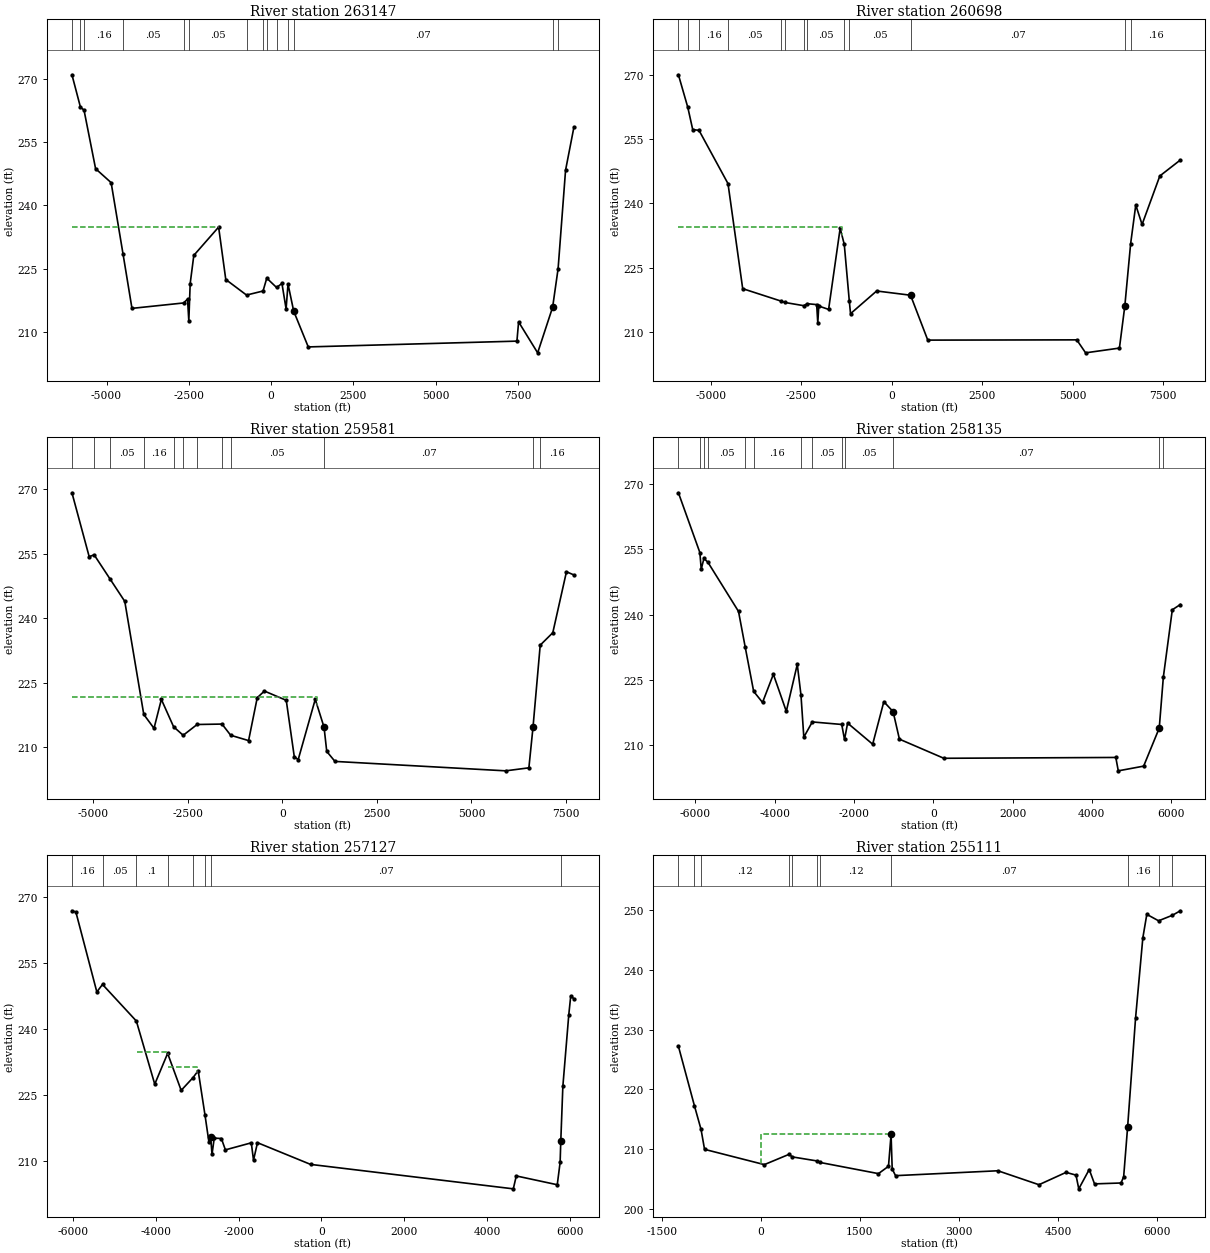
Type RM Length L Ch R = 1 ,263147  ,2449,2449,2449
BEGIN DESCRIPTION:
NAVASOTA RIVER 452
END DESCRIPTION:
XS GIS Cut Line= 3
      3613306.83     10245225.58      3602305.58      10244187.7
      3598198.12      10243346.6
#Sta/Elev= 30
 -6050.1  270.89 -5791.9  263.22 -5683.5  262.53 -5332.2  248.67 -4860.1  245.37
 -4497.9  228.45 -4227.3  215.62 -2660.9   216.9 -2539.9  217.81 -2500.7  212.65
 -2459.5  221.48   -2349  228.16 -1595.7  234.85 -1378.3  222.45  -748.4  218.77
  -246.4  219.73  -133.2  222.77   164.3  220.56   327.3  221.51   453.4   215.5
   511.8  221.38   684.4  214.96  1126.4   206.5  7463.6  207.87  7514.6  212.42
  8093.3   205.1  8547.6  215.88  8714.2     225  8940.9  248.31  9192.7  258.42
#Mann= 14 ,-1 , 0
 -6050.1     .16       0 -5791.9     .05       0 -5683.5     .16       0
 -4497.9     .05       0 -2660.9     .12       0 -2500.7     .05       0
  -748.4     .05       0  -246.4     .16       0  -133.2     .05       0
   164.3     .16       0   511.8     .05       0   684.4     .07       0
  8547.6     .12       0  8714.2     .16       0
#XS Ineff= 2 , 0
        -1594.18  234.87
Permanent Ineff=
       F       F
Bank Sta=684.4,8547.6
XS Rating Curve= 0 ,0
Exp/Cntr=0.3,0.1

Type RM Length L Ch R = 1 ,260698  ,1117,1117,1117
BEGIN DESCRIPTION:
NAVASOTA RIVER 453
END DESCRIPTION:
XS GIS Cut Line= 4
      3613390.76      10245167.2      3602675.77     10243144.64
      3601930.27     10242996.88       3599837.9     10242252.92
#Sta/Elev= 30
 -5904.2  270.02   -5645  262.43 -5508.7  257.23 -5334.8  257.05 -4532.4  244.61
 -4125.9  220.09 -3058.5  217.17 -2960.2  216.87   -2437  216.12   -2338  216.58
 -2079.2  216.37 -2048.6  212.07 -2021.3  216.03 -1749.2  215.25 -1429.7  234.19
 -1315.9  230.43 -1176.4  217.18 -1142.9  214.25  -420.4  219.55   517.7  218.56
   994.2  208.08  5115.9  208.14  5360.3  205.11    6296  206.22  6444.9  216.01
  6606.2  230.59  6748.1  239.61  6922.5  235.07  7413.7   246.4  7980.7  250.12
#Mann= 13 ,-1 , 0
 -5904.2     .16       0   -5645     .05       0 -5334.8     .16       0
 -4532.4     .05       0 -3058.5     .12       0 -2960.2     .05       0
   -2437     .12       0   -2338     .05       0 -1315.9     .16       0
 -1176.4     .05       0   517.7     .07       0  6444.9     .12       0
  6606.2     .16       0
#XS Ineff= 2 , 0
        -1375.93  234.45
Permanent Ineff=
       F       F
Bank Sta=517.7,6444.9
XS Rating Curve= 0 ,0
Exp/Cntr=0.3,0.1

Type RM Length L Ch R = 1 ,259581  ,1446,1446,1446
BEGIN DESCRIPTION:
NAVASOTA RIVER 454
END DESCRIPTION:
XS GIS Cut Line= 3
      3613401.78     10245142.03      3603196.61     10242392.03
      3600497.25     10242145.44
#Sta/Elev= 30
 -5569.2  269.18 -5113.8  254.35 -4981.2  254.75 -4564.7  249.19 -4171.4  243.94
 -3668.8  217.67   -3398  214.44 -3203.5  221.16 -2879.7   214.8 -2626.3  212.82
   -2258  215.33 -1599.1  215.43 -1369.6  212.83  -895.8  211.59  -666.5  221.56
  -477.2   223.1     101  220.95   313.1  207.87   416.6  207.15   868.5  221.19
  1101.2  214.69  1172.4  209.07  1390.2  206.75    5908  204.56  6520.8  205.26
  6629.8  214.69  6820.5  233.77  7153.4  236.66  7514.9  250.83  7710.6  250.09
#Mann= 12 ,-1 , 0
 -5569.2     .16       0 -4981.2     .16       0 -4564.7     .05       0
 -3668.8     .16       0 -2879.7     .16       0 -2626.3     .12       0
   -2258     .05       0 -1599.1     .12       0 -1369.6     .05       0
  1101.2     .07       0  6629.8     .12       0  6820.5     .16       0
#XS Ineff= 2 , 0
          923.97  221.73
Permanent Ineff=
       F       F
Bank Sta=1101.2,6629.8
XS Rating Curve= 0 ,0
Exp/Cntr=0.3,0.1

Type RM Length L Ch R = 1 ,258135  ,1008,1008,1008
BEGIN DESCRIPTION:
NAVASOTA RIVER 455
END DESCRIPTION:
XS GIS Cut Line= 3
      3613448.91      10245107.3      3602586.26     10241557.36
      3601365.58     10241389.27
#Sta/Elev= 30
   -6428  267.93 -5887.1  254.22 -5852.7  250.39 -5784.5  252.86 -5684.2  251.99
   -4912  240.71 -4744.5  232.59 -4530.2  222.37 -4306.3  219.83 -4032.7  226.29
 -3706.6  217.79 -3429.9  228.56 -3336.8  221.55 -3264.7  211.87 -3050.9  215.36
 -2308.6  214.78 -2238.4  211.33 -2160.1  215.09 -1528.1  210.25 -1246.5     220
 -1012.8  217.73  -853.5  211.41   267.5  207.02  4604.6  207.21  4667.5  204.14
    5307  205.22  5700.7  213.95  5804.1  225.65  6030.2  241.09  6232.2  242.29
#Mann= 13 ,-1 , 0
   -6428     .16       0 -5887.1     .05       0 -5784.5     .16       0
 -5684.2     .05       0 -4744.5      .1       0 -4530.2     .16       0
 -3336.8     .12       0 -3050.9     .05       0 -2308.6     .12       0
 -2238.4     .05       0 -1012.8     .07       0  5700.7     .12       0
  5804.1     .16       0
#XS Ineff= 2 ,-1
   -4912 -3429.9  228.56 -3429.9 -1246.5     220
Permanent Ineff=
       F       F
Bank Sta=-1012.8,5700.7
XS Rating Curve= 0 ,0
Exp/Cntr=0.3,0.1

Type RM Length L Ch R = 1 ,257127  ,2016,2016,2016
BEGIN DESCRIPTION:
NAVASOTA RIVER 456
END DESCRIPTION:
XS GIS Cut Line= 3
      3613489.72      10245066.4      3603266.92     10240938.91
      3602258.63     10240495.96
#Sta/Elev= 30
 -6024.6  266.91 -5930.1  266.64 -5423.3  248.48 -5286.2  250.18 -4468.5  241.87
 -4024.3  227.53 -3712.8  234.52 -3385.7  226.12 -3098.6  229.03   -2975  230.59
 -2809.6  220.48 -2717.5  214.51 -2673.2  215.51 -2640.9  211.57   -2587  215.28
 -2414.2  215.19 -2317.6  212.61 -1691.9  214.21   -1638  210.28 -1542.1  214.24
  -259.4  209.31  4638.3  203.76  4710.4  206.69  5700.3  204.69  5769.8   209.8
  5785.2  214.52  5835.4  227.01  5979.1  243.34  6025.8  247.55  6101.3  246.94
#Mann= 8 ,-1 , 0
 -6024.6     .16       0 -5286.2     .05       0 -4468.5      .1       0
 -3712.8     .16       0 -3098.6     .05       0 -2809.6     .12       0
 -2673.2     .07       0  5785.2     .16       0
#XS Ineff= 2 ,-1
 -4448.3 -3696.9   234.8 -3696.9-3009.19   231.5
Permanent Ineff=
       F       F
Bank Sta=-2673.2,5785.2
XS Rating Curve= 0 ,0
Exp/Cntr=0.3,0.1

Type RM Length L Ch R = 1 ,255111  ,1920,1920,1920
BEGIN DESCRIPTION:
NAVASOTA RIVER 448
END DESCRIPTION:
XS GIS Cut Line= 3
      3609962.36     10241158.34      3605888.61     10239996.88
      3602535.74     10239830.28
#Sta/Elev= 30
 -1245.6  227.21 -1002.5   217.2  -903.2  213.27  -850.2  209.93    54.5  207.37
   427.3  209.09   479.3  208.66   854.2  207.98   893.7  207.74  1780.6  205.86
  1932.5  207.09  1971.6  212.43  1988.6  206.64  2039.2  205.52  3587.7  206.34
  4208.9     204    4619  206.07  4769.2  205.61  4811.2  203.31  4969.4  206.55
  5049.5  204.14    5450  204.29  5490.1  205.31  5550.2  213.67  5670.3  231.92
  5780.4  245.38  5840.5  249.32  6018.5  248.24  6228.6  249.17  6347.5  249.92
#Mann= 11 ,-1 , 0
 -1245.6     .05       0 -1002.5      .1       0  -903.2     .12       0
   427.3     .07       0   479.3     .12       0   854.2     .05       0
   893.7     .12       0  1971.6     .07       0  5550.2     .16       0
  6018.5     .05       0  6228.6     .16       0
#XS Ineff= 2 , 0
       0  1971.6  212.43               0
Permanent Ineff=
       F       F
Bank Sta=1971.6,5550.2
XS Rating Curve= 0 ,0
Exp/Cntr=0.3,0.1

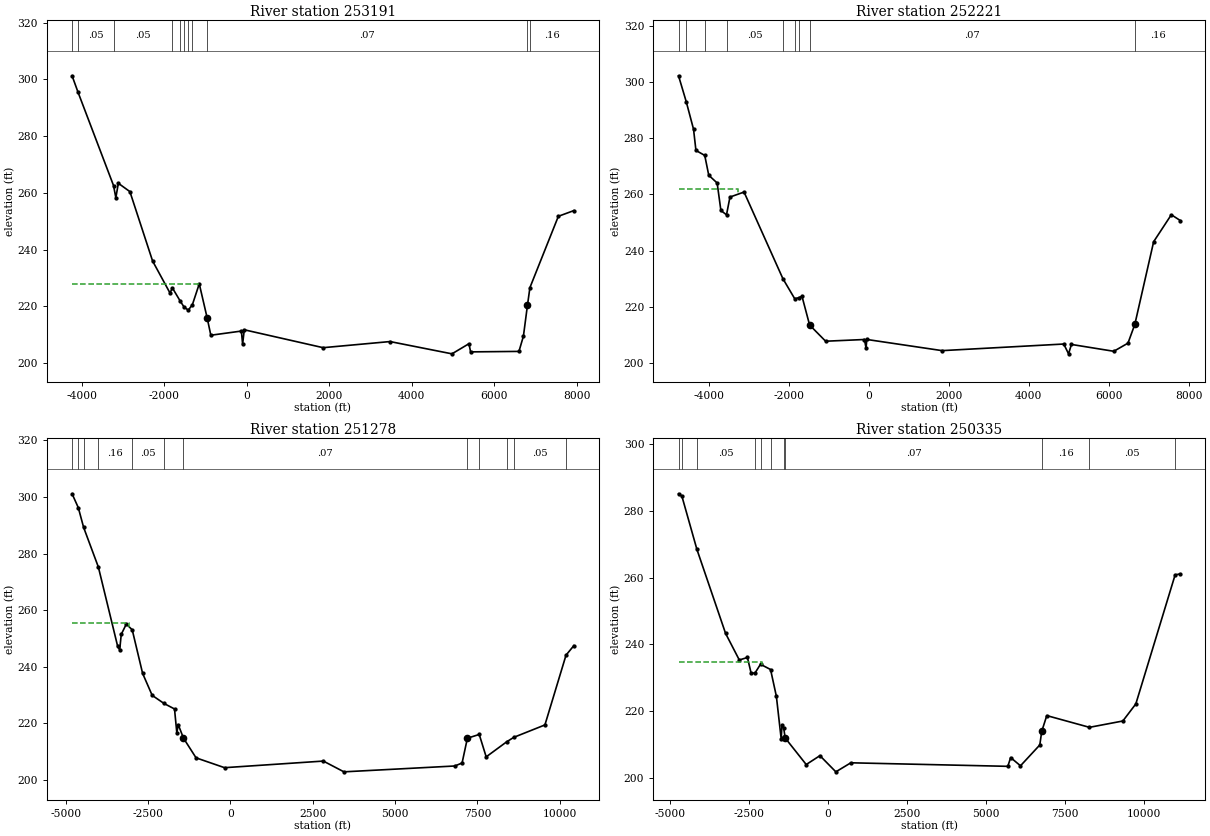
Type RM Length L Ch R = 1 ,253191  ,970,970,970
BEGIN DESCRIPTION:
NAVASOTA RIVER 447
END DESCRIPTION:
XS GIS Cut Line= 3
      3614402.59     10239073.83       3605173.6     10238886.35
      3602262.41     10239161.94
#Sta/Elev= 30
 -4230.9  301.26 -4086.7  295.47 -3226.8  262.57 -3170.2  258.27 -3110.2  263.36
 -2830.1  260.42   -2280  235.94 -1859.9  224.71 -1799.1  226.44 -1612.3  221.85
 -1513.6  219.63 -1414.9  218.66 -1316.2  220.56 -1149.8  227.91  -959.7  215.97
  -869.7  209.79  -129.6  211.26   -99.6  206.64   -59.6  211.71  1850.8   205.4
  3471.2  207.56  4971.2  203.23  5383.2   206.8    5423  203.92  6594.1  204.09
  6702.4  209.46  6799.5  220.29    6860  226.59  7548.7  251.72  7924.2  253.73
#Mann= 11 ,-1 , 0
 -4230.9     .05       0 -4086.7     .05       0 -3226.8     .05       0
 -1799.1     .07       0 -1612.3     .05       0 -1513.6     .07       0
 -1414.9      .1       0 -1316.2     .12       0  -959.7     .07       0
  6799.5     .12       0    6860     .16       0
#XS Ineff= 2 , 0
        -1148.66  227.99
Permanent Ineff=
       F       F
Bank Sta=-959.7,6799.5
XS Rating Curve= 0 ,0
Exp/Cntr=0.3,0.1

Type RM Length L Ch R = 1 ,252221  ,943,943,943
BEGIN DESCRIPTION:
NAVASOTA RIVER 457
END DESCRIPTION:
XS GIS Cut Line= 3
      3614406.97     10238829.82      3604656.24      10238154.4
      3601943.01     10238818.02
#Sta/Elev= 30
 -4774.1  302.18 -4580.8  292.94 -4398.3  283.16 -4338.2  275.62 -4117.6  273.85
 -4017.4   266.8 -3806.9  264.04 -3713.4  254.27 -3572.6  252.72 -3486.2  259.04
 -3133.3  260.82 -2159.9  229.99 -1863.8  222.86 -1765.1  223.23 -1681.8  223.72
 -1491.4  213.52 -1090.4  207.76  -118.1  208.37     -78  205.34     -58  208.38
  1826.5  204.41  4873.8  206.76  4993.9  203.27    5066  206.61  6126.4  204.18
  6482.1  207.07  6653.8  213.76    7125  243.16  7567.7  252.75  7793.2  250.68
#Mann= 9 ,-1 , 0
 -4774.1      .1       0 -4580.8     .05       0 -4117.6     .16       0
 -3572.6     .05       0 -2159.9     .07       0 -1863.8     .12       0
 -1765.1     .07       0 -1491.4     .07       0  6653.8     .16       0
#XS Ineff= 2 , 0
        -3283.13  261.96
Permanent Ineff=
       F       F
Bank Sta=-1491.4,6653.8
XS Rating Curve= 0 ,0
Exp/Cntr=0.3,0.1

Type RM Length L Ch R = 1 ,251278  ,943,943,943
BEGIN DESCRIPTION:
NAVASOTA RIVER 458
END DESCRIPTION:
XS GIS Cut Line= 3
      3614425.68     10238527.22      3604701.68     10237276.58
      3599285.26     10236978.71
#Sta/Elev= 30
 -4804.1  301.14 -4614.8  296.22 -4453.2  289.23 -4005.9  275.21 -3419.2  247.11
 -3358.7  245.92 -3311.7  251.39 -3157.7  255.04 -2978.3     253   -2663  237.58
 -2372.6  229.81 -2013.3  226.94 -1695.1     225 -1624.5  216.53 -1582.3  219.46
 -1422.9  214.67 -1040.8   207.7  -176.1  204.22  2821.8  206.56  3446.6  202.75
  6812.3  204.82  7032.6  205.89  7192.9  214.64  7552.8  215.98  7763.7  208.05
    8385  213.37  8602.3  214.96  9546.4  219.35 10186.9  244.04 10424.6  247.41
#Mann= 12 ,-1 , 0
 -4804.1      .1       0 -4614.8     .05       0 -4453.2      .1       0
 -4005.9     .16       0 -2978.3     .05       0 -2013.3     .12       0
 -1422.9     .07       0  7192.9     .05       0  7552.8     .16       0
    8385     .16       0  8602.3     .05       0 10186.9     .16       0
#XS Ineff= 2 , 0
        -3080.38  255.57
Permanent Ineff=
       F       F
Bank Sta=-1422.9,7192.9
XS Rating Curve= 0 ,0
Exp/Cntr=0.3,0.1

Type RM Length L Ch R = 1 ,250335  ,1933,1933,1933
BEGIN DESCRIPTION:
NAVASOTA RIVER 459
END DESCRIPTION:
XS GIS Cut Line= 3
      3614149.17     10237642.23      3604502.26     10236367.27
      3598367.93     10235884.42
#Sta/Elev= 30
 -4730.8  285.15 -4625.6  284.46 -4148.8  268.47   -3242   243.3 -2807.1  235.33
 -2550.5  236.08 -2433.9  231.42   -2313  231.39 -2135.9  234.04 -1817.6  232.47
 -1633.6  224.44 -1481.7  211.71 -1455.5  215.79 -1402.8     215 -1354.6  211.94
  -688.9  203.99  -255.1  206.65     249   201.8   723.3  204.51  5692.3  203.45
  5782.6  206.08  6093.5  203.61  6705.4  209.86  6765.6  213.91  6926.1  218.66
  8276.8  215.14  9333.5  217.04  9744.8  222.16 10988.7  260.85 11153.3  261.13
#Mann= 11 ,-1 , 0
 -4730.8     .05       0 -4625.6      .1       0 -4148.8     .05       0
   -2313      .1       0 -2135.9     .12       0 -1817.6     .16       0
 -1402.8     .12       0 -1354.6     .07       0  6765.6     .16       0
  8276.8     .05       0 10988.7     .05       0
#XS Ineff= 2 , 0
        -2101.53  234.61
Permanent Ineff=
       F       F
Bank Sta=-1354.6,6765.6
XS Rating Curve= 0 ,0
Exp/Cntr=0.3,0.1