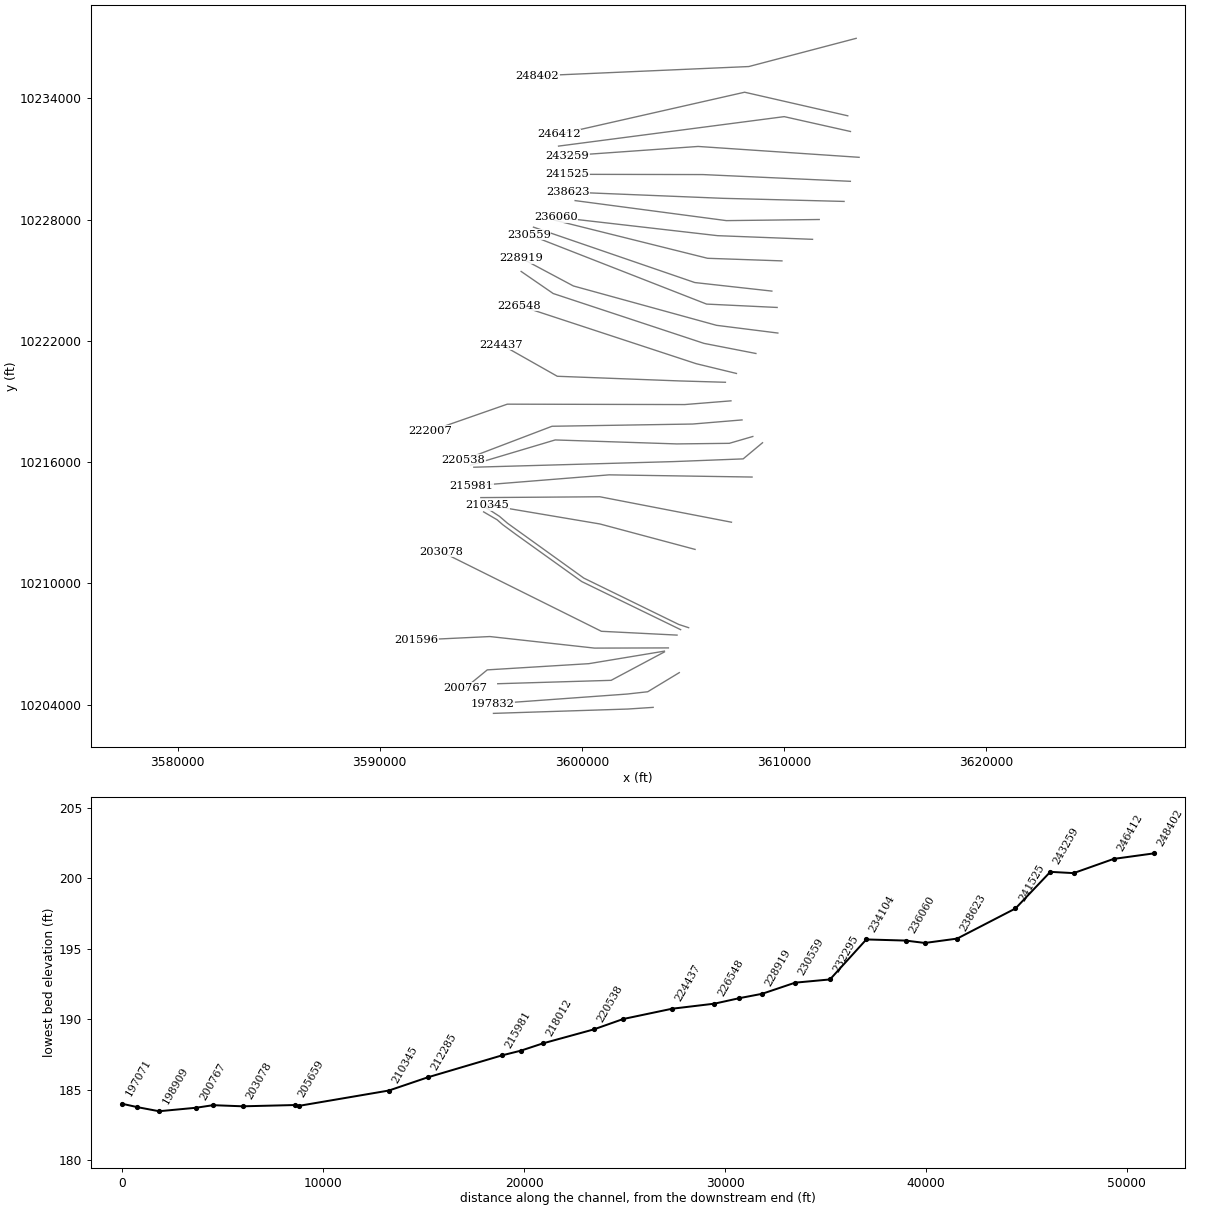
HEC-RAS study NAVASOTA RIVER.prj: NAVASOTA RIVER Base Level Engineering

--- NAVASOTA RIVER.g01 (geometry) --- (continued)

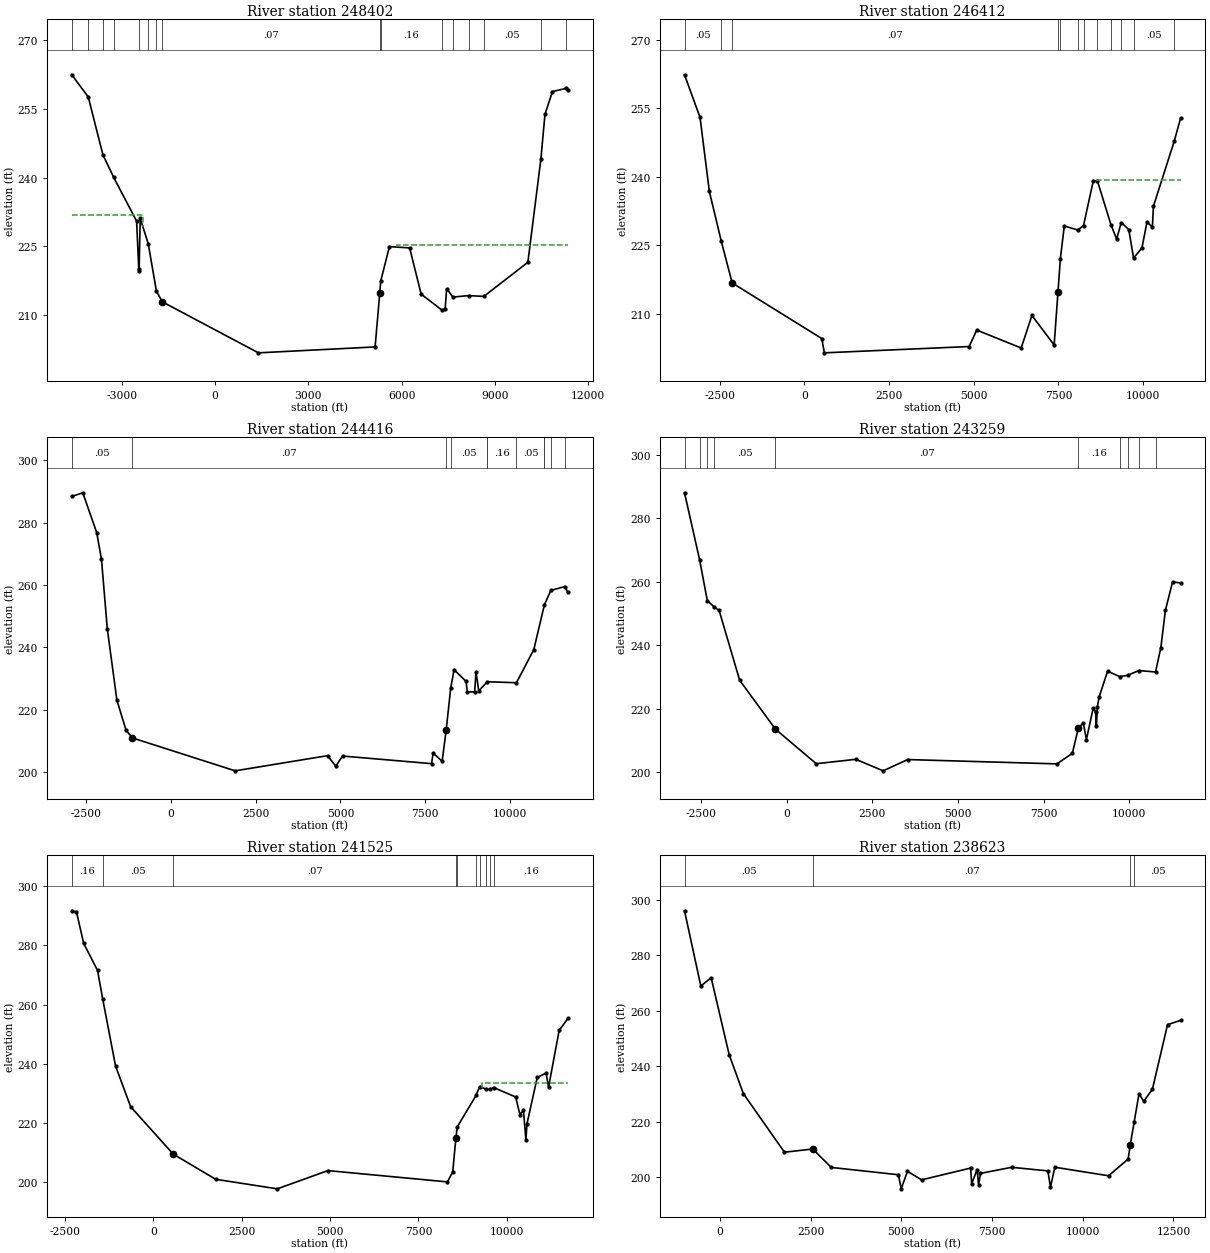
Type RM Length L Ch R = 1 ,248402  ,1990,1990,1990
BEGIN DESCRIPTION:
NAVASOTA RIVER 205
END DESCRIPTION:
XS GIS Cut Line= 3
      3613576.14     10236976.05      3608263.61     10235580.21
      3597806.19     10235121.92
#Sta/Elev= 30
 -4610.5  262.49 -4080.1  257.64 -3611.7  245.08 -3263.1  240.09 -2525.1  230.54
 -2454.8     220 -2444.4  219.64 -2409.2  231.16 -2151.7  225.61 -1886.9  215.23
 -1698.3  212.91  1394.1  201.77  5147.9  203.06  5298.1  214.87  5328.4  217.43
  5608.4  224.97    6259  224.68  6629.4  214.59  7292.3  211.14  7400.1  211.26
  7450.1  215.77  7650.9  213.95  8156.6  214.27  8645.5  214.09 10062.7  221.54
 10481.7  244.08 10613.2  253.88 10853.4  258.82 11301.7  259.54 11349.8  259.13
#Mann= 16 ,-1 , 0
 -4610.5     .05       0 -4080.1      .1       0 -3611.7      .1       0
 -3263.1      .1       0 -2454.8      .1       0 -2151.7     .16       0
 -1886.9     .05       0 -1698.3     .07       0  5298.1     .12       0
  5328.4     .16       0  7292.3     .16       0  7650.9     .05       0
  8156.6     .16       0  8645.5     .05       0 10481.7     .16       0
 11301.7     .16       0
#XS Ineff= 2 , 0
         -2324.4  231.94 5860.46          225.34
Permanent Ineff=
       F       F
Bank Sta=-1698.3,5298.1
XS Rating Curve= 0 ,0
Exp/Cntr=0.3,0.1

Type RM Length L Ch R = 1 ,246412  ,1996,1996,1996
BEGIN DESCRIPTION:
NAVASOTA RIVER 206
END DESCRIPTION:
XS GIS Cut Line= 3
      3613159.41     10233142.72      3608055.27     10234309.38
      3598869.06     10232226.34
#Sta/Elev= 30
 -3544.3  262.34 -3085.5  252.98 -2811.1  236.78 -2461.9  225.95   -2136   216.7
   511.1  204.51   586.6  201.38  4863.2  202.76  5088.8  206.37  6401.2  202.44
  6718.6  209.58  7375.4  203.09  7487.5  214.65  7558.5  222.03  7675.3  229.19
  8077.6   228.3  8242.8  229.29  8530.5  239.05    8651  239.14  9052.4  229.48
  9221.1  226.33  9358.3  229.95  9579.9   228.4  9721.7  222.16  9969.6  224.39
 10116.5  230.03 10277.2  228.98   10308  233.52 10926.3  247.86 11110.9  252.84
#Mann= 12 ,-1 , 0
 -3544.3     .05       0 -2461.9     .05       0   -2136     .07       0
  7487.5     .12       0  7558.5     .16       0  8077.6     .05       0
  8242.8     .16       0    8651     .16       0  9052.4     .05       0
  9358.3     .16       0  9721.7     .05       0 10926.3     .16       0
#XS Ineff= 2 , 0
                         8655.34          239.23
Permanent Ineff=
       F       F
Bank Sta=-2136,7487.5
XS Rating Curve= 0 ,0
Exp/Cntr=0.3,0.1

Type RM Length L Ch R = 1 ,244416  ,1157,1157,1157
BEGIN DESCRIPTION:
NAVASOTA RIVER 460
END DESCRIPTION:
XS GIS Cut Line= 3
      3613293.77     10232365.94      3610013.61     10233101.04
      3598847.06     10231642.73
#Sta/Elev= 30
 -2918.5  288.44 -2594.6  289.63 -2183.8  276.85 -2043.5  268.31 -1871.5  245.94
 -1589.4  223.07   -1319   213.4 -1130.2  210.93  1896.5  200.37  4619.7  205.24
  4861.7  201.86  5063.4  205.12  7685.5  202.68  7733.4  206.06  7998.1  203.45
    8118  213.54  8249.7  226.87  8349.8  232.83  8704.1  229.09  8739.6  225.67
  8956.2  225.74  8996.5  232.16  9077.2  226.01    9330  228.97 10188.4  228.65
 10700.9  239.31   11014  253.76 11203.8  258.28   11611  259.53 11704.4  257.63
#Mann= 11 ,-1 , 0
 -2918.5     .05       0 -1130.2     .07       0    8118     .12       0
  8249.7     .05       0    9330     .05       0    9330     .16       0
 10188.4     .05       0   11014     .05       0   11014     .16       0
 11203.8     .05       0   11611     .16       0
Bank Sta=-1130.2,8118
XS Rating Curve= 0 ,0
Exp/Cntr=0.3,0.1

Type RM Length L Ch R = 1 ,243259  ,1734,1734,1734
BEGIN DESCRIPTION:
NAVASOTA RIVER 461
END DESCRIPTION:
XS GIS Cut Line= 3
      3613720.99       10231088.      3605753.31     10231625.72
      3599267.88     10231166.13
#Sta/Elev= 30
 -2985.8  287.96 -2542.9  266.76 -2320.8  254.05   -2135  252.16 -1974.6  250.92
 -1375.3  228.96  -329.3  213.56   861.8   202.7  2014.4  204.09    2816  200.46
  3530.7  204.01  7888.4  202.65  8339.6  205.96  8519.3  214.06  8660.2  215.45
  8750.6  210.31  8952.1  220.34  9021.3  218.86  9041.3  214.45  9071.4  220.62
  9121.5  223.68  9369.8  231.85  9721.5   230.1  9951.8  230.52   10283  232.02
 10768.9  231.57 10924.8  239.23 11056.4  250.92 11266.9  259.93 11501.7  259.57
#Mann= 10 ,-1 , 0
 -2985.8     .16       0 -2542.9     .05       0 -2320.8     .16       0
   -2135     .05       0  -329.3     .07       0  8519.3     .16       0
  9721.5     .05       0  9951.8     .16       0   10283     .05       0
 10768.9     .16       0
Bank Sta=-329.3,8519.3
XS Rating Curve= 0 ,0
Exp/Cntr=0.3,0.1

Type RM Length L Ch R = 1 ,241525  ,2902,2902,2902
BEGIN DESCRIPTION:
NAVASOTA RIVER 462
END DESCRIPTION:
XS GIS Cut Line= 3
      3613288.72      10229900.5      3605992.65     10230234.12
      3599265.36     10230246.87
#Sta/Elev= 30
 -2303.7  291.64 -2170.6  291.23 -1966.7  280.63 -1576.3  271.55 -1429.9  261.94
 -1065.8  239.28  -638.6  225.54   565.9  209.57  1766.8  201.08  3508.7  197.86
  4940.5  204.01  8320.5   200.2  8470.5  203.57  8560.5  215.07  8599.4  218.77
  9131.7  229.37  9230.5  232.36  9414.7  231.47  9526.7  231.41  9625.4  232.02
 10250.6  228.85 10370.6  222.91 10470.6  224.32 10540.6  214.34 10570.6   219.8
 10860.6  235.43 11110.6  236.89 11180.6  232.14 11480.6  251.31 11727.3  255.31
#Mann= 10 ,-1 , 0
 -2303.7     .16       0 -1429.9     .05       0   565.9     .07       0
  8560.5     .12       0  8599.4     .16       0  9131.7     .05       0
  9230.5     .16       0  9414.7      .1       0  9526.7     .05       0
  9625.4     .16       0
#XS Ineff= 2 , 0
       0                  9300.5       0   233.6
Permanent Ineff=
       F       F
Bank Sta=565.9,8560.5
XS Rating Curve= 0 ,0
Exp/Cntr=0.3,0.1

Type RM Length L Ch R = 1 ,238623  ,1606,1606,1606
BEGIN DESCRIPTION:
NAVASOTA RIVER 463
END DESCRIPTION:
XS GIS Cut Line= 3
      3612977.02     10228905.19      3607000.28     10229057.96
      3599306.15     10229371.29
#Sta/Elev= 30
  -978.7   296.1  -529.5  268.96  -243.5  271.91   251.9  244.17   642.7  230.11
  1777.1  208.94  2557.4   210.1  3067.5  203.45  4918.1  200.81  4996.3  195.72
  5168.3  202.04  5558.6  198.97  6909.8  203.22  6939.8  197.59  7089.9  202.66
  7129.9  197.13  7182.2  201.29  8040.7   203.5  9041.5  202.19  9111.6  196.28
  9231.7  203.52 10712.9  200.44 11253.3  206.46 11313.4  211.67 11421.3  219.95
 11553.6  230.05 11683.7  227.31 11923.9  231.72 12339.9  254.98 12700.5  256.54
#Mann= 4 ,-1 , 0
  -978.7     .05       0  2557.4     .07       0 11313.4     .16       0
 11421.3     .05       0
Bank Sta=2557.4,11313.4
XS Rating Curve= 0 ,0
Exp/Cntr=0.3,0.1

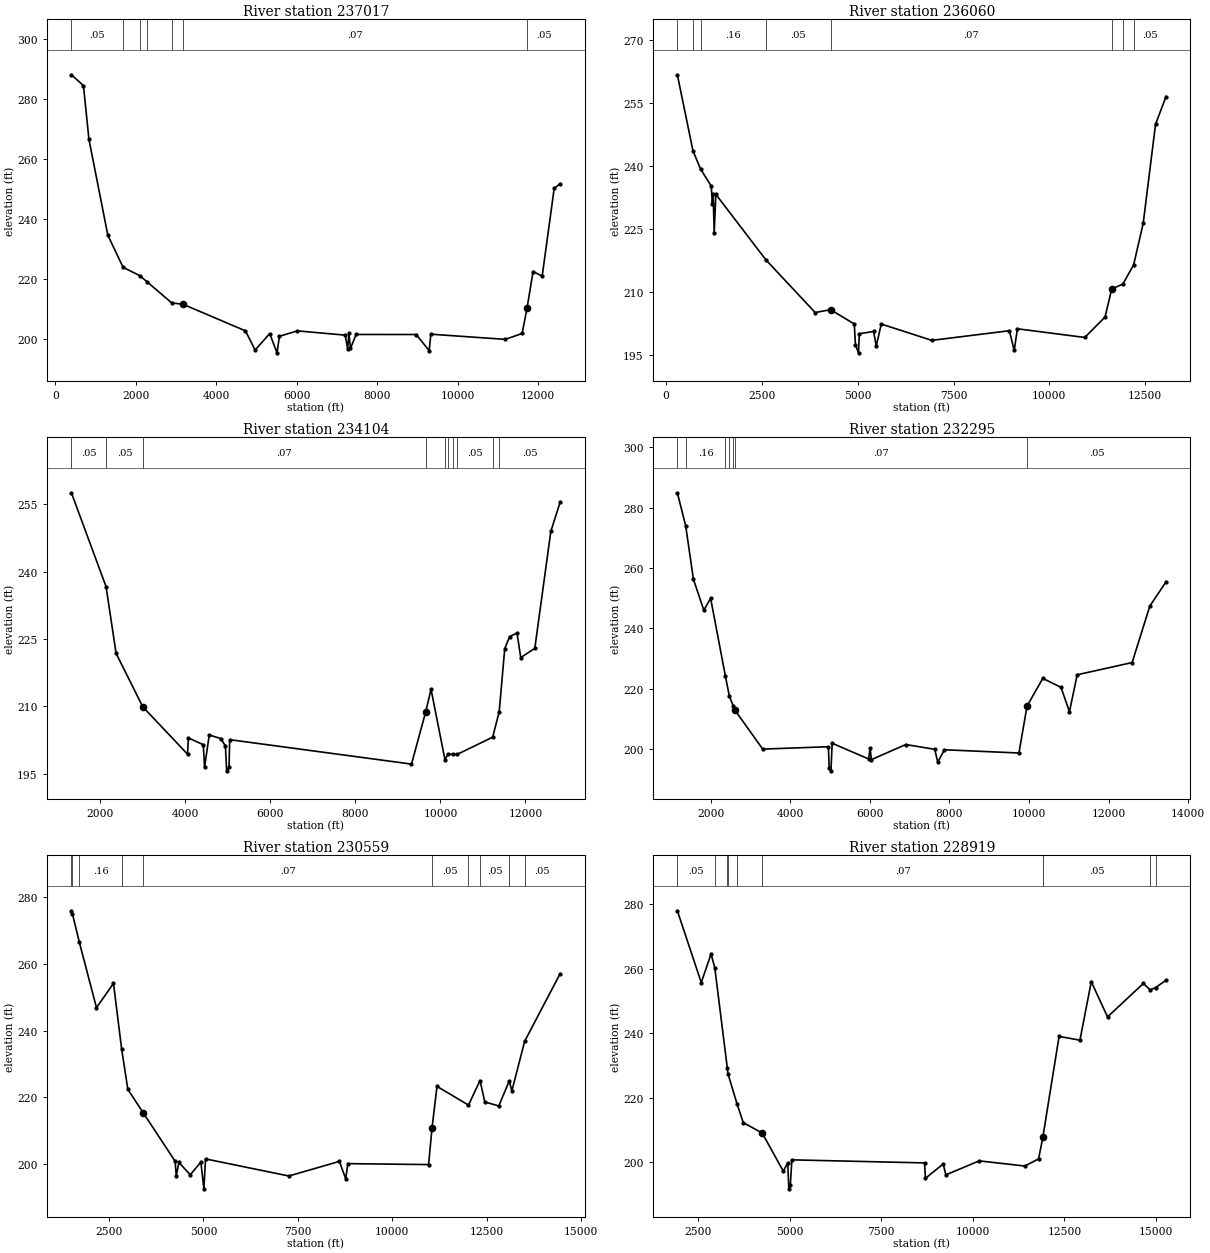
Type RM Length L Ch R = 1 ,237017  ,957,957,957
BEGIN DESCRIPTION:
NAVASOTA RIVER 464
END DESCRIPTION:
XS GIS Cut Line= 3
       3611747.4     10228010.22      3607150.83     10227955.09
      3599666.86     10228945.31
#Sta/Elev= 30
   403.1  288.21   702.5  284.59   838.4  266.68  1308.5  234.66  1688.6  223.93
  2105.6  221.15  2280.8  219.14  2895.1  212.09  3178.6  211.61  4728.7  202.75
  4968.7  196.35  5331.6  201.84  5512.9  195.41  5573.7  200.93  6017.5  202.74
  7207.8  201.32  7268.3  196.76  7301.3  201.87  7338.9   196.9  7480.2  201.54
  8972.1  201.53  9295.8  196.14  9336.2  201.63 11187.1  199.91 11605.8  201.88
 11726.8   210.3 11878.2  222.55 12103.5  220.99 12402.3  250.27 12549.2  251.84
#Mann= 7 ,-1 , 0
   403.1     .05       0  1688.6     .16       0  2105.6     .05       0
  2280.8     .16       0  2895.1     .05       0  3178.6     .07       0
 11726.8     .05       0
Bank Sta=3178.6,11726.8
XS Rating Curve= 0 ,0
Exp/Cntr=0.3,0.1

Type RM Length L Ch R = 1 ,236060  ,1956,1956,1956
BEGIN DESCRIPTION:
NAVASOTA RIVER 465
END DESCRIPTION:
XS GIS Cut Line= 3
      3611415.76     10227029.54      3606712.55     10227210.82
      3598720.47      10228128.5
#Sta/Elev= 30
   293.3  261.81   700.4  243.73   899.2  239.36  1177.6  235.31  1207.6  231.03
  1227.6   233.5  1254.7  224.12  1297.7  233.33  2603.7  217.73  3889.6  205.18
  4289.9  205.86  4910.4  202.46  4940.4  197.48  5020.3  195.58  5040.7  200.13
  5413.1  200.67  5483.6   197.2  5614.5  202.44  6933.1  198.55  8956.3  200.85
  9082.8  196.14  9166.9  201.31 10924.3  199.24   11454  204.12 11627.2   210.8
 11917.8  211.95 12198.5  216.51 12449.1  226.45 12771.2  250.04 13044.6  256.62
#Mann= 8 ,-1 , 0
   293.3     .16       0   700.4     .05       0   899.2     .16       0
  2603.7     .05       0  4289.9     .07       0 11627.2     .05       0
 11917.8     .16       0 12198.5     .05       0
Bank Sta=4289.9,11627.2
XS Rating Curve= 0 ,0
Exp/Cntr=0.3,0.1

Type RM Length L Ch R = 1 ,234104  ,1809,1809,1809
BEGIN DESCRIPTION:
NAVASOTA RIVER 466
END DESCRIPTION:
XS GIS Cut Line= 3
      3609902.67     10225962.48      3606222.21     10226090.77
      3598639.69      10227980.7
#Sta/Elev= 30
  1317.3  257.58  2132.2  236.68  2368.5  221.82  2996.7  209.91  4049.5  199.37
  4069.5  202.99  4419.8  201.48  4449.8  196.44  4559.8  203.65    4830  202.85
  4940.1  201.21  4969.8  195.66  5025.1  196.46  5041.3   202.6  9318.3  197.16
  9654.3  208.85  9778.1  213.82 10105.7  198.13 10182.7  199.49 10294.3   199.3
   10397  199.34 11227.7  203.16 11381.2  208.79 11512.1  222.85 11626.8  225.56
 11801.1  226.35 11888.8  220.88 12219.1  222.93 12595.9  248.96 12814.5  255.47
#Mann= 10 ,-1 , 0
  1317.3     .05       0  2132.2     .05       0  2996.7     .07       0
  9654.3     .05       0 10105.7     .12       0 10182.7     .05       0
 10294.3     .07       0   10397     .05       0 11227.7     .16       0
 11381.2     .05       0
Bank Sta=2996.7,9654.3
XS Rating Curve= 0 ,0
Exp/Cntr=0.3,0.1

Type RM Length L Ch R = 1 ,232295  ,1736,1736,1736
BEGIN DESCRIPTION:
NAVASOTA RIVER 467
END DESCRIPTION:
XS GIS Cut Line= 3
      3609403.42     10224467.69      3605590.16     10224890.25
      3597606.83     10227631.66
#Sta/Elev= 30
  1163.4  284.94  1372.8  274.01  1567.2   256.3  1828.8  246.04  1999.8  249.97
  2370.7  224.18  2470.5  217.57  2570.3  214.27  2602.5  213.06  3307.8  200.02
  4957.8  200.81  4977.9  193.69  5021.8  192.82  5053.3  201.95  5969.8  196.75
  6006.3  200.44  6037.6  196.53  6902.1  201.53  7630.7  199.96  7704.7  195.66
  7873.8   199.8  9745.3  198.73  9948.8  214.27 10344.5  223.45 10802.6  220.47
 11014.1  212.41 11209.1  224.65 12589.1  228.69 13033.5   247.4 13440.9  255.45
#Mann= 7 ,-1 , 0
  1163.4     .05       0  1372.8     .16       0  2370.7     .05       0
  2470.5     .08       0  2570.3     .05       0  2602.5     .07       0
  9948.8     .05       0
Bank Sta=2602.5,9948.8
XS Rating Curve= 0 ,0
Exp/Cntr=0.3,0.1

Type RM Length L Ch R = 1 ,230559  ,1640,1640,1640
BEGIN DESCRIPTION:
NAVASOTA RIVER 468
END DESCRIPTION:
XS GIS Cut Line= 3
      3609664.71     10223657.79      3606172.19     10223824.62
      3597379.63     10227262.32
#Sta/Elev= 30
  1503.5  275.91  1529.8  275.05    1713  266.49  2166.9  246.88  2617.4  254.15
  2833.1  234.49  2997.8  222.37  3402.6  215.41  4249.2  200.85  4279.3  196.46
  4349.3   200.5  4649.7  196.79    4930  200.62  5010.6  192.59  5053.8  201.56
  7258.9  196.44    8597  200.81  8765.7  195.59    8820  200.14 10959.2  199.86
 11048.9   210.7 11181.9  223.29 12015.7  217.68 12321.1  225.05 12447.1  218.64
 12816.7  217.42 13095.5  224.93 13163.8  221.91   13502   236.8 14440.7  257.04
#Mann= 10 ,-1 , 0
  1503.5     .16       0  1529.8     .05       0    1713     .16       0
  2833.1     .05       0  3402.6     .07       0 11048.9     .05       0
 12015.7     .16       0 12321.1     .05       0 13095.5     .16       0
   13502     .05       0
Bank Sta=3402.6,11048.9
XS Rating Curve= 0 ,0
Exp/Cntr=0.3,0.1

Type RM Length L Ch R = 1 ,228919  ,1135,1135,1135
BEGIN DESCRIPTION:
NAVASOTA RIVER 469
END DESCRIPTION:
XS GIS Cut Line= 4
      3609699.59     10222391.64      3606663.85     10222773.84
      3599580.62     10224721.51       3596999.7     10226097.42
#Sta/Elev= 30
  1940.3  278.01  2592.9  255.75  2860.5  264.63  2960.9  260.38  3302.1  229.35
  3322.3  227.47    3568  218.13  3739.2  212.33  4255.9  209.09  4830.4  197.27
  4951.4  199.86  4981.4   191.8  5022.6  193.05    5064  200.79  8683.6  199.84
  8708.2  195.05  9191.8  199.52  9264.4  196.13 10174.9  200.47 11419.5  198.87
 11794.7  201.09 11910.8  207.83 12353.6  239.06 12922.4  237.89 13231.3  256.02
 13675.5  245.11 14651.7  255.47 14842.1  253.46 14988.7  254.22 15270.9  256.47
#Mann= 10 ,-1 , 0
  1940.3     .05       0  2960.9     .16       0  3302.1     .05       0
  3322.3     .16       0    3568     .05       0  4255.9     .07       0
 11910.8     .16       0 11910.8     .05       0 14842.1     .16       0
 14988.7     .05       0
Bank Sta=4255.9,11910.8
XS Rating Curve= 0 ,0
Exp/Cntr=0.3,0.1

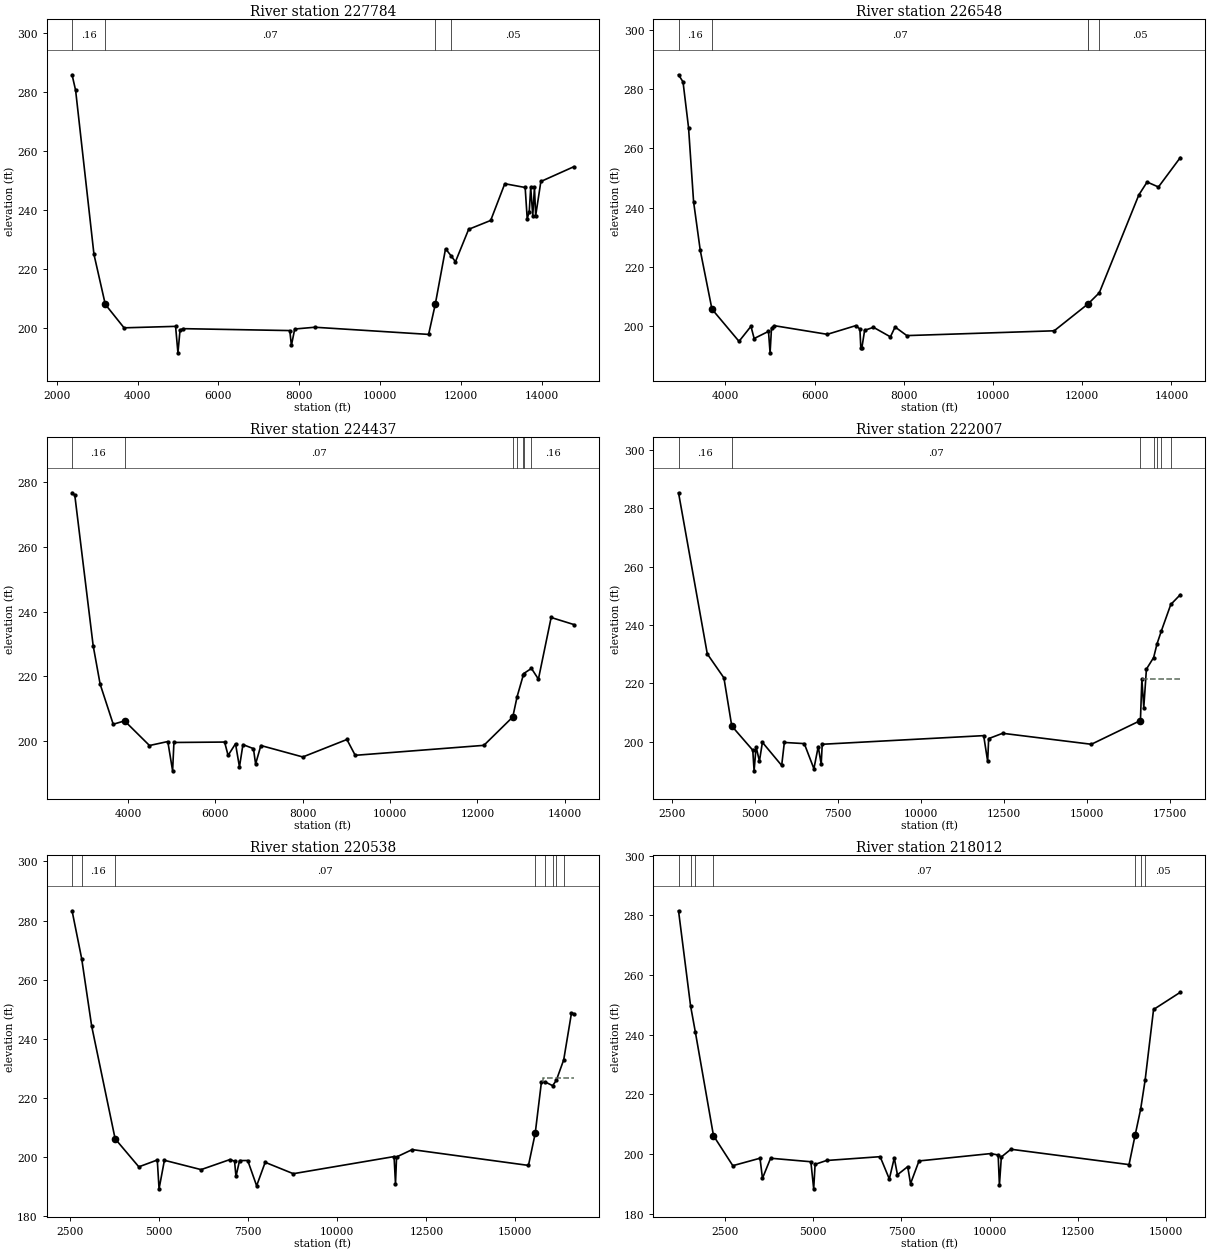
Type RM Length L Ch R = 1 ,227784  ,1236,1236,1236
BEGIN DESCRIPTION:
NAVASOTA RIVER 470
END DESCRIPTION:
XS GIS Cut Line= 4
      3608613.57     10221379.94      3606042.63     10221880.43
      3598583.23     10224346.51      3596995.87     10225439.44
#Sta/Elev= 30
  2380.8   285.9  2468.6   280.6  2922.2  224.91  3201.6  207.96  3665.9  199.98
  4939.4  200.48  4997.5  191.49  5049.8  199.23  5126.9   199.7  7762.4  199.05
  7802.1  194.01  7884.1  199.58  8381.4  200.18 11193.6  197.75 11358.2  207.98
   11612  226.83 11745.6   224.5 11857.1  222.42 12183.1  233.43 12727.7  236.44
 13076.4  248.91   13580  247.63 13630.7  237.02 13681.4  239.46 13717.3  247.64
   13768  238.11 13809.9  247.74 13839.7  238.05 13968.2  249.67 14783.7  254.69
#Mann= 4 ,-1 , 0
  2380.8     .16       0  3201.6     .07       0 11358.2     .16       0
 11745.6     .05       0
Bank Sta=3201.6,11358.2
XS Rating Curve= 0 ,0
Exp/Cntr=0.3,0.1

Type RM Length L Ch R = 1 ,226548  ,2111,2111,2111
BEGIN DESCRIPTION:
NAVASOTA RIVER 471
END DESCRIPTION:
XS GIS Cut Line= 3
      3607650.08     10220391.64      3605657.21     10220875.22
      3596915.86     10223747.98
#Sta/Elev= 30
  2949.3  284.81  3050.1   282.4  3173.6  267.02  3286.8  242.04  3436.5  225.63
  3698.4  205.84  4305.5  194.97  4573.1  200.03  4645.1  195.93  4966.4  198.33
  5002.1   191.1  5034.1  199.41  5089.6  200.27    6285  197.34  6926.4  200.28
  7015.9  199.11  7036.9  192.83  7058.8  192.67  7122.4   198.7  7321.1   199.7
  7700.2  196.49  7805.3  199.81  8068.5  196.91 11373.4  198.53 12134.3  207.62
 12384.6  211.34 13270.9  244.32 13456.5  248.67 13710.5  246.99 14201.3  256.92
#Mann= 5 ,-1 , 0
  2949.3     .16       0  3698.4     .07       0 12134.3     .05       0
 12134.3     .16       0 12384.6     .05       0
Bank Sta=3698.4,12134.3
XS Rating Curve= 0 ,0
Exp/Cntr=0.3,0.1

Type RM Length L Ch R = 1 ,224437  ,2430,2430,2430
BEGIN DESCRIPTION:
NAVASOTA RIVER 472
END DESCRIPTION:
XS GIS Cut Line= 4
       3607104.7     10219955.21      3604821.08     10220022.07
      3598784.44     10220252.09      3596025.57     10221813.71
#Sta/Elev= 30
  2715.4  276.71    2778  275.95  3198.2  229.49  3358.3  217.55  3658.4  205.14
  3918.5  206.19  4488.8  198.57  4908.9   199.8  5018.7  190.74    5049  199.51
  6209.9  199.64  6289.9  195.51    6460  199.12  6550.1  191.95  6630.2  198.86
  6870.3  197.61  6920.4  192.86  7040.5  198.57  8001.2  195.03  9011.9  200.43
    9202  195.54 12149.5  198.62   12812   207.4 12911.8  213.71 13052.6  220.35
 13060.7   220.8 13239.4  222.41 13399.3  219.09 13690.8  238.15 14211.2  235.97
#Mann= 7 ,-1 , 0
  2715.4     .16       0  3918.5     .07       0   12812     .16       0
 12911.8     .05       0 13052.6     .16       0 13060.7     .05       0
 13239.4     .16       0
Bank Sta=3918.5,12812
XS Rating Curve= 0 ,0
Exp/Cntr=0.3,0.1

Type RM Length L Ch R = 1 ,222007  ,1469,1469,1469
BEGIN DESCRIPTION:
NAVASOTA RIVER 473
END DESCRIPTION:
XS GIS Cut Line= 4
       3607379.3     10219036.01      3605091.68     10218852.22
      3596310.48     10218871.88      3592508.39     10217543.75
#Sta/Elev= 30
    2705  285.26  3570.6  230.06  4071.1  221.85  4307.3  205.36  4939.4  197.08
  4979.3  190.01  5039.6  198.25  5139.6  193.32  5229.6  199.78  5809.6  191.84
  5889.6  199.73  6489.6  199.34  6779.6  190.74  6909.6  198.31  6999.6  192.29
  7029.6  199.11 11889.6  202.07 12009.6  193.23 12039.6  201.05 12459.6  202.87
 15130.7  199.11 16607.7  207.24 16651.4  221.45 16708.3  211.68 16787.8  224.85
 17005.5  228.83 17108.6  233.56 17241.2  238.05 17521.3  246.99 17808.6  250.36
#Mann= 7 ,-1 , 0
    2705     .16       0  4307.3     .07       0 16607.7     .05       0
 17005.5      .1       0 17108.6     .08       0 17241.2     .05       0
 17521.3     .05       0
#XS Ineff= 2 , 0
                        16651.08          221.41
Permanent Ineff=
       F       F
Bank Sta=4307.3,16607.7
XS Rating Curve= 0 ,0
Exp/Cntr=0.3,0.1

Type RM Length L Ch R = 1 ,220538  ,2526,2526,2526
BEGIN DESCRIPTION:
NAVASOTA RIVER 255
END DESCRIPTION:
XS GIS Cut Line= 4
      3607927.29     10218092.05      3605484.04     10217888.68
      3598524.02     10217778.13      3594149.02     10216111.46
#Sta/Elev= 30
  2548.3   283.3  2818.4   267.1  3098.1  244.35  3757.6   206.2  4423.4  196.71
  4941.7  199.02  4991.7  189.27  5141.9  198.93  6172.1  195.77  6982.2  199.17
  7112.2  198.62  7152.2  193.46  7252.2  198.82  7482.2  198.85  7732.3   190.3
  7972.3  198.24  8762.4  194.39 11592.8  200.18 11632.8  190.94 11662.8  200.05
 12101.1  202.54 15367.6  197.19 15556.9  208.02 15732.1  225.44 15837.3  225.41
 16045.5  224.16 16149.6  225.94 16357.7  232.91 16576.2  248.75 16642.6  248.49
#Mann= 8 ,-1 , 0
  2548.3     .05       0  2818.4     .16       0  3757.6     .07       0
 15556.9      .1       0 15837.3     .16       0 16045.5     .16       0
 16149.6     .12       0 16357.7     .16       0
#XS Ineff= 2 , 0
                        15787.96          226.77
Permanent Ineff=
       F       F
Bank Sta=3757.6,15556.9
XS Rating Curve= 0 ,0
Exp/Cntr=0.3,0.1

Type RM Length L Ch R = 1 ,218012  ,1103,1103,1103
BEGIN DESCRIPTION:
NAVASOTA RIVER 256
END DESCRIPTION:
XS GIS Cut Line= 5
      3608460.38     10217272.38      3607297.23     10216933.85
      3604698.01      10216904.3      3598680.27     10217101.04
       3594487.6     10215851.05
#Sta/Elev= 30
  1189.2  281.57  1529.5  249.71  1666.1  240.83    2179   206.1  2725.8  196.05
  3495.8  198.55  3565.8  191.82  3795.8  198.55  4935.9  197.37  5015.7  188.28
  5055.9   196.5  5379.3  197.79  6896.9  199.07  7157.1  191.58  7297.1  198.63
  7387.2     193  7677.3  195.72  7757.4     190  7997.5  197.64 10028.6  200.11
 10238.7  199.63 10273.9  189.51 10328.8  198.97 10598.9  201.56 13943.7  196.41
 14119.9  206.49 14272.5     215 14399.7  224.77 14638.1  248.45   15396  254.23
#Mann= 7 ,-1 , 0
  1189.2     .16       0  1529.5     .05       0  1666.1     .16       0
    2179     .07       0 14119.9     .05       0 14272.5     .12       0
 14399.7     .05       0
Bank Sta=2179,14119.9
XS Rating Curve= 0 ,0
Exp/Cntr=0.3,0.1

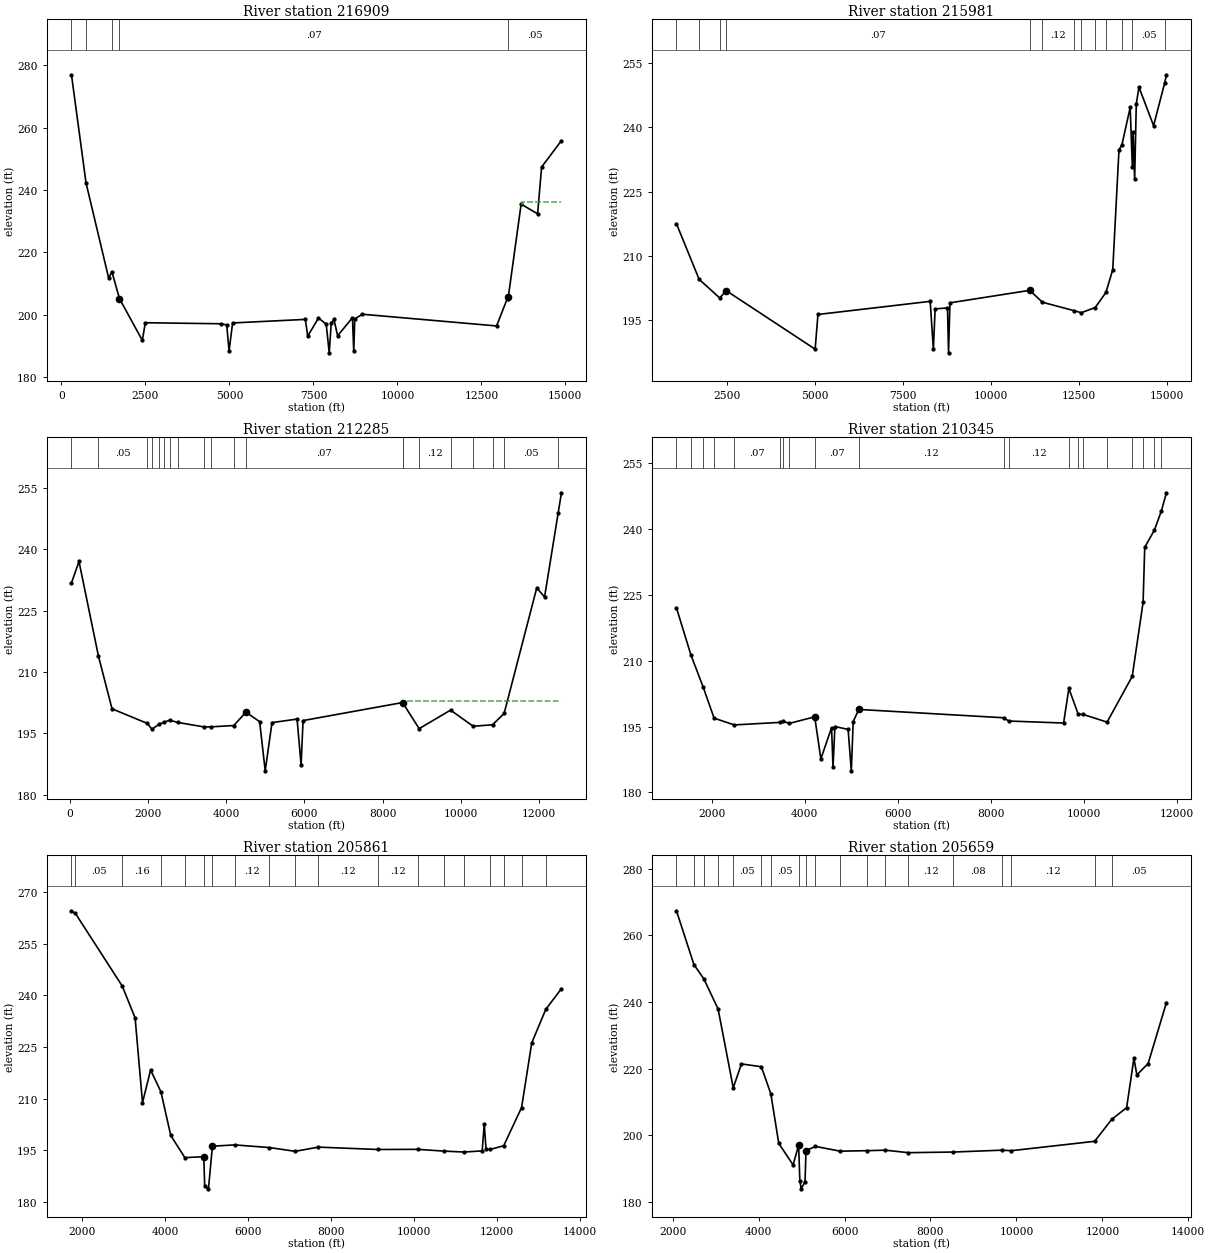
Type RM Length L Ch R = 1 ,216909  ,928,928,928
BEGIN DESCRIPTION:
NAVASOTA RIVER 257
END DESCRIPTION:
XS GIS Cut Line= 4
      3608941.18     10216962.52      3607982.82     10216163.89
      3604531.35      10216029.3      3594652.34     10215751.99
#Sta/Elev= 30
   298.4  276.97   731.1   242.3  1405.6  211.73  1501.4  213.78  1726.8  205.16
  2407.3  191.76  2497.1  197.42    4749  197.09  4919.2   196.7  4989.2  188.37
  5094.6  197.35  7260.1  198.49  7330.2  193.11  7650.3  198.93  7880.4  196.98
  7970.2  187.76  8030.4  197.21  8110.5  198.51  8220.5  193.24  8662.2  199.02
  8700.7  188.28  8730.7  198.68  8960.8  200.14 12952.4  196.39 13289.6  205.68
 13294.6  205.16 13682.7  235.46 14172.9  232.36 14292.9  247.38 14882.9  255.84
#Mann= 5 ,-1 , 0
   298.4     .16       0   731.1     .05       0  1501.4     .16       0
  1726.8     .07       0 13294.6     .05       0
#XS Ineff= 2 , 0
                        13709.71          236.31
Permanent Ineff=
       F       F
Bank Sta=1726.8,13289.6
XS Rating Curve= 0 ,0
Exp/Cntr=0.3,0.1

Type RM Length L Ch R = 1 ,215981  ,3696,3696,3696
BEGIN DESCRIPTION:
NAVASOTA RIVER 207
END DESCRIPTION:
XS GIS Cut Line= 3
      3608424.16     10215265.11      3601349.54     10215373.61
      3594518.25     10214824.17
#Sta/Elev= 30
  1065.2  217.55  1709.9  204.58    2297  200.21  2477.4  201.95  5007.7  188.29
  5087.7  196.38  8278.5  199.44  8368.8  188.26    8419  197.68  8770.1  197.91
    8800  187.43  8840.3  199.09 11107.6  202.01 11469.5  199.23 12376.8  197.25
 12574.2  196.79 12969.1     198 13274.5  201.51 13468.3  206.84 13645.8  234.82
 13726.6  235.86 13963.6  244.68 14025.1   230.7 14047.1  239.01 14091.1  227.98
 14137.4  245.52 14213.7   249.4   14629  240.42 14943.7  250.34   14994  252.29
#Mann= 13 ,-1 , 0
  1065.2     .16       0  1709.9     .07       0    2297     .12       0
  2477.4     .07       0 11107.6     .07       0 11469.5     .12       0
 12376.8     .12       0 12574.2     .05       0 12969.1     .16       0
 13274.5     .16       0 13726.6     .05       0 14025.1     .05       0
 14943.7      .1       0
#XS Ineff= 2 , 0
                        11106.86          201.99
Permanent Ineff=
       F       F
Bank Sta=2477.4,11107.6
XS Rating Curve= 0 ,0
Exp/Cntr=0.3,0.1

Type RM Length L Ch R = 1 ,212285  ,1940,1940,1940
BEGIN DESCRIPTION:
NAVASOTA RIVER 208
END DESCRIPTION:
XS GIS Cut Line= 3
      3607404.22     10213029.87      3600893.81     10214288.54
      3595000.91     10214248.04
#Sta/Elev= 30
    46.5  231.74   238.7  236.97   734.2  213.94  1082.8  201.01  1980.6  197.46
  2103.9  196.04  2285.5  197.23  2400.6  197.71  2558.5  198.23  2766.2  197.68
  3445.4  196.57  3615.2  196.61  4195.3  196.93  4506.1  200.19  4856.1  197.88
  4998.4  185.87  5171.8  197.64  5813.5  198.51  5915.3  187.36  5966.2  198.14
  8509.2  202.54  8933.6  196.17  9736.7  200.69 10315.3  196.75 10808.8  197.11
 11104.9  199.87 11939.3  230.52 12139.3  228.31 12486.6   248.8 12570.5  253.74
#Mann= 20 ,-1 , 0
    46.5      .1       0   734.2     .05       0  1980.6     .07       0
  2103.9     .12       0  2285.5     .12       0  2400.6     .07       0
  2558.5     .12       0  2766.2     .07       0  3445.4     .12       0
  3615.2     .07       0  4195.3     .12       0  4506.1     .07       0
  8509.2     .12       0  8509.2     .16       0  8933.6     .12       0
  9736.7     .05       0 10315.3     .05       0 10808.8     .12       0
 11104.9     .05       0 12486.6     .08       0
#XS Ineff= 2 , 0
                         8576.31          202.98
Permanent Ineff=
       F       F
Bank Sta=4506.1,8509.2
XS Rating Curve= 0 ,0
Exp/Cntr=0.3,0.1

Type RM Length L Ch R = 1 ,210345  ,4484,4484,4484
BEGIN DESCRIPTION:
NAVASOTA RIVER 209
END DESCRIPTION:
XS GIS Cut Line= 3
      3605603.01     10211684.38      3600893.81     10212943.06
      3595316.25     10213884.13
#Sta/Elev= 30
  1244.4  222.06  1555.9  211.32  1819.9  203.97    2054  196.93  2487.8  195.39
  3471.3  195.97  3538.7  196.18  3673.9  195.75  4216.1  197.23  4348.4  187.65
  4578.4  194.77  4609.4   185.8  4650.8  195.03  4933.9  194.37  5002.5  184.93
  5043.7  196.16  5163.9  198.92  8280.6  197.02  8384.6  196.28  9565.1  195.82
    9679  203.69  9880.5   197.8  9976.9  197.81 10499.8  196.03 11040.6  206.45
 11274.2  223.34 11308.8  235.83   11519  239.83 11667.1  244.15 11775.3  248.28
#Mann= 20 ,-1 , 0
  1244.4     .05       0  1555.9      .1       0  1819.9     .05       0
    2054     .12       0  2487.8     .07       0  3471.3     .12       0
  3538.7     .05       0  3673.9     .12       0  4216.1     .07       0
  5163.9     .12       0  8280.6     .07       0  8384.6     .12       0
    9679     .05       0  9880.5     .07       0  9976.9     .12       0
 10499.8     .16       0 11040.6     .05       0 11274.2     .16       0
   11519     .05       0 11667.1     .08       0
Bank Sta=4216.1,5163.9
XS Rating Curve= 0 ,0
Exp/Cntr=0.3,0.1

Type RM Length L Ch R = 1 ,205861  ,202,202,202
BEGIN DESCRIPTION:
NAVASOTA RIVER 253
END DESCRIPTION:
XS GIS Cut Line= 6
      3605284.98     10207810.01      3604790.15     10207972.49
      3600095.59     10210264.85      3596321.09     10212978.49
      3595922.89     10213320.57      3595188.04     10213797.12
#Sta/Elev= 30
  1747.6  264.54    1843  263.76  2970.6  242.68  3279.8  233.44  3457.6  208.85
  3652.9  218.33  3901.5  211.99  4137.9  199.33  4477.4   192.9  4933.2  193.16
  4955.8  184.55  5045.8  183.84  5141.9  196.22  5676.9  196.59  6509.6  195.83
  7134.1  194.73  7695.5  195.95    9129  195.26 10084.7   195.3 10721.8  194.79
 11199.7  194.52 11636.7  194.85 11686.7  202.61 11730.1  195.32 11830.5  195.28
 12154.9  196.35   12586  207.44 12829.6  226.16 13167.1  235.91 13545.4  241.94
#Mann= 19 ,-1 , 0
  1747.6     .08       0    1843     .05       0  2970.6     .16       0
  3901.5     .05       0  4477.4     .12       0  4933.2     .07       0
  5141.9     .12       0  5676.9     .12       0  6509.6     .12       0
  7134.1     .12       0  7695.5     .12       0    9129     .12       0
 10084.7     .12       0 10721.8     .12       0 11199.7     .12       0
 11830.5     .16       0 12154.9     .16       0   12586     .05       0
 13167.1     .05       0
Bank Sta=4933.2,5141.9
XS Rating Curve= 0 ,0
Exp/Cntr=0.3,0.1

Type RM Length L Ch R = 1 ,205659  ,2581,2581,2581
BEGIN DESCRIPTION:
NAVASOTA RIVER 254
END DESCRIPTION:
XS GIS Cut Line= 6
      3604888.14     10207712.98       3599993.6     10210092.71
      3596743.13     10212422.22      3596084.36      10212907.7
      3595805.29     10213151.81      3595138.63     10213540.69
#Sta/Elev= 30
  2087.7  267.39  2494.4  251.23    2725  246.96  3056.8  237.89  3409.4  214.23
  3600.2  221.41  4063.7  220.56  4283.9  212.45  4468.7  197.55  4802.5  191.08
  4931.1  197.01  4959.3  186.37  4991.2   183.9  5080.4  186.08  5102.6  195.38
  5322.9  196.64  5898.2  195.21  6524.8  195.36  6945.6  195.51  7486.8  194.76
    8532  194.95  9659.9  195.51  9879.3  195.35 11820.9  198.17 12218.9  204.77
 12565.4  208.27 12734.6  223.09 12803.3   218.1 13065.4  221.52 13491.1  239.83
#Mann= 19 ,-1 , 0
  2087.7     .05       0  2494.4     .16       0    2725      .1       0
  3056.8     .16       0  3409.4     .05       0  4063.7     .16       0
  4283.9     .05       0  4931.1    .033       0  5102.6     .12       0
  5322.9     .08       0  5898.2     .12       0  6524.8     .12       0
  6945.6     .12       0  7486.8     .12       0    8532     .08       0
  9659.9     .08       0  9879.3     .12       0 11820.9     .05       0
 12218.9     .05       0
Bank Sta=4931.1,5102.6
XS Rating Curve= 0 ,0
Exp/Cntr=0.3,0.1

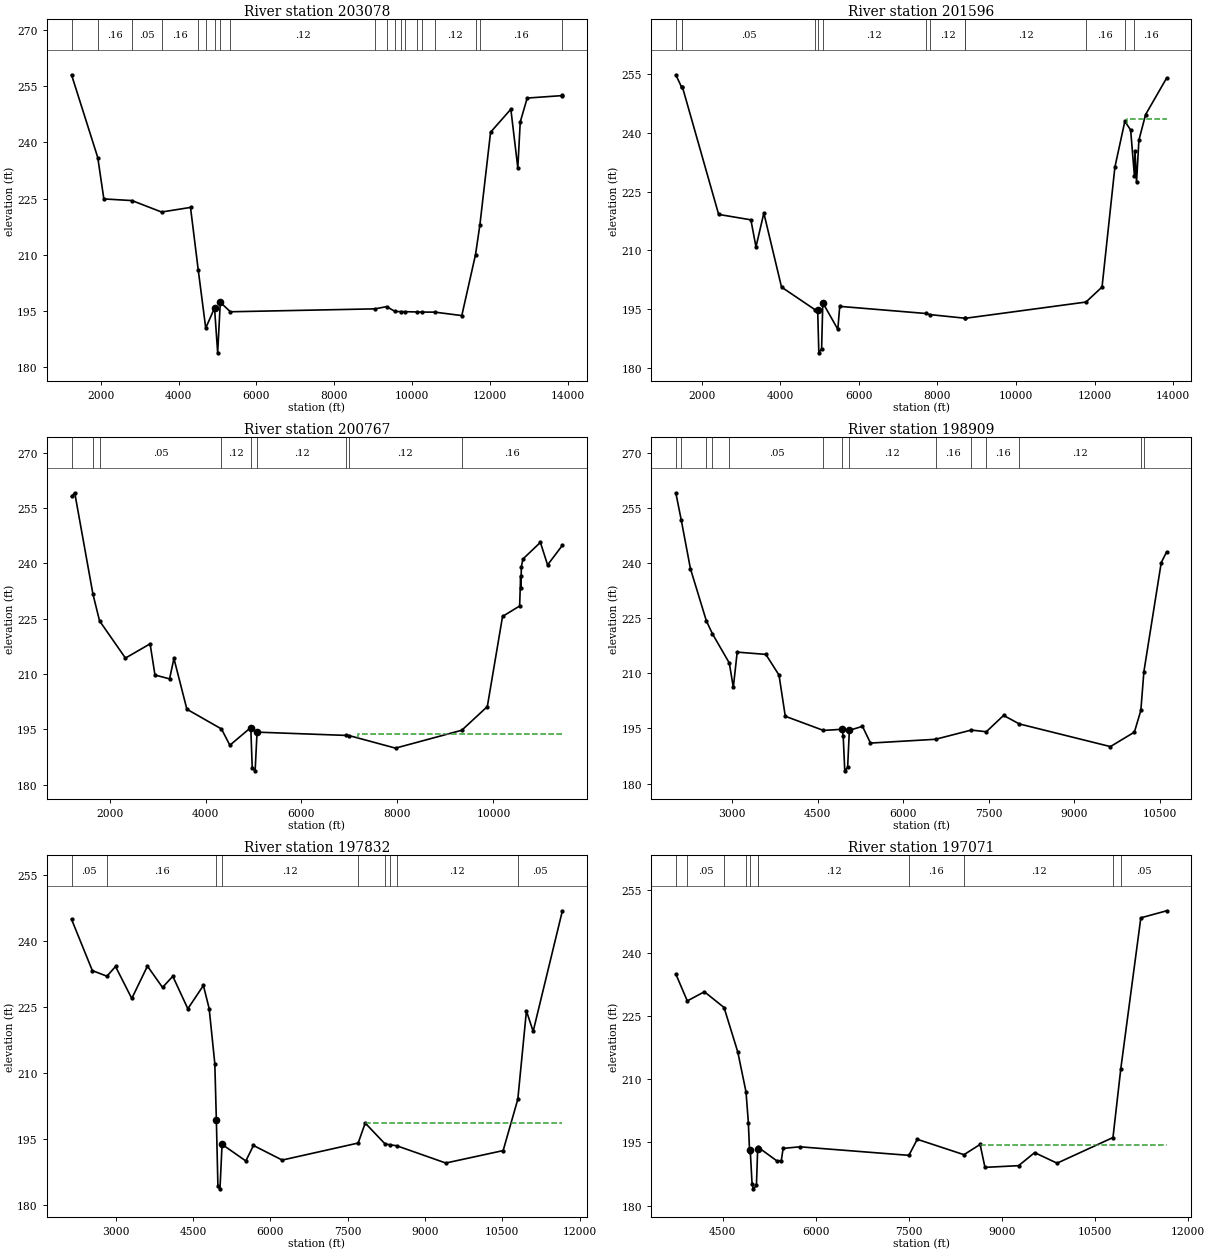
Type RM Length L Ch R = 1 ,203078  ,1482,1482,1482
BEGIN DESCRIPTION:
NAVASOTA RIVER 258
END DESCRIPTION:
XS GIS Cut Line= 3
       3604711.5     10207442.85      3600967.26      10207631.6
      3593033.44     10211577.04
#Sta/Elev= 30
    1251  258.08  1925.3  235.97  2081.5  224.92  2804.1  224.48  3564.2  221.42
  4307.5  222.65  4505.2  206.03  4698.4  190.43  4925.1  195.79  5005.5  183.81
  5072.8  197.31  5332.3  194.78  9052.9  195.56  9344.9  196.16  9562.4  194.86
  9717.7  194.82  9830.2   194.8 10125.8  194.73 10248.2   194.7   10586  194.68
 11276.9  193.76 11629.4  210.05 11741.8  218.01   12016  242.74 12536.8  248.88
 12715.9  233.19 12777.6  245.45 12956.7  251.86 13857.5  252.52 13860.7  252.65
#Mann= 20 ,-1 , 0
    1251     .16       0  1925.3     .16       0  2804.1     .05       0
  3564.2     .16       0  4505.2     .16       0  4698.4     .12       0
  4925.1     .07       0  5072.8     .12       0  5332.3     .12       0
  9052.9     .16       0  9344.9     .05       0  9562.4     .16       0
  9717.7     .05       0  9830.2     .16       0 10125.8     .12       0
 10248.2     .16       0   10586     .12       0 11629.4     .12       0
 11741.8     .16       0 13857.5     .05       0
Bank Sta=4925.1,5072.8
XS Rating Curve= 0 ,0
Exp/Cntr=0.3,0.1

Type RM Length L Ch R = 1 ,201596  ,829,829,829
BEGIN DESCRIPTION:
NAVASOTA RIVER 259
END DESCRIPTION:
XS GIS Cut Line= 4
      3604282.48     10206808.99      3600625.59     10206799.83
      3595449.39     10207371.43      3591826.21     10207197.86
#Sta/Elev= 30
  1343.1  254.78  1491.8   251.6  1511.9  251.65  2433.5  219.18  3253.5   217.8
  3383.5   210.9  3583.5  219.52  4033.5  200.65    4891  194.85  4953.5  194.79
  4983.2  183.89  5053.8  184.92    5084  196.66  5466.3  189.89  5514.6  195.74
  7709.5  193.92  7809.3  193.64    8707  192.71    8711   192.7 11781.6  196.84
 12190.4  200.67 12517.6  231.25 12770.5  242.91 12918.1  240.71 13015.7  228.88
 13028.8   235.4 13068.2  227.38 13128.3  238.11 13298.5  244.63   13835  253.97
#Mann= 13 ,-1 , 0
  1343.1     .05       0  1491.8     .08       0  1511.9     .05       0
    4891     .12       0  4953.5     .07       0    5084     .12       0
  7709.5     .07       0  7809.3     .12       0    8707     .07       0
    8711     .12       0 11781.6     .16       0 12770.5     .05       0
 13015.7     .16       0
#XS Ineff= 2 , 0
                        12824.36          243.38
Permanent Ineff=
       F       F
Bank Sta=4953.5,5084
XS Rating Curve= 0 ,0
Exp/Cntr=0.3,0.1

Type RM Length L Ch R = 1 ,200767  ,1858,1858,1858
BEGIN DESCRIPTION:
NAVASOTA RIVER 260
END DESCRIPTION:
XS GIS Cut Line= 4
      3604087.77     10206650.21       3600345.9     10206029.52
      3595319.18     10205722.12      3594235.61     10204833.59
#Sta/Elev= 30
    1207  258.17  1273.6  259.15    1654  231.61  1791.9  224.38  2330.8   214.3
  2844.7  218.17  2946.1  209.71  3250.3  208.66  3341.4   214.2  3611.1  200.43
  4332.1  195.07  4507.2  190.66    4943  195.45  4973.4   184.5  5033.6  183.71
  5073.9  194.21    6932  193.32  6986.7  193.29  7959.3  189.87  9340.1  194.72
  9872.9  201.14 10190.3   225.6 10546.3  228.43 10567.1  236.52   10575  233.32
 10581.5   239.1 10616.6   241.2   10979  245.69   11129  239.57 11437.4  244.89
#Mann= 9 ,-1 , 0
    1207     .05       0    1654     .16       0  1791.9     .05       0
  4332.1     .12       0    4943     .07       0  5073.9     .12       0
    6932     .16       0  6986.7     .12       0  9340.1     .16       0
#XS Ineff= 2 , 0
                          7186.1          193.58
Permanent Ineff=
       F       F
Bank Sta=4943,5073.9
XS Rating Curve= 0 ,0
Exp/Cntr=0.3,0.1

Type RM Length L Ch R = 1 ,198909  ,1077,1077,1077
BEGIN DESCRIPTION:
NAVASOTA RIVER 261
END DESCRIPTION:
XS GIS Cut Line= 3
      3604080.87     10206607.83      3601449.03     10205204.52
      3595837.13     10205036.94
#Sta/Elev= 30
  2017.4  259.16  2113.3   251.7    2273  238.53  2552.1  224.31  2659.5  220.75
  2954.2  212.82  3024.6  206.17  3092.6  215.78  3594.8  215.16    3825  209.52
  3934.8  198.32  4603.6  194.46  4927.3  194.77  4949.2  192.96  4976.6  183.46
  5026.9  184.41  5056.9   194.5  5287.1  195.57  5427.1  191.02  6565.8  192.05
  7192.3  194.56  7455.4   194.1  7758.2  198.55  8033.7  196.23    9629  190.06
 10049.2     194 10162.1   199.9 10215.3  210.44 10519.4  240.17 10614.4  243.08
#Mann= 14 ,-1 , 0
  2017.4     .05       0  2113.3     .16       0  2552.1     .05       0
  2659.5     .16       0  2954.2     .05       0  4603.6     .12       0
  4927.3     .07       0  5056.9     .12       0  6565.8     .16       0
  7192.3     .12       0  7455.4     .16       0  8033.7     .12       0
 10162.1     .16       0 10215.3     .05       0
#XS Ineff= 2 , 0
                          7756.7          198.52
Permanent Ineff=
       F       F
Bank Sta=4927.3,5056.9
XS Rating Curve= 0 ,0
Exp/Cntr=0.3,0.1

Type RM Length L Ch R = 1 ,197832  ,761,761,761
BEGIN DESCRIPTION:
NAVASOTA RIVER 262
END DESCRIPTION:
XS GIS Cut Line= 4
      3604822.12       10205586.      3603259.59      10204639.8
      3602234.45     10204525.35      3595586.35     10204043.94
#Sta/Elev= 30
  2141.8  244.86  2545.6  233.22    2829  231.95  2995.5  234.15  3310.9   226.9
  3614.8  234.24  3907.1  229.41  4106.8  231.93  4398.6  224.57  4700.5  229.85
  4812.2  224.62  4921.9  212.15    4952  199.37  4982.2  184.33  5022.1  183.75
  5062.5  193.83  5523.7  190.07  5671.7  193.58  6229.4  190.27  7703.3  194.13
  7839.8  198.66  8226.7  193.91  8321.9  193.74  8452.6  193.51  9403.8   189.6
 10516.1  192.42 10800.6  204.05 10967.9  224.08 11098.3  219.44 11665.5  246.78
#Mann= 9 ,-1 , 0
  2141.8     .05       0    2829     .16       0    4952     .07       0
  5062.5     .12       0  7703.3     .16       0  8226.7     .05       0
  8321.9     .16       0  8452.6     .12       0 10800.6     .05       0
#XS Ineff= 2 , 0
                          7839.2          198.65
Permanent Ineff=
       F       F
Bank Sta=4952,5062.5
XS Rating Curve= 0 ,0
Exp/Cntr=0.3,0.1

Type RM Length L Ch R = 1 ,197071  ,599,599,599
BEGIN DESCRIPTION:
NAVASOTA RIVER 263
END DESCRIPTION:
XS GIS Cut Line= 3
      3603528.51      10203866.8      3602274.03      10203784.2
      3595625.79     10203569.53
#Sta/Elev= 30
  3742.8     235  3927.9  228.61  4203.5  230.78  4520.3  227.04  4741.4  216.48
  4874.3  206.98  4911.7  199.72  4931.8  192.77  4941.8  193.22  4971.9  185.09
  4991.7  183.99  5041.9   184.8    5062  193.52  5070.7  193.85  5372.1  190.62
  5442.2  190.68  5472.2  193.59  5742.3  193.97    7498  191.94  7633.3  195.75
  8385.4   192.1  8645.8  194.53  8723.9  189.09  9265.8  189.49  9524.3  192.59
  9885.8  190.08 10786.6  196.17 10912.7  212.51 11235.2  248.33 11651.7  250.01
#Mann= 11 ,-1 , 0
  3742.8     .16       0  3927.9     .05       0  4520.3     .16       0
  4874.3     .12       0  4941.8     .07       0    5062     .16       0
  5070.7     .12       0    7498     .16       0  8385.4     .12       0
 10786.6     .16       0 10912.7     .05       0
#XS Ineff= 2 , 0
                         8648.45          194.51
Permanent Ineff=
       F       F
Bank Sta=4941.8,5062
XS Rating Curve= 0 ,0
Exp/Cntr=0.3,0.1