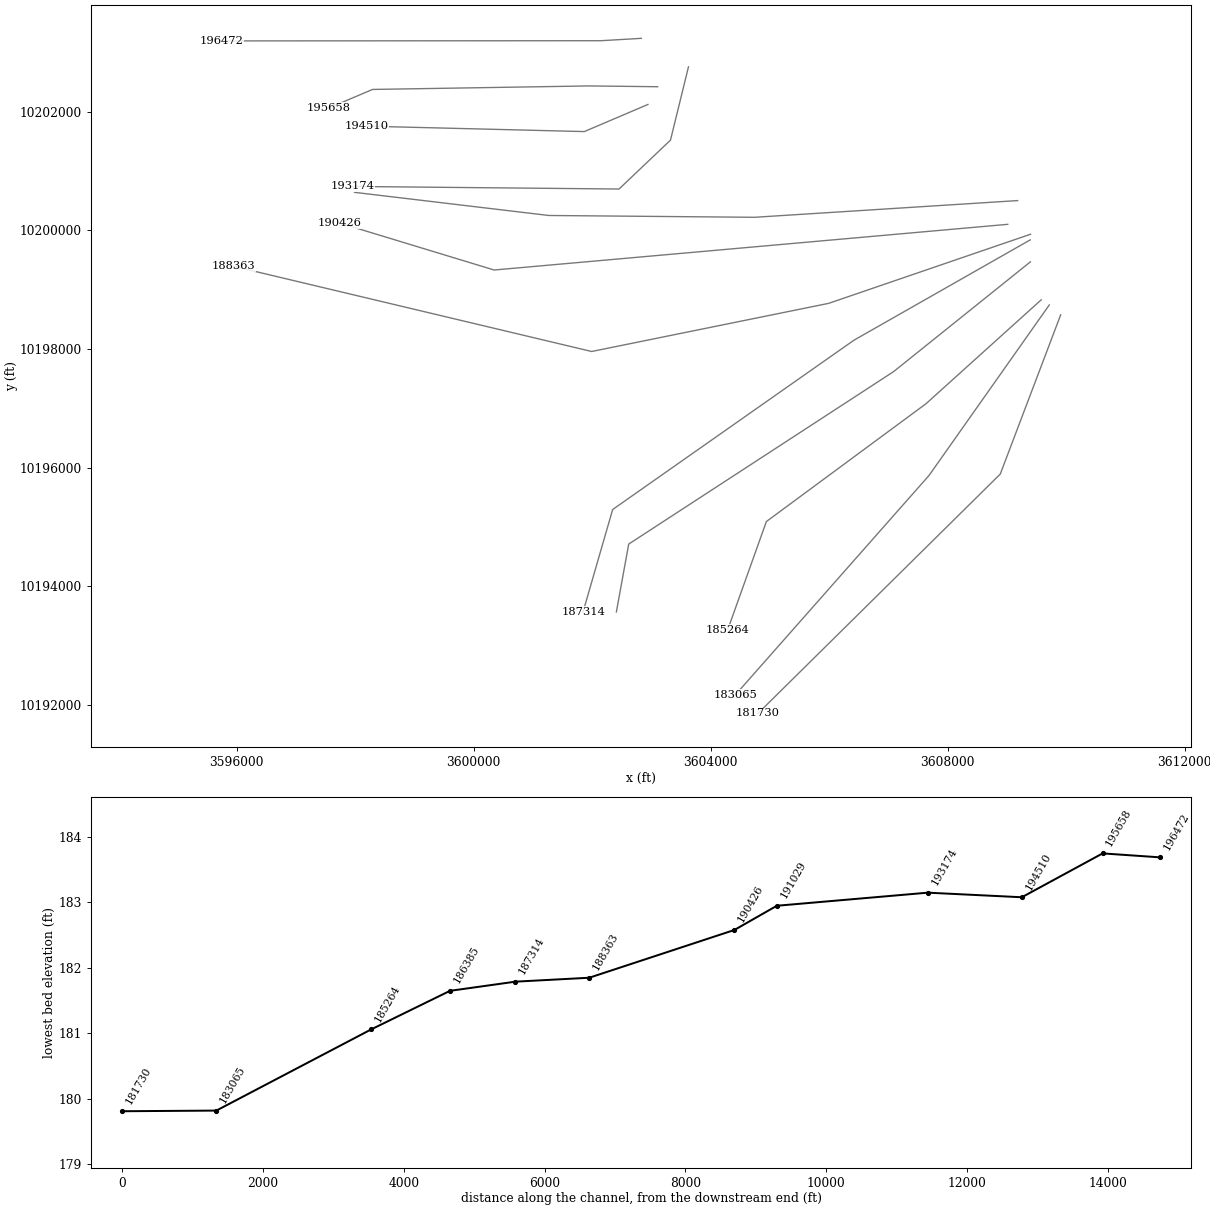
HEC-RAS study NAVASOTA RIVER.prj: NAVASOTA RIVER Base Level Engineering

--- NAVASOTA RIVER.g01 (geometry) --- (continued)

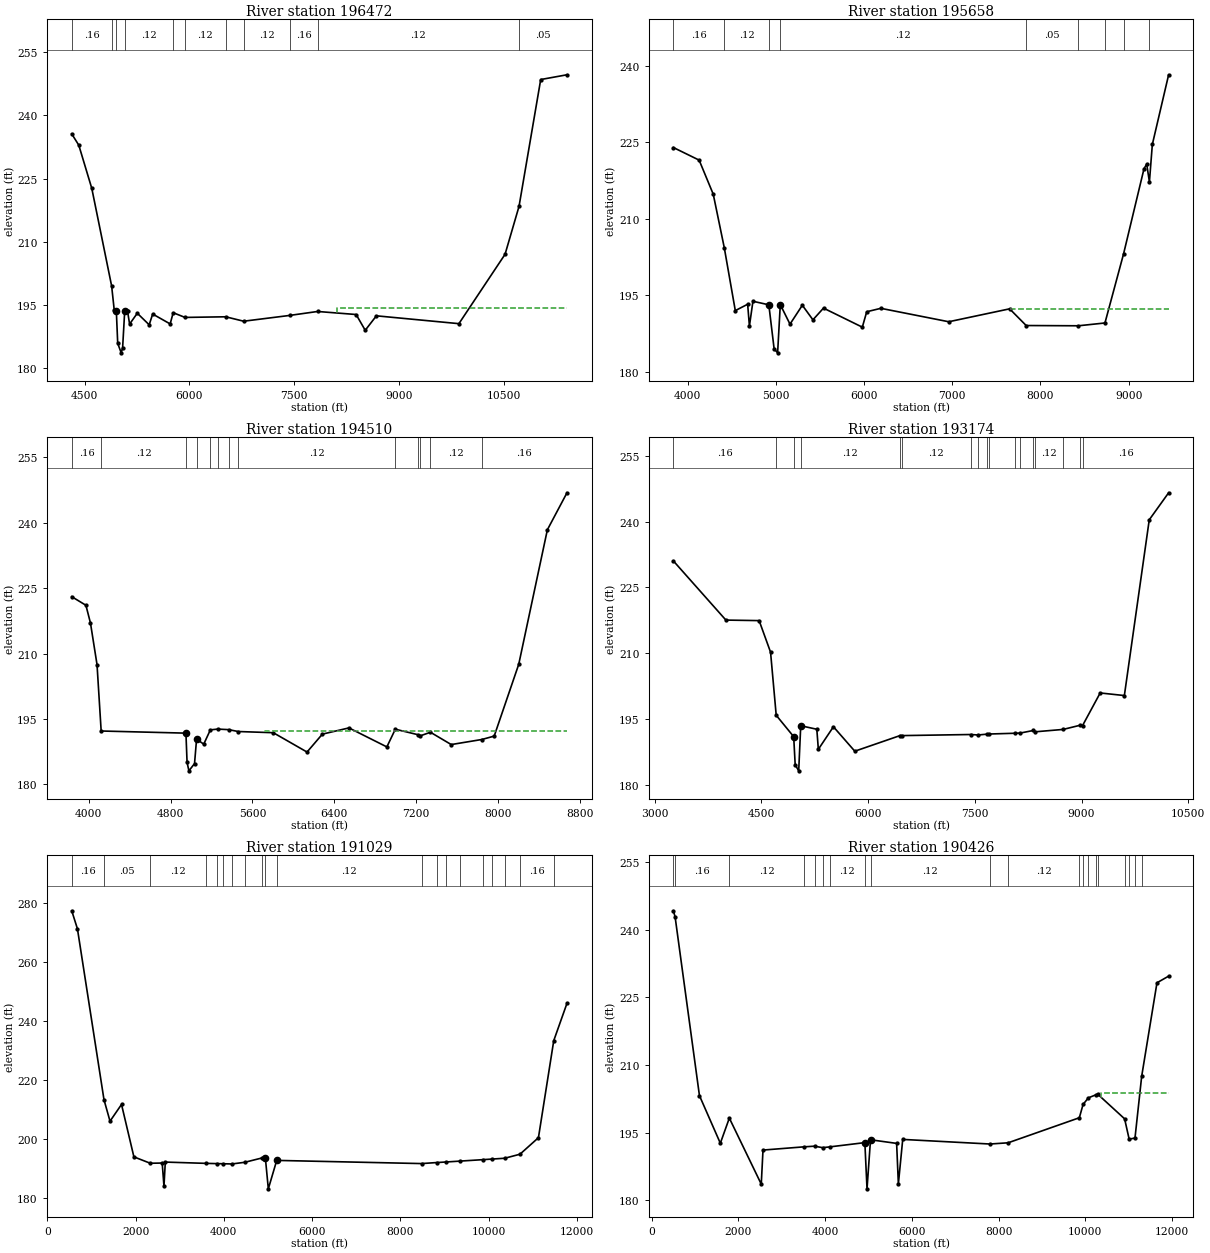
Type RM Length L Ch R = 1 ,196472  ,814,814,814
BEGIN DESCRIPTION:
NAVASOTA RIVER 264
END DESCRIPTION:
XS GIS Cut Line= 3
      3602828.53     10203242.52       3602145.9     10203202.43
      3595746.21     10203199.12
#Sta/Elev= 30
  4316.2  235.62  4417.1  232.94  4603.1  222.68    4887  199.53  4923.4  193.91
  4953.7  193.71  4973.8  185.94  5023.5  183.69  5043.8  184.87  5073.8  193.62
  5113.8  193.63  5143.8  190.51  5253.8  193.08  5423.8  190.34  5473.8  192.89
  5723.8  190.55  5767.4  193.21  5936.1  192.09  6518.4  192.24  6775.2  191.19
  7431.6  192.56  7832.8   193.5  8383.8  192.78  8513.8  189.04  8673.8  192.47
  9853.8  190.61 10513.8  207.06 10713.7  218.43 11023.8  248.51 11399.7  249.64
#Mann= 11 ,-1 , 0
  4316.2     .16       0    4887     .12       0  4953.7     .07       0
  5073.8     .12       0  5767.4     .07       0  5936.1     .12       0
  6518.4     .07       0  6775.2     .12       0  7431.6     .16       0
  7832.8     .12       0 10713.7     .05       0
#XS Ineff= 2 , 0
                         8104.61          194.39
Permanent Ineff=
       F       F
Bank Sta=4953.7,5073.8
XS Rating Curve= 0 ,0
Exp/Cntr=0.3,0.1

Type RM Length L Ch R = 1 ,195658  ,1148,1148,1148
BEGIN DESCRIPTION:
NAVASOTA RIVER 265
END DESCRIPTION:
XS GIS Cut Line= 4
       3603104.2     10202426.11      3601941.87     10202439.41
      3598292.27     10202380.11      3597553.23     10202066.01
#Sta/Elev= 30
  3837.6  223.97  4129.7   221.5  4289.7  214.82  4414.9  204.33  4539.7  192.02
  4679.7  193.27  4699.7     189  4739.8  193.85  4919.8  193.16  4979.8  184.54
  5019.5  183.75  5049.8   193.2  5159.8  189.37  5299.8  193.07  5419.8  190.22
  5539.8  192.51  5979.9  188.78  6029.9   191.8  6189.9  192.47    6960  189.84
  7650.1  192.37  7837.9   189.1  8429.8  189.05  8731.1   189.6  8942.1  203.13
  9173.8  219.81  9204.4  220.72  9235.3  217.24  9268.4  224.57  9453.1  238.22
#Mann= 9 ,-1 , 0
  3837.6     .16       0  4414.9     .12       0  4919.8     .07       0
  5049.8     .12       0  7837.9     .05       0  8429.8     .12       0
  8731.1     .16       0  8942.1     .12       0  9235.3     .05       0
#XS Ineff= 2 , 0
                         7650.16           192.4
Permanent Ineff=
       F       F
Bank Sta=4919.8,5049.8
XS Rating Curve= 0 ,0
Exp/Cntr=0.3,0.1

Type RM Length L Ch R = 1 ,194510  ,1336,1336,1336
BEGIN DESCRIPTION:
NAVASOTA RIVER 266
END DESCRIPTION:
XS GIS Cut Line= 3
      3602939.66     10202126.61      3601865.55     10201669.07
      3598190.29     10201760.63
#Sta/Elev= 30
  3832.5  223.04  3971.1  221.07  4015.6     217  4079.8  207.46  4120.3  192.22
  4949.4  191.73  4960.4  185.04  4978.4  183.08  5033.5  184.74  5053.5  190.36
  5123.5   189.2  5188.3  192.48  5260.4  192.66  5367.9  192.53  5461.3   192.1
  5803.7  191.83  6133.8  187.39  6283.8   191.5  6543.9  192.93  6914.6  188.57
  6997.3  192.63  7218.9  191.37    7242  191.12  7340.9  191.93  7544.2  189.11
  7843.1  190.27  7964.4  191.05  8204.4  207.52  8484.5  238.39  8676.4  246.88
#Mann= 13 ,-1 , 0
  3832.5     .16       0  4120.3     .12       0  4949.4     .07       0
  5053.5     .12       0  5188.3     .07       0  5260.4     .12       0
  5367.9     .07       0  5461.3     .12       0  6997.3     .07       0
  7218.9     .12       0    7242     .07       0  7340.9     .12       0
  7843.1     .16       0
#XS Ineff= 2 , 0
                         5724.06          192.29
Permanent Ineff=
       F       F
Bank Sta=4949.4,5053.5
XS Rating Curve= 0 ,0
Exp/Cntr=0.3,0.1

Type RM Length L Ch R = 1 ,193174  ,2145,2145,2145
BEGIN DESCRIPTION:
NAVASOTA RIVER 068
END DESCRIPTION:
XS GIS Cut Line= 4
      3603623.81     10202761.42        3603320.     10201524.47
      3602451.94     10200699.81      3597959.78     10200743.22
#Sta/Elev= 30
  3261.3  231.05  3999.7  217.55  4467.1  217.43  4627.6  210.23  4707.1  195.83
  4952.9  190.95  4973.9  184.54  5023.4  183.15  5051.9  193.44  5278.1  192.64
  5299.5  188.06  5511.5  193.21  5812.2  187.63  6449.4   191.2    6472  191.19
  7446.1  191.44  7543.2  191.33  7664.5  191.51  7698.2  191.55  8069.9  191.73
  8136.9  191.77  8323.5  192.36    8350  192.06  8741.5   192.6  8974.5  193.53
  9014.8  193.49  9262.3  200.92  9602.3  200.33  9952.4  240.44 10224.7   246.6
#Mann= 17 ,-1 , 0
  3261.3     .16       0  4707.1     .12       0  4952.9     .07       0
  5051.9     .12       0  6449.4     .07       0    6472     .12       0
  7446.1     .07       0  7543.2     .12       0  7664.5     .07       0
  7698.2     .12       0  8069.9     .07       0  8136.9     .12       0
  8323.5     .07       0    8350     .12       0  8741.5     .05       0
  8974.5     .12       0  9014.8     .16       0
Bank Sta=4952.9,5051.9
XS Rating Curve= 0 ,0
Exp/Cntr=0.3,0.1

Type RM Length L Ch R = 1 ,191029  ,603,603,603
BEGIN DESCRIPTION:
NAVASOTA RIVER 272
END DESCRIPTION:
XS GIS Cut Line= 4
      3609177.61     10200504.69      3604739.65     10200222.75
      3601267.26     10200253.28      3597988.44     10200643.58
#Sta/Elev= 30
   553.1  277.49     682  271.36  1283.8  213.25  1420.3  205.95  1680.9  211.64
  1961.4  193.82  2331.8  191.65  2602.7  191.72  2642.8  183.83  2672.9  192.05
  3594.4  191.61    3838  191.53  3979.4  191.48  4183.7  191.41  4475.6  191.98
  4855.7  193.42  4940.5  193.44  5007.3  182.95  5197.6  192.62  8478.4  191.54
  8828.2  191.89  9032.5  192.08    9351  192.38  9876.7  192.88 10076.5  193.07
 10363.5  193.35 10709.1  194.72 11127.5  200.34 11474.8  233.35 11774.5  246.04
#Mann= 20 ,-1 , 0
   553.1     .16       0  1283.8     .05       0  2331.8     .12       0
  3594.4     .07       0    3838     .12       0  3979.4     .05       0
  4183.7     .07       0  4475.6     .05       0  4855.7     .12       0
  4940.5     .07       0  5197.6     .12       0  8478.4     .12       0
  8828.2     .12       0  9032.5     .07       0    9351     .12       0
  9876.7     .12       0 10076.5     .12       0 10363.5     .05       0
 10709.1     .16       0 11474.8     .16       0
#XS Ineff= 2 , 0
         3173.06  191.34
Permanent Ineff=
       F       F
Bank Sta=4940.5,5197.6
XS Rating Curve= 0 ,0
Exp/Cntr=0.3,0.1

Type RM Length L Ch R = 1 ,190426  ,2063,2063,2063
BEGIN DESCRIPTION:
NAVASOTA RIVER 248
END DESCRIPTION:
XS GIS Cut Line= 3
      3609010.99     10200104.06      3600344.35     10199333.23
      3597740.18      10200124.9
#Sta/Elev= 30
   500.7  244.18   540.6  242.82  1101.9  203.23  1583.8  192.68  1791.2  198.25
  2527.6  183.62  2567.7  191.17  3507.5  191.88    3756  192.03  3944.6   191.7
  4103.2  191.87  4916.9  192.82  4966.9  182.58  5047.5  193.45  5649.8  192.65
    5690  183.66  5790.4  193.53  7803.1  192.51    8221  192.78    9864  198.33
  9950.6  201.29 10072.8  202.74 10249.9  203.43 10288.4  203.54 10908.2  198.09
 11012.6   193.6 11147.5  193.83 11301.8  207.51 11654.6  228.23 11923.4   229.7
#Mann= 20 ,-1 , 0
   500.7     .05       0   540.6     .16       0  1791.2     .12       0
  3507.5     .05       0    3756     .05       0  3944.6     .07       0
  4103.2     .12       0  4916.9     .07       0  5047.5     .12       0
  7803.1     .07       0    8221     .12       0    9864     .16       0
  9950.6     .12       0 10072.8     .16       0 10249.9     .12       0
 10288.4     .16       0 10908.2     .07       0 11012.6     .05       0
 11147.5     .05       0 11301.8     .16       0
#XS Ineff= 2 , 0
         3470.26  191.8510374.17          203.75
Permanent Ineff=
       F       F
Bank Sta=4916.9,5047.5
XS Rating Curve= 0 ,0
Exp/Cntr=0.3,0.1

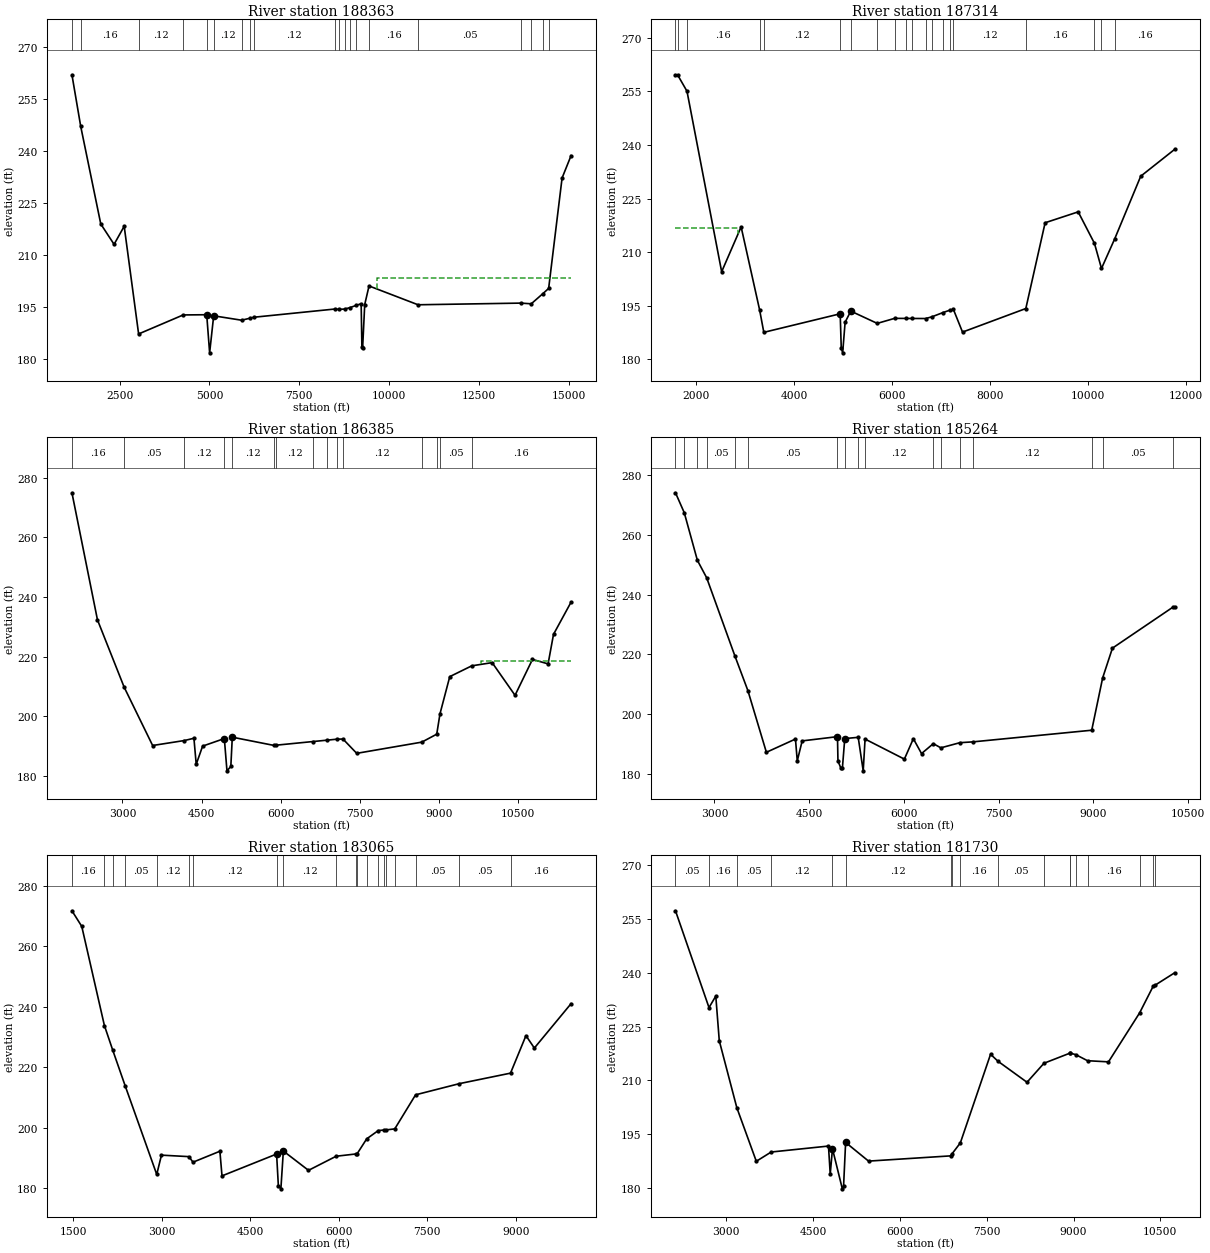
Type RM Length L Ch R = 1 ,188363  ,1049,1049,1049
BEGIN DESCRIPTION:
NAVASOTA RIVER 271
END DESCRIPTION:
XS GIS Cut Line= 4
      3609395.95     10199936.77      3605990.19     10198770.73
      3601990.19     10197958.23      3595948.48     10199395.74
#Sta/Elev= 30
  1172.5  261.97  1417.4  247.07  1975.1  218.98  2345.3  213.11  2626.9  218.32
  3028.3  187.29    4269  192.77  4923.5  192.83  5004.8  181.85  5117.3  192.52
  5894.1  191.25    6133  191.84  6238.8  192.11  8486.5  194.47  8601.2  194.38
  8760.6  194.46  8909.7  194.88  9084.9  195.53  9222.1  196.01  9242.7  183.47
  9263.2  183.36  9321.1  195.76  9441.1  201.12 10805.2   195.7 13663.6  196.18
 13956.2  195.98 14279.8  198.91 14440.1  200.41 14814.1  232.23 15064.4  238.68
#Mann= 20 ,-1 , 0
  1172.5     .05       0  1417.4     .16       0  3028.3     .12       0
    4269     .12       0  4923.5     .07       0  5117.3     .12       0
  5894.1     .12       0    6133     .07       0  6238.8     .12       0
  8486.5     .16       0  8601.2     .05       0  8760.6     .12       0
  8909.7     .16       0  9084.9     .12       0  9441.1     .16       0
 10805.2     .05       0 13663.6     .12       0 13956.2     .05       0
 14279.8     .12       0 14440.1     .05       0
#XS Ineff= 2 , 0
                         9664.23          203.44
Permanent Ineff=
       F       F
Bank Sta=4923.5,5117.3
XS Rating Curve= 0 ,0
Exp/Cntr=0.3,0.1

Type RM Length L Ch R = 1 ,187314  ,929,929,929
BEGIN DESCRIPTION:
NAVASOTA RIVER 270
END DESCRIPTION:
XS GIS Cut Line= 4
      3609390.08     10199841.25      3606415.18     10198148.27
      3602344.35     10195291.56      3601844.34     10193562.37
#Sta/Elev= 30
  1577.1  259.65  1619.1  259.68  1812.1  255.07  2520.2  204.51    2918  217.07
  3295.9   193.8  3381.3  187.53  4941.4  192.73  4963.1  183.22  4991.8  181.79
  5042.1  190.35    5158  193.48  5698.3  190.04  6053.7  191.45  6283.7  191.43
  6401.9  191.42  6686.7   191.4  6814.7  191.88  7038.8  193.06  7177.1  193.72
  7254.1  193.96  7440.5   187.6  8733.4   194.2  9127.8  218.23  9803.2  221.28
 10135.6  212.46   10279  205.42 10549.5  213.73 11080.5  231.26 11773.2  238.78
#Mann= 20 ,-1 , 0
  1577.1     .16       0  1619.1     .05       0  1812.1     .16       0
  3295.9     .05       0  3381.3     .12       0  4941.4     .07       0
    5158     .12       0  5698.3     .12       0  6053.7     .05       0
  6283.7     .12       0  6401.9      .1       0  6686.7     .07       0
  6814.7     .12       0  7038.8     .16       0  7177.1     .16       0
  7254.1     .12       0  8733.4     .16       0 10135.6     .08       0
   10279     .05       0 10549.5     .16       0
#XS Ineff= 2 , 0
       0  2858.9  216.73  9803.2       0  221.28
Permanent Ineff=
       F       F
Bank Sta=4941.4,5158
XS Rating Curve= 0 ,0
Exp/Cntr=0.3,0.1

Type RM Length L Ch R = 1 ,186385  ,1121,1121,1121
BEGIN DESCRIPTION:
NAVASOTA RIVER 269
END DESCRIPTION:
XS GIS Cut Line= 4
      3609393.12     10199470.69      3607086.53     10197619.62
      3602615.19     10194708.23      3602406.97     10193563.05
#Sta/Elev= 30
  2042.5  274.93  2526.5  232.28  3032.2   209.7  3571.4  190.15  4173.8  191.82
  4353.9  192.58  4397.1  183.84  4518.4  189.94    4930  192.48  4979.8  181.65
    5053  183.11  5080.8  192.94  5869.3  190.18  5907.2  190.25  6616.4  191.49
  6876.2  191.94  7063.2  192.27    7178  192.32  7438.3  187.52  8671.2  191.28
  8954.4  193.95  9015.8  200.78    9201  213.25  9618.4  216.88   10004  217.95
 10437.8  206.99 10768.1  219.03   11064  217.53 11167.1  227.45 11499.6  238.25
#Mann= 15 ,-1 , 0
  2042.5     .16       0  3032.2     .05       0  4173.8     .12       0
    4930     .07       0  5080.8     .12       0  5869.3     .07       0
  5907.2     .12       0  6616.4     .07       0  6876.2     .12       0
  7063.2     .07       0    7178     .12       0  8671.2     .05       0
  8954.4     .16       0  9015.8     .05       0  9618.4     .16       0
#XS Ineff= 2 , 0
       0                  9786.6       0  218.34
Permanent Ineff=
       F       F
Bank Sta=4930,5080.8
XS Rating Curve= 0 ,0
Exp/Cntr=0.3,0.1

Type RM Length L Ch R = 1 ,185264  ,2199,2199,2199
BEGIN DESCRIPTION:
NAVASOTA RIVER 268
END DESCRIPTION:
XS GIS Cut Line= 4
      3609575.84     10198830.06       3607633.4     10197077.95
       3604938.1     10195088.44      3604287.27     10193266.12
#Sta/Elev= 30
  2384.1  274.02    2523  267.36  2730.7  251.44  2877.4  245.61  3326.3  219.37
  3530.1  207.89  3822.9  187.26  4283.3  191.69  4311.7  184.38  4389.4  191.07
  4948.4  192.49  4955.9  184.32    5000  182.08  5026.5  182.05  5063.6  191.85
  5276.4  192.26  5355.6  181.06  5385.1  191.68  6007.3  184.98  6149.3   191.8
  6278.8  186.83  6465.2  190.15  6584.4  188.75  6885.8  190.47  7094.6  190.75
  8972.8  194.64  9145.8  212.13  9300.7  222.08 10251.8  235.69 10285.1  235.76
#Mann= 17 ,-1 , 0
  2384.1     .16       0    2523     .05       0  2730.7     .16       0
  2877.4     .05       0  3326.3     .16       0  3530.1     .05       0
  4948.4     .07       0  5063.6     .12       0  5276.4     .07       0
  5385.1     .12       0  6465.2     .07       0  6584.4     .12       0
  6885.8     .05       0  7094.6     .12       0  8972.8     .16       0
  9145.8     .05       0 10251.8     .16       0
Bank Sta=4948.4,5063.6
XS Rating Curve= 0 ,0
Exp/Cntr=0.3,0.1

Type RM Length L Ch R = 1 ,183065  ,1335,1335,1335
BEGIN DESCRIPTION:
NAVASOTA RIVER 267
END DESCRIPTION:
XS GIS Cut Line= 3
      3609712.31     10198743.69      3607683.75     10195867.36
      3604417.88     10192167.33
#Sta/Elev= 30
  1480.3  271.68  1646.7  266.53  2030.1  233.78  2169.9  225.72  2383.5  213.77
  2916.9  184.57  2996.4  190.95  3462.2  190.46  3530.9  188.62  3986.5  192.24
  4022.2   184.1    4947  191.32  4976.6  180.91  5019.5  179.82  5061.5  192.31
  5487.4  185.93  5955.7  190.59  6285.3  191.33  6309.3  191.35  6473.4  196.34
  6669.8  199.08    6759  199.23  6805.6   199.3  6948.5  199.62  7301.2  210.88
  8044.4  214.58  8909.4  218.04  9170.8  230.43    9313  226.33  9935.2     241
#Mann= 20 ,-1 , 0
  1480.3     .16       0  2030.1     .05       0  2169.9     .16       0
  2383.5     .05       0  2916.9     .12       0  3462.2     .07       0
  3530.9     .12       0    4947     .07       0  5061.5     .12       0
  5955.7     .05       0  6285.3     .16       0  6309.3     .05       0
  6473.4     .16       0  6669.8     .05       0    6759     .16       0
  6805.6     .05       0  6948.5     .16       0  7301.2     .05       0
  8044.4     .05       0  8909.4     .16       0
Bank Sta=4947,5061.5
XS Rating Curve= 0 ,0
Exp/Cntr=0.3,0.1

Type RM Length L Ch R = 1 ,181730  ,1627,1627,1627
BEGIN DESCRIPTION:
NAVASOTA RIVER 274
END DESCRIPTION:
XS GIS Cut Line= 3
       3609904.2     10198576.66      3608885.14     10195889.93
      3604797.01     10191851.72
#Sta/Elev= 30
  2126.5  257.22  2705.3  230.27  2822.5  233.47  2882.8  221.03    3186  202.39
  3522.2  187.48  3779.2  190.06  4768.6  191.72  4798.7  183.92  4837.7  190.96
  5007.7  179.81  5029.2  180.51  5064.6  192.73  5460.6  187.53  6879.9  188.99
  6898.4  189.47  7045.7   192.6  7567.8  217.28  7695.6  215.33  8197.1  209.48
  8489.8  214.77  8939.2  217.59  8940.4   217.6  9037.9  217.18    9242  215.48
  9604.3  215.16   10142   228.8 10378.3  236.29 10409.1  236.51 10746.3  239.95
#Mann= 18 ,-1 , 0
  2126.5     .05       0  2705.3     .16       0    3186     .05       0
  3779.2     .12       0  4837.7     .07       0  5064.6     .12       0
  6879.9     .07       0  6898.4     .12       0  7045.7     .16       0
  7695.6     .05       0  8489.8     .16       0  8939.2     .05       0
  8940.4     .16       0  9037.9     .05       0    9242     .16       0
   10142     .05       0 10378.3     .16       0 10409.1     .05       0
#XS Ineff= 2 , 0
       0                  7567.8       0  217.28
Permanent Ineff=
       F       F
Bank Sta=4837.7,5064.6
XS Rating Curve= 0 ,0
Exp/Cntr=0.3,0.1