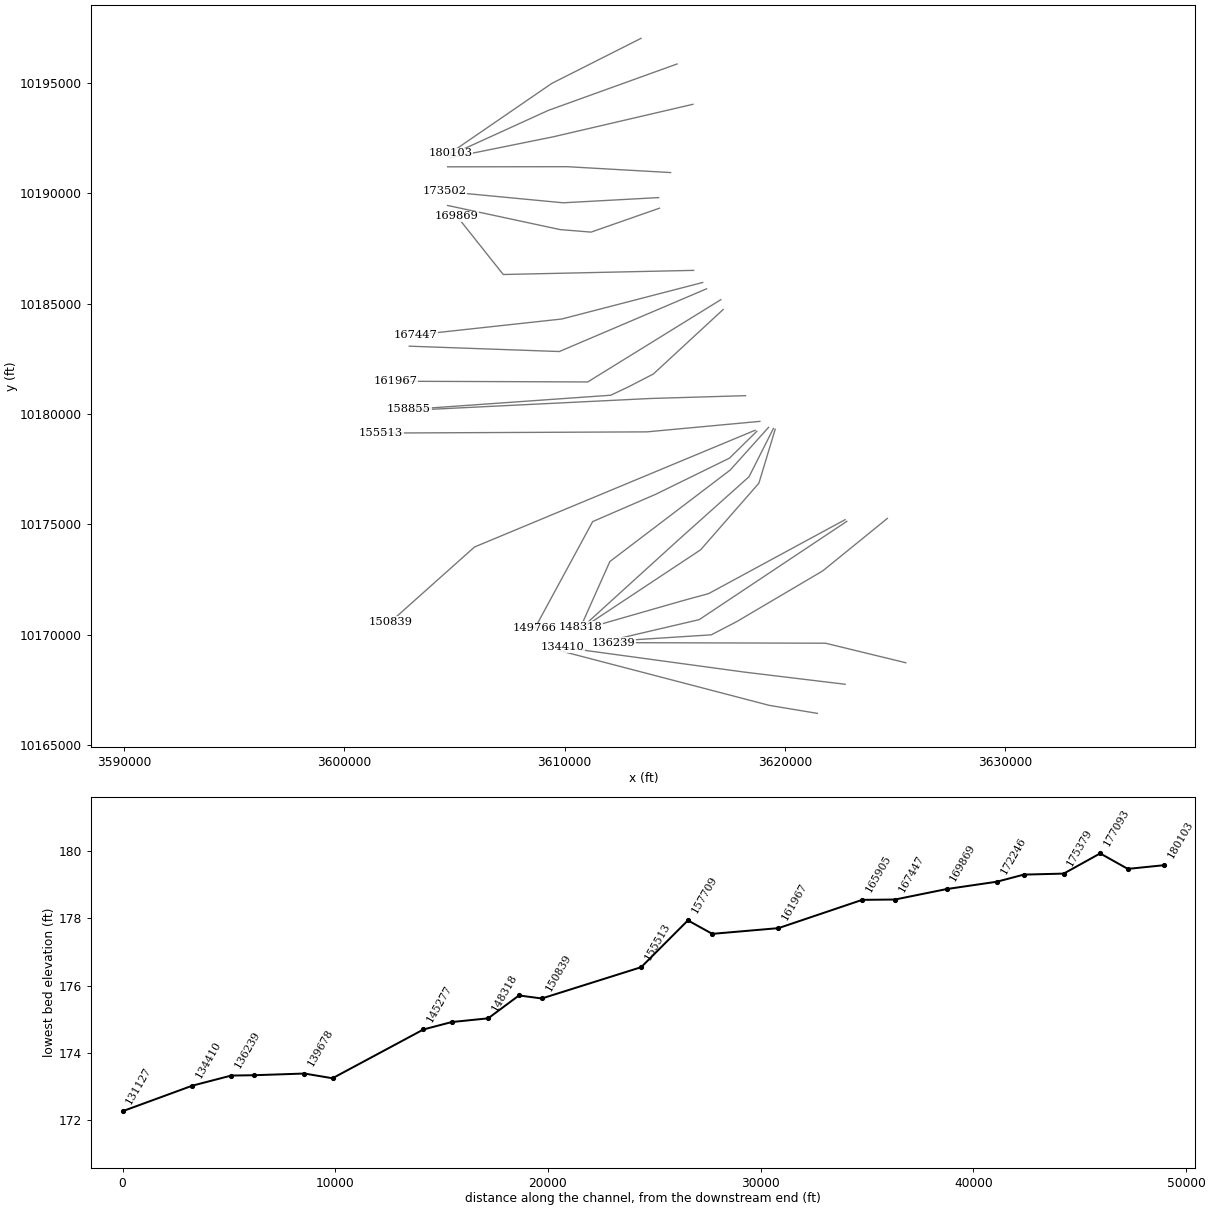
HEC-RAS study NAVASOTA RIVER.prj: NAVASOTA RIVER Base Level Engineering

--- NAVASOTA RIVER.g01 (geometry) --- (continued)

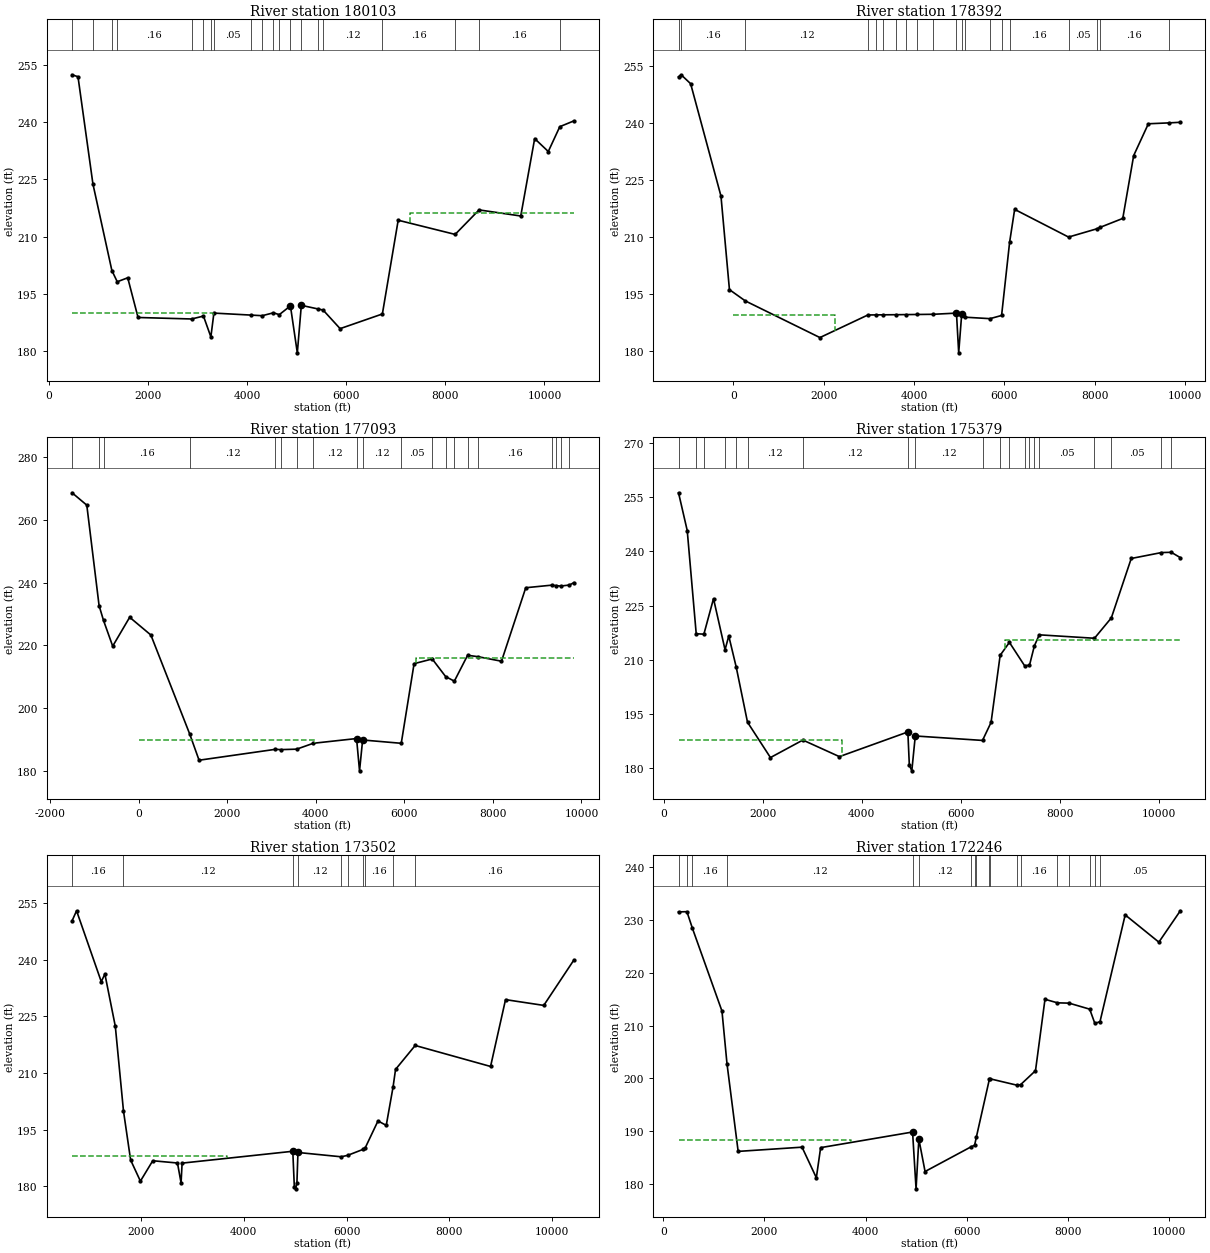
Type RM Length L Ch R = 1 ,180103  ,1711,1711,1711
BEGIN DESCRIPTION:
NAVASOTA RIVER 273
END DESCRIPTION:
XS GIS Cut Line= 3
      3613471.58     10197031.71      3609420.73     10194989.76
      3604806.63     10191827.91
#Sta/Elev= 30
   463.6  252.34   583.3  251.83   884.8  223.76  1267.2  201.12  1375.6  198.18
  1587.1  199.22  1795.6  188.83  2876.7  188.44  3116.2   189.2  3265.7  183.75
  3326.8  189.98  4085.6  189.45  4302.4   189.3  4529.9  190.06  4646.5  189.57
  4871.7  191.87  5010.8  179.58  5091.6  192.01  5418.9  191.09  5531.9  190.77
  5874.8  185.91  6727.9  189.75  7047.1  214.28  8196.7  210.57  8679.7  216.98
  9521.4  215.39  9802.3  235.64 10077.2  232.26 10309.6  238.76 10593.5  240.27
#Mann= 20 ,-1 , 0
   463.6     .16       0   884.8     .05       0  1267.2     .16       0
  1375.6     .16       0  2876.7     .12       0  3116.2     .07       0
  3265.7     .07       0  3326.8     .05       0  4085.6     .07       0
  4302.4     .07       0  4529.9     .12       0  4646.5     .12       0
  4871.7     .07       0  5091.6     .12       0  5418.9     .07       0
  5531.9     .12       0  6727.9     .16       0  8196.7     .05       0
  8679.7     .16       0 10309.6     .05       0
#XS Ineff= 2 , 0
       0 3316.17  189.97  7277.4       0  216.17
Permanent Ineff=
       F       F
Bank Sta=4871.7,5091.6
XS Rating Curve= 0 ,0
Exp/Cntr=0.3,0.1

Type RM Length L Ch R = 1 ,178392  ,1299,1299,1299
BEGIN DESCRIPTION:
NAVASOTA RIVER 275
END DESCRIPTION:
XS GIS Cut Line= 3
      3615105.66     10195868.51      3609260.14     10193764.93
      3604808.36     10191738.73
#Sta/Elev= 30
 -1212.5  252.13 -1154.9  252.68  -944.8  250.33  -273.5  220.74   -86.1  196.11
   265.4  193.14  1915.9  183.49  2977.7  189.44  3147.5  189.46  3317.5  189.48
  3598.4  189.51  3818.4  189.54  4070.2  189.57  4425.9  189.62  4937.7  189.93
    4987  179.47  5052.8  189.58  5119.2  188.86    5680  188.47  5936.2  189.31
  6113.5  208.58    6225  217.24  7418.1  209.95    8045  212.13    8119  212.52
  8617.5  214.86    8859  231.41  9183.9  239.78  9629.7  240.01  9891.2  240.17
#Mann= 20 ,-1 , 0
 -1212.5     .05       0 -1154.9     .16       0   265.4     .12       0
  2977.7     .07       0  3147.5     .07       0  3317.5     .05       0
  3598.4     .12       0  3818.4     .07       0  4070.2     .05       0
  4425.9     .12       0  4937.7     .07       0  5052.8     .12       0
  5119.2     .12       0    5680     .12       0  5936.2     .16       0
  6113.5     .16       0  7418.1     .05       0    8045     .05       0
    8119     .16       0  9629.7     .05       0
#XS Ineff= 2 , 0
       0 2246.09  189.37    6225       0  217.24
Permanent Ineff=
       F       F
Bank Sta=4937.7,5052.8
XS Rating Curve= 0 ,0
Exp/Cntr=0.3,0.1

Type RM Length L Ch R = 1 ,177093  ,1714,1714,1714
BEGIN DESCRIPTION:
NAVASOTA RIVER 276
END DESCRIPTION:
XS GIS Cut Line= 3
      3615825.75     10194040.83      3609491.04     10192568.75
      3604758.13     10191612.27
#Sta/Elev= 30
 -1503.5  268.69 -1170.9  264.74  -893.5  232.68  -793.1  227.93    -586  219.73
  -202.4  228.95   276.3  223.28  1154.2  191.65  1364.6  183.32  3088.4   186.8
  3208.4   186.7  3569.2  186.85  3944.6  188.73  4921.4  190.24  4988.4  179.93
  5058.1  189.78  5930.6  188.72  6220.2  214.14    6630  215.64    6934     210
  7129.6  208.56  7429.3  216.82  7663.3  216.37  8194.2  214.92  8742.2  238.38
  9327.7   239.2  9427.6  239.05  9527.5  238.91  9727.3  239.24  9828.6     240
#Mann= 20 ,-1 , 0
 -1503.5     .05       0  -893.5     .08       0  -793.1     .16       0
  1154.2     .12       0  3088.4     .05       0  3208.4     .12       0
  3569.2     .05       0  3944.6     .12       0  4921.4     .07       0
  5058.1     .12       0  5930.6     .05       0    6630     .16       0
    6934     .05       0  7129.6     .16       0  7429.3     .05       0
  7663.3     .16       0  9327.7      .1       0  9427.6     .05       0
  9527.5     .16       0  9727.3     .05       0
#XS Ineff= 2 , 0
       0 3982.09  189.65  6270.9       0     216
Permanent Ineff=
       F       F
Bank Sta=4921.4,5058.1
XS Rating Curve= 0 ,0
Exp/Cntr=0.3,0.1

Type RM Length L Ch R = 1 ,175379  ,1877,1877,1877
BEGIN DESCRIPTION:
NAVASOTA RIVER 277
END DESCRIPTION:
XS GIS Cut Line= 3
      3614814.59     10190946.82      3610124.42     10191212.69
      3604690.92     10191207.24
#Sta/Elev= 30
   302.3  256.22   477.9  245.77   659.2  217.24   814.1  217.12  1008.4  226.94
  1241.4  212.81  1316.4  216.63  1466.5  208.04  1694.7  192.78  2157.8     183
  2812.6  187.84    3550  183.26  4932.2  190.08  4962.2   180.9  5012.1  179.33
  5082.3  188.97  6439.6  187.74  6612.3  192.72  6795.7  211.27  6982.7  214.85
  7289.2   208.4  7387.9  208.52  7486.6  213.88  7585.3  216.94    8700  215.99
  9040.5  221.62  9442.3  238.05 10052.9  239.69 10250.4  239.76 10433.5  238.29
#Mann= 20 ,-1 , 0
   302.3     .05       0   659.2     .16       0   814.1     .16       0
  1241.4     .05       0  1466.5     .16       0  1694.7     .12       0
  2812.6     .12       0  4932.2     .07       0  5082.3     .12       0
  6439.6     .16       0  6795.7      .1       0  6982.7      .1       0
  7289.2     .05       0  7387.9     .12       0  7486.6     .16       0
  7585.3     .05       0    8700     .16       0  9040.5     .05       0
 10052.9      .1       0 10250.4     .05       0
#XS Ineff= 2 , 0
       0 3612.09   187.8  6892.3       0  215.46
Permanent Ineff=
       F       F
Bank Sta=4932.2,5082.3
XS Rating Curve= 0 ,0
Exp/Cntr=0.3,0.1

Type RM Length L Ch R = 1 ,173502  ,1256,1256,1256
BEGIN DESCRIPTION:
NAVASOTA RIVER 278
END DESCRIPTION:
XS GIS Cut Line= 3
      3614269.42     10189812.28      3609935.24     10189576.27
      3604539.01     10190089.62
#Sta/Elev= 30
   659.4  250.27   746.8  252.94  1227.6  234.16  1297.7  236.19  1500.8  222.33
  1659.7   199.9  1798.4  186.93  1988.7  181.34    2229  186.74  2709.7  186.14
  2779.9  180.88  2799.9  186.11  4953.1  189.25  4983.1  179.83  5005.8   179.3
  5033.3  180.84  5053.4  188.93  5892.8  187.79  6020.7  188.17  6320.2  189.75
  6356.1  189.99  6610.4  197.28  6771.1  196.11    6904   206.3  6951.9  210.93
  7334.1  217.27  8800.2  211.71  9091.5  229.41  9834.9  227.88 10420.6  239.89
#Mann= 10 ,-1 , 0
   659.4     .16       0  1659.7     .12       0  4953.1     .07       0
  5053.4     .12       0  5892.8     .05       0  6020.7     .12       0
  6320.2     .05       0  6356.1     .16       0    6904     .05       0
  7334.1     .16       0
#XS Ineff= 2 , 0
         3664.12  188.03
Permanent Ineff=
       F       F
Bank Sta=4953.1,5053.4
XS Rating Curve= 0 ,0
Exp/Cntr=0.3,0.1

Type RM Length L Ch R = 1 ,172246  ,2377,2377,2377
BEGIN DESCRIPTION:
NAVASOTA RIVER 279
END DESCRIPTION:
XS GIS Cut Line= 4
      3614305.32     10189330.64      3611201.12     10188247.29
      3609794.62     10188362.21      3604685.75     10189456.29
#Sta/Elev= 30
     301  231.53   466.7  231.57     575  228.44    1160  212.75  1259.2  202.79
  1480.1  186.18  2743.4  186.98  3026.4  181.19  3111.2  186.89  4929.5  189.85
  4998.5  179.09  5053.7  188.51  5176.4  182.37  6091.1  187.07  6155.8  187.33
  6192.9  188.97  6450.6  199.93  6460.1  199.93  7000.6   198.7  7067.3  198.83
  7360.5  201.46    7548  214.98  7794.7  214.31  8025.4  214.25  8432.6  213.11
  8534.4  210.41  8636.2  210.75  9134.2  230.96  9800.3   225.8 10224.7  231.74
#Mann= 18 ,-1 , 0
     301     .16       0   466.7     .05       0     575     .16       0
  1259.2     .12       0  4929.5     .07       0  5053.7     .12       0
  6091.1     .05       0  6155.8     .12       0  6192.9     .16       0
  6450.6     .05       0  6460.1     .16       0  7000.6     .05       0
  7067.3     .16       0  7794.7     .05       0  8025.4     .16       0
  8432.6     .12       0  8534.4     .07       0  8636.2     .05       0
#XS Ineff= 2 , 0
         3719.53  188.37
Permanent Ineff=
       F       F
Bank Sta=4929.5,5053.7
XS Rating Curve= 0 ,0
Exp/Cntr=0.3,0.1

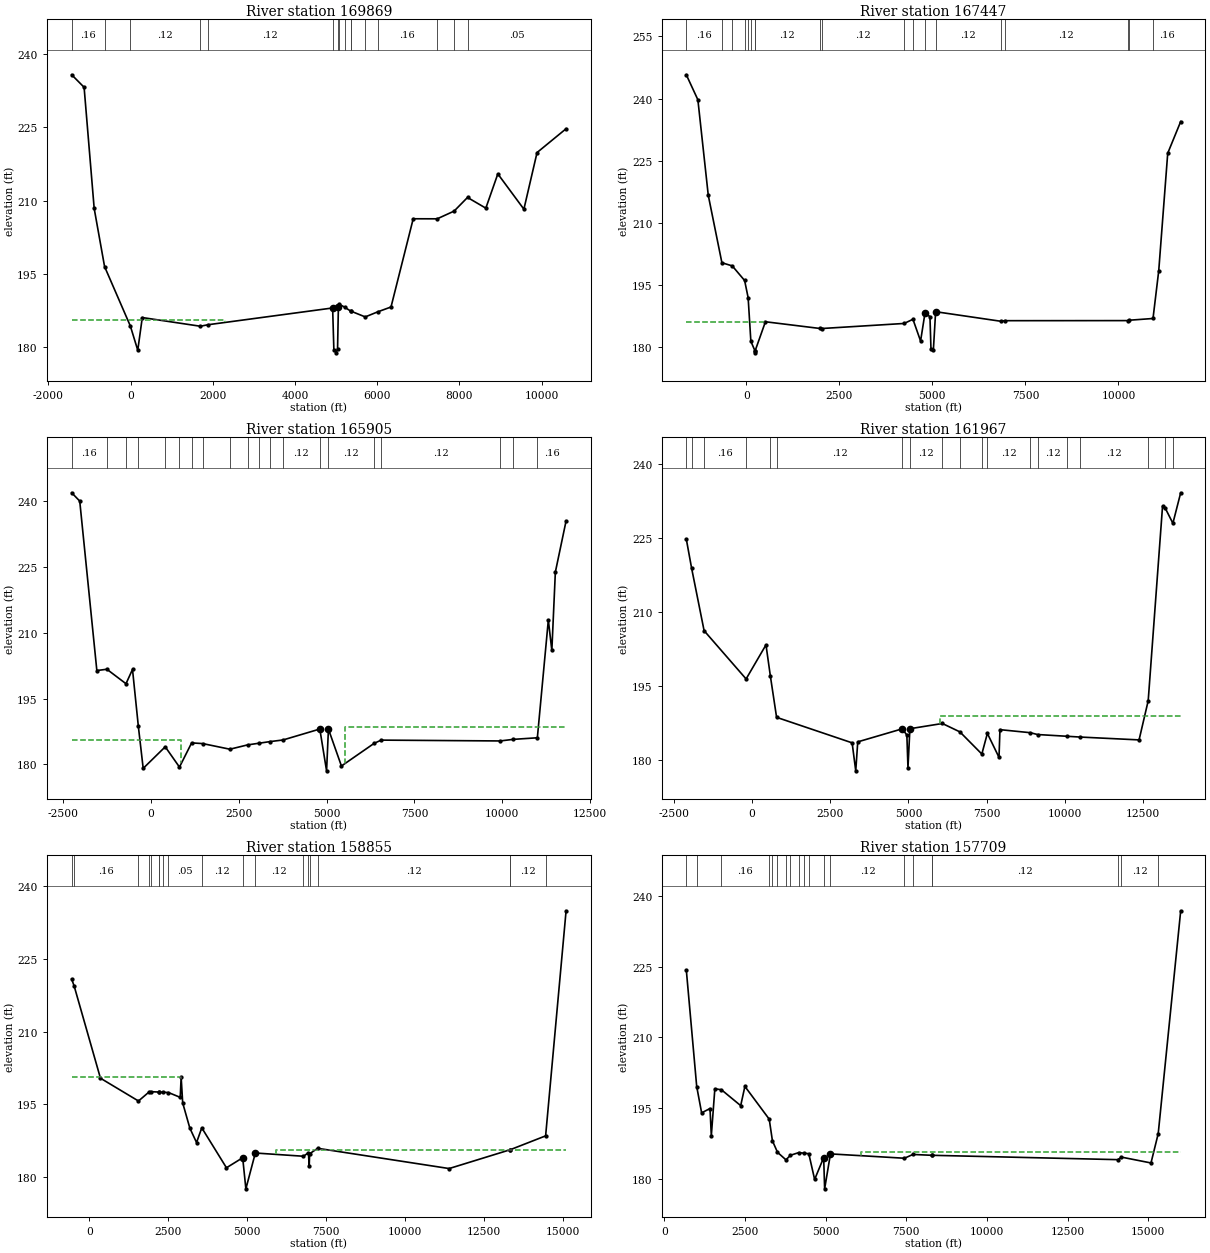
Type RM Length L Ch R = 1 ,169869  ,2422,2422,2422
BEGIN DESCRIPTION:
NAVASOTA RIVER 069
END DESCRIPTION:
XS GIS Cut Line= 3
      3615859.01     10186513.18      3607213.23     10186325.68
      3605109.09     10188971.48
#Sta/Elev= 30
   -1431  235.76 -1129.2   233.2    -884  208.41  -631.3  196.52      -4  184.36
   176.3   179.4   286.3  186.09  1700.5  184.31    1885  184.62  4917.4  188.05
  4947.4  179.49  5007.2  178.87  5037.4  179.75  5057.4  188.19  5076.8  188.84
  5208.2  188.22  5352.9  187.43  5374.2  187.36  5710.8  186.22  6009.1  187.24
  6337.7  188.25  6877.9   206.3  7461.2  206.29    7873  207.87    8199  210.66
  8644.7  208.47  8936.5  215.48  9570.6  208.26    9891  219.85 10597.3  224.72
#Mann= 16 ,-1 , 0
   -1431     .16       0  -631.3     .05       0      -4     .12       0
  1700.5     .07       0    1885     .12       0  4917.4     .07       0
  5057.4     .16       0  5076.8     .12       0  5208.2     .16       0
  5352.9     .05       0  5374.2     .16       0  5710.8     .12       0
  6009.1     .16       0  7461.2     .05       0    7873     .16       0
    8199     .05       0
#XS Ineff= 2 , 0
         2300.71  185.69
Permanent Ineff=
       F       F
Bank Sta=4917.4,5057.4
XS Rating Curve= 0 ,0
Exp/Cntr=0.3,0.1

Type RM Length L Ch R = 1 ,167447  ,1542,1542,1542
BEGIN DESCRIPTION:
NAVASOTA RIVER 280
END DESCRIPTION:
XS GIS Cut Line= 3
      3616270.24     10185963.96      3609869.75     10184307.77
      3603235.59     10183586.07
#Sta/Elev= 30
 -1611.3  245.75 -1300.4  239.71 -1021.2  216.63  -654.9  200.33  -376.8  199.57
   -44.4  196.04      50   191.9   123.3  181.35   232.7  179.06   235.5  178.56
   238.7  179.06   514.6  186.07  1968.8  184.46  2035.4  184.44  4242.4  185.66
  4478.5  186.67  4683.8  181.41  4800.5  188.08  4935.6  187.33    4963  179.49
  5027.8  179.29  5088.2   188.5  6832.1   186.2  6941.9  186.33 10257.4  186.35
 10273.4  186.43 10929.4  186.86 11083.3  198.41 11324.7  226.79 11673.3  234.45
#Mann= 19 ,-1 , 0
 -1611.3     .16       0  -654.9     .05       0  -376.8     .16       0
   -44.4     .12       0      50     .16       0   123.3     .12       0
   232.7     .07       0   238.7     .12       0  1968.8     .07       0
  2035.4     .12       0  4242.4     .07       0  4478.5     .12       0
  4800.5     .07       0  5088.2     .12       0  6832.1     .07       0
  6941.9     .12       0 10257.4     .07       0 10273.4     .12       0
 10929.4     .16       0
#XS Ineff= 2 , 0
          515.32   186.1
Permanent Ineff=
       F       F
Bank Sta=4800.5,5088.2
XS Rating Curve= 0 ,0
Exp/Cntr=0.3,0.1

Type RM Length L Ch R = 1 ,165905  ,3938,3938,3938
BEGIN DESCRIPTION:
NAVASOTA RIVER 281
END DESCRIPTION:
XS GIS Cut Line= 3
      3616446.08     10185677.07      3609762.09     10182833.81
       3602946.6     10183076.35
#Sta/Elev= 30
 -2263.6  241.81 -2034.5  239.92 -1547.3  201.37 -1261.5  201.66    -717  198.37
  -531.4  201.62  -364.8  188.65  -227.1  179.11   401.1  184.02   806.3   179.4
  1152.8  184.91  1468.5  184.75  2242.1  183.47  2745.1  184.45  3069.4  184.83
  3384.4   185.2    3755  185.57  4804.4  188.06    4997  178.55    5050  188.04
  5420.2  179.65  6351.4   184.8  6552.6  185.54  9942.6  185.35 10312.4  185.71
 11001.3  186.07   11314  212.86   11414  205.94 11514.1  223.77 11819.8  235.41
#Mann= 20 ,-1 , 0
 -2263.6     .16       0 -1261.5     .05       0    -717     .16       0
  -364.8     .12       0   401.1     .12       0   806.3     .12       0
  1152.8     .07       0  1468.5     .12       0  2242.1     .12       0
  2745.1     .12       0  3069.4     .12       0  3384.4     .07       0
    3755     .12       0  4804.4     .07       0    5050     .12       0
  6351.4     .07       0  6552.6     .12       0  9942.6     .07       0
 10312.4     .12       0 11001.3     .16       0
#XS Ineff= 2 , 0
          859.73  185.49 5518.79          188.42
Permanent Ineff=
       F       F
Bank Sta=4804.4,5050
XS Rating Curve= 0 ,0
Exp/Cntr=0.3,0.1

Type RM Length L Ch R = 1 ,161967  ,3112,3112,3112
BEGIN DESCRIPTION:
NAVASOTA RIVER 282
END DESCRIPTION:
XS GIS Cut Line= 3
      3617095.69     10185185.19      3611050.94     10181455.09
       3602340.9     10181487.13
#Sta/Elev= 30
   -2103  224.75 -1933.6  218.85   -1534  206.16  -190.4  196.36   445.6  203.28
   586.6  196.92   784.7  188.57  3200.8  183.39  3316.6  177.71  3380.7  183.59
  4805.7  186.24  4951.6  184.96  4986.9  178.34  5048.8  186.26  6086.5  187.32
  6647.2  185.62  7349.4  181.12  7526.6  185.31  7898.9  180.44  7928.9  186.07
  8901.3  185.45  9131.1  185.08 10088.3  184.72 10487.2  184.57 12378.9  183.99
 12670.6  191.94 13128.9  231.37 13218.6  230.99 13460.4  227.96 13710.1  234.15
#Mann= 19 ,-1 , 0
   -2103     .05       0 -1933.6     .05       0   -1534     .16       0
  -190.4     .05       0   586.6     .16       0   784.7     .12       0
  4805.7     .07       0  5048.8     .12       0  6086.5     .16       0
  6647.2     .12       0  7349.4     .07       0  7526.6     .12       0
  8901.3     .07       0  9131.1     .12       0 10088.3     .07       0
 10487.2     .12       0 12670.6     .05       0 13218.6     .16       0
 13460.4     .05       0
#XS Ineff= 2 , 0
          445.64  203.26 6009.03          188.74
Permanent Ineff=
       F       F
Bank Sta=4805.7,5048.8
XS Rating Curve= 0 ,0
Exp/Cntr=0.3,0.1

Type RM Length L Ch R = 1 ,158855  ,1146,1146,1146
BEGIN DESCRIPTION:
NAVASOTA RIVER 283
END DESCRIPTION:
XS GIS Cut Line= 5
       3617201.2     10184739.26      3614032.42     10181816.49
      3612925.84     10181245.06      3612096.65     10180852.95
      3602937.91     10180207.18
#Sta/Elev= 30
  -556.3  220.84    -478  219.42     354  200.39  1558.1  195.68  1906.5  197.62
  1946.9  197.61  2206.1  197.53  2209.2  197.53  2335.7  197.49  2508.4  197.43
  2880.8  196.43  2909.2  200.62  2958.5  195.28  3184.8  190.08  3397.4   187.1
  3562.5  190.14  4344.3  181.89  4857.9  183.96  4958.9  177.54  5258.8  184.94
    6783  184.27  6940.1     185  6964.4  182.23  6977.1  184.78  7232.1  185.91
 11395.3  181.73 13315.1  185.59 13318.3  185.59 14450.7  188.48 15098.7  234.97
#Mann= 19 ,-1 , 0
  -556.3     .05       0    -478     .16       0  1558.1     .05       0
  1906.5     .08       0  1946.9     .05       0  2206.1     .08       0
  2209.2     .05       0  2335.7     .08       0  2508.4     .05       0
  3562.5     .12       0  4857.9     .07       0  5258.8     .12       0
    6783     .07       0  6940.1     .12       0  6977.1     .07       0
  7232.1     .12       0 13315.1     .07       0 13318.3     .12       0
 14450.7     .16       0
#XS Ineff= 2 , 0
         2906.58  200.66 5925.66          185.64
Permanent Ineff=
       F       F
Bank Sta=4857.9,5258.8
XS Rating Curve= 0 ,0
Exp/Cntr=0.3,0.1

Type RM Length L Ch R = 1 ,157709  ,2196,2196,2196
BEGIN DESCRIPTION:
NAVASOTA RIVER 284
END DESCRIPTION:
XS GIS Cut Line= 3
      3618216.63     10180832.88      3613903.62     10180705.47
      3602912.72     10180164.47
#Sta/Elev= 30
   685.1   224.3  1007.2  199.61  1159.8  194.03  1419.9  194.95    1460  189.17
  1569.4  199.12  1771.5  198.93  2370.4  195.56  2500.4  199.63  3254.7  192.69
  3353.3  188.12  3510.6  185.68  3772.4  184.08  3912.8  185.05    4168  185.61
  4321.3   185.5  4480.5  185.38  4661.4  179.93  4941.5  184.56  4971.2  177.94
  5151.7  185.34  7443.7  184.42  7707.4  185.22  8301.8  185.04  8310.2  185.04
 14057.9  184.12 14166.6  184.66 15083.7  183.42 15307.4  189.62 16004.2  236.82
#Mann= 20 ,-1 , 0
   685.1     .05       0  1007.2     .12       0  1771.5     .16       0
  3254.7     .08       0  3353.3     .05       0  3510.6     .12       0
  3772.4     .05       0  3912.8     .05       0    4168     .12       0
  4321.3     .05       0  4480.5     .12       0  4941.5     .07       0
  5151.7     .12       0  7443.7     .07       0  7707.4     .12       0
  8301.8     .07       0  8310.2     .12       0 14057.9     .07       0
 14166.6     .12       0 15307.4     .16       0
#XS Ineff= 2 , 0
         2502.53  199.54 6085.46          185.68
Permanent Ineff=
       F       F
Bank Sta=4941.5,5151.7
XS Rating Curve= 0 ,0
Exp/Cntr=0.3,0.1

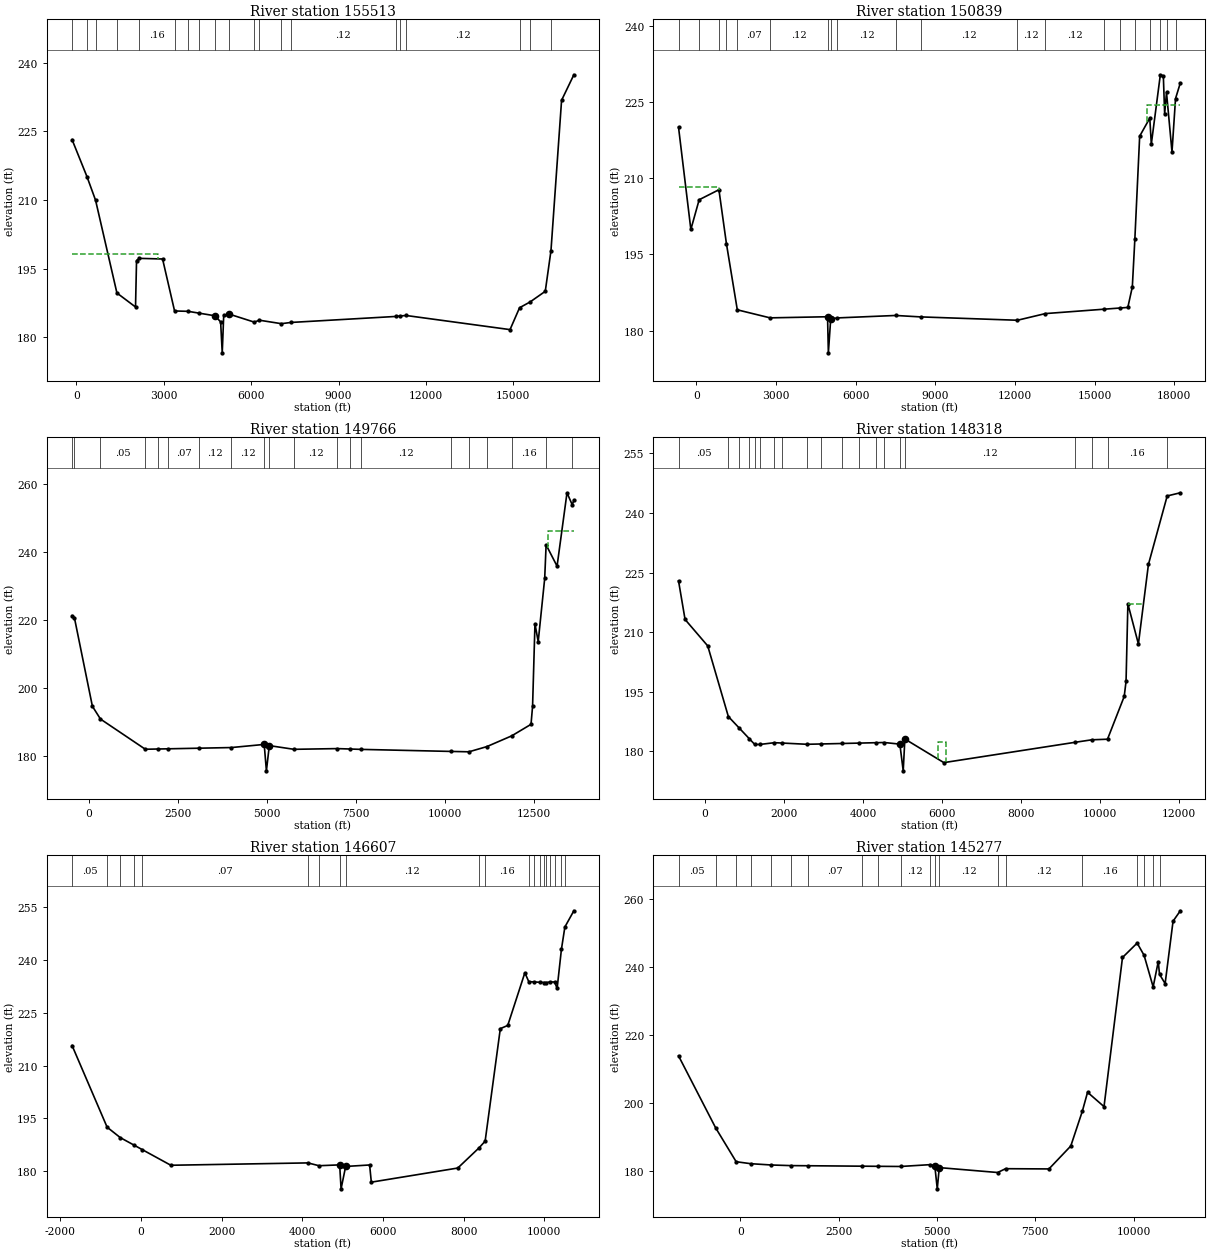
Type RM Length L Ch R = 1 ,155513  ,4674,4674,4674
BEGIN DESCRIPTION:
NAVASOTA RIVER 285
END DESCRIPTION:
XS GIS Cut Line= 3
      3618866.25     10179667.98       3613737.3     10179191.93
      3601660.52     10179138.04
#Sta/Elev= 30
    -151  223.19   359.7  215.11     656  209.93  1388.9  189.64  2027.5  186.58
  2062.6  196.74  2156.6  197.22  2956.4  197.08  3368.1  185.71    3833  185.63
  4211.7  185.23  4754.1  184.66  4949.5  183.32  5004.9  176.55  5055.2  184.73
  5235.2  185.04  6104.5  183.27  6279.2  183.69  7033.1  182.93  7368.7   183.2
 10960.8  184.51 11091.9  184.61 11317.8  184.72 14885.3  181.63 15212.8  186.42
   15574  187.68 16095.3  190.01 16290.9  198.89 16655.3   231.8 17076.9  237.38
#Mann= 20 ,-1 , 0
    -151     .05       0   359.7     .08       0     656     .05       0
  1388.9     .12       0  2156.6     .16       0  3368.1     .05       0
    3833     .05       0  4211.7     .12       0  4754.1     .07       0
  5235.2     .12       0  6104.5     .07       0  6279.2     .12       0
  7033.1     .12       0  7368.7     .12       0 10960.8     .16       0
 11091.9     .12       0 11317.8     .12       0 15212.8     .05       0
   15574     .12       0 16290.9     .05       0
#XS Ineff= 2 , 0
          2787.6  198.17
Permanent Ineff=
       F       F
Bank Sta=4754.1,5235.2
XS Rating Curve= 0 ,0
Exp/Cntr=0.3,0.1

Type RM Length L Ch R = 1 ,150839  ,1073,1073,1073
BEGIN DESCRIPTION:
NAVASOTA RIVER 210
END DESCRIPTION:
XS GIS Cut Line= 4
      3618648.14     10179263.77       3613405.9      10177086.5
      3605909.46     10173972.99        3602090.      10170570.2
#Sta/Elev= 30
  -676.4  219.98  -212.1  199.89   100.8  205.73   845.3   207.7  1128.1   197.1
    1538  184.08  2773.1   182.5  4939.1  182.72  4969.6  175.62  5058.3  182.29
  5312.6  182.49  7505.5  182.97  8441.9  182.69 12094.8  182.03 13146.9  183.34
 15372.7  184.21 15943.6  184.43 16254.1  184.55 16423.8  188.58 16519.4     198
 16700.5  218.23 17082.3  221.79 17139.5  216.67 17479.4  230.31 17592.7  230.08
   17642  222.63 17711.7  226.84 17918.7  215.14   18052  225.63 18232.7   228.7
#Mann= 20 ,-1 , 0
  -676.4     .05       0   100.8     .05       0   845.3     .16       0
  1128.1     .05       0    1538     .07       0  2773.1     .12       0
  4939.1     .07       0  5058.3     .12       0  5312.6     .12       0
  7505.5     .16       0  8441.9     .12       0 12094.8     .12       0
 13146.9     .12       0 15372.7     .12       0 15943.6     .12       0
 16519.4     .05       0 17082.3     .16       0 17479.4     .05       0
 17711.7     .16       0   18052     .05       0
#XS Ineff= 2 , 0
           829.7  208.2416990.13          224.36
Permanent Ineff=
       F       F
Bank Sta=4939.1,5058.3
XS Rating Curve= 0 ,0
Exp/Cntr=0.3,0.1

Type RM Length L Ch R = 1 ,149766  ,1448,1448,1448
BEGIN DESCRIPTION:
NAVASOTA RIVER 211
END DESCRIPTION:
XS GIS Cut Line= 5
       3618725.5     10179214.81      3617487.62     10178001.23
      3614138.16     10176363.11      3611274.76     10175124.43
      3608652.52     10170292.45
#Sta/Elev= 30
  -462.1  221.34  -396.4  220.74   108.2   194.7   334.8  190.94  1593.1  182.06
    1935  182.13  2235.5  182.19  3105.9  182.37  4007.7  182.56    4929  183.48
  4990.8  175.71    5072  183.13  5764.9  182.04  6975.5  182.25  7338.7  182.13
  7650.2  182.02 10165.5  181.42 10674.3  181.31 11174.6  182.83 11873.9     186
 12415.5  189.39 12459.2  194.71 12526.2  218.97   12617  213.71 12799.2  232.29
 12838.9  242.17 13146.4  235.91   13425  257.49 13571.5  253.97 13617.5  255.28
#Mann= 20 ,-1 , 0
  -462.1     .08       0  -396.4     .05       0   334.8     .05       0
  1593.1     .12       0    1935     .12       0  2235.5     .07       0
  3105.9     .12       0  4007.7     .12       0    4929     .07       0
    5072     .12       0  5764.9     .12       0  6975.5     .12       0
  7338.7     .16       0  7650.2     .12       0 10165.5     .05       0
 10674.3     .12       0 11174.6     .12       0 11873.9     .16       0
 12838.9     .05       0 13571.5     .16       0
#XS Ineff= 2 , 0
                        12881.78          246.15
Permanent Ineff=
       F       F
Bank Sta=4929,5072
XS Rating Curve= 0 ,0
Exp/Cntr=0.3,0.1

Type RM Length L Ch R = 1 ,148318  ,1711,1711,1711
BEGIN DESCRIPTION:
NAVASOTA RIVER 364
END DESCRIPTION:
XS GIS Cut Line= 4
      3619260.55      10179396.1      3617524.42     10177464.66
      3612055.29     10173313.27       3610736.5     10170363.33
#Sta/Elev= 30
  -666.8  222.89  -501.6  213.17    71.7  206.51   593.4  188.71   865.1  185.85
  1124.9  183.11  1261.9  181.67  1392.6  181.68  1758.7  182.12  1941.1  182.04
  2581.4  181.72  2944.4   181.8  3468.3  181.92  3904.5  182.02    4331  182.12
  4536.3  182.17  4932.3  181.76  5017.3  175.03  5059.2  183.05    6045   177.1
  9351.3   182.2  9788.3  182.85 10185.5     183 10608.2  193.77 10654.6  197.57
   10701   217.1 10967.1     207 11221.1  227.05 11695.6  244.29 12027.8  245.09
#Mann= 20 ,-1 , 0
  -666.8     .05       0   593.4     .07       0   865.1     .12       0
  1124.9     .07       0  1261.9     .12       0  1392.6     .07       0
  1758.7     .12       0  1941.1     .07       0  2581.4     .07       0
  2944.4     .07       0  3468.3     .12       0  3904.5     .12       0
    4331     .07       0  4536.3     .12       0  4932.3     .07       0
  5059.2     .12       0  9351.3     .05       0  9788.3     .12       0
 10185.5     .16       0 11695.6     .05       0
#XS Ineff= 2 ,-1
  5909.8    6095  182.2110700.84 11117.4  217.06
Permanent Ineff=
       F       F
Bank Sta=4932.3,5059.2
XS Rating Curve= 0 ,0
Exp/Cntr=0.3,0.1

Type RM Length L Ch R = 1 ,146607  ,1330,1330,1330
BEGIN DESCRIPTION:
NAVASOTA RIVER 365
END DESCRIPTION:
XS GIS Cut Line= 4
      3619482.36     10179346.93      3618375.58     10177159.41
      3615198.07     10174321.48      3610949.37     10170467.58
#Sta/Elev= 30
 -1711.9   215.7  -842.3  192.46  -515.2  189.49  -165.5   187.3      29  186.08
     738  181.63  4138.7   182.3  4413.5   181.5  4926.5  181.74  4961.4  174.92
  5075.2  181.29  5669.6  181.71  5711.8  176.82  7856.8  180.84  8384.9  186.59
  8535.1  188.48  8911.7   220.5  9096.2  221.42  9520.6   236.4  9617.5  233.88
  9750.2  233.79  9903.1  233.69 10003.5  233.63   10056   233.6 10132.2  233.78
 10260.9  233.78 10320.8  231.93 10428.1  243.11 10513.4  249.43 10736.2  254.04
#Mann= 20 ,-1 , 0
 -1711.9     .05       0  -842.3     .05       0  -515.2     .07       0
  -165.5     .12       0      29     .07       0  4138.7     .07       0
  4413.5     .12       0  4926.5     .07       0  5075.2     .12       0
  8384.9     .16       0  8535.1     .16       0  9617.5      .1       0
  9750.2     .08       0  9903.1     .08       0 10003.5     .05       0
   10056      .1       0 10132.2     .05       0 10260.9     .05       0
 10428.1     .16       0 10513.4     .05       0
Bank Sta=4926.5,5075.2
XS Rating Curve= 0 ,0
Exp/Cntr=0.3,0.1

Type RM Length L Ch R = 1 ,145277  ,4278,4278,4278
BEGIN DESCRIPTION:
NAVASOTA RIVER 366
END DESCRIPTION:
XS GIS Cut Line= 4
      3619562.91     10179310.49      3618822.45       10176866.
      3616178.28       10173847.      3611020.34     10170436.71
#Sta/Elev= 30
 -1567.4  213.78  -622.8  192.59  -103.2  182.67   267.7  182.09   787.8  181.71
  1278.7  181.53  1715.7  181.49  3082.4  181.36  3505.9  181.32  4073.8  181.27
  4826.9  181.81  4944.2  181.49  5007.1   174.7  5058.2  180.94  6541.1   179.5
  6743.2  180.62  7844.9  180.55    8400  187.29  8693.6  197.52    8826  203.08
  9244.3  198.87  9713.8  242.69 10086.3  246.93 10262.2  243.34 10492.9  234.05
 10622.6   241.5 10654.6  237.76 10797.2  235.02 10998.8  253.37 11183.4  256.42
#Mann= 20 ,-1 , 0
 -1567.4     .05       0  -622.8     .05       0  -103.2     .12       0
   267.7     .07       0   787.8     .12       0  1278.7     .12       0
  1715.7     .07       0  3082.4     .12       0  3505.9     .12       0
  4073.8     .12       0  4826.9     .12       0  4944.2     .07       0
  5058.2     .12       0  6541.1     .07       0  6743.2     .12       0
  8693.6     .16       0 10086.3     .16       0 10262.2     .05       0
 10492.9     .08       0 10654.6     .05       0
Bank Sta=4944.2,5058.2
XS Rating Curve= 0 ,0
Exp/Cntr=0.3,0.1

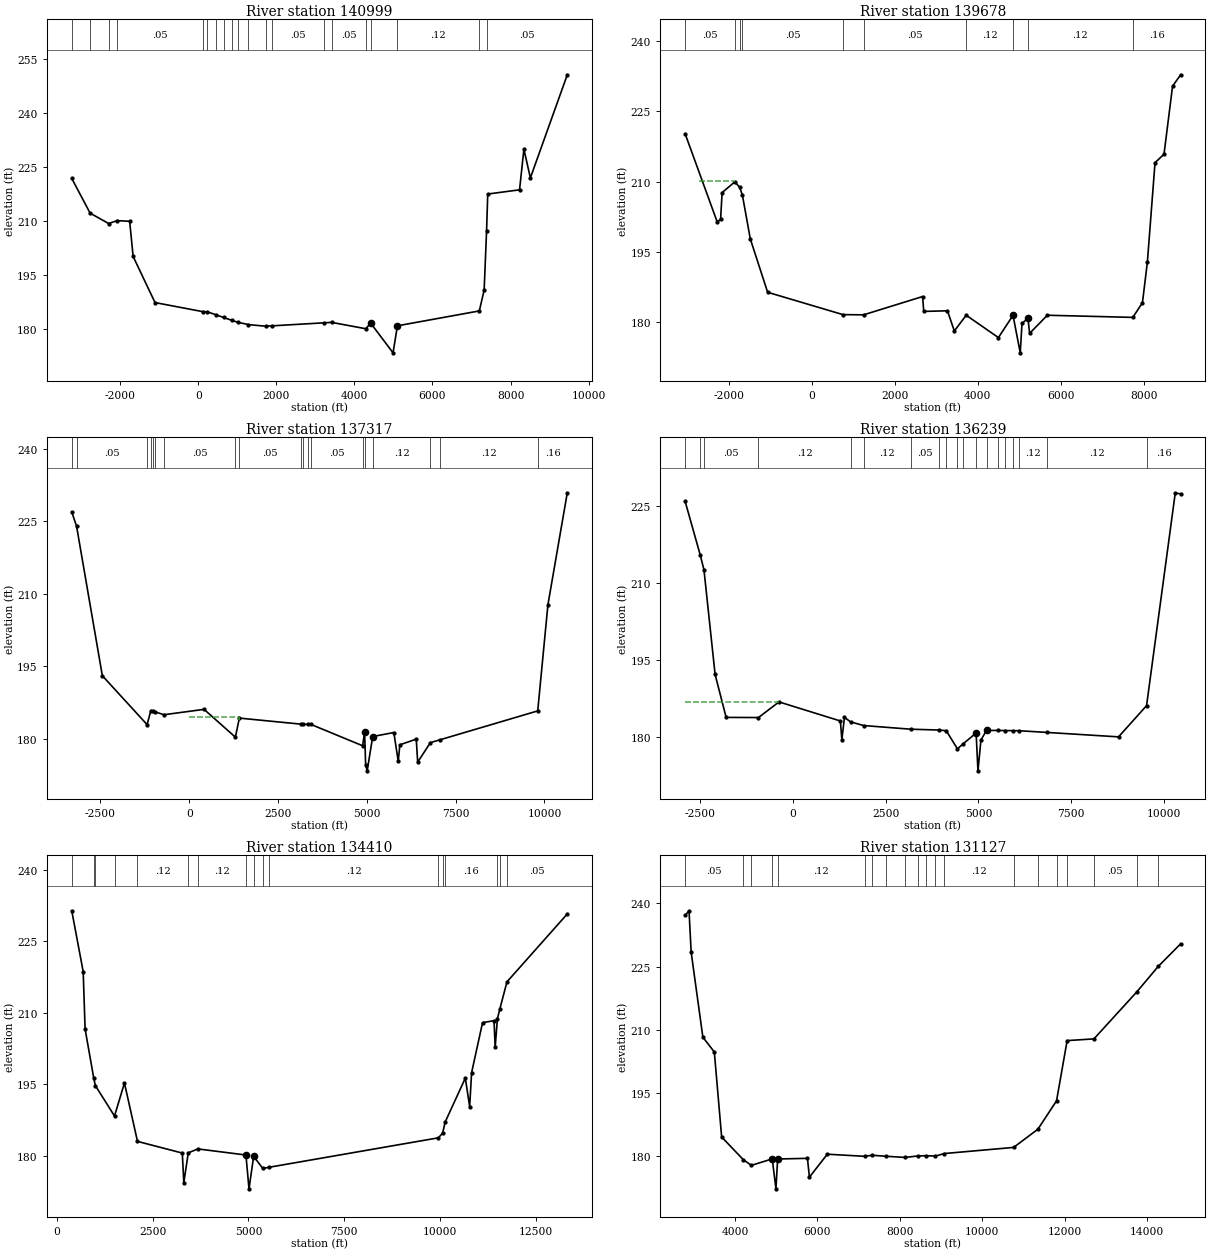
Type RM Length L Ch R = 1 ,140999  ,1321,1321,1321
BEGIN DESCRIPTION:
NAVASOTA RIVER 367
END DESCRIPTION:
XS GIS Cut Line= 4
      3622734.77     10175211.03      3616537.72     10171858.42
      3615384.09     10171544.85      3611102.78     10170319.52
#Sta/Elev= 30
 -3241.3  221.76 -2770.4   212.1 -2296.7  209.22 -2076.9  210.03 -1757.8  209.83
 -1669.3  200.06   -1108  187.23   124.3  184.69   230.8  184.65   450.6  183.85
   650.2  183.08   863.1  182.27    1015  181.75  1286.3   181.1  1723.7  180.66
  1890.4  180.76  3221.5   181.6  3416.2  181.72  4289.1  179.96  4418.9  181.47
  4989.6  173.25  5101.7  180.77  7199.5  184.91  7323.1  190.71  7385.6  207.24
  7415.2  217.42  8229.9  218.59  8341.6  229.88  8507.4   221.9  9453.2  250.59
#Mann= 20 ,-1 , 0
 -3241.3     .05       0 -2770.4     .05       0 -2296.7     .08       0
 -2076.9     .05       0   124.3     .05       0   230.8      .1       0
   450.6     .16       0   650.2     .12       0   863.1     .12       0
    1015     .05       0  1286.3     .12       0  1723.7     .07       0
  1890.4     .05       0  3221.5     .12       0  3416.2     .05       0
  4289.1     .12       0  4418.9     .07       0  5101.7     .12       0
  7199.5     .16       0  7385.6     .05       0
Bank Sta=4418.9,5101.7
XS Rating Curve= 0 ,0
Exp/Cntr=0.3,0.1

Type RM Length L Ch R = 1 ,139678  ,2361,2361,2361
BEGIN DESCRIPTION:
NAVASOTA RIVER 417
END DESCRIPTION:
XS GIS Cut Line= 3
        3622814.     10175135.15      3616112.94       10170680.
      3612332.27      10169797.5
#Sta/Elev= 30
 -3046.9  220.25 -2271.5  201.32   -2192  202.01   -2156  207.66 -1849.2  209.96
 -1733.6  208.78 -1667.8  207.12 -1477.9  197.77   -1060  186.34   754.1  181.56
    1250  181.52  2670.7  185.43  2697.8  182.25  3268.9  182.38  3434.3  178.06
  3720.1  181.43  4495.5  176.65  4847.2  181.41  5021.1  173.39  5063.2  179.67
  5206.2  180.79  5247.3  177.56  5674.1  181.43  7730.9  180.97  7962.8   184.1
  8081.5   192.8  8265.7  214.06    8482  215.86  8687.4   230.4  8882.3  232.85
#Mann= 10 ,-1 , 0
 -3046.9     .05       0 -1849.2     .08       0 -1733.6      .1       0
 -1667.8     .05       0   754.1     .12       0    1250     .05       0
  3720.1     .12       0  4847.2     .07       0  5206.2     .12       0
  7730.9     .16       0
#XS Ineff= 2 ,-1
 -2719.4 -1867.8  210.05 -1867.8  2661.7  185.35
Permanent Ineff=
       F       F
Bank Sta=4847.2,5206.2
XS Rating Curve= 0 ,0
Exp/Cntr=0.3,0.1

Type RM Length L Ch R = 1 ,137317  ,1078,1078,1078
BEGIN DESCRIPTION:
NAVASOTA RIVER 418
END DESCRIPTION:
XS GIS Cut Line= 5
      3624656.23     10175268.83      3621723.04     10172891.21
      3617817.62     10170590.94      3616661.35     10169991.21
        3612328.     10169713.43
#Sta/Elev= 30
 -3308.3   226.9 -3172.6  223.94 -2447.1  193.02 -1186.5   182.9   -1081  185.82
 -1022.5  185.68  -957.9  185.53  -711.6  184.95   417.4  186.06  1298.8  180.31
  1410.8  184.25  3146.8     183  3202.2  182.99  3354.2  182.95  3431.4  182.93
  4881.6  178.53  4936.8   181.3  4967.4  174.54  5010.3  173.34  5165.5  180.44
    5761  181.27  5884.9  175.29    5930  178.73    6392   179.9  6432.1  175.14
  6790.6  179.18  7057.5  179.76    9812  185.74 10099.6  207.72 10644.8  230.87
#Mann= 19 ,-1 , 0
 -3308.3     .16       0 -3172.6     .05       0 -1186.5     .12       0
   -1081     .07       0 -1022.5     .05       0  -957.9     .07       0
  -711.6     .05       0  1298.8     .07       0  1410.8     .05       0
  3146.8     .12       0  3202.2     .08       0  3354.2     .12       0
  3431.4     .05       0  4881.6     .07       0  4936.8    .033       0
  5165.5     .12       0  6790.6     .07       0  7057.5     .12       0
    9812     .16       0
#XS Ineff= 2 , 0
       0  1396.9  184.58               0
Permanent Ineff=
       F       F
Bank Sta=4936.8,5165.5
XS Rating Curve= 0 ,0
Exp/Cntr=0.3,0.1

Type RM Length L Ch R = 1 ,136239  ,1829,1829,1829
BEGIN DESCRIPTION:
NAVASOTA RIVER 141
END DESCRIPTION:
XS GIS Cut Line= 3
      3625492.78     10168725.59      3621846.96     10169611.01
      3612237.59     10169637.05
#Sta/Elev= 30
 -2908.4  225.94 -2501.7  215.49 -2399.1  212.53 -2099.4  192.14 -1801.9  183.76
  -930.2  183.73  -376.2  186.78  1278.3  183.06  1318.3  179.41  1388.3  183.76
  1551.6   182.9  1904.7  182.17  3170.2  181.46  3940.7  181.29  4132.3  181.17
  4434.3  177.62  4597.4  178.66  4938.3   180.7    4988  173.33  5068.3  179.34
  5218.3  181.23  5520.1  181.21  5717.5  181.19  5945.5  181.17  6104.5  181.16
  6842.4  180.83  8778.3  179.96  9533.8  186.05 10308.3   227.6 10452.8  227.37
#Mann= 19 ,-1 , 0
 -2908.4     .05       0 -2501.7     .08       0 -2399.1     .05       0
  -930.2     .12       0  1551.6     .05       0  1904.7     .12       0
  3170.2     .05       0  3940.7     .12       0  4132.3     .05       0
  4434.3     .12       0  4597.4     .12       0  4938.3     .07       0
  5218.3     .07       0  5520.1     .12       0  5717.5     .12       0
  5945.5     .07       0  6104.5     .12       0  6842.4     .12       0
  9533.8     .16       0
#XS Ineff= 2 , 0
         -375.94   186.8
Permanent Ineff=
       F       F
Bank Sta=4938.3,5218.3
XS Rating Curve= 0 ,0
Exp/Cntr=0.3,0.1

Type RM Length L Ch R = 1 ,134410  ,3283,3283,3283
BEGIN DESCRIPTION:
NAVASOTA RIVER 474
END DESCRIPTION:
XS GIS Cut Line= 3
      3622738.23      10167750.1      3618157.21      10168302.4
      3609905.55     10169425.25
#Sta/Elev= 30
   385.8   231.4   684.1  218.65   734.4  206.58   959.6  196.28  1002.1  194.71
  1502.3  188.31  1761.8  195.25  2102.5  182.99  3272.7  180.54    3313  174.34
  3428.2  180.58  3680.1  181.41  4934.6  180.13    5015  173.03  5136.3  179.86
  5376.2   177.3  5526.4  177.54  9961.5  183.74 10071.7  184.73 10138.2  187.06
 10664.9  196.28 10777.9  190.28 10828.3  197.41 11114.5  207.92 11414.2  208.33
 11443.9  202.72 11502.3  208.73 11567.6  210.83 11751.9  216.48 13327.7  230.74
#Mann= 17 ,-1 , 0
   385.8     .05       0   959.6     .16       0  1002.1     .05       0
  1502.3     .16       0  2102.5     .12       0  3428.2     .07       0
  3680.1     .12       0  4934.6     .07       0  5136.3     .12       0
  5376.2     .07       0  5526.4     .12       0  9961.5     .16       0
 10071.7     .12       0 10138.2     .16       0 11502.3     .05       0
 11567.6     .16       0 11751.9     .05       0
#XS Ineff= 2 , 0
         1762.24  195.23
Permanent Ineff=
       F       F
Bank Sta=4934.6,5136.3
XS Rating Curve= 0 ,0
Exp/Cntr=0.3,0.1

Type RM Length L Ch R = 1 ,131127  ,1795,1795,1795
BEGIN DESCRIPTION:
NAVASOTA RIVER 427
END DESCRIPTION:
XS GIS Cut Line= 3
      3621477.75      10166430.5      3619296.27     10166793.02
       3609795.4      10169268.6
#Sta/Elev= 30
  2788.6  237.15  2883.8  238.26  2936.2  228.39  3220.1  208.25    3498  204.75
  3675.6  184.58  4199.3  179.21  4397.5  177.84    4904  179.38  4993.8  172.27
  5035.3  179.35  5758.7  179.51  5806.4  175.05  6241.5  180.49  7145.4  179.99
  7328.7  180.24    7661     180  8131.9  179.73  8444.2  180.08  8642.4  180.13
  8861.8  180.04  9084.7  180.65 10763.9   182.1 11352.4  186.42 11805.7  193.16
 12062.6  207.45 12713.5  207.86 13753.7  219.01   14280  225.12 14818.1  230.41
#Mann= 20 ,-1 , 0
  2788.6     .05       0  4199.3     .07       0  4397.5     .12       0
    4904     .07       0  5035.3     .12       0  7145.4     .12       0
  7328.7     .07       0    7661     .12       0  8131.9     .12       0
  8444.2     .07       0  8642.4     .12       0  8861.8     .07       0
  9084.7     .12       0 10763.9     .05       0 11352.4     .16       0
 11805.7     .05       0 12062.6     .16       0 12713.5     .05       0
 13753.7     .16       0   14280     .05       0
Bank Sta=4904,5035.3
XS Rating Curve= 0 ,0
Exp/Cntr=0.3,0.1