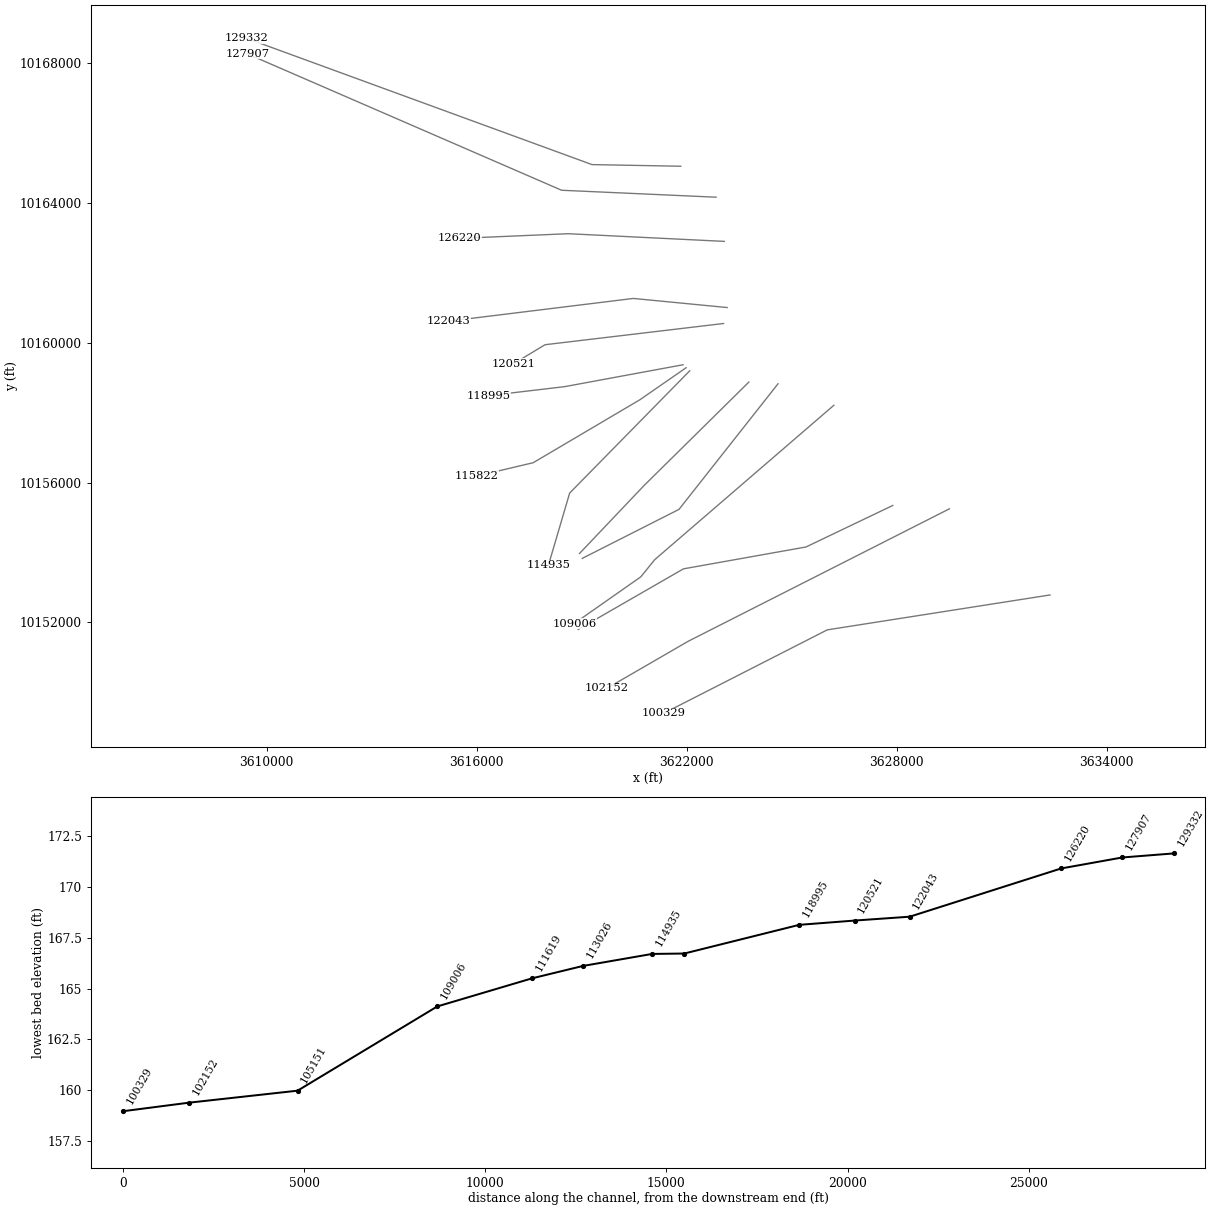
HEC-RAS study NAVASOTA RIVER.prj: NAVASOTA RIVER Base Level Engineering

--- NAVASOTA RIVER.g01 (geometry) --- (continued)

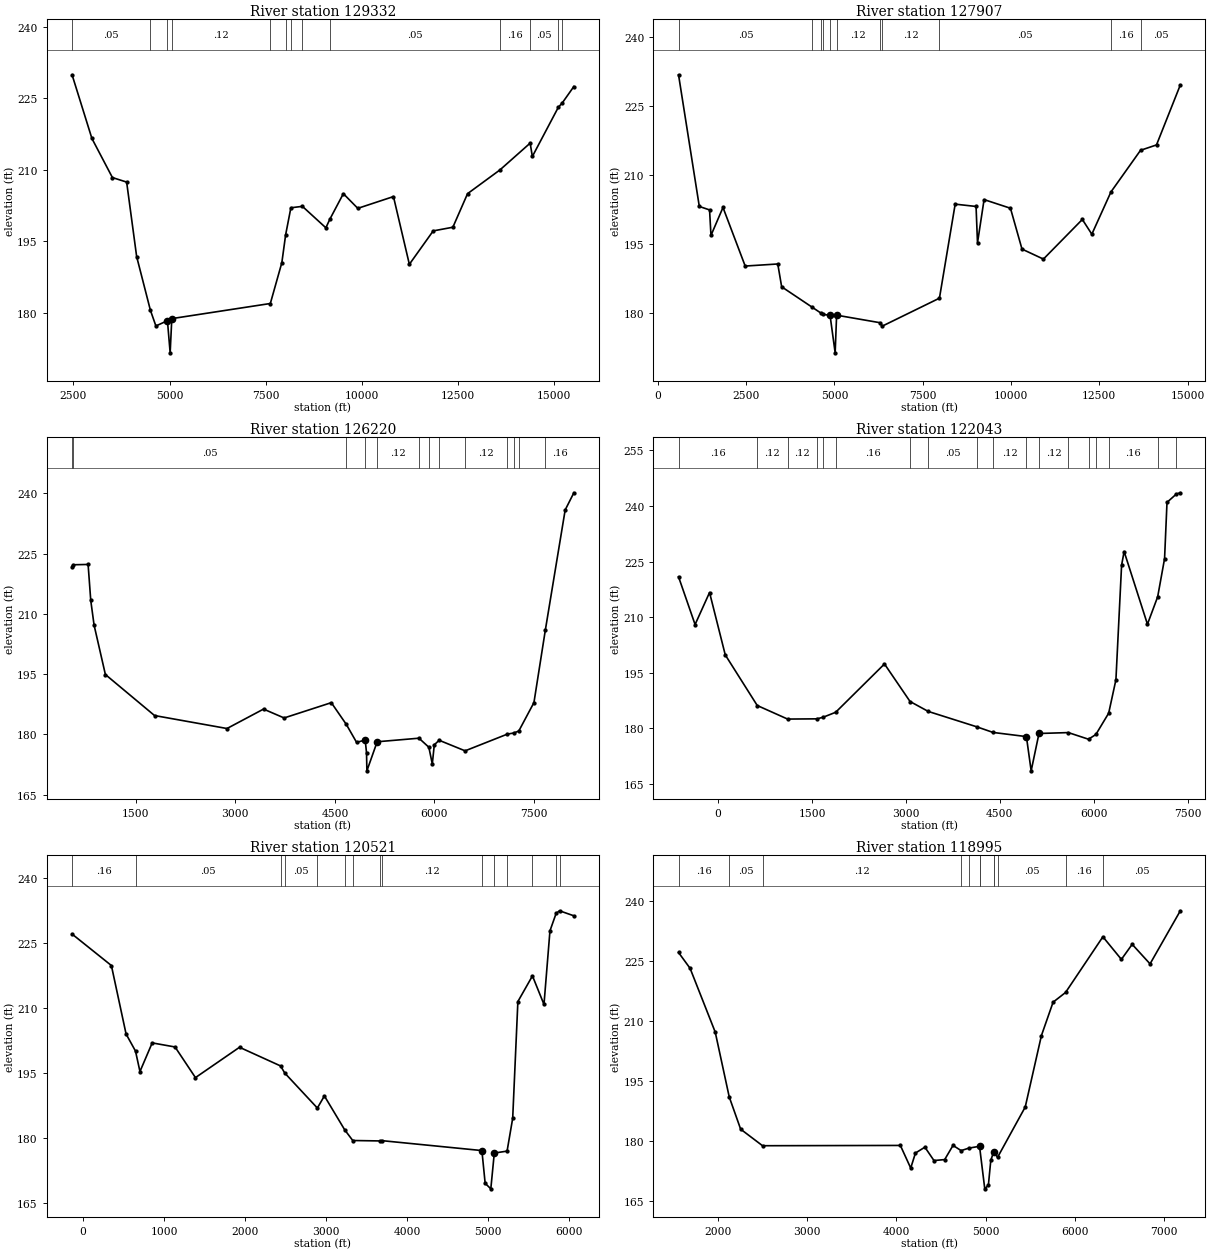
Type RM Length L Ch R = 1 ,129332  ,1425,1425,1425
BEGIN DESCRIPTION:
NAVASOTA RIVER 426
END DESCRIPTION:
XS GIS Cut Line= 3
      3621830.31     10165047.04      3619295.75     10165094.06
      3609429.08     10168704.82
#Sta/Elev= 30
    2465  229.97  2980.5  216.61  3513.4  208.41  3883.5  207.46  4143.5  191.83
  4501.3  180.56  4643.6  177.28  4943.6  178.38  5014.3  171.64  5057.1  178.82
    7618  181.99  7916.8  190.55  8016.5  196.44  8151.8  202.07  8451.2  202.37
    9061  197.87  9166.6   199.7  9515.6  205.03  9891.1  201.95   10818  204.42
 11231.2  190.21 11850.9  197.22   12362  197.99 12743.8  205.03 13583.6     210
 14370.8  215.63 14427.9  212.83 15101.6  223.13 15208.2   224.1 15506.6  227.51
#Mann= 13 ,-1 , 0
    2465     .05       0  4501.3     .12       0  4943.6     .07       0
  5057.1     .12       0    7618     .05       0  8016.5     .16       0
  8151.8     .05       0  8451.2     .16       0  9166.6     .05       0
 13583.6     .16       0 14370.8     .05       0 15101.6      .1       0
 15208.2     .16       0
Bank Sta=4943.6,5057.1
XS Rating Curve= 0 ,0
Exp/Cntr=0.3,0.1

Type RM Length L Ch R = 1 ,127907  ,1687,1687,1687
BEGIN DESCRIPTION:
NAVASOTA RIVER 425
END DESCRIPTION:
XS GIS Cut Line= 3
      3622839.93     10164161.62        3618427.     10164360.21
      3609443.19     10168263.19
#Sta/Elev= 30
   582.6  231.77    1171   203.2  1461.3  202.45  1501.4  196.92  1841.7  202.98
  2470.6  190.27  3393.3  190.72  3503.4  185.77  4370.8  181.32  4611.6  180.09
  4661.7  179.83  4874.8  179.55  5018.7  171.44  5059.8  179.61  6279.4  177.99
  6354.5  177.24  7972.3   183.3    8418   203.7  9009.3   203.2  9050.3   195.3
  9236.7  204.69  9983.9  202.81 10310.5  193.95   10917  191.78 12019.7  200.38
 12288.5  197.18 12830.8  206.36 13667.6  215.38 14120.2  216.55   14795  229.57
#Mann= 11 ,-1 , 0
   582.6     .05       0  4370.8     .12       0  4611.6     .05       0
  4661.7     .12       0  4874.8     .07       0  5059.8     .12       0
  6279.4     .07       0  6354.5     .12       0  7972.3     .05       0
 12830.8     .16       0 13667.6     .05       0
Bank Sta=4874.8,5059.8
XS Rating Curve= 0 ,0
Exp/Cntr=0.3,0.1

Type RM Length L Ch R = 1 ,126220  ,4177,4177,4177
BEGIN DESCRIPTION:
NAVASOTA RIVER 424
END DESCRIPTION:
XS GIS Cut Line= 3
      3623073.37     10162898.17      3618618.66      10163117.5
       3615521.3     10162984.97
#Sta/Elev= 30
   539.9  221.75   553.8  222.22   781.5   222.3   821.5  213.33   871.6  207.19
  1041.8  194.89  1782.7  184.67    2874  181.44  3424.7  186.28    3735  184.07
  4445.9  187.88    4672  182.46  4826.3     178  4956.5  178.56  4976.5  175.36
  4981.8   170.9  5136.7  178.14  5766.4  179.03  5915.4  176.78  5967.4  172.61
  5997.5  177.39  6070.8  178.51  6461.7  175.88  7097.4  180.04  7196.2  180.33
  7270.6  180.82  7498.8   187.9  7671.8  206.09  7969.3  235.87  8100.2  240.15
#Mann= 13 ,-1 , 0
   539.9      .1       0   553.8     .05       0    4672     .12       0
  4956.5     .07       0  5136.7     .12       0  5766.4     .07       0
  5915.4     .12       0  6070.8     .07       0  6461.7     .12       0
  7097.4     .05       0  7196.2     .12       0  7270.6     .05       0
  7671.8     .16       0
Bank Sta=4956.5,5136.7
XS Rating Curve= 0 ,0
Exp/Cntr=0.3,0.1

Type RM Length L Ch R = 1 ,122043  ,1522,1522,1522
BEGIN DESCRIPTION:
NAVASOTA RIVER 249
END DESCRIPTION:
XS GIS Cut Line= 3
      3623155.26     10161006.03      3620475.09     10161266.45
      3615190.83     10160615.41
#Sta/Elev= 30
  -632.1  220.89  -367.7  208.01  -136.6  216.65   114.6  199.81   625.4  186.16
  1110.4   182.5  1579.6  182.56  1679.1     183  1878.2  184.33  2658.2  197.37
  3066.8  187.24  3357.8  184.56    4133  180.41  4392.9  178.89  4925.8  177.77
  5001.7  168.53  5126.7  178.61  5596.1  178.85  5918.2  177.06  6035.7  178.34
  6240.2  184.09  6355.9  193.11  6446.6  224.03  6486.9  227.71  6859.7  208.09
    7023   215.5  7133.1  225.79    7172  240.97  7322.2  243.23  7384.9  243.56
#Mann= 18 ,-1 , 0
  -632.1     .16       0   625.4     .12       0  1110.4     .12       0
  1579.6     .16       0  1679.1     .05       0  1878.2     .16       0
  3066.8     .05       0  3357.8     .05       0    4133     .12       0
  4392.9     .12       0  4925.8     .07       0  5126.7     .12       0
  5596.1     .07       0  5918.2     .12       0  6035.7     .05       0
  6240.2     .16       0    7023     .05       0  7322.2     .08       0
Bank Sta=4925.8,5126.7
XS Rating Curve= 0 ,0
Exp/Cntr=0.3,0.1

Type RM Length L Ch R = 1 ,120521  ,1526,1526,1526
BEGIN DESCRIPTION:
NAVASOTA RIVER 423
END DESCRIPTION:
XS GIS Cut Line= 3
      3623053.91     10160549.65      3617953.56     10159943.02
      3617049.99     10159396.87
#Sta/Elev= 30
  -136.3  227.12   348.9  219.86   530.2  204.06   646.5  200.12   701.4   195.4
   852.4  202.01  1134.4  201.07  1386.2     194    1930     201    2437  196.69
    2488  195.06  2890.6  186.98  2977.3  189.77  3228.4  181.94  3327.3  179.49
  3667.1  179.39    3686  179.46  4920.9  177.17  4961.2  169.62    5031  168.34
    5074   176.6  5231.7  177.04    5301  184.62    5365  211.55  5544.9  217.47
  5687.1  210.88  5760.8  227.86  5836.8  231.88  5878.7  232.49  6055.8  231.33
#Mann= 15 ,-1 , 0
  -136.3     .16       0   646.5     .05       0    2437     .16       0
    2488     .05       0  2890.6     .16       0  3228.4     .05       0
  3327.3     .12       0  3667.1     .16       0    3686     .12       0
  4920.9     .07       0    5074     .12       0  5231.7     .16       0
  5544.9     .05       0  5836.8      .1       0  5878.7     .05       0
Bank Sta=4920.9,5074
XS Rating Curve= 0 ,0
Exp/Cntr=0.3,0.1

Type RM Length L Ch R = 1 ,118995  ,3173,3173,3173
BEGIN DESCRIPTION:
NAVASOTA RIVER 422
END DESCRIPTION:
XS GIS Cut Line= 3
      3621896.44      10159369.8      3618511.89     10158743.54
      3616346.31     10158487.23
#Sta/Elev= 30
    1558  227.11  1687.4  223.16  1969.2  207.24    2126  191.07    2254  183.02
  2499.2  178.89  4043.7  178.96  4159.7  173.31  4212.6  177.06  4318.4  178.53
  4420.1  175.19  4540.2  175.43  4633.7  178.97  4724.4  177.67  4809.5  178.28
  4930.8  178.75  4989.4  168.13    5030  169.06  5056.9  175.24  5089.4  177.37
  5132.8  175.99  5442.9  188.55  5624.1  206.37    5755  214.71  5894.6  217.13
    6313  231.03  6520.3  225.39  6641.2  229.15  6841.5  224.27  7180.7  237.52
#Mann= 12 ,-1 , 0
    1558     .16       0    2126     .05       0  2499.2     .12       0
  4724.4     .07       0  4809.5     .12       0  4930.8     .07       0
  4930.8     .07       0  5089.4     .07       0  5089.4     .12       0
  5132.8     .05       0  5894.6     .16       0    6313     .05       0
Bank Sta=4930.8,5089.4
XS Rating Curve= 0 ,0
Exp/Cntr=0.3,0.1

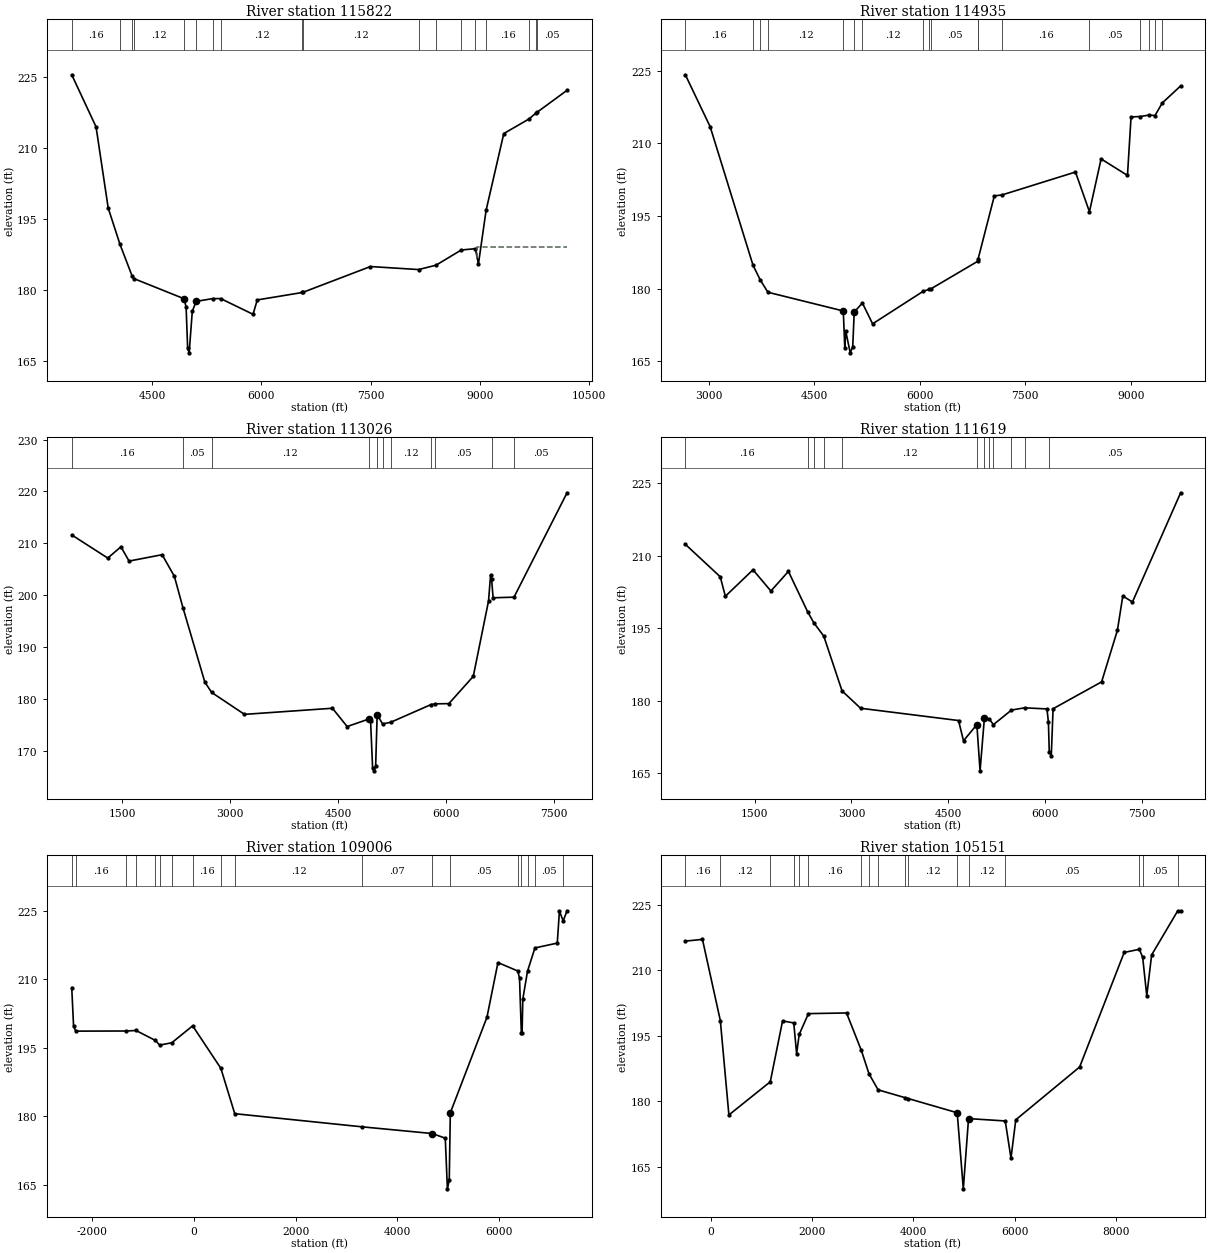
Type RM Length L Ch R = 1 ,115822  ,887,887,887
BEGIN DESCRIPTION:
NAVASOTA RIVER 250
END DESCRIPTION:
XS GIS Cut Line= 4
      3621984.38     10159285.24      3620663.68     10158369.53
      3617614.75     10156568.47      3616000.36     10156186.57
#Sta/Elev= 30
  3392.9  225.52  3727.1   214.5  3893.9  197.34  4056.2  189.65    4223  182.95
  4248.3  182.41  4934.9  178.17  4964.6  176.44  4985.6   167.7  5006.4  166.72
  5049.5  175.48  5102.3   177.6  5329.8  178.19    5440  178.19  5884.5  174.87
  5942.6  177.91  6561.6  179.48  6569.4  179.51  7497.9  184.97  8159.4  184.33
  8398.7  185.25  8745.4  188.46  8939.2  188.75  8982.1  185.51  9087.4  196.86
  9330.5  213.09  9678.5  216.19    9779  217.52  9790.4  217.62 10200.1  222.24
#Mann= 18 ,-1 , 0
  3392.9     .16       0  4056.2     .12       0    4223     .05       0
  4248.3     .12       0  4934.9     .07       0  5102.3     .12       0
  5329.8     .07       0    5440     .12       0  6561.6     .07       0
  6569.4     .12       0  8159.4     .07       0  8398.7     .12       0
  8745.4     .07       0  8939.2     .12       0  9087.4     .16       0
  9678.5     .05       0    9779     .16       0  9790.4     .05       0
#XS Ineff= 2 , 0
                         8964.86           189.2
Permanent Ineff=
       F       F
Bank Sta=4934.9,5102.3
XS Rating Curve= 0 ,0
Exp/Cntr=0.3,0.1

Type RM Length L Ch R = 1 ,114935  ,1909,1909,1909
BEGIN DESCRIPTION:
NAVASOTA RIVER 421
END DESCRIPTION:
XS GIS Cut Line= 3
      3622086.41     10159196.83      3618656.42     10155700.42
      3618049.09     10153635.51
#Sta/Elev= 30
  2661.5   224.2  3014.7  213.47    3625  184.81  3727.3  181.79  3836.7  179.23
  4909.9  175.36  4931.1  167.77  4945.2  171.16  5008.5   166.7  5044.2  167.96
  5065.4  175.14  5181.8     177  5327.1   172.7  6047.2  179.43    6128  179.81
  6161.7  179.97  6824.4  185.64  6829.9  186.17  7059.5  199.14  7172.8  199.37
  8214.8  204.09  8413.5  195.88  8579.6   206.8  8954.9  203.39  9005.9  215.48
    9139  215.57  9265.9  215.88  9346.3  215.76    9450  218.37  9711.8   221.9
#Mann= 18 ,-1 , 0
  2661.5     .16       0    3625     .05       0  3727.3     .16       0
  3836.7     .12       0  4909.9     .07       0  5065.4     .07       0
  5181.8     .12       0  6047.2     .07       0    6128     .12       0
  6161.7     .05       0  6824.4     .12       0  6829.9     .05       0
  7172.8     .16       0  8413.5     .05       0    9139      .1       0
  9265.9     .05       0  9346.3      .1       0    9450     .05       0
#XS Ineff= 2 , 0
       0                  8214.8       0  204.09
Permanent Ineff=
       F       F
Bank Sta=4909.9,5065.4
XS Rating Curve= 0 ,0
Exp/Cntr=0.3,0.1

Type RM Length L Ch R = 1 ,113026  ,1407,1407,1407
BEGIN DESCRIPTION:
NAVASOTA RIVER 420
END DESCRIPTION:
XS GIS Cut Line= 3
      3623776.66     10158875.01      3620784.91     10155919.11
      3618937.55     10153972.03
#Sta/Elev= 30
   794.3   211.6  1294.9  207.14  1478.7  209.31  1591.9  206.56  2051.5  207.79
  2221.2  203.64  2341.7  197.54  2645.5  183.22  2741.1  181.22    3197     177
  4420.4  178.18  4625.4  174.65  4922.4  176.08  4950.7  175.76    4979  166.75
  4998.2  166.11  5021.5  167.01  5042.6  176.96  5116.9  175.16    5230  175.47
  5790.3  178.88  5851.4  179.03  6040.1  179.07  6379.5  184.33  6591.8  198.87
  6620.1  203.85  6634.7  203.01  6655.3  199.48    6946   199.6    7684  219.73
#Mann= 11 ,-1 , 0
   794.3     .16       0  2341.7     .05       0  2741.1     .12       0
  4922.4     .07       0  5042.6     .12       0  5116.9     .07       0
    5230     .12       0  5790.3     .07       0  5851.4     .05       0
  6634.7     .16       0    6946     .05       0
Bank Sta=4922.4,5042.6
XS Rating Curve= 0 ,0
Exp/Cntr=0.3,0.1

Type RM Length L Ch R = 1 ,111619  ,2613,2613,2613
BEGIN DESCRIPTION:
NAVASOTA RIVER 419
END DESCRIPTION:
XS GIS Cut Line= 3
       3624608.7     10158825.61      3621779.66     10155233.73
      3619016.31     10153832.54
#Sta/Elev= 30
   427.8  212.38   968.8  205.65  1047.4  201.62  1475.6   207.1    1753  202.71
    2024  206.77  2320.7  198.45  2415.5  196.18    2572  193.37  2854.7  182.04
  3141.7  178.45  4658.7  175.91  4735.5  171.72  4942.4  175.07  4991.9   165.5
  5059.4  176.47  5135.8  176.21  5198.9  175.06  5477.8  178.07  5680.3  178.54
    6028  178.31  6050.3  175.61  6063.8  169.42  6094.8  168.65  6122.7  178.35
  6874.2  183.91  7119.1  194.59  7202.6  201.69  7351.8  200.44  8098.3  223.04
#Mann= 12 ,-1 , 0
   427.8     .16       0  2320.7      .1       0  2415.5     .16       0
    2572     .05       0  2854.7     .12       0  4942.4     .07       0
  5059.4     .12       0  5135.8     .07       0  5198.9     .12       0
  5477.8     .07       0  5680.3     .12       0  6063.8     .05       0
Bank Sta=4942.4,5059.4
XS Rating Curve= 0 ,0
Exp/Cntr=0.3,0.1

Type RM Length L Ch R = 1 ,109006  ,3855,3855,3855
BEGIN DESCRIPTION:
NAVASOTA RIVER 416
END DESCRIPTION:
XS GIS Cut Line= 4
      3626204.04     10158210.61      3621085.21     10153794.82
      3620689.91     10153305.16      3618785.59     10151969.55
#Sta/Elev= 30
 -2389.6  208.13 -2353.5  199.64 -2310.2  198.62 -1322.5  198.65 -1128.5  198.76
  -750.3  196.59  -664.4  195.56  -426.5  196.08   -17.9  199.78   534.9  190.49
   807.8  180.56  3310.4  177.68  4681.4  176.22  4937.3   175.2  4978.7  164.12
  5015.2  166.03  5036.2  180.75  5754.6  201.65  5970.5  213.62  6358.6  211.78
  6393.3  210.23  6429.3  198.18  6443.8  198.26  6458.6  205.66  6550.1  211.72
  6695.1  216.82  7134.1  217.88    7176  224.86  7250.5  222.74    7326  224.95
#Mann= 18 ,-1 , 0
 -2389.6     .05       0 -2310.2     .16       0 -1322.5      .1       0
 -1128.5     .16       0  -750.3     .05       0  -664.4     .16       0
  -426.5     .16       0   -17.9     .16       0   534.9     .05       0
   807.8     .12       0  3310.4     .07       0  4681.4     .03       0
  5036.2     .05       0  6358.6     .16       0  6429.3     .12       0
  6550.1     .16       0  6695.1     .05       0  7250.5      .1       0
Bank Sta=4681.4,5036.2
XS Rating Curve= 0 ,0
Exp/Cntr=0.3,0.1

Type RM Length L Ch R = 1 ,105151  ,2999,2999,2999
BEGIN DESCRIPTION:
NAVASOTA RIVER 415
END DESCRIPTION:
XS GIS Cut Line= 4
      3627886.86     10155345.82      3625407.71     10154158.33
      3621907.71     10153533.33      3618900.98     10151800.83
#Sta/Elev= 30
  -497.7  216.73  -159.8  217.13   192.9  198.52   361.9  176.91  1178.4   184.5
    1421  198.45  1641.7  197.99  1698.5  190.94  1749.1  195.36  1932.1  200.12
  2683.5  200.27  2976.1  191.68  3126.3  186.34  3306.3  182.66  3831.6  180.89
  3898.3  180.67  4867.5  177.41  4987.6  159.98    5091  176.07  5815.1  175.53
  5928.4     167  6023.4   175.8  7283.3  187.89  8162.5  214.14  8461.2  214.85
  8527.1  213.04  8607.9  204.22  8704.2  213.57  9216.4  223.61  9276.7  223.68
#Mann= 17 ,-1 , 0
  -497.7     .16       0   192.9     .12       0  1178.4     .05       0
  1641.7     .08       0  1749.1     .05       0  1932.1     .16       0
  2976.1     .05       0  3126.3     .16       0  3306.3     .12       0
  3831.6     .05       0  3898.3     .12       0  4867.5     .07       0
    5091     .12       0  5815.1     .05       0  8461.2     .16       0
  8527.1     .05       0  9216.4     .08       0
#XS Ineff= 2 , 0
         2683.56  200.09
Permanent Ineff=
       F       F
Bank Sta=4867.5,5091
XS Rating Curve= 0 ,0
Exp/Cntr=0.3,0.1

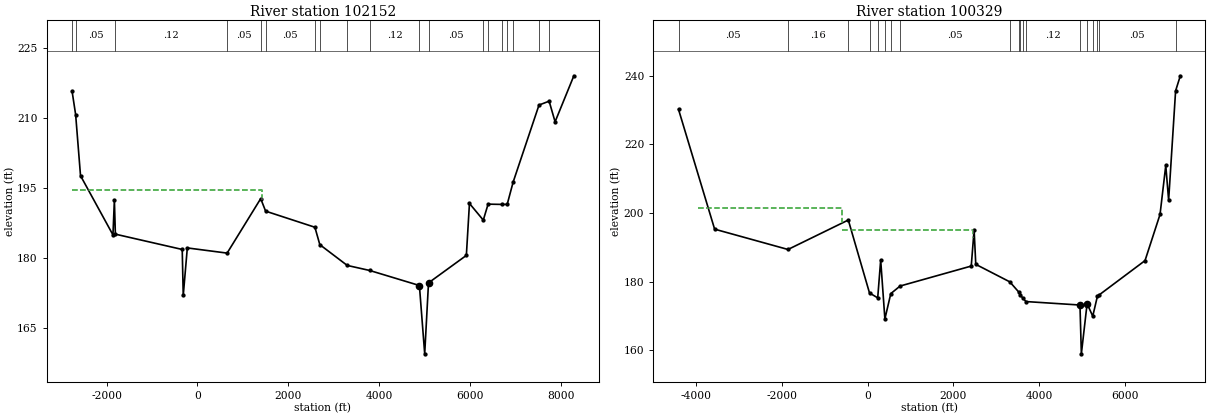
Type RM Length L Ch R = 1 ,102152  ,1823,1823,1823
BEGIN DESCRIPTION:
NAVASOTA RIVER 252
END DESCRIPTION:
XS GIS Cut Line= 3
      3629505.13     10155249.88      3622044.86     10151463.02
      3619722.78     10150117.51
#Sta/Elev= 30
 -2759.4  215.66 -2680.7  210.64 -2573.2  197.55 -1858.8  184.87 -1827.6  192.36
 -1805.9  185.03  -333.7  181.75  -311.2  171.89  -221.5  182.08   654.9  180.97
  1394.4  192.64  1502.9  189.96  2588.1  186.51  2696.6  182.78  3300.1  178.33
  3794.5  177.25  4889.3  174.03    5006  159.39  5089.7  174.59  5923.4  180.48
  5991.5  191.61  6296.3  188.04    6402  191.46    6713   191.4  6822.5  191.41
  6953.7  196.19  7523.1  212.69  7746.2  213.52  7877.4   209.1  8290.7  218.96
#Mann= 19 ,-1 , 0
 -2759.4     .08       0 -2680.7     .05       0 -1805.9     .12       0
   654.9     .05       0  1394.4     .08       0  1502.9     .05       0
  2588.1     .16       0  2696.6     .12       0  3300.1     .05       0
  3794.5     .12       0  4889.3     .07       0  5089.7     .05       0
  6296.3     .07       0    6402     .16       0    6713     .12       0
  6822.5     .16       0  6953.7     .05       0  7523.1     .08       0
  7746.2     .05       0
#XS Ineff= 2 , 0
         1415.82  194.56
Permanent Ineff=
       F       F
Bank Sta=4889.3,5089.7
XS Rating Curve= 0 ,0
Exp/Cntr=0.3,0.1

Type RM Length L Ch R = 1 ,100329  ,6477,6477,6477
BEGIN DESCRIPTION:
NAVASOTA RIVER 251
END DESCRIPTION:
XS GIS Cut Line= 3
      3632380.12     10152786.57      3626016.21     10151788.54
      3621339.45     10149399.98
#Sta/Elev= 30
   -4407  230.16 -3566.1  195.29 -1856.3  189.37  -451.2  197.95    43.2   176.7
   234.4  175.28   303.6  186.29   401.5  169.13     539  176.51     756  178.72
    2414  184.54  2480.7  195.07  2519.5  185.04  3312.2  179.94  3517.5  177.02
  3558.5  176.09  3615.6  175.22  3688.6   174.2  4947.5  173.19    4980  158.97
  5113.6  173.57  5245.2  169.94  5353.8  175.74  5384.8  176.04  6463.5  186.13
  6813.4  199.59  6946.8  213.84  7013.6  203.73    7176  235.58  7286.1  239.97
#Mann= 19 ,-1 , 0
   -4407     .05       0 -1856.3     .16       0  -451.2     .12       0
    43.2     .05       0   234.4     .12       0   401.5     .07       0
     539     .12       0     756     .05       0  3312.2     .12       0
  3517.5     .05       0  3558.5     .12       0  3615.6     .05       0
  3688.6     .12       0  4947.5     .07       0  5113.6     .12       0
  5245.2     .07       0  5353.8     .12       0  5384.8     .05       0
    7176      .1       0
#XS Ineff= 2 ,-1
 -3957.1  -598.7  201.55  -598.7    2466  195.06
Permanent Ineff=
       F       F
Bank Sta=4947.5,5113.6
XS Rating Curve= 0 ,0
Exp/Cntr=0.3,0.1