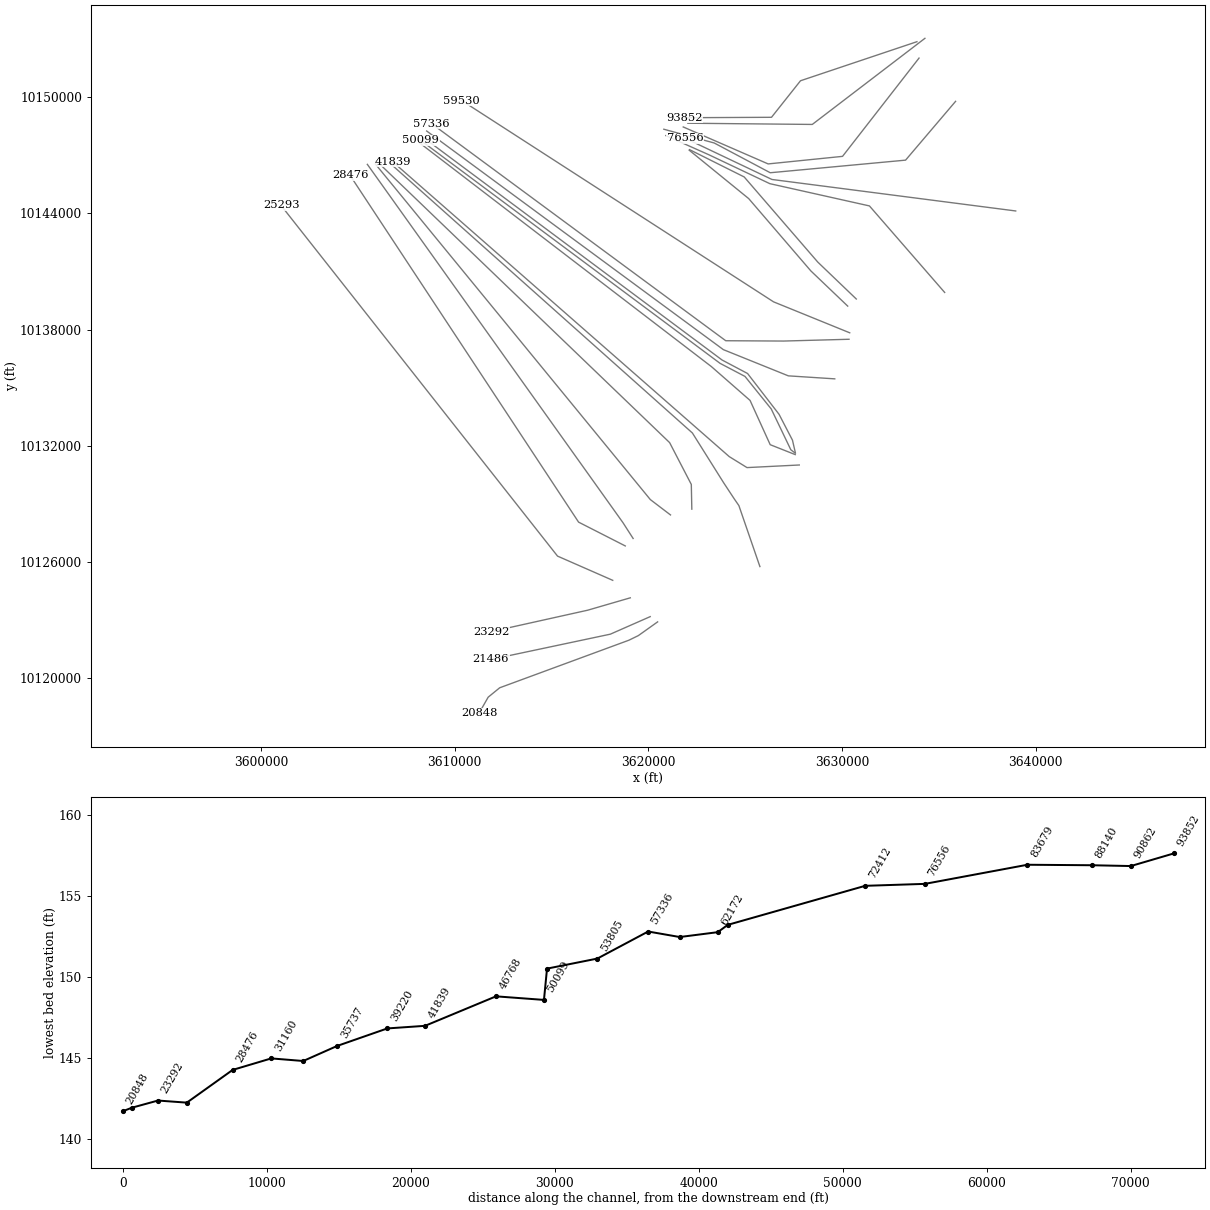
HEC-RAS study NAVASOTA RIVER.prj: NAVASOTA RIVER Base Level Engineering

--- NAVASOTA RIVER.g01 (geometry) --- (continued)

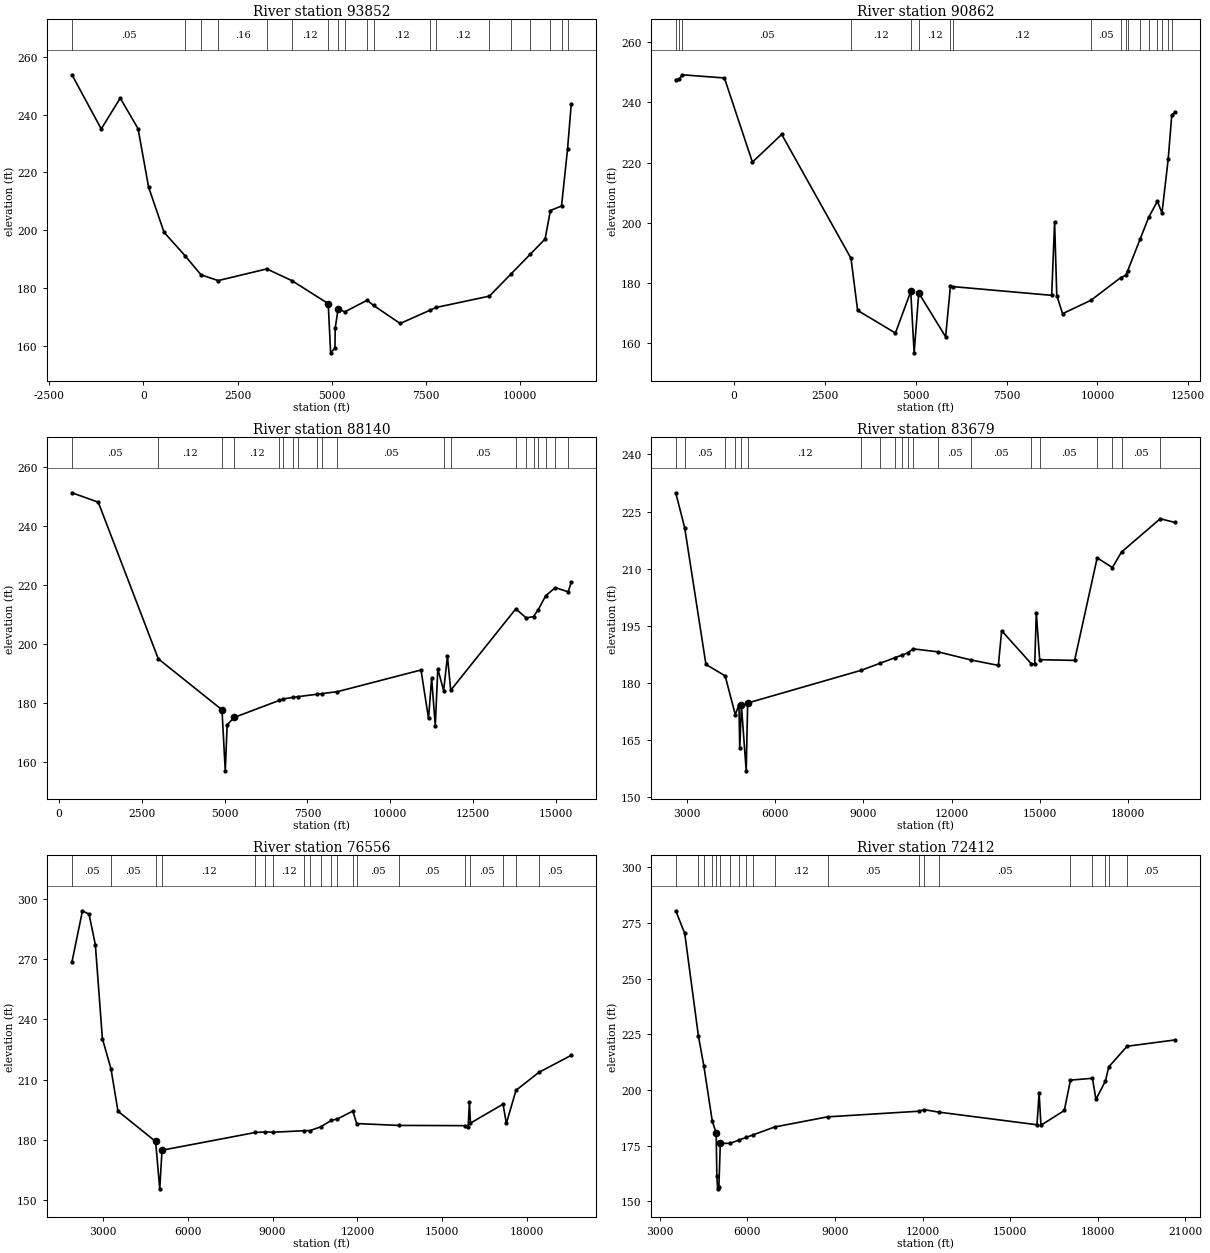
Type RM Length L Ch R = 1 ,93852   ,2990,2990,2990
BEGIN DESCRIPTION:
NAVASOTA RIVER 100
END DESCRIPTION:
XS GIS Cut Line= 4
      3633872.97      10152874.3      3627861.66     10150856.06
      3626364.27     10148968.04      3621866.72     10148946.77
#Sta/Elev= 30
 -1897.7  253.76 -1120.5  235.04    -616   245.7    -143   235.1   135.5  214.94
   545.4  199.32    1100  191.25  1527.2  184.61    1982  182.62  3271.9  186.65
  3939.7  182.58  4901.7  174.66  4965.5  157.64  5079.6  159.27  5087.2   166.2
  5164.5  172.84  5342.3  171.81  5934.5  175.82  6105.6  174.01  6810.1  167.79
  7599.6  172.36  7764.7  173.33  9177.5  177.24  9757.5  184.99   10256  191.65
 10655.3  196.98 10795.9  206.82 11091.9  208.43 11250.7     228 11350.7  243.76
#Mann= 19 ,-1 , 0
 -1897.7     .05       0    1100     .12       0  1527.2     .05       0
    1982     .16       0  3271.9     .05       0  3939.7     .12       0
  4901.7     .07       0  5164.5     .07       0  5342.3     .12       0
  5934.5     .05       0  6105.6     .12       0  7599.6     .07       0
  7764.7     .12       0  9177.5     .05       0  9757.5     .12       0
   10256     .16       0 10795.9     .05       0 11091.9     .05       0
 11250.7      .1       0
Bank Sta=4901.7,5164.5
XS Rating Curve= 0 ,0
Exp/Cntr=0.3,0.1

Type RM Length L Ch R = 1 ,90862   ,2722,2722,2722
BEGIN DESCRIPTION:
NAVASOTA RIVER 101
END DESCRIPTION:
XS GIS Cut Line= 3
      3634285.24     10153047.88       3628469.3     10148599.12
      3622045.85     10148661.89
#Sta/Elev= 30
 -1609.1   247.5 -1507.9  247.72 -1433.3  249.18  -269.1  248.12   501.7  220.18
  1307.8  229.38  3215.6  188.24    3398  170.95  4438.9  163.43  4860.7  177.23
  4953.8  156.86    5081  176.74  5820.4  162.19  5952.3  178.92  6011.7  178.86
  8740.6  175.95  8820.6  200.34  8880.6  175.87  9040.6  169.86  9821.3  174.31
 10641.5  181.84 10785.3  182.66 10830.2  184.04 11176.6  194.67 11410.8  201.86
 11651.1   207.2 11776.4  203.29 11947.3  221.15 12046.1  235.79   12137  236.78
#Mann= 18 ,-1 , 0
 -1609.1     .05       0 -1507.9     .08       0 -1433.3     .05       0
  3215.6     .12       0  4860.7     .07       0    5081     .12       0
  5952.3     .07       0  6011.7     .12       0  9821.3     .05       0
 10641.5     .12       0 10785.3     .16       0 10830.2     .12       0
 11176.6     .16       0 11410.8     .05       0 11651.1     .08       0
 11776.4     .08       0 11947.3     .05       0 12046.1      .1       0
Bank Sta=4860.7,5081
XS Rating Curve= 0 ,0
Exp/Cntr=0.3,0.1

Type RM Length L Ch R = 1 ,88140   ,4461,4461,4461
BEGIN DESCRIPTION:
NAVASOTA RIVER 102
END DESCRIPTION:
XS GIS Cut Line= 4
      3633981.44     10152027.92       3630031.8     10146949.81
      3626190.66     10146559.19      3621807.08     10148468.86
#Sta/Elev= 30
   391.7  251.24    1186  248.05  2998.7  194.91  4921.5  177.62  5020.7  156.91
  5077.1  172.52  5290.7  175.03  6649.3   180.8  6756.1  181.24  7054.3  181.85
  7210.7  182.07    7783  182.88  7941.3  183.11  8405.6  183.77 10929.8  191.12
   11157  174.68 11250.8  188.32 11360.8  172.25   11437  191.49 11613.2  184.15
 11728.6  195.78 11826.6  184.24 13792.7  211.87 14107.6  208.78 14326.6  209.24
 14470.2  211.58   14696  216.33 14983.7  219.06 15373.5  217.64 15467.4  220.93
#Mann= 20 ,-1 , 0
   391.7     .05       0  2998.7     .12       0  4921.5     .07       0
  5290.7     .12       0  6649.3     .07       0  6756.1     .12       0
  7054.3     .12       0  7210.7     .05       0    7783     .12       0
  7941.3     .05       0  8405.6     .05       0 11613.2     .07       0
 11826.6     .05       0 13792.7     .05       0 14107.6     .08       0
 14326.6      .1       0 14470.2     .08       0   14696     .15       0
 14983.7     .05       0 15373.5     .08       0
Bank Sta=4921.5,5290.7
XS Rating Curve= 0 ,0
Exp/Cntr=0.3,0.1

Type RM Length L Ch R = 1 ,83679   ,7123,7123,7123
BEGIN DESCRIPTION:
NAVASOTA RIVER 103
END DESCRIPTION:
XS GIS Cut Line= 5
       3635869.5     10149792.73      3633287.01      10146754.5
      3626299.16     10146103.46      3623408.28     10147640.14
      3620805.58     10148351.54
#Sta/Elev= 30
  2618.2  229.92  2923.2  220.73  3645.4  184.87  4298.9  181.86  4642.7   171.7
  4766.8  174.24  4795.4  162.82  4851.3  174.09  5014.7  156.94  5064.4  174.74
  8929.2  183.34  9566.7  185.18   10083  186.67 10301.3   187.3 10499.1  187.87
   10695  188.95 11532.1  188.17 12658.2  186.04 13587.6  184.61   13700  193.71
 14710.5  185.02 14825.1  185.03 14877.5  198.48 14991.7  186.11 16179.9  185.93
 16947.3  212.83 17464.3   210.3 17774.6  214.37 19092.2  223.11 19595.9  222.12
#Mann= 20 ,-1 , 0
  2618.2     .05       0  2923.2     .05       0  4298.9     .16       0
  4642.7     .12       0  4851.3     .07       0  5064.4     .12       0
  8929.2     .12       0  9566.7     .05       0   10083     .05       0
 10301.3     .12       0 10499.1      .1       0   10695      .1       0
 11532.1     .05       0 12658.2     .05       0 14710.5     .16       0
 14991.7     .05       0 16947.3     .08       0 17464.3      .1       0
 17774.6     .05       0 19092.2     .05       0
Bank Sta=4851.3,5064.4
XS Rating Curve= 0 ,0
Exp/Cntr=0.3,0.1

Type RM Length L Ch R = 1 ,76556   ,4144,4144,4144
BEGIN DESCRIPTION:
NAVASOTA RIVER 104
END DESCRIPTION:
XS GIS Cut Line= 3
      3638972.76     10144128.63      3626385.97     10145756.24
      3621916.27      10147882.6
#Sta/Elev= 30
  1914.7  268.53  2286.2  293.99  2519.1  292.26  2742.2  277.05    2990  230.46
  3295.3  215.31  3540.2  194.37  4869.8  179.32  5016.9  155.76  5096.4  174.96
  8395.9  183.78  8737.1  184.04  9032.5  183.91 10096.1  184.64 10328.9  184.73
 10696.2  186.55 11077.5  189.78 11296.3  190.52 11836.9  194.41 11975.1  188.21
 13459.4  187.29 15797.9  187.17 15911.3   186.6 15956.7  198.74 15993.8  188.43
 17144.1  197.86 17261.8   188.3 17602.4  204.73 18412.6  213.68   19556  222.15
#Mann= 20 ,-1 , 0
  1914.7     .05       0  3295.3     .05       0  4869.8     .07       0
  5096.4     .12       0  8395.9     .05       0  8737.1     .05       0
  9032.5     .12       0 10096.1     .05       0 10328.9     .05       0
 10696.2     .12       0 11077.5     .05       0 11296.3     .12       0
 11836.9      .1       0 11975.1     .05       0 13459.4     .05       0
 15797.9     .16       0 15993.8     .05       0 17144.1     .05       0
 17602.4      .1       0 18412.6     .05       0
Bank Sta=4869.8,5096.4
XS Rating Curve= 0 ,0
Exp/Cntr=0.3,0.1

Type RM Length L Ch R = 1 ,72412   ,9548,9548,9548
BEGIN DESCRIPTION:
NAVASOTA RIVER 105
END DESCRIPTION:
XS GIS Cut Line= 5
      3635305.23     10139918.57      3631420.69     10144389.05
      3626277.46     10145539.22      3623130.51      10147032.5
      3620908.32     10148022.06
#Sta/Elev= 30
  3544.4  280.52  3853.2  270.35  4321.2  224.33    4506  210.98  4798.1  185.92
  4930.9  180.73  4952.7  161.46    4980  155.64    5023  156.39  5072.4  176.07
  5406.9  176.08  5719.5  177.58  5957.9  178.73  6204.1  179.91  6932.7  183.42
  8744.6  187.97 11878.2   190.5   12056   191.2 12572.4  190.06 15921.3  184.42
   15995  198.57 16057.6  184.18 16858.2  190.83 17068.3  204.46 17822.2   205.3
 17941.9  195.81 18266.9  204.06   18381   210.4 19007.9  219.68 20652.9  222.51
#Mann= 20 ,-1 , 0
  3544.4     .05       0  4321.2     .16       0    4506     .05       0
  4798.1     .12       0  4930.9     .07       0  5072.4     .12       0
  5406.9     .12       0  5719.5     .07       0  5957.9     .12       0
  6204.1     .16       0  6932.7     .12       0  8744.6     .05       0
 11878.2     .16       0   12056     .12       0 12572.4     .05       0
 17068.3     .15       0 17822.2     .05       0 18266.9      .1       0
   18381     .05       0 19007.9     .05       0
Bank Sta=4930.9,5072.4
XS Rating Curve= 0 ,0
Exp/Cntr=0.3,0.1

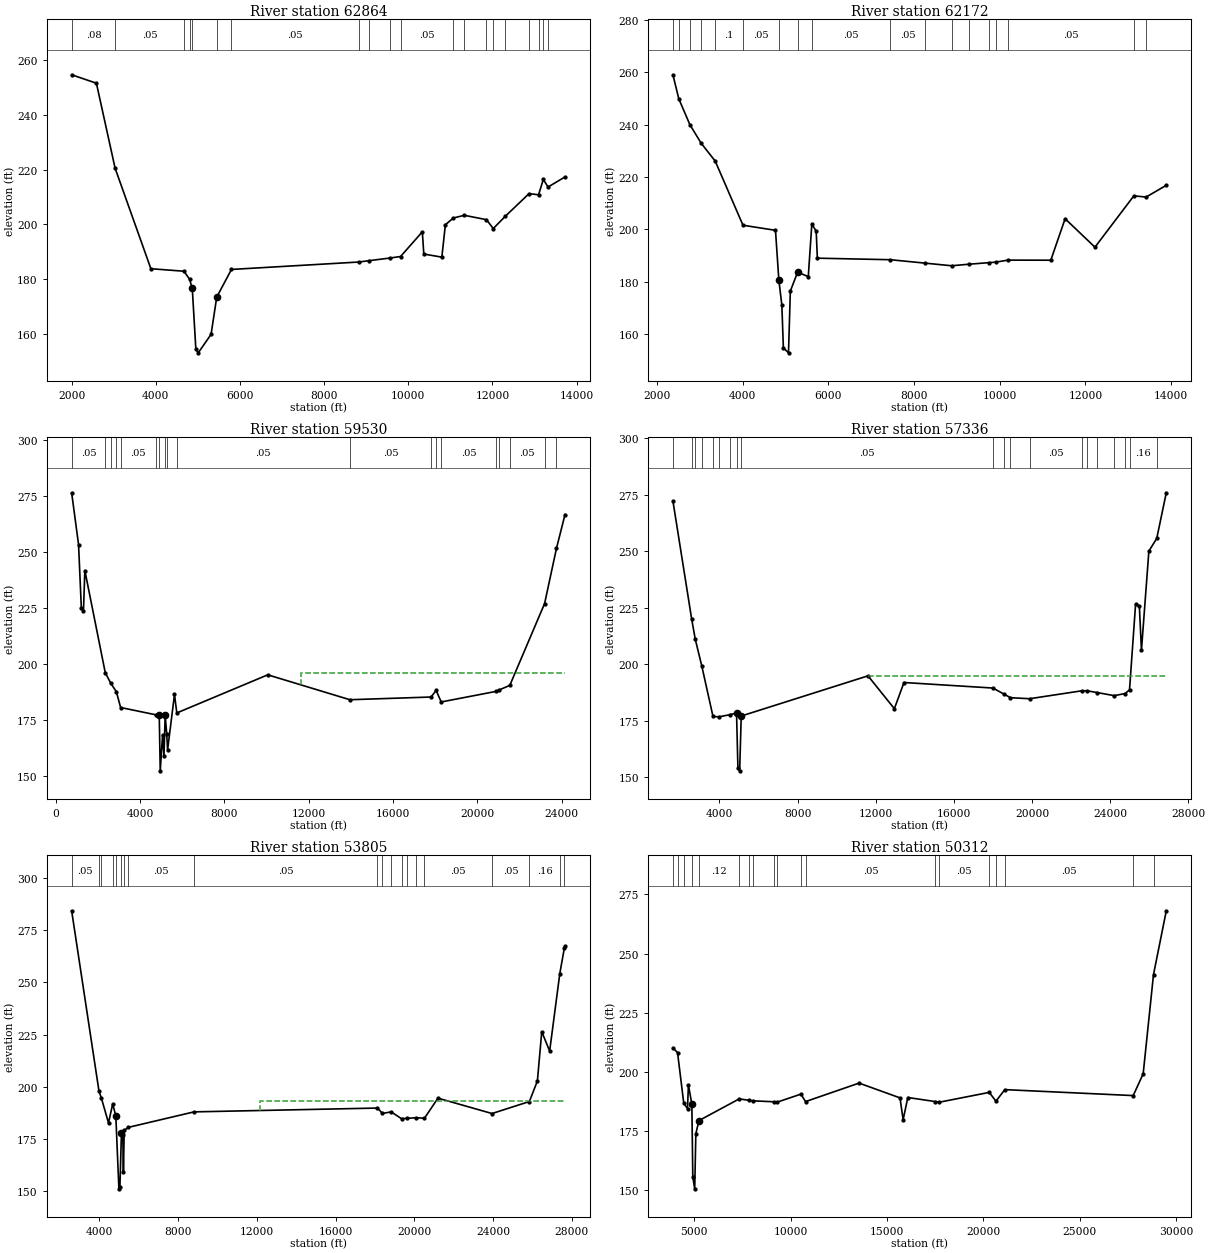
Type RM Length L Ch R = 1 ,62864   ,692,692,692
BEGIN DESCRIPTION:
NAVASOTA RIVER 368
END DESCRIPTION:
XS GIS Cut Line= 4
      3630741.98      10139579.9      3628753.83     10141486.81
      3624953.68     10145886.44      3622132.86     10147296.85
#Sta/Elev= 30
  2002.4  254.52  2590.6  251.45  3034.9  220.48    3885  183.87  4672.3  182.96
  4804.6     180  4868.7  176.67  4953.2  154.67  5009.9  153.23  5315.1  159.96
    5450  173.55  5799.7  183.61  8825.4  186.31  9076.7  186.82  9561.2  187.76
  9817.4  188.32 10334.7  197.31 10369.8  189.22 10798.3  188.09 10882.2   199.9
 11070.8  202.34 11332.9  203.33 11858.6  201.74 12019.8  198.51 12308.7  203.02
 12871.4  211.24 13096.5   210.8   13209   216.4 13321.6  213.63 13724.6  217.31
#Mann= 20 ,-1 , 0
  2002.4     .08       0  3034.9     .05       0  4672.3     .05       0
  4804.6     .05       0  4868.7    .033       0    5450     .05       0
  5799.7     .05       0  8825.4     .05       0  9076.7     .07       0
  9561.2     .07       0  9817.4     .05       0 11070.8     .08       0
 11332.9     .15       0 11858.6     .08       0 12019.8     .15       0
 12308.7     .05       0 12871.4     .05       0 13096.5     .05       0
   13209     .16       0 13321.6     .05       0
Bank Sta=4868.7,5450
XS Rating Curve= 0 ,0
Exp/Cntr=0.3,0.1

Type RM Length L Ch R = 1 ,62172   ,2642,2642,2642
BEGIN DESCRIPTION:
NAVASOTA RIVER 106
END DESCRIPTION:
XS GIS Cut Line= 4
      3630298.94     10139213.12      3628396.36     10141030.78
      3625188.28     10144766.06      3622115.82     10147268.45
#Sta/Elev= 30
  2368.7  259.08  2504.9  249.93  2763.7  240.04  3028.3   232.9  3355.6  226.09
  4004.4  201.56  4763.1  199.62  4840.8  180.75  4911.6  170.97  4947.1   154.7
  5066.8  152.78  5109.7  176.38  5279.8  183.61  5528.4  181.92  5611.1  201.94
    5713  199.33  5740.7  188.97  7444.2  188.38  8243.8  187.09  8875.7  186.07
  9284.6  186.67  9742.8  187.25  9903.6  187.45 10194.8  188.23 11190.4  188.19
 11524.3  204.05 12220.9  193.17 13128.5  212.79 13415.3  212.34 13886.4  216.82
#Mann= 18 ,-1 , 0
  2368.7     .05       0  2504.9     .08       0  2763.7     .08       0
  3028.3      .1       0  3355.6      .1       0  4004.4     .05       0
  4840.8    .033       0  5279.8     .16       0  5611.1     .05       0
  7444.2     .05       0  8243.8      .1       0  8875.7     .05       0
  9284.6     .08       0  9742.8     .05       0  9903.6     .08       0
 10194.8     .05       0 13128.5     .16       0 13415.3     .05       0
Bank Sta=4840.8,5279.8
XS Rating Curve= 0 ,0
Exp/Cntr=0.3,0.1

Type RM Length L Ch R = 1 ,59530   ,2194,2194,2194
BEGIN DESCRIPTION:
NAVASOTA RIVER 380
END DESCRIPTION:
XS GIS Cut Line= 3
      3630402.38     10137833.45      3626471.01     10139432.69
      3610373.74     10149830.84
#Sta/Elev= 30
   755.8  276.63  1084.1  253.46  1215.2  225.23  1316.8  223.92  1382.2  241.91
  2349.1  196.35  2611.9  191.58    2877   187.8  3079.2  180.76  4751.2   177.5
  4912.4  177.19    4959  152.48  5070.1  168.62  5135.9  158.95  5193.4  177.38
  5266.3  169.01  5308.2  161.84  5634.8  186.57  5745.5  178.33 10060.6  195.35
 13955.4  184.23 17807.6  185.44 18048.7  188.39 18289.8  183.23 20868.9  187.91
 21039.4   188.6 21544.3  190.64 23195.9  227.19 23759.5  251.85 24163.6   266.9
#Mann= 19 ,-1 , 0
   755.8     .05       0  2349.1     .16       0  2611.9     .05       0
    2877     .16       0  3079.2     .05       0  4751.2     .16       0
  4912.4     .07       0  5193.4     .12       0  5266.3     .16       0
  5745.5     .05       0 13955.4     .05       0 17807.6     .05       0
 18048.7     .12       0 18289.8     .05       0 20868.9     .07       0
 21039.4     .05       0 21544.3     .05       0 23195.9     .16       0
 23759.5     .05       0
#XS Ineff= 2 , 0
                        11622.87          196.15
Permanent Ineff=
       F       F
Bank Sta=4912.4,5193.4
XS Rating Curve= 0 ,0
Exp/Cntr=0.3,0.1

Type RM Length L Ch R = 1 ,57336   ,3531,3531,3531
BEGIN DESCRIPTION:
NAVASOTA RIVER 383
END DESCRIPTION:
XS GIS Cut Line= 4
      3630367.13     10137499.47      3626988.18     10137407.35
      3624001.65     10137423.94      3608808.91     10148645.32
#Sta/Elev= 30
  1619.8   272.2  2581.1  219.87  2762.5  211.08  3096.2  199.23    3671  176.87
  3987.8  176.72  4522.3  177.65    4876  178.38  4946.1  154.23  5035.8  152.82
  5116.1  177.07 11603.7  194.85 12954.5  180.32 13447.2   191.9 17999.7  189.45
 18561.1  186.79 18898.3  185.19 19875.2  184.72 22540.8  188.22 22823.8  188.23
 23320.5  187.47 24213.6  186.09 24769.8  187.03 24992.1  188.67 25303.7  226.66
 25496.3  225.57 25602.7  206.19 25982.7  250.04 26385.3  255.64 26874.1  275.84
#Mann= 20 ,-1 , 0
  1619.8     .05       0  2581.1     .16       0  2762.5     .05       0
  3096.2     .12       0    3671     .05       0  3987.8     .12       0
  4522.3     .16       0    4876    .033       0  5116.1     .05       0
 17999.7     .16       0 18561.1     .12       0 18898.3     .12       0
 19875.2     .05       0 22540.8     .05       0 22823.8      .1       0
 23320.5     .05       0 24213.6     .16       0 24769.8     .05       0
 24992.1     .16       0 26385.3     .05       0
#XS Ineff= 2 , 0
                        11601.11          194.89
Permanent Ineff=
       F       F
Bank Sta=4876,5116.1
XS Rating Curve= 0 ,0
Exp/Cntr=0.3,0.1

Type RM Length L Ch R = 1 ,53805   ,3493,3493,3493
BEGIN DESCRIPTION:
NAVASOTA RIVER 386
END DESCRIPTION:
XS GIS Cut Line= 4
       3629630.3     10135454.27      3627233.89      10135609.1
      3623878.34     10136963.82        3608560.     10148259.82
#Sta/Elev= 30
  2598.6  284.25  3984.8  198.02    4112  194.47  4470.7  182.69  4681.6  191.78
  4841.5  186.13  4998.1  151.15  5048.7  151.83  5126.5  177.75    5196  176.71
  5228.4  159.15  5267.2  179.11  5483.5  180.59  8813.7  187.99 18129.3  189.82
   18381  187.24 18824.6  187.98 19351.6  184.72 19623.9  184.89   20099  185.19
 20513.4  184.94 21200.5  194.56 23944.7   187.2 25843.3  192.95 26249.5  202.81
 26470.8  226.38 26871.8  217.09 27387.2  254.19 27621.2  266.59 27651.6  267.32
#Mann= 20 ,-1 , 0
  2598.6     .05       0  3984.8     .16       0    4112     .05       0
  4681.6     .16       0  4841.5     .07       0  5126.5     .12       0
  5267.2     .16       0  5483.5     .05       0  8813.7     .05       0
 18129.3     .12       0   18381     .05       0 18824.6     .07       0
 19351.6     .12       0 19623.9     .07       0   20099     .12       0
 20513.4     .05       0 23944.7     .05       0 25843.3     .16       0
 27387.2     .05       0 27621.2     .16       0
#XS Ineff= 2 , 0
                        12155.49          193.18
Permanent Ineff=
       F       F
Bank Sta=4841.5,5126.5
XS Rating Curve= 0 ,0
Exp/Cntr=0.3,0.1

Type RM Length L Ch R = 1 ,50312   ,213,213,213
BEGIN DESCRIPTION:
NAVASOTA RIVER 384
END DESCRIPTION:
XS GIS Cut Line= 6
       3627598.8     10131623.69      3627446.89     10132285.61
      3626754.22     10133622.17      3625128.61     10135730.06
      3623812.47     10136427.34      3608376.52     10147933.84
#Sta/Elev= 30
  3891.2  210.07  4130.6  208.15  4453.9   186.7  4647.9  184.47  4694.9  194.51
  4872.6  186.35  4922.7  155.48  5021.3  150.53  5080.6  173.87  5242.4  179.39
  7327.2  188.55  7821.5  187.99  8048.4  187.74  9135.3  187.34    9308  187.21
 10530.9  190.57 10772.6  187.42 13549.5  195.24 15672.2  188.99 15836.9  179.76
 16078.8  189.15   17514  187.42 17719.5  187.17 20305.2  191.31 20650.2  187.59
 21112.4  192.48 27774.7  189.96 28291.3  199.19 28827.5  241.15 29490.4   268.1
#Mann= 19 ,-1 , 0
  3891.2     .05       0  4130.6     .16       0  4453.9     .16       0
  4872.6     .07       0  5242.4     .12       0  7327.2     .12       0
  7821.5     .16       0  8048.4     .12       0  9135.3     .05       0
    9308     .12       0 10530.9      .1       0 10772.6     .05       0
   17514      .1       0 17719.5     .05       0 20305.2     .12       0
 20650.2     .16       0 21112.4     .05       0 27774.7     .16       0
 28827.5     .05       0
#XS Ineff= 2 , 0
                        13548.85          195.22
Permanent Ineff=
       F       F
Bank Sta=4872.6,5242.4
XS Rating Curve= 0 ,0
Exp/Cntr=0.3,0.1

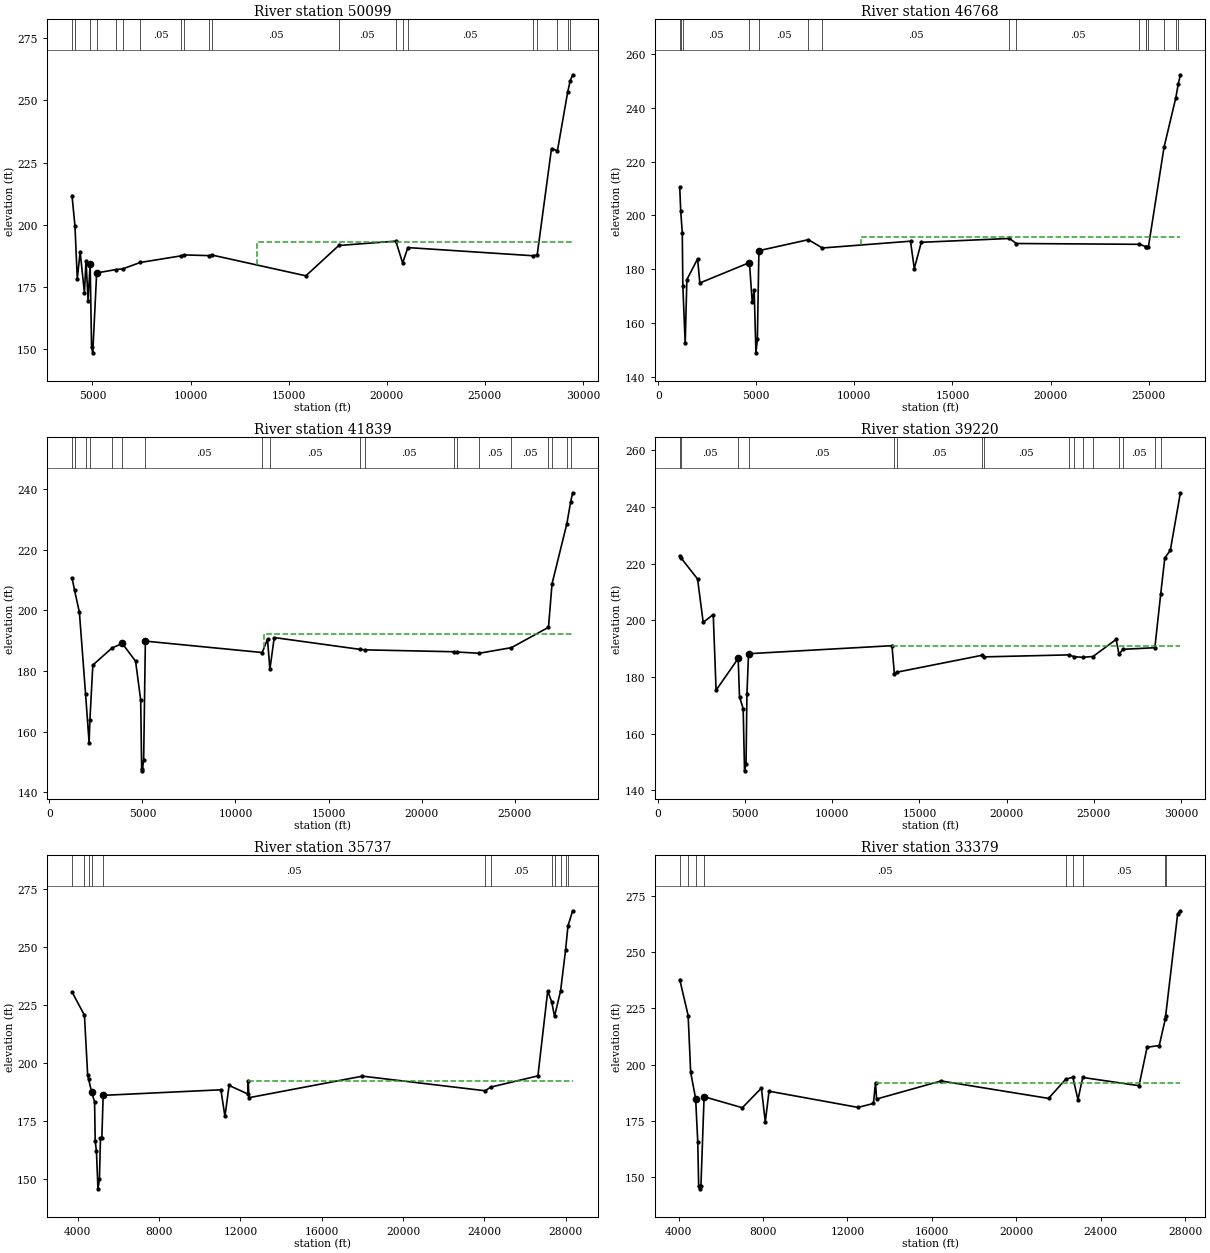
Type RM Length L Ch R = 1 ,50099   ,3331,3331,3331
BEGIN DESCRIPTION:
NAVASOTA RIVER 385
END DESCRIPTION:
XS GIS Cut Line= 6
      3627578.49     10131625.66      3627362.51     10131789.44
      3626352.03      10133896.4      3624995.51     10135579.83
      3623708.98     10136255.04      3608256.75     10147773.66
#Sta/Elev= 30
  3958.9  211.74  4109.9  199.53  4227.6  178.37    4374  189.12  4591.5  172.69
  4672.8  185.66  4777.8  169.61  4883.8  184.39  4955.7  150.78  5016.1   148.6
  5215.1  180.69  6180.4  182.01  6561.7  182.37  7435.8  184.89  9534.7  187.57
  9688.2  187.92   10918  187.65 11107.2  187.85 15877.1  179.53 17555.5  191.71
 20461.6  193.45 20809.4  184.67 21075.6  190.87 27439.9   187.6   27665  187.83
 28396.2  230.65 28697.3  229.73 29220.6  253.29 29347.4  257.82   29474  260.27
#Mann= 20 ,-1 , 0
  3958.9     .05       0  4109.9     .16       0  4883.8     .07       0
  5215.1     .12       0  6180.4     .05       0  6561.7     .05       0
  7435.8     .05       0  9534.7     .05       0  9688.2     .12       0
   10918     .12       0 11107.2     .05       0 17555.5     .05       0
 20461.6     .12       0 20809.4     .16       0 21075.6     .05       0
 27439.9     .05       0   27665     .16       0 28697.3     .05       0
 29220.6     .16       0 29347.4     .05       0
#XS Ineff= 2 , 0
                        13399.04          193.23
Permanent Ineff=
       F       F
Bank Sta=4883.8,5215.1
XS Rating Curve= 0 ,0
Exp/Cntr=0.3,0.1

Type RM Length L Ch R = 1 ,46768   ,4929,4929,4929
BEGIN DESCRIPTION:
NAVASOTA RIVER 388
END DESCRIPTION:
XS GIS Cut Line= 5
      3627589.84     10131540.03      3626296.86     10132052.62
       3625257.8     10134339.56      3623258.67     10136089.08
      3608211.15     10147632.58
#Sta/Elev= 30
  1097.2  210.44  1147.2  201.57  1226.5  193.58  1255.1   173.8  1374.4  152.33
  1460.5  176.11  2007.2  183.81  2120.6  174.85  4648.8  182.44  4650.8  182.44
  4793.6  167.64  4892.4  172.13  4981.4  148.82  5055.2  153.95    5133  186.89
    7653  190.98  8370.1  187.89 12862.2  190.42 13055.3   180.2 13412.1  190.01
   17909  191.44 18253.9  189.56 24528.9  189.26 24880.2  188.37 24888.4  188.35
   24988   188.1 25786.1  225.35 26390.2  243.92 26517.3  249.18 26621.8  252.43
#Mann= 16 ,-1 , 0
  1097.2     .05       0  1147.2     .16       0  1255.1     .05       0
  4648.8     .03       0    5133     .05       0    7653     .12       0
  8370.1     .05       0   17909     .12       0 18253.9     .05       0
 24528.9     .16       0 24880.2     .05       0 24888.4      .1       0
   24988     .16       0 25786.1     .05       0 26390.2     .16       0
 26517.3     .05       0
#XS Ineff= 2 , 0
                        10315.79          192.09
Permanent Ineff=
       F       F
Bank Sta=4650.8,5133
XS Rating Curve= 0 ,0
Exp/Cntr=0.3,0.1

Type RM Length L Ch R = 1 ,41839   ,2619,2619,2619
BEGIN DESCRIPTION:
NAVASOTA RIVER 413
END DESCRIPTION:
XS GIS Cut Line= 4
      3627799.33     10131003.58      3625099.65     10130869.03
      3624182.81     10131436.16      3606801.04     10146676.71
#Sta/Elev= 30
  1218.9  210.81  1354.4  206.75  1616.6  199.35  1946.1  172.46  2137.3  156.29
  2179.7  163.77  2337.5  181.96    3369  187.61  3921.9  189.09  4635.1  183.22
  4909.3  170.38  4961.3  147.53  4997.2     147  5067.7   150.7  5160.5  189.87
 11438.1   186.1 11722.1  190.54 11850.2  180.57 12083.6  191.05 16675.1  187.16
 16946.2  186.99 21733.9  186.36 21915.4  186.27 23097.8  185.86 24829.7  187.72
 26818.7  194.44 27009.5  208.81 27807.6  228.73 28011.3  235.97 28117.1   238.9
#Mann= 19 ,-1 , 0
  1218.9     .05       0  1354.4     .16       0  1946.1     .16       0
  2179.7     .05       0    3369     .05       0  3921.9     .03       0
  5160.5     .05       0 11438.1     .16       0 11850.2     .05       0
 16675.1     .16       0 16946.2     .05       0 21733.9      .1       0
 21915.4     .05       0 23097.8     .05       0 24829.7     .05       0
 26818.7     .16       0 27009.5     .05       0 27807.6     .05       0
 28011.3     .16       0
#XS Ineff= 2 , 0
                        11523.68          192.19
Permanent Ineff=
       F       F
Bank Sta=3921.9,5160.5
XS Rating Curve= 0 ,0
Exp/Cntr=0.3,0.1

Type RM Length L Ch R = 1 ,39220   ,3483,3483,3483
BEGIN DESCRIPTION:
NAVASOTA RIVER 414
END DESCRIPTION:
XS GIS Cut Line= 6
      3625765.01     10125755.21      3624679.93     10128906.27
      3624441.92     10129252.26      3623889.84      10130090.8
      3622280.26     10132656.69        3606669.     10146591.73
#Sta/Elev= 30
  1255.2   222.8  1316.7   222.1  2277.3  214.57    2600  199.28  3176.3  202.03
  3338.8   175.3  4605.5  186.51  4683.2  172.93  4892.3  168.81  4970.4  146.84
  5056.9  149.42  5108.2  173.96  5201.5   188.2 13426.9  191.03 13567.2  180.88
 13697.1  181.66 18580.7  187.63 18709.3  187.08 23553.1  187.78 23894.2  187.13
 24356.9  186.93 24955.3  187.21 26281.5  193.24 26447.2  187.99 26667.8  189.76
   28503  190.31 28839.6  209.37 29072.1  221.96 29390.6  224.74 29966.7  245.02
#Mann= 16 ,-1 , 0
  1255.2     .08       0  1316.7     .05       0  4605.5    .033       0
  5201.5     .05       0 13567.2     .16       0 13697.1     .05       0
 18580.7     .16       0 18709.3     .05       0 23553.1      .1       0
 23894.2     .05       0 24356.9      .1       0 24955.3     .05       0
 26447.2     .12       0 26667.8     .05       0   28503     .16       0
 28839.6     .05       0
#XS Ineff= 2 , 0
                        13427.19          191.03
Permanent Ineff=
       F       F
Bank Sta=4605.5,5201.5
XS Rating Curve= 0 ,0
Exp/Cntr=0.3,0.1

Type RM Length L Ch R = 1 ,35737   ,2358,2358,2358
BEGIN DESCRIPTION:
NAVASOTA RIVER 390
END DESCRIPTION:
XS GIS Cut Line= 4
      3622250.12     10128721.71      3622223.84     10129998.84
      3621104.29     10132159.19      3606035.82     10146648.89
#Sta/Elev= 30
  3722.6  230.59    4333  220.58  4492.7  194.76  4538.7  193.03  4682.7   187.6
  4832.8  183.21  4862.8  166.34  4922.8  162.08  4998.7  145.76  5070.7  149.85
  5122.4  167.53  5188.8  167.55  5255.1  186.04 11043.3  188.44 11241.4  176.95
 11446.4  190.31   12359  186.66 12387.3  192.08 12422.5  185.03 18002.7  194.31
 24042.1  188.01 24299.4  189.57 26629.8  194.43 27111.9  230.97 27309.3  226.31
   27447  220.03 27747.2  231.18 27987.6  248.49 28109.4  259.07   28338  265.57
#Mann= 12 ,-1 , 0
  3722.6     .05       0    4333     .16       0  4538.7     .05       0
  4682.7     .07       0  5255.1     .05       0 24042.1     .12       0
 24299.4     .05       0 27309.3     .08       0   27447     .05       0
 27747.2     .16       0 27987.6     .05       0 28109.4     .16       0
#XS Ineff= 2 , 0
                        12387.48          192.13
Permanent Ineff=
       F       F
Bank Sta=4682.7,5255.1
XS Rating Curve= 0 ,0
Exp/Cntr=0.3,0.1

Type RM Length L Ch R = 1 ,33379   ,2219,2219,2219
BEGIN DESCRIPTION:
NAVASOTA RIVER 389
END DESCRIPTION:
XS GIS Cut Line= 3
      3621149.48     10128422.58      3620107.85     10129216.83
      3605908.38     10146557.39
#Sta/Elev= 30
  4056.8  237.82  4454.7  221.84  4575.1  196.53    4810  184.94  4909.8  165.76
  4953.4  145.95  4996.4  144.83  5059.5   145.9  5210.4  185.76    7023  180.86
  7925.2   189.6  8110.4  174.58  8287.7  188.21 12508.1  181.01   13233  182.76
 13333.5  191.99   13383  184.73 16437.8  192.76 21533.1  185.01 22346.2  193.55
 22683.9   194.4 22925.6  184.41 23150.5  194.32 25818.8  190.66 26202.1  207.76
   26777  208.49 27067.3   220.4 27081.5  221.69   27652  267.14 27779.2  268.37
#Mann= 9 ,-1 , 0
  4056.8     .05       0  4454.7     .16       0    4810    .033       0
  5210.4     .05       0 22346.2     .16       0 22683.9     .12       0
 23150.5     .05       0 27067.3     .16       0 27081.5     .05       0
#XS Ineff= 2 , 0
                        13334.09          191.99
Permanent Ineff=
       F       F
Bank Sta=4810,5210.4
XS Rating Curve= 0 ,0
Exp/Cntr=0.3,0.1

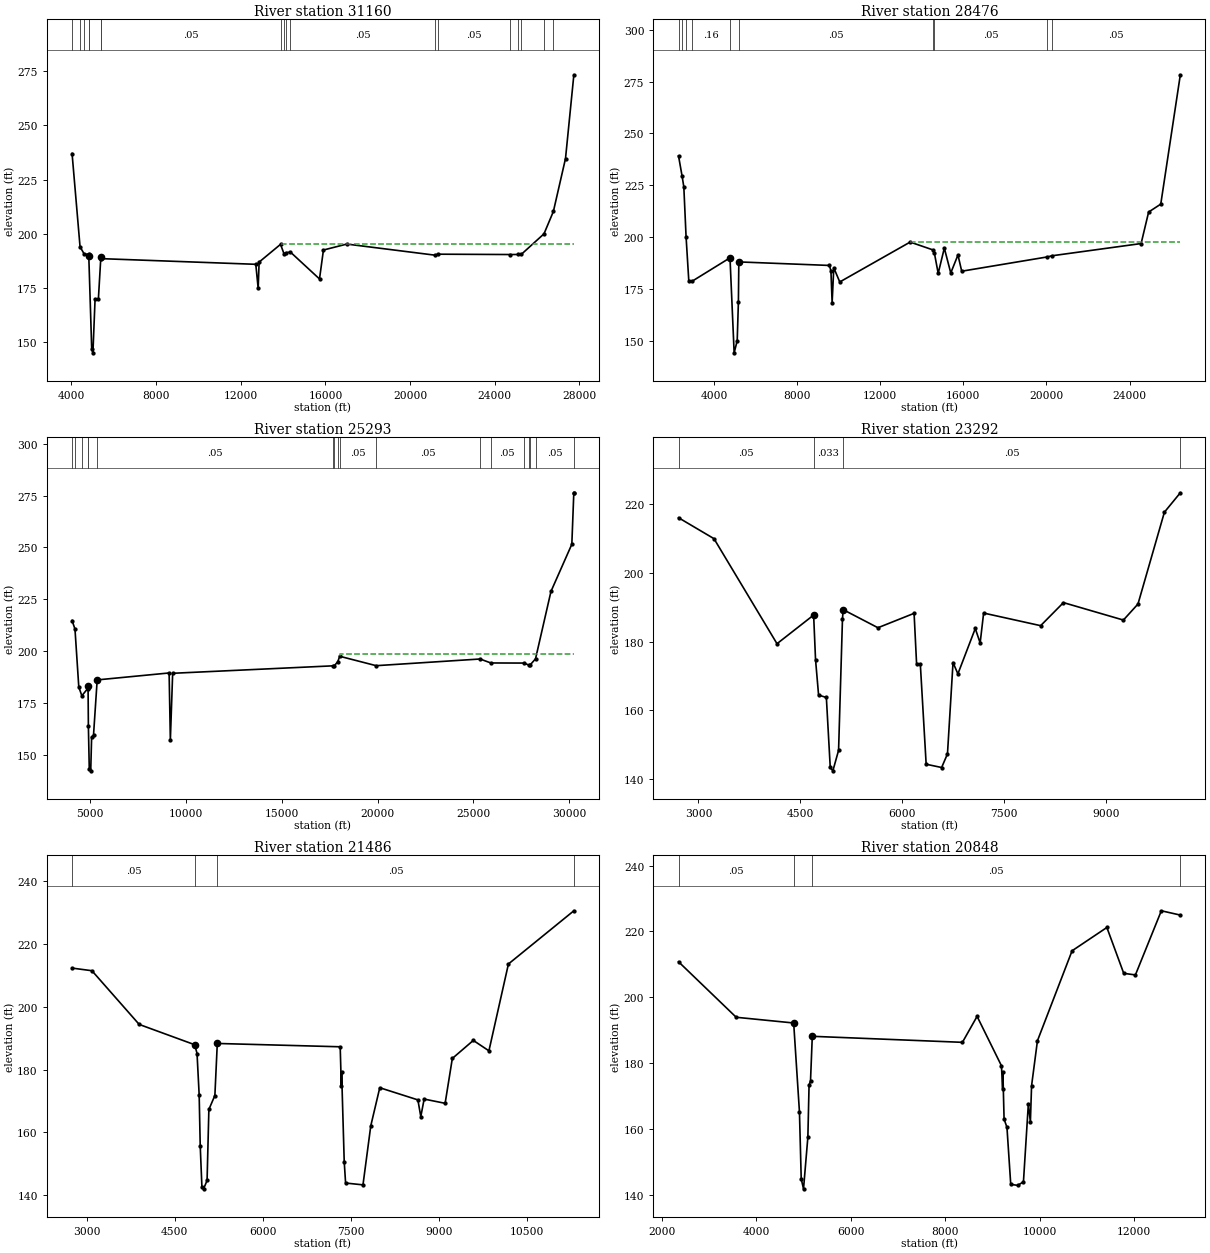
Type RM Length L Ch R = 1 ,31160   ,2684,2684,2684
BEGIN DESCRIPTION:
NAVASOTA RIVER 387
END DESCRIPTION:
XS GIS Cut Line= 3
      3619219.48     10127206.89      3618695.83      10128022.1
      3605497.06     10146536.59
#Sta/Elev= 30
  4031.1     237  4408.4  193.93  4598.7   190.7  4810.3  190.42  4821.2  189.68
  4959.3   146.7  5016.2  144.99  5117.3  169.68  5274.6  169.88  5390.2  189.12
  5412.7  188.47 12710.6  185.86 12823.7  174.74   12868  186.88 13879.7  195.07
 14042.1  190.76 14130.6  191.17 14342.7  191.54 15720.7   179.1 15906.8  192.45
 17010.7   195.2 21173.4  190.08 21312.8  190.53 24739.9  190.37 25094.1  190.39
 25249.3   190.4 26326.4  199.92 26769.8  210.25 27342.9  234.69 27737.5  273.35
#Mann= 18 ,-1 , 0
  4031.1     .16       0  4408.4     .05       0  4598.7      .1       0
  4810.3     .12       0  4821.2    .033       0  5390.2     .16       0
  5412.7     .05       0 13879.7     .12       0 14042.1     .05       0
 14130.6     .12       0 14342.7     .05       0 21173.4     .12       0
 21312.8     .05       0 24739.9     .05       0 25094.1      .1       0
 25249.3     .05       0 26326.4     .16       0 26769.8     .05       0
#XS Ineff= 2 , 0
                        13878.35          195.35
Permanent Ineff=
       F       F
Bank Sta=4821.2,5390.2
XS Rating Curve= 0 ,0
Exp/Cntr=0.3,0.1

Type RM Length L Ch R = 1 ,28476   ,3183,3183,3183
BEGIN DESCRIPTION:
NAVASOTA RIVER 382
END DESCRIPTION:
XS GIS Cut Line= 3
      3618814.18     10126821.21       3616403.3     10128051.61
      3604608.41     10145961.87
#Sta/Elev= 30
  2293.3  239.17  2465.8  229.35  2547.7  224.25  2656.7   200.1  2786.6  179.06
  2956.2  178.84  4770.1  190.06  4969.9  144.28  5117.1   150.1  5174.3   168.6
  5195.3  188.09  9556.4  186.39  9628.7   183.7  9685.9  168.39  9765.6  185.25
 10053.3  178.43 13441.5  197.65 14530.2  193.91 14605.1  192.51 14790.8  182.57
 15085.9  194.74 15396.1  182.77 15742.5  191.43 15923.2  183.61   20046   190.5
 20275.5  191.06 24557.9  196.94 24919.3  212.12 25503.6  215.94 26445.2  278.26
#Mann= 10 ,-1 , 0
  2293.3     .05       0  2465.8     .16       0  2656.7     .12       0
  2956.2     .16       0  4770.1     .07       0  5195.3     .05       0
 14530.2      .1       0 14605.1     .05       0   20046     .08       0
 20275.5     .05       0
#XS Ineff= 2 , 0
                        13440.91           197.7
Permanent Ineff=
       F       F
Bank Sta=4770.1,5195.3
XS Rating Curve= 0 ,0
Exp/Cntr=0.3,0.1

Type RM Length L Ch R = 1 ,25293   ,2001,2001,2001
BEGIN DESCRIPTION:
NAVASOTA RIVER 381
END DESCRIPTION:
XS GIS Cut Line= 3
      3618166.41     10125044.46      3615317.01     10126295.36
      3601039.06     10144416.61
#Sta/Elev= 30
  4058.8  214.73    4211  210.59    4410  182.63  4569.7  178.45    4869  181.87
  4893.5     183    4910   163.8  4956.7  143.25    5032  142.26    5079  158.48
  5177.5   159.4  5369.2   186.1  9122.9  189.45  9187.1  157.09  9307.3  189.29
 17678.9  192.89 17743.6  192.94 17921.8  194.86   18024  197.49 19925.1  192.96
 25348.1  196.18 25908.8  194.27 27633.8  194.22 27876.5  193.33 27943.9  193.16
 28240.7  196.26 29046.4  228.75 30135.1   251.5 30238.3  276.28   30241  276.32
#Mann= 18 ,-1 , 0
  4058.8     .05       0    4211     .16       0  4569.7     .05       0
    4869     .12       0  4893.5    .033       0  5369.2     .05       0
 17678.9      .1       0 17743.6     .05       0 17921.8     .08       0
   18024     .05       0 19925.1     .05       0 25348.1     .12       0
 25908.8     .05       0 27633.8     .16       0 27876.5     .12       0
 27943.9     .16       0 28240.7     .05       0 30238.3     .16       0
#XS Ineff= 2 , 0
                        18038.32          198.75
Permanent Ineff=
       F       F
Bank Sta=4893.5,5369.2
XS Rating Curve= 0 ,0
Exp/Cntr=0.3,0.1

Type RM Length L Ch R = 1 ,23292   ,1806,1806,1806
BEGIN DESCRIPTION:
NAVASOTA RIVER 379
END DESCRIPTION:
XS GIS Cut Line= 3
      3619073.51     10124140.63      3616871.18      10123500.4
      3611893.04     10122393.57
#Sta/Elev= 30
  2706.5  216.02  3228.7  209.93  4157.2  179.37    4697  187.71    4725  174.75
  4769.9  164.43  4884.5  163.73  4941.8  143.38  4980.3  142.39  5064.5  148.36
    5122  186.66  5132.2  189.28  5644.4  184.02  6177.1  188.21  6214.1   173.4
  6269.3  173.33  6354.9  144.31  6582.8  143.36  6668.9  147.31  6750.8   173.9
  6822.5  170.59  7078.6   183.8  7150.3  179.59  7201.6  188.29  8041.6  184.62
  8377.7  191.33    9261  186.25  9475.8  190.92    9865  217.63 10099.7  223.28
#Mann= 4 ,-1 , 0
  2706.5     .05       0    4697    .033       0  5132.2     .05       0
 10099.7     .05       0
#XS Ineff= 2 , 0
                         6176.55          188.19
Permanent Ineff=
       F       F
Bank Sta=4697,5132.2
XS Rating Curve= 0 ,0
Exp/Cntr=0.3,0.1

Type RM Length L Ch R = 1 ,21486   ,638,638,638
BEGIN DESCRIPTION:
NAVASOTA RIVER 378
END DESCRIPTION:
XS GIS Cut Line= 3
      3620101.97      10123168.7      3618043.06     10122262.55
      3611875.33      10120955.5
#Sta/Elev= 30
  2750.5  212.36  3089.1  211.52  3894.8  194.39  4841.8  187.91  4880.9  185.11
  4917.2  171.89  4935.1  155.71  4963.9  142.64  4992.5  141.95  5052.1  144.62
  5082.7  167.27    5185  171.72  5226.2  188.32  7321.4  187.26  7340.3  174.76
  7345.4  179.31    7390  150.59  7413.4   143.8  7709.8  143.22  7842.7  162.05
    7996   174.2  8645.7  170.32  8695.4     165  8752.5  170.58  9110.2  169.23
  9232.9  183.54  9590.7  189.29  9856.8  185.97 10189.2  213.67 11304.7  230.64
#Mann= 4 ,-1 , 0
  2750.5     .05       0  4841.8    .033       0  5226.2     .05       0
 11304.7     .05       0
Bank Sta=4841.8,5226.2
XS Rating Curve= 0 ,0
Exp/Cntr=0.3,0.1

Type RM Length L Ch R = 1 ,20848   ,319,319,319
BEGIN DESCRIPTION:
NAVASOTA RIVER 370
END DESCRIPTION:
XS GIS Cut Line= 6
       3620484.6     10122897.79      3619491.15     10122189.77
      3619004.51      10121951.6      3612330.45     10119492.71
       3611736.2      10119007.4       3611258.8     10118170.19
#Sta/Elev= 30
  2358.5  210.79  3578.9  193.91  4794.8  192.17  4917.1  165.13  4954.5  144.75
  5003.2  141.73  5095.2  157.47  5120.4  173.27    5151  174.55  5188.7  188.12
  8365.5  186.29  8675.8  194.19  9191.4  179.16  9216.5  172.19  9221.8  177.27
  9246.9  162.93  9307.7  160.45  9387.8   143.1  9535.1  142.78  9656.8  143.87
  9760.9  167.65  9803.6  162.05  9828.7  173.09  9952.8  186.76 10685.8  214.13
   11422  221.22 11778.9  207.27 12025.9  206.79 12574.6   226.3 12976.3  224.99
#Mann= 4 ,-1 , 0
  2358.5     .05       0  4794.8    .033       0  5188.7     .05       0
 12976.3     .05       0
Bank Sta=4794.8,5188.7
XS Rating Curve= 0 ,0
Exp/Cntr=0.3,0.1