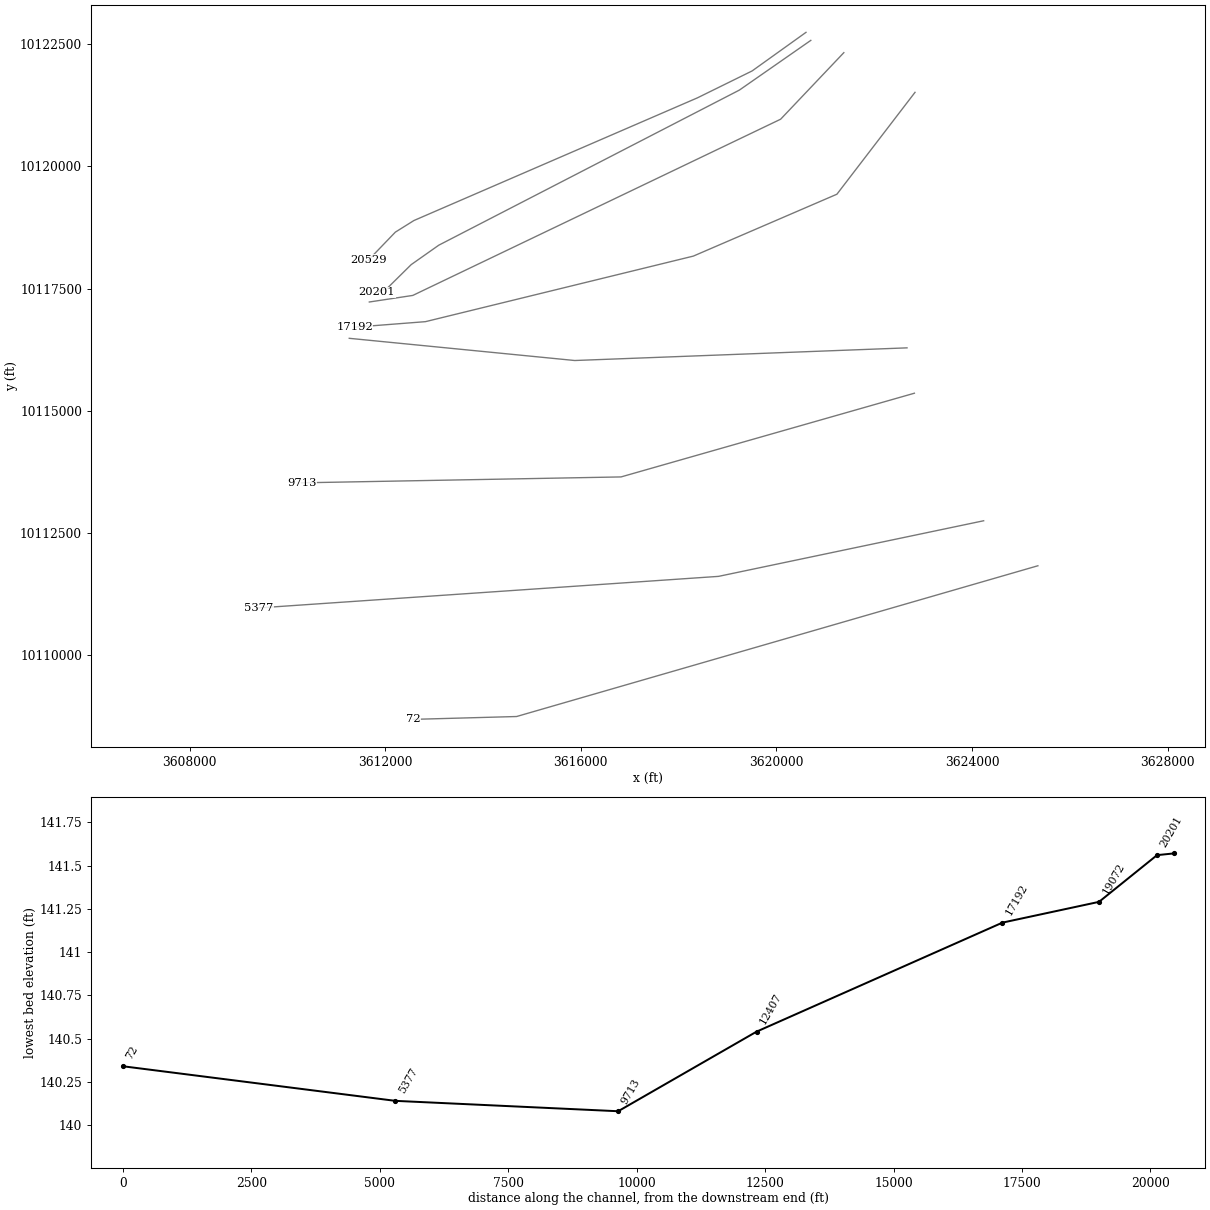
HEC-RAS study NAVASOTA RIVER.prj: NAVASOTA RIVER Base Level Engineering

--- NAVASOTA RIVER.g01 (geometry) --- (continued)

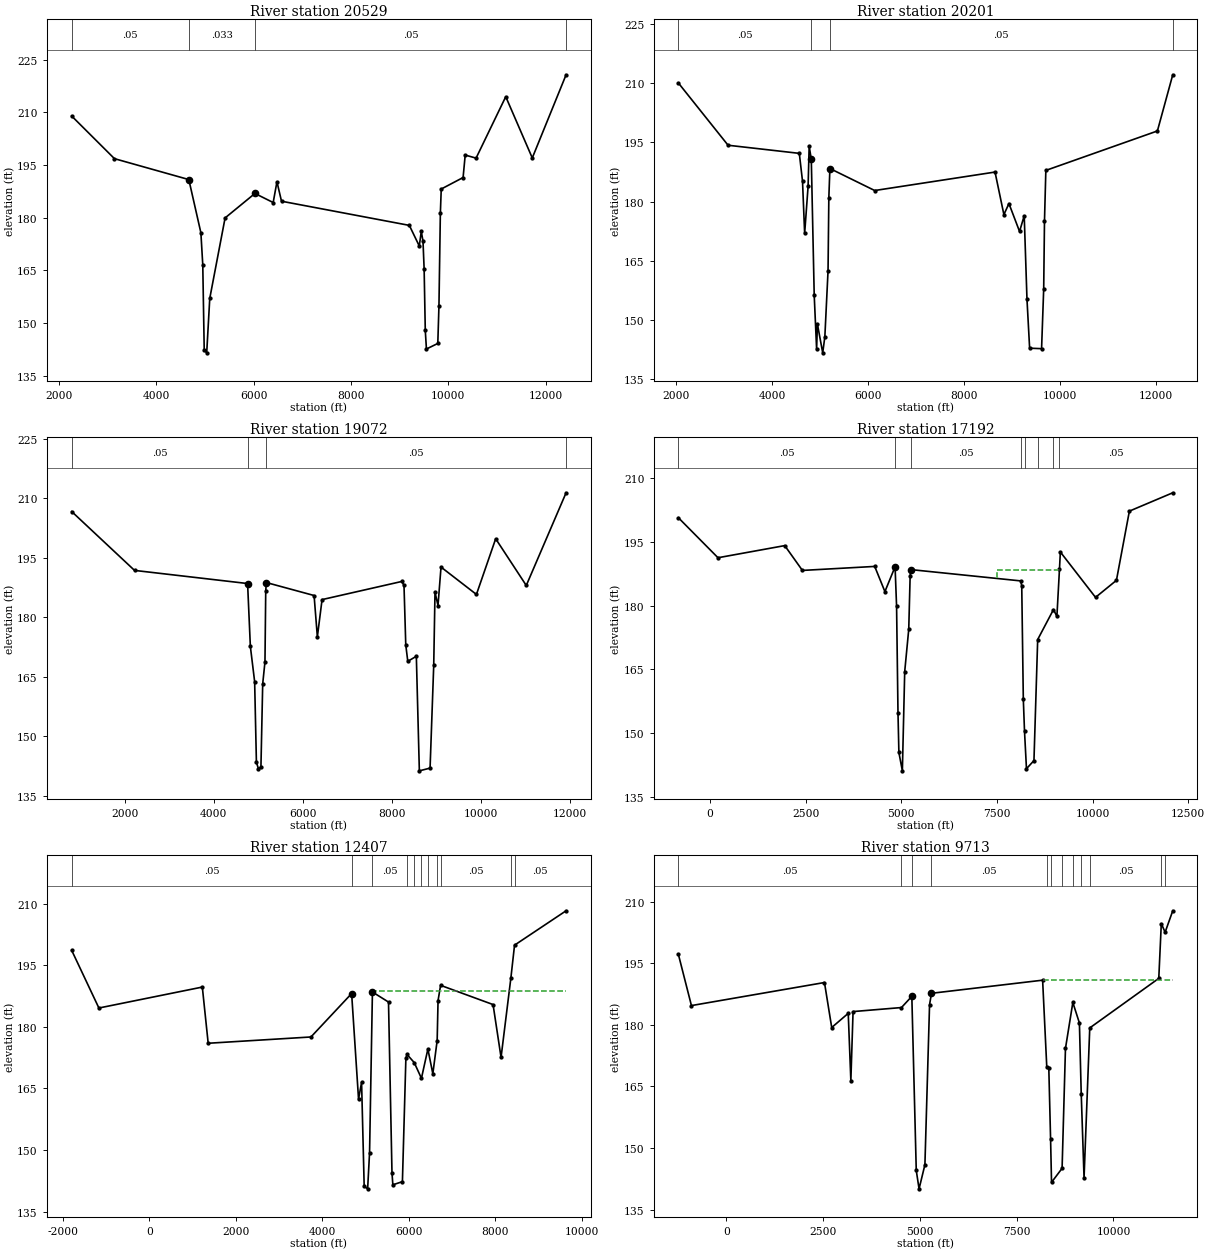
Type RM Length L Ch R = 1 ,20529   ,328,328,328
BEGIN DESCRIPTION:
NAVASOTA RIVER 369
END DESCRIPTION:
XS GIS Cut Line= 6
      3620604.92     10122738.02      3619503.15     10121948.98
       3618387.7     10121399.93      3612588.22     10118890.39
      3612208.01     10118652.54      3611659.42     10118083.12
#Sta/Elev= 30
    2262  208.93  3140.3  196.81  4668.9  190.86  4916.8  175.73  4955.6  166.59
  4985.4  142.33  5036.5  141.57    5099  157.05  5414.3  179.95  6027.5  186.91
  6402.3  184.33  6479.9  190.23  6573.5   184.7  9200.2  177.83  9404.9  171.96
  9445.7  176.09    9481   173.4  9504.6  165.39  9528.1  147.96  9551.7  142.66
  9785.4  144.24    9809   154.9    9838  181.26  9856.1  188.17 10305.1  191.44
 10348.5  197.83 10571.9  196.96 11181.8  214.44   11727  197.01 12421.6  220.67
#Mann= 4 ,-1 , 0
    2262     .05       0  4668.9    .033       0  6027.5     .05       0
 12421.6     .05       0
Bank Sta=4668.9,6027.5
XS Rating Curve= 0 ,0
Exp/Cntr=0.3,0.1

Type RM Length L Ch R = 1 ,20201   ,1129,1129,1129
BEGIN DESCRIPTION:
NAVASOTA RIVER 371
END DESCRIPTION:
XS GIS Cut Line= 6
      3620703.23     10122573.87      3619243.48     10121557.85
       3613096.9     10118386.37      3612532.25      10117988.6
      3612048.96      10117511.7      3611832.41     10117426.15
#Sta/Elev= 30
  2049.5  210.11  3085.2  194.29  4569.5  192.23  4636.4  185.14  4680.7  171.89
  4752.8  183.88    4775  194.05  4819.3  190.73  4880.2  156.16  4930.1  142.51
  4946.6  148.89  5057.2  141.56  5101.8  145.65  5168.3  162.42  5184.8  180.99
    5207  188.38  6140.5  182.79  8647.7  187.48  8832.5  176.67  8937.5  179.48
  9158.7  172.39    9256  176.39  9313.6  155.14  9368.6  142.74  9617.7  142.62
  9661.9  157.84  9678.4  175.08  9706.6   187.9 12031.1  197.92 12351.1  212.19
#Mann= 4 ,-1 , 0
  2049.5     .05       0  4819.3    .033       0    5207     .05       0
 12351.1     .05       0
Bank Sta=4819.3,5207
XS Rating Curve= 0 ,0
Exp/Cntr=0.3,0.1

Type RM Length L Ch R = 1 ,19072   ,1880,1880,1880
BEGIN DESCRIPTION:
NAVASOTA RIVER 376
END DESCRIPTION:
XS GIS Cut Line= 4
      3621378.36     10122322.79      3620086.27     10120961.98
      3612564.93     10117358.83      3611676.11     10117224.42
#Sta/Elev= 30
   804.6  206.66  2217.4  191.82  4759.2  188.51  4821.6  172.64  4917.7  163.78
  4957.5  143.46  5002.8  141.81  5059.3  142.32    5099  163.23  5149.9  168.76
    5167  186.61  5180.6  188.76  6254.3  185.49  6327.8  175.07  6433.6  184.46
  8224.8  189.03  8275.7  188.07  8315.5  173.04  8360.8   168.9  8553.2  170.17
  8620.9  141.29  8861.9  141.98    8944  167.87  8972.8  186.32  9040.2  182.97
  9108.1  192.66  9904.2  185.76 10336.9   199.8 11024.9  188.02 11919.9  211.39
#Mann= 4 ,-1 , 0
   804.6     .05       0  4759.2    .033       0  5180.6     .05       0
 11919.9     .05       0
#XS Ineff= 2 , 0
       0                  8224.8       0  189.03
Permanent Ineff=
       F       F
Bank Sta=4759.2,5180.6
XS Rating Curve= 0 ,0
Exp/Cntr=0.3,0.1

Type RM Length L Ch R = 1 ,17192   ,4785,4785,4785
BEGIN DESCRIPTION:
NAVASOTA RIVER 377
END DESCRIPTION:
XS GIS Cut Line= 5
      3622834.07     10121511.69      3621236.83     10119428.32
      3618301.23     10118162.91      3612823.63     10116822.42
      3611372.25     10116709.57
#Sta/Elev= 30
  -821.9  200.63   213.1  191.23  1957.3  194.08  2418.8  188.25    4308  189.19
  4574.4  183.27  4840.1  189.12  4879.3   179.8  4916.1  154.82  4939.6  145.48
  5030.5  141.17  5091.8   164.5  5197.2  174.44  5233.7  187.01  5256.5  188.44
  8121.3  185.79  8149.4  184.63  8190.6  157.98  8221.9  150.44  8272.9  141.67
  8468.5  143.58    8566  172.02    8979  179.06  9067.9  177.44  9134.8  188.47
  9158.3  192.58 10077.2  181.92 10623.4  185.92 10961.7  202.18   12095  206.49
#Mann= 8 ,-1 , 0
  -821.9     .05       0  4840.1    .033       0  5256.5     .05       0
  8121.3     .16       0  8221.9     .05       0    8566     .12       0
    8979     .16       0  9134.8     .05       0
#XS Ineff= 1 ,-1
  7507.2  9158.3  188.41
Permanent Ineff=
       F
Bank Sta=4840.1,5256.5
XS Rating Curve= 0 ,0
Exp/Cntr=0.3,0.1

Type RM Length L Ch R = 1 ,12407   ,2694,2694,2694
BEGIN DESCRIPTION:
NAVASOTA RIVER 375
END DESCRIPTION:
XS GIS Cut Line= 3
      3622670.43     10116286.78      3615876.75     10116028.01
      3611265.64     10116481.95
#Sta/Elev= 30
 -1798.6  198.59 -1169.8  184.56  1221.9  189.66  1357.4  175.98  3733.7  177.51
  4674.4  188.08  4834.5  162.37  4904.6  166.48  4964.6  141.17  5044.6  140.54
  5089.1  149.33  5155.4  188.46  5527.2  186.01  5607.6  144.44  5627.7  141.52
  5848.7  142.29  5929.1  172.37  5955.7  173.25  6122.3  171.27  6288.7  167.44
  6437.6  174.57  6552.1  168.55  6652.4  176.65  6672.7  186.36  6731.6  190.08
  7944.9   185.4  8129.7  172.54  8357.6  191.94  8441.5  199.86  9633.4  208.23
#Mann= 11 ,-1 , 0
 -1798.6     .05       0  4674.4    .033       0  5155.4     .05       0
  5955.7     .12       0  6122.3     .07       0  6288.7     .12       0
  6437.6     .07       0  6652.4     .16       0  6731.6     .05       0
  8357.6     .08       0  8441.5     .05       0
#XS Ineff= 2 , 0
                         5175.58          188.63
Permanent Ineff=
       F       F
Bank Sta=4674.4,5155.4
XS Rating Curve= 0 ,0
Exp/Cntr=0.3,0.1

Type RM Length L Ch R = 1 ,9713    ,4336,4336,4336
BEGIN DESCRIPTION:
NAVASOTA RIVER 374
END DESCRIPTION:
XS GIS Cut Line= 3
      3622821.11     10115359.27      3616823.11     10113647.81
      3610291.12     10113527.23
#Sta/Elev= 30
 -1237.4  197.15  -900.1  184.68  2536.5  190.29  2723.6  179.34  3150.4  182.79
    3218  166.41  3274.8  183.22  4525.5   184.2  4793.1  186.93  4907.5  144.55
    4980  140.08    5131  145.95    5251  184.91  5301.1  187.67  8171.5  190.86
  8278.7  169.76  8331.6  169.39  8377.3  152.17  8401.6  141.66  8674.4  145.07
  8761.6  174.24    8952  185.43  9121.7  180.45  9168.8  163.24  9241.7  142.75
  9389.1  179.24 11172.1   191.3 11237.2  204.63 11335.8  202.52 11533.1  207.75
#Mann= 12 ,-1 , 0
 -1237.4     .05       0  4525.5     .16       0  4793.1    .033       0
  5301.1     .05       0  8278.7     .16       0  8377.3     .05       0
  8674.4     .16       0    8952     .12       0  9168.8     .16       0
  9389.1     .05       0 11237.2     .08       0 11335.8     .05       0
#XS Ineff= 2 , 0
                         8171.51          190.86
Permanent Ineff=
       F       F
Bank Sta=4793.1,5301.1
XS Rating Curve= 0 ,0
Exp/Cntr=0.3,0.1

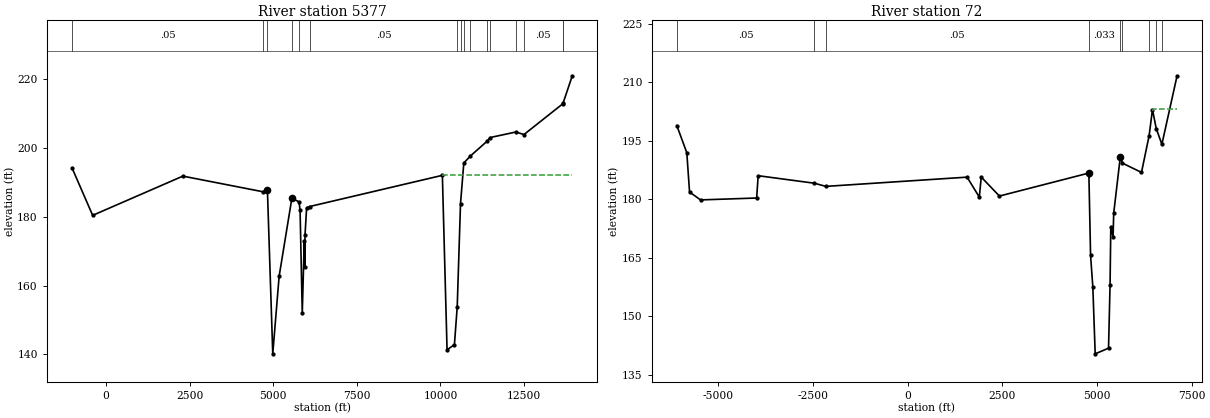
Type RM Length L Ch R = 1 ,5377    ,5305,5305,5305
BEGIN DESCRIPTION:
NAVASOTA RIVER 373
END DESCRIPTION:
XS GIS Cut Line= 3
      3624237.12     10112751.49      3618816.13     10111614.34
       3609416.5     10110969.41
#Sta/Elev= 30
 -1018.3  194.27  -400.1  180.44  2297.3  191.86  4691.6  187.31  4825.4   187.9
  4985.5  140.14  5176.2  162.72  5557.1  185.42  5770.9  184.37  5802.3  182.05
  5867.9  151.98    5928  173.12  5945.5  165.31  5950.5  174.77  5998.2  182.62
  6088.7  183.01 10057.7  192.09   10198  141.29 10418.5  142.84 10501.8  153.82
 10600.4  183.87 10699.1  195.68 10896.3  197.72 11389.5  201.97 11488.1  203.09
 12256.6   204.7 12498.3  203.96 13658.1   212.9 13668.2  213.11 13942.4  221.06
#Mann= 16 ,-1 , 0
 -1018.3     .05       0  4691.6     .16       0  4825.4    .033       0
  5557.1     .05       0  5770.9     .12       0  6088.7     .05       0
 10501.8     .16       0 10600.4     .05       0 10699.1     .08       0
 10896.3     .05       0 11389.5     .08       0 11488.1     .05       0
 12256.6     .16       0 12498.3     .05       0 13658.1     .08       0
 13668.2     .05       0
#XS Ineff= 2 , 0
                         10057.7           192.1
Permanent Ineff=
       F       F
Bank Sta=4825.4,5557.1
XS Rating Curve= 0 ,0
Exp/Cntr=0.3,0.1

Type RM Length L Ch R = 1 ,72      ,0,0,0
BEGIN DESCRIPTION:
NAVASOTA RIVER 372
END DESCRIPTION:
XS GIS Cut Line= 3
      3625346.49     10111831.43      3614687.17     10108748.85
      3612572.77     10108690.61
#Sta/Elev= 30
 -6096.1   198.9 -5831.7  191.93 -5759.3  181.85 -5469.5  179.82 -3987.3  180.31
 -3947.1  186.03 -2461.1   184.1 -2161.3  183.29  1570.1  185.66  1892.8  180.54
  1943.9  185.68  2423.7  180.81  4776.3  186.69  4786.7  186.27  4830.7  165.61
  4890.8  157.44    4953  140.34  5305.2  141.79  5345.2   157.9  5365.2  172.94
  5425.2   170.3  5441.8   176.4  5615.3  190.81  5671.2  189.26  6175.5  186.87
  6376.7  196.27  6465.6     203    6565  198.13  6714.1  194.08  7115.2  211.66
#Mann= 9 ,-1 , 0
 -6096.1     .05       0 -2461.1     .16       0 -2161.3     .05       0
  4776.3    .033       0  5615.3     .05       0  5671.2     .16       0
  6376.7     .05       0    6565     .16       0  6714.1     .05       0
#XS Ineff= 2 , 0
                         6475.74          203.08
Permanent Ineff=
       F       F
Bank Sta=4776.3,5615.3
XS Rating Curve= 0 ,0
Exp/Cntr=0.3,0.1

Chan Stop Cuts=-1
Use User Specified Reach Order=0
Composite Channel Slope=5