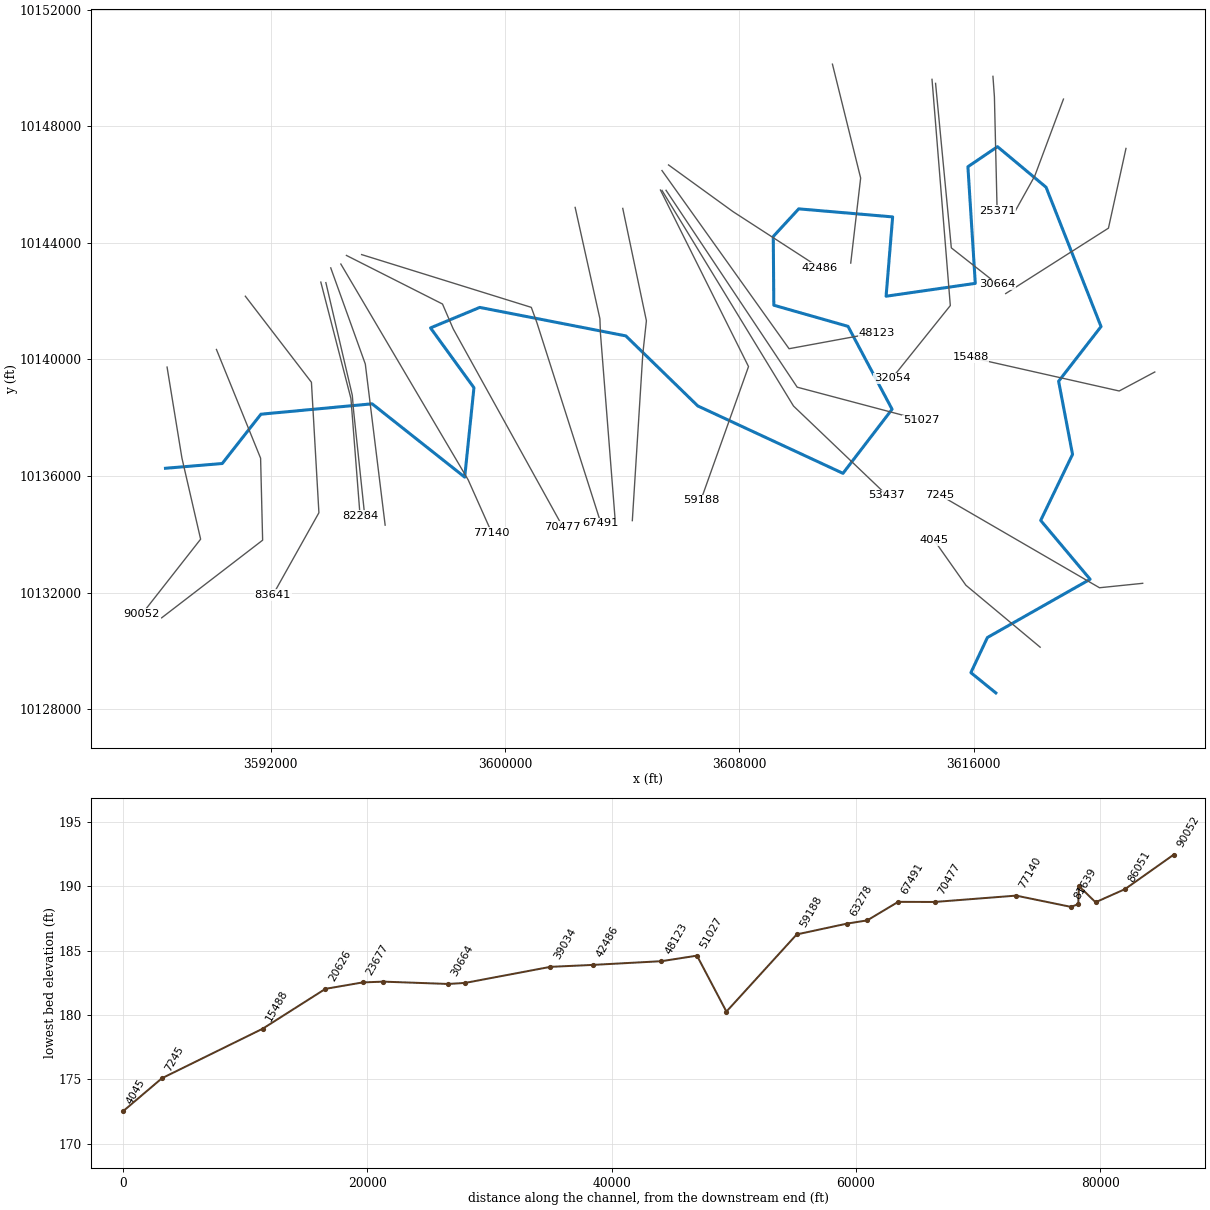
--- BIG CREEK.prj (project) ---

Proj Title=BIG CREEK Base Level Engineering
Current Plan=p01
Default Exp/Contr=0.3,0.1
English Units
Geom File=g01
Flow File=f01
Plan File=p01
Y Axis Title=Elevation
X Axis Title(PF)=Main Channel Distance
X Axis Title(XS)=Station
BEGIN DESCRIPTION:
BIG CREEK
END DESCRIPTION:
DSS Export Rating Curves= 0
DSS Export Rating Curve Sorted= 0
DSS Export Volume Flow Curves= 0
DXF OffsetX= 0
DXF OffsetY= 0
DXF ScaleX= 1
DXF ScaleY= 10

--- BIG CREEK.p01 (plan) ---

Plan Title=Multiple Run
Short Identifier=Multiple
Geom File=g01
Flow File=f01
Subcritical Flow
K Sum by GR= 0
Std Step Tol= 0.01
Critical Tol= 0.01
Num of Std Step Trials= 20
Max Error Tol= 0.3
Flow Tol Ratio= 0.001
Split Flow NTrial= 30
Split Flow Tol= 0.02
Split Flow Ratio= 0.02
Log Output Level= 0
Friction Slope Method= 1
Unsteady Friction Slope Method= 2
Unsteady Bridges Friction Slope Method= 1
Parabolic Critical Depth
Global Vel Dist=  1 , 1 , 1
Global Log Level= 0
CheckData=True
Encroach Param= -1, 0, 0, 0
BEGIN DESCRIPTION:
Multiple Run
END DESCRIPTION:

--- BIG CREEK.f01 (steady flow) ---

Flow Title=Multiple
Number of Profiles=7
Profile Names=10-year,25-year,50-year,1pct_min,100-year,1pct_plu,500-year
River Rch & RM= BIG CREEK,Reach-1,90052
    2844    4024    5026    4570    6180    8358    9374
River Rch & RM= BIG CREEK,Reach-1,86051
    3119    4420    5527    5029    6802    9199   10332
River Rch & RM= BIG CREEK,Reach-1,82284
    2955    4150    5156    4661    6304    8525    9449
River Rch & RM= BIG CREEK,Reach-1,64963
    3912    5539    6924    6293    8511   11509   12892
River Rch & RM= BIG CREEK,Reach-1,63278
    3988    5628    7018    6363    8605   11637   12968
River Rch & RM= BIG CREEK,Reach-1,51027
    3951    5551    6899    6233    8429   11400   12614
River Rch & RM= BIG CREEK,Reach-1,32054
    4003    5606    6953    6267    8475   11462   12623
River Rch & RM= BIG CREEK,Reach-1,25371
    4074    5695    7054    6349    8586   11612   12750
River Rch & RM= BIG CREEK,Reach-1,15488
    4303    6039    7502    6772    9158   12385   13678
Boundary for River Rch & Prof#=BIG CREEK,Reach-1,1
Up Type=0
Dn Type=3
Dn Slope=0.005
Boundary for River Rch & Prof#=BIG CREEK,Reach-1,2
Up Type=0
Dn Type=3
Dn Slope=0.005
Boundary for River Rch & Prof#=BIG CREEK,Reach-1,3
Up Type=0
Dn Type=3
Dn Slope=0.005
Boundary for River Rch & Prof#=BIG CREEK,Reach-1,4
Up Type=0
Dn Type=3
Dn Slope=0.005
Boundary for River Rch & Prof#=BIG CREEK,Reach-1,5
Up Type=0
Dn Type=3
Dn Slope=0.005
Boundary for River Rch & Prof#=BIG CREEK,Reach-1,6
Up Type=0
Dn Type=3
Dn Slope=0.005
Boundary for River Rch & Prof#=BIG CREEK,Reach-1,7
Up Type=0
Dn Type=3
Dn Slope=0.005

--- BIG CREEK.g01 (geometry) ---

Geom Title=Existing Conditions
Program Version=4.10

River Reach=BIG CREEK       ,Reach-1
Reach XY= 30
      3588401.52     10136266.52      3590340.42      10136429.8
      3591661.46     10138121.17      3595459.21     10138477.94
       3598621.8     10135962.71      3598937.43      10139029.5
      3597454.36     10141081.15      3599135.78     10141784.27
      3604124.95     10140807.13       3606583.2     10138404.27
      3611541.31     10136092.82      3613218.69     10138290.83
      3611713.48     10141134.58      3609179.31     10141859.45
      3609161.08     10144217.09      3610030.88       10145165.
      3613238.07     10144888.53      3613014.46      10142167.7
      3616060.98     10142608.67       3615808.9     10146609.37
      3616819.32     10147297.56      3618478.36     10145906.24
      3620355.85     10141127.12      3618907.07     10139252.12
      3619382.11     10136742.57      3618294.22     10134477.82
      3619982.59     10132459.59      3616474.77     10130461.32
      3615910.54     10129256.46      3616762.11     10128561.64

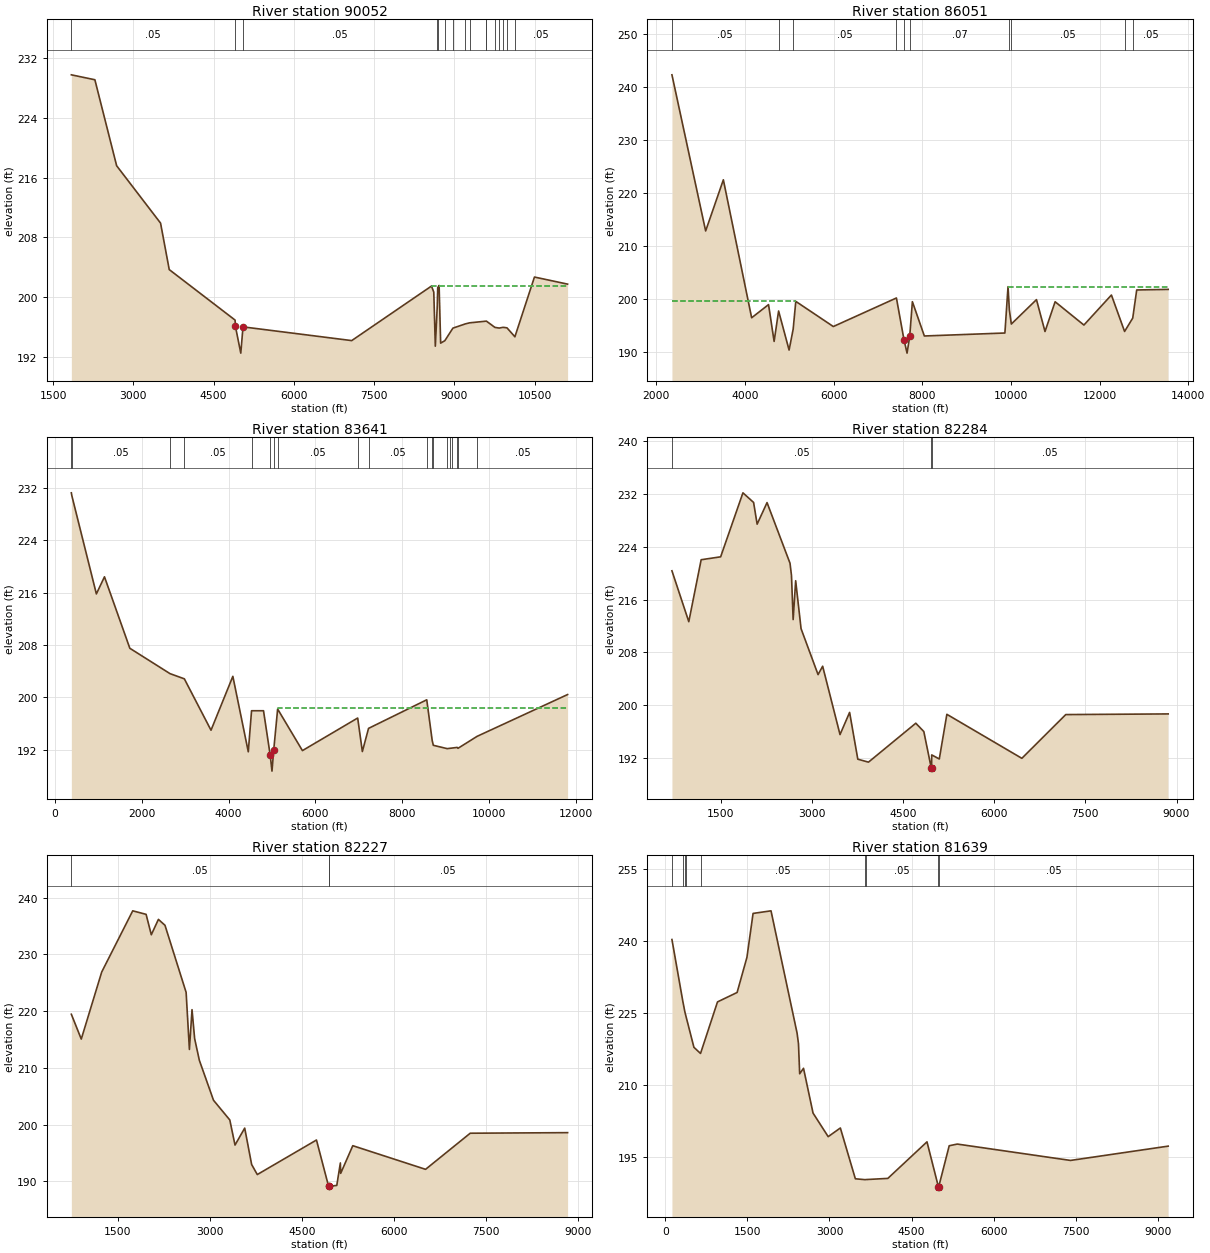
Type RM Length L Ch R = 1 ,90052   ,4001,4001,4001
BEGIN DESCRIPTION:
BIG CREEK 54.0
END DESCRIPTION:
XS GIS Cut Line= 4
      3588456.03     10139737.19      3588963.15     10136618.95
      3589601.86     10133834.46      3587597.46     10131266.52
#Sta/Elev= 30
  1840.8  229.78  2280.3  229.12  2687.3  217.59    3508   209.9  3670.1  203.67
  4900.5   196.9  4906.1  196.08  5007.3  192.47  5048.5  195.99  7080.1  194.15
  8570.8  201.46  8613.7  200.66  8642.6   193.4  8678.1  198.64  8687.4  201.24
  8713.2  201.54  8742.1  193.81  8820.8  194.14  8971.1  195.82  9204.2  196.39
  9282.6  196.53  9583.4  196.75  9597.3  196.76  9756.1  195.92    9836  195.83
  9908.8  195.93  9981.8  195.86 10129.7  194.66   10495  202.67 11114.4  201.72
#Mann= 16 ,-1 , 0
  1840.8     .05       0  4900.5    .035       0  5048.5     .05       0
  8678.1      .1       0  8687.4     .05       0  8820.8     .12       0
  8971.1     .05       0  9204.2      .1       0  9282.6     .05       0
  9583.4      .1       0  9597.3     .05       0  9756.1      .1       0
    9836     .12       0  9908.8     .05       0  9981.8     .12       0
 10129.7     .05       0
#XS Ineff= 2 , 0
                         8577.27          201.51
Permanent Ineff=
       F       F
Bank Sta=4906.1,5048.5
XS Rating Curve= 0 ,0
Exp/Cntr=0.3,0.1

Type RM Length L Ch R = 1 ,86051   ,2410,2410,2410
BEGIN DESCRIPTION:
BIG CREEK 49.0
END DESCRIPTION:
XS GIS Cut Line= 4
      3590142.12      10140341.6      3591650.47     10136612.23
      3591719.91     10133799.73      3588270.43     10131136.42
#Sta/Elev= 30
  2354.2  242.22  3114.5   212.8    3514  222.44  4152.3  196.44  4533.2  198.92
  4659.2  191.99  4760.1  197.72    4997  190.36  5088.7  194.29    5148  199.53
  5994.7  194.79    7418  200.17    7588  192.34  7657.8  189.78    7718  192.94
  7778.1  199.47  8048.1  193.01  9864.9  193.57  9935.6   202.3  9965.6  197.93
   10010  195.26 10577.3  199.86 10769.7  193.85   10998  199.46 11647.4  195.07
 12267.8  200.73 12564.9  193.86 12748.4  196.38 12838.5  201.68 13548.4  201.79
#Mann= 10 ,-1 , 0
  2354.2     .05       0  4760.1     .12       0  5088.7     .05       0
    7418     .07       0    7588     .05       0    7718     .07       0
  9965.6      .1       0   10010     .05       0 12564.9     .12       0
 12748.4     .05       0
#XS Ineff= 2 , 0
            5150  199.54 9936.36          202.25
Permanent Ineff=
       F       F
Bank Sta=7588,7718
XS Rating Curve= 0 ,0
Exp/Cntr=0.3,0.1

Type RM Length L Ch R = 1 ,83641   ,1357,1357,1357
BEGIN DESCRIPTION:
BIG CREEK 46.0
END DESCRIPTION:
XS GIS Cut Line= 4
      3591129.61     10142167.82      3593386.58      10139216.4
      3593642.11     10134741.64      3592067.82     10131917.41
#Sta/Elev= 30
   378.3  231.21   389.7  230.77   954.6  215.79  1141.4   218.4  1725.4   207.5
  2651.1  203.63    2981  202.84  3595.4     195  4098.4  203.22    4454  191.71
  4529.2  197.97  4804.7  197.97  4958.7   191.2  4999.8  188.76  5040.1  191.99
  5130.2  198.23  5701.2  191.89  6973.9  196.86  7081.6  191.75  7224.1  195.28
  8564.7  199.64  8690.4  193.43  8716.6   192.7  9035.6  192.19  9095.2  192.24
  9150.7  192.28  9265.7  192.38  9284.5  192.24    9726  194.07 11809.2  200.44
#Mann= 19 ,-1 , 0
   378.3     .16       0   389.7     .05       0  2651.1      .1       0
    2981     .05       0  4529.2     .11       0  4958.7     .05       0
  5040.1      .1       0  5130.2     .05       0  6973.9      .1       0
  7224.1     .05       0  8564.7     .16       0  8690.4     .05       0
  8716.6     .07       0  9035.6     .12       0  9095.2     .07       0
  9150.7     .12       0  9265.7      .1       0  9284.5     .12       0
    9726     .05       0
#XS Ineff= 2 , 0
                         5134.09           198.4
Permanent Ineff=
       F       F
Bank Sta=4958.7,5040.1
XS Rating Curve= 0 ,0
Exp/Cntr=0.3,0.1

Type RM Length L Ch R = 1 ,82284   ,57,57,57
BEGIN DESCRIPTION:
Mapping XS 283d72ef
END DESCRIPTION:
XS GIS Cut Line= 3
      3593707.35     10142652.55      3594735.99     10138656.72
      3595048.49     10134631.74
#Sta/Elev= 30
   699.4  220.38   976.6  212.67  1180.1  222.06  1500.6   222.5  1867.2   232.2
  2042.7  230.74  2100.9  227.45  2263.8  230.72  2641.6  221.53  2665.7  219.68
  2693.3  212.99  2734.6  218.88  2823.4  211.61  3103.1  204.65  3178.6  205.92
  3464.4  195.56    3622  198.92  3756.8  191.83  3932.4  191.38  4710.8  197.28
  4842.8  196.02  4964.6  190.52  4967.3  190.02  4970.6  190.52  4972.6  192.48
  5097.3  191.86  5221.8  198.63  6455.5  191.96  7177.6  198.59  8862.6  198.69
#Mann= 3 ,-1 , 0
   699.4     .05       0  4964.6     .03       0  4970.6     .05       0
Bank Sta=4964.6,4970.6
XS Rating Curve= 0 ,0
Exp/Cntr=0.3,0.1

Type RM Length L Ch R = 1 ,82227   ,588,588,588
BEGIN DESCRIPTION:
Mapping XS 10e8fd9d
END DESCRIPTION:
XS GIS Cut Line= 4
      3593880.18     10142633.69      3594782.37     10138769.46
      3594824.04     10138265.99      3595203.96     10134669.24
#Sta/Elev= 30
     740  219.46   901.8  215.08    1235  226.91  1740.7   237.7  1958.5  237.08
  2043.6  233.48  2159.2  236.19  2266.5  235.15    2611  223.32  2664.6  213.25
  2707.2  220.27  2749.7  215.17  2826.7  211.34  3057.7  204.29  3323.1  200.82
  3408.2  196.39  3566.1  199.38    3679  192.97  3771.4  191.19  4736.1  197.28
  4933.7  189.12  4936.5  188.62  4939.7  189.12  5067.2  189.27  5125.8  193.24
  5130.8   191.4  5328.3  196.28  6514.9  192.11  7242.8  198.48  8830.1  198.58
#Mann= 3 ,-1 , 0
     740     .05       0  4933.7     .03       0  4939.7     .05       0
Bank Sta=4933.7,4939.7
XS Rating Curve= 0 ,0
Exp/Cntr=0.3,0.1

Type RM Length L Ch R = 1 ,81639   ,4499,4499,4499
BEGIN DESCRIPTION:
BIG CREEK 43.0
END DESCRIPTION:
XS GIS Cut Line= 3
       3594046.3       10143140.      3595226.86      10139841.4
      3595904.41     10134315.38
#Sta/Elev= 30
   120.9  240.25   320.8  227.35     357  225.23   372.5  224.52   522.8  217.86
   643.5  216.58   953.6  227.29  1312.2  229.25  1491.5  236.54    1604  245.67
  1931.8  246.21  2408.2  220.82  2433.7  218.62  2455.8  212.36    2526   213.5
    2700   204.2  2976.9   199.3  3199.3   201.1  3473.4  190.55  3653.6  190.36
  3660.9  190.38  4067.4  190.63  4782.8  198.22  4991.3   188.9  4994.1   188.4
  4997.3   188.9  5189.2  197.41  5336.9  197.76  7406.8  194.36  9191.8  197.33
#Mann= 9 ,-1 , 0
   120.9     .05       0   320.8     .16       0     357     .05       0
   372.5     .16       0   643.5     .05       0  3653.6     .12       0
  3660.9     .05       0  4991.3     .03       0  4997.3     .05       0
Bank Sta=4991.3,4997.3
XS Rating Curve= 0 ,0
Exp/Cntr=0.3,0.1

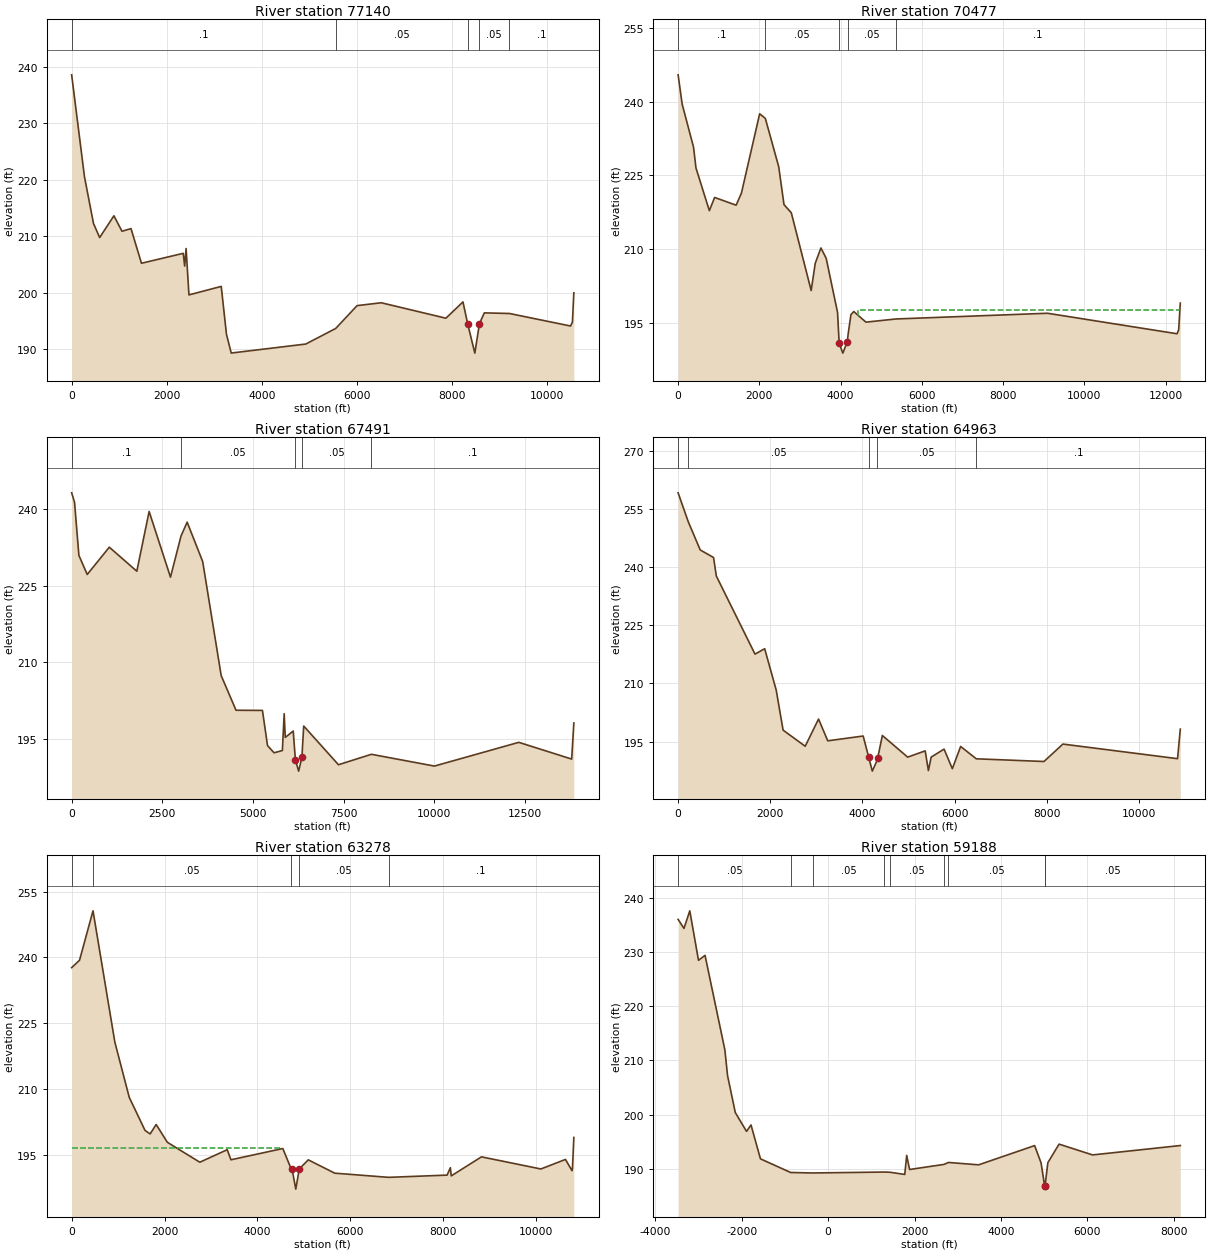
Type RM Length L Ch R = 1 ,77140   ,6663,6663,6663
BEGIN DESCRIPTION:
Mapping XS 28f6373d
END DESCRIPTION:
XS GIS Cut Line= 3
     3594391.272    10143271.913     3598742.225    10135864.754
     3599544.348    10134059.991
#Sta/Elev= 30
       0238.6087 269.808220.5458459.6729212.2535589.5804209.7679 889.367213.6222
1059.246210.87941249.111211.34891468.954205.20732348.329206.96622378.307204.7125
2408.286207.82062468.243199.5961 3147.76201.10623257.681192.6142 3357.61189.2913
4926.494190.88835556.045193.64826005.726197.69566515.363198.20527874.396195.4677
 8234.14 198.3538334.068194.43398483.962 189.2778563.905193.60148573.897194.3887
 8683.57196.41269211.726196.303510497.24 194.084 10537.1194.754710566.99199.9687
#Mann= 5 ,-1 , 0
       0      .1       05556.045     .05       08334.068    .035       0
8563.905     .05       09211.726      .1       0
Bank Sta=8334.068,8573.897
XS Rating Curve= 0 ,0
Exp/Cntr=0.3,0.1

Type RM Length L Ch R = 1 ,70477   ,2986,2986,2986
BEGIN DESCRIPTION:
Mapping XS 36ce747f
END DESCRIPTION:
XS GIS Cut Line= 4
     3594582.245    10143567.052     3597863.495    10141900.385
     3598228.078    10141049.691     3601969.214    10134262.322
#Sta/Elev= 30
       0 245.52499.86612239.5443379.4912230.7796439.4109226.5388768.9691217.8265
 898.795 220.5221428.085218.94661557.911 221.3852007.309237.58042147.122236.6397
 2476.68226.78332606.506219.06482786.265217.39923275.609201.54993375.475207.0909
3515.287210.22263645.113208.11493924.729197.08963964.675190.80934054.551188.7835
4164.399191.09534184.372192.58854254.275196.63414324.179197.25944623.778195.1019
5363.643195.7473 9092.96196.912112282.38192.732412322.37193.536112362.36198.9839
#Mann= 5 ,-1 , 0
       0      .1       02147.122     .05       03964.675    .035       0
4184.372     .05       05363.643      .1       0
#XS Ineff= 2 , 0
                         4438.64          197.52
Permanent Ineff=
       F       F
Bank Sta=3964.675,4164.399
XS Rating Curve= 0 ,0
Exp/Cntr=0.3,0.1

Type RM Length L Ch R = 1 ,67491   ,2528,2528,2528
BEGIN DESCRIPTION:
Mapping XS 0c26bd97
END DESCRIPTION:
XS GIS Cut Line= 4
     3595101.173    10143596.094     3600896.149    10141785.854
     3601084.458    10141270.534     3603274.615    10134380.422
#Sta/Elev= 30
       0243.125679.90589241.2758199.7647230.9157429.4942227.18631038.777232.5105
1797.883227.82112137.483239.48532726.789226.66493016.448234.66873186.248237.4025
3615.742229.69214125.142207.4501 4534.66200.67515263.801200.64515403.636193.7832
5583.424192.37365813.154 192.8095863.095199.9978 5893.06195.3693 6112.75196.6197
6172.604191.00556262.384188.79226352.165191.47376402.042197.59847360.768190.0425
8269.861192.077810008.13189.7791 12335.8194.412613794.35191.146213854.29198.1937
#Mann= 5 ,-1 , 0
       0      .1       03016.448     .05       06172.604    .035       0
6352.165     .05       08269.861      .1       0
Bank Sta=6172.604,6352.165
XS Rating Curve= 0 ,0
Exp/Cntr=0.3,0.1

Type RM Length L Ch R = 1 ,64963   ,1685,1685,1685
BEGIN DESCRIPTION:
Mapping XS 688fc5c5
END DESCRIPTION:
XS GIS Cut Line= 4
     3602394.013    10145213.892     3603239.716    10141394.882
     3603256.255    10140920.009     3603766.327    10134420.532
#Sta/Elev= 30
       0259.2668219.8793251.8058479.7368244.5096769.5777 242.545829.5448237.7679
1669.084 217.5891878.969218.98232128.832208.3275 2278.75197.94922758.486193.7848
3048.327200.81033248.218195.1842 4016.81196.4231 4135.67191.0225 4214.91 187.353
4323.864190.2349 4333.77190.81414433.275196.56094983.069190.96845362.926192.5883
  5432.9187.50335492.877190.97725772.772193.04055952.704187.98236132.637193.7282
6472.509190.53597941.957 189.8418351.803194.344210840.87 190.57110900.84198.2022
#Mann= 5 ,-1 , 0
       0      .1       0219.8793     .05       0 4135.67    .035       0
4323.864     .05       06472.509      .1       0
#XS Ineff= 2 , 0
         3047.73  197.52
Permanent Ineff=
       F       F
Bank Sta=4135.67,4333.77
XS Rating Curve= 0 ,0
Exp/Cntr=0.3,0.1

Type RM Length L Ch R = 1 ,63278   ,4090,4090,4090
BEGIN DESCRIPTION:
BIG CREEK 34.0
END DESCRIPTION:
XS GIS Cut Line= 4
     3604020.258    10145179.942      3604827.55    10141325.775
     3604704.787    10140188.426     3604346.767    10134470.156
#Sta/Elev= 30
       0237.6737 169.994239.3706459.9839  250.65929.9674220.67911239.957208.0602
1579.945200.50951689.941199.70071819.936201.85482059.928197.79822759.903193.2399
3349.883196.1015 3429.88193.79674547.496 196.3654726.798191.71924746.721191.6514
 4826.41187.09594886.178190.7565  4906.1191.75735095.399  193.785665.219190.7406
6824.852189.78668084.454190.29558154.432191.98268174.425190.1222 8824.22194.4661
10103.82191.697110633.65193.8779 10773.6191.3135 10783.6191.820710813.59198.8945
#Mann= 5 ,-1 , 0
       0      .1       0459.9839     .05       04726.798    .035       0
4886.178     .05       06824.852      .1       0
#XS Ineff= 2 , 0
         4534.09  196.42
Permanent Ineff=
       F       F
Bank Sta=4746.721,4906.1
XS Rating Curve= 0 ,0
Exp/Cntr=0.3,0.1

Type RM Length L Ch R = 1 ,59188   ,5751,5751,5751
BEGIN DESCRIPTION:
Mapping XS d5d5364d
END DESCRIPTION:
XS GIS Cut Line= 3
      3605307.54      10145810.1      3608315.36      10139755.4
      3606687.75     10135172.06
#Sta/Elev= 30
 -3473.1  236.02 -3337.2  234.36 -3202.8   237.6 -3001.2  228.47 -2849.9  229.39
 -2390.7  211.94   -2329  207.23 -2149.8  200.39 -1889.3  196.91 -1785.7   198.1
 -1567.3  191.85  -868.6  189.33  -358.5  189.24  1293.7  189.41  1424.6  189.38
  1773.2  188.97  1817.8  192.48  1884.8  189.88  2681.4  190.82  2785.1  191.18
  3482.5  190.74  4779.5  194.29  4928.5   191.1  5012.7  186.76  5015.5  186.26
  5018.7  186.76  5084.9  191.13  5344.6  194.56  6120.4  192.57  8151.3   194.3
#Mann= 9 ,-1 , 0
 -3473.1     .05       0  -868.6     .12       0  -358.5     .05       0
  1293.7      .1       0  1424.6     .05       0  2681.4      .1       0
  2785.1     .05       0  5012.7     .03       0  5018.7     .05       0
Bank Sta=5012.7,5018.7
XS Rating Curve= 0 ,0
Exp/Cntr=0.3,0.1

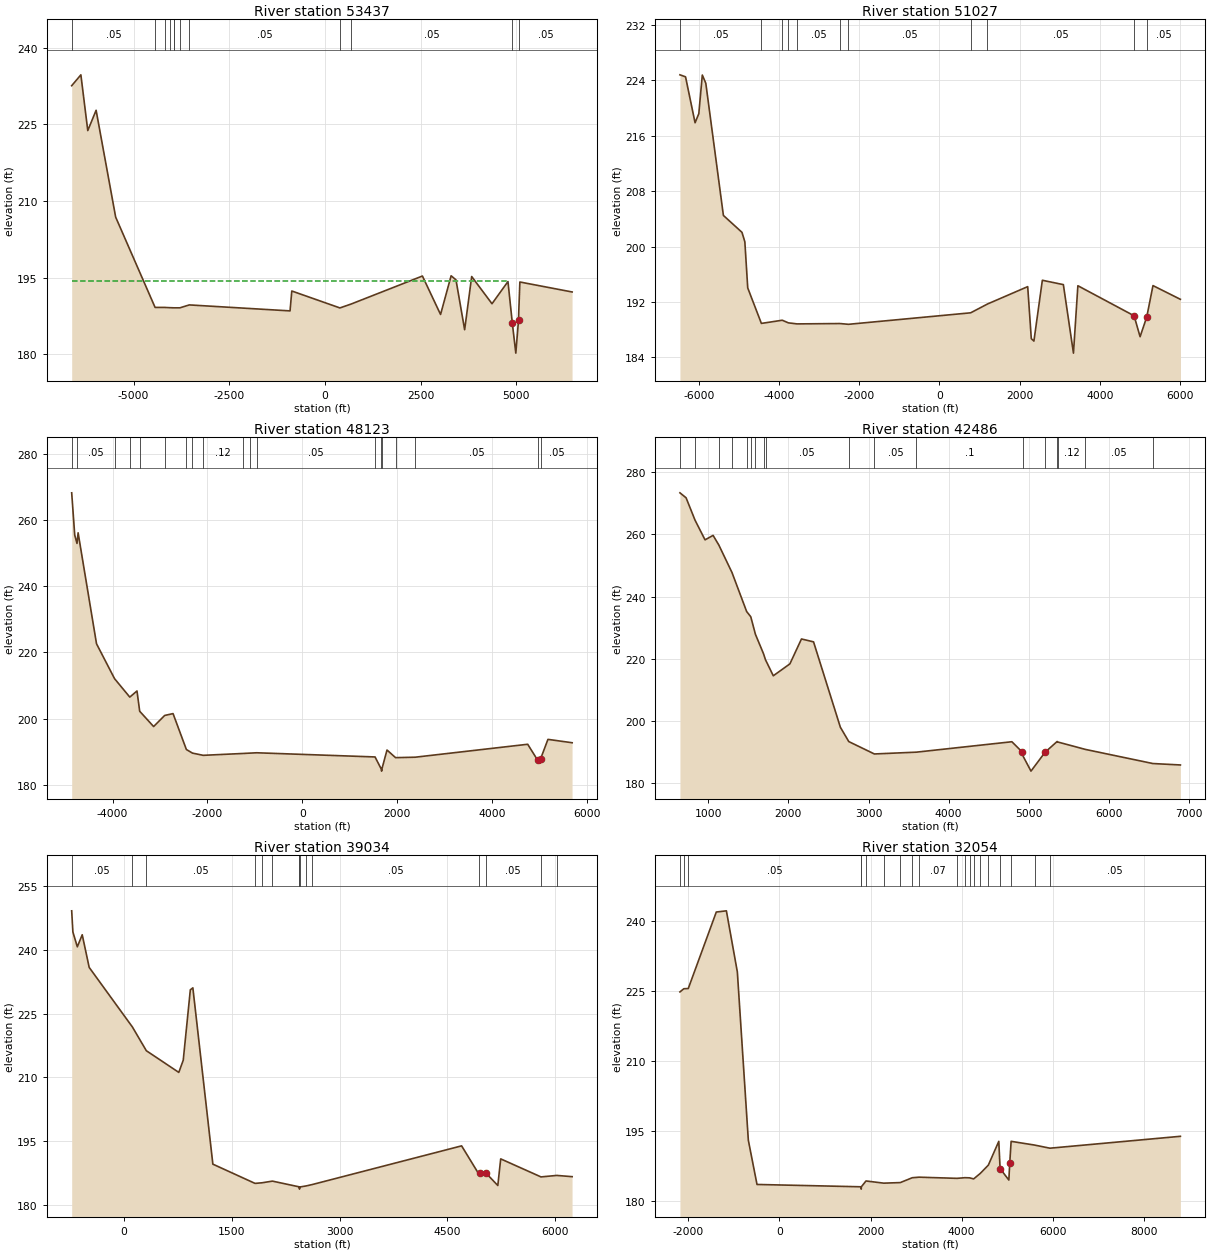
Type RM Length L Ch R = 1 ,53437   ,2410,2410,2410
BEGIN DESCRIPTION:
Mapping XS 3e72f473
END DESCRIPTION:
XS GIS Cut Line= 3
      3605359.63     10145797.06      3609851.81     10138401.23
      3613041.93     10135341.32
#Sta/Elev= 30
 -6615.2  232.56 -6375.2  234.69 -6194.9  223.79 -5977.1  227.76 -5466.2  206.86
 -4436.5   189.2   -4190   189.2 -4056.7  189.15 -3949.2  189.12 -3945.2  189.12
 -3787.2  189.12 -3542.8  189.69  -910.9  188.52  -865.2  192.41   391.7   189.1
   685.2  189.86  2547.2  195.34  3021.1  187.82  3296.9  195.39  3424.1  194.59
  3650.4  184.84  3834.4  195.24  4364.9  189.92    4782  194.26  4895.2  186.17
    4987  180.26    5058  186.72    5065  188.56  5093.3  194.17  6458.4  192.22
#Mann= 12 ,-1 , 0
 -6615.2     .05       0 -4436.5     .12       0   -4190     .05       0
 -4056.7      .1       0 -3949.2     .05       0 -3945.2      .1       0
 -3787.2     .12       0 -3542.8     .05       0   391.7      .1       0
   685.2     .05       0  4895.2    .035       0    5065     .05       0
#XS Ineff= 2 , 0
         4786.04  194.28
Permanent Ineff=
       F       F
Bank Sta=4895.2,5058
XS Rating Curve= 0 ,0
Exp/Cntr=0.3,0.1

Type RM Length L Ch R = 1 ,51027   ,2904,2904,2904
BEGIN DESCRIPTION:
Mapping XS 2b453a86
END DESCRIPTION:
XS GIS Cut Line= 3
      3605498.53     10145801.39      3609977.68     10139047.94
      3614213.82     10137919.46
#Sta/Elev= 30
 -6475.9  224.79   -6336   224.5 -6098.4  217.87 -6005.1  219.18 -5917.9  224.76
 -5830.7  223.58 -5391.6  204.49 -4928.4  202.05 -4856.3  200.69 -4784.3  194.03
 -4443.6   188.9 -3922.2  189.36 -3770.3  188.98 -3553.9  188.83 -2483.5  188.88
 -2271.9  188.77   778.3  190.43  1197.9   191.7  2201.7  194.21  2291.5   186.7
  2356.9  186.35  2567.2  195.13  3091.7   194.5  3343.5  184.61  3453.7  194.34
  4856.7     190  5006.2  186.98  5172.5  189.83  5327.8  194.36  6011.8  192.38
#Mann= 11 ,-1 , 0
 -6475.9     .05       0 -4443.6     .12       0 -3922.2      .1       0
 -3770.3     .12       0 -3553.9     .05       0 -2483.5      .1       0
 -2271.9     .05       0   778.3      .1       0  1197.9     .05       0
  4856.7    .035       0  5172.5     .05       0
Bank Sta=4856.7,5172.5
XS Rating Curve= 0 ,0
Exp/Cntr=0.3,0.1

Type RM Length L Ch R = 1 ,48123   ,5637,5637,5637
BEGIN DESCRIPTION:
Mapping XS 66710ba7
END DESCRIPTION:
XS GIS Cut Line= 3
      3605359.64     10146478.47       3609699.9     10140367.38
       3612703.4     10140922.94
#Sta/Elev= 30
 -4862.4  268.21 -4798.3  255.46 -4750.6  252.93 -4726.9  256.14 -4338.9  222.63
 -3958.3  212.09 -3637.5  206.53 -3485.8  208.38 -3428.7  202.26 -3135.3  197.64
   -2902  200.99 -2725.6  201.55 -2444.7  190.71 -2316.1  189.62 -2090.9  188.95
   -1252  189.51 -1112.4  189.61  -962.7  189.72    1533  188.46  1668.2  184.68
    1671  184.18  1674.2  184.68  1784.9  190.55  1965.1  188.25  2376.2  188.38
  4750.7  192.29  4964.2   187.4  5025.3  187.99  5177.8  193.77  5687.6  192.75
#Mann= 19 ,-1 , 0
 -4862.4      .1       0 -4750.6     .05       0 -3958.3     .16       0
 -3637.5     .16       0 -3428.7     .05       0   -2902     .05       0
 -2444.7      .1       0 -2316.1     .12       0 -2090.9     .12       0
   -1252     .05       0 -1112.4      .1       0  -962.7     .05       0
    1533     .12       0  1668.2    .035       0  1674.2     .12       0
  1965.1     .05       0  2376.2     .05       0  4964.2    .035       0
  5025.3     .05       0
Bank Sta=4964.2,5025.3
XS Rating Curve= 0 ,0
Exp/Cntr=0.3,0.1

Type RM Length L Ch R = 1 ,42486   ,3452,3452,3452
BEGIN DESCRIPTION:
BIG CREEK 23.0
END DESCRIPTION:
XS GIS Cut Line= 3
      3605583.77     10146670.81      3607783.77     10145070.81
      3610738.06     10143149.31
#Sta/Elev= 30
   646.8  273.39   723.5  271.79   835.1   264.6     960  258.27  1060.4   259.7
  1131.3  256.64  1295.8  247.79  1479.1  235.22  1530.8  233.52  1588.8  227.88
  1689.4  221.66  1714.4   219.7  1811.6  214.55  2018.7  218.38  2163.2  226.39
  2313.9  225.46  2648.6     198  2753.7  193.39  3072.8  189.41  3597.3  189.99
  4788.8  193.34  4918.6  190.01  4927.8  188.74  5027.1  183.89  5202.2  189.94
  5353.4  193.42  5359.4  193.27  5706.6  190.87  6548.2  186.33  6891.3  185.87
#Mann= 18 ,-1 , 0
   646.8     .05       0   835.1     .16       0  1131.3     .05       0
  1295.8     .16       0  1479.1      .1       0  1530.8     .16       0
  1588.8      .1       0  1689.4     .16       0  1714.4     .05       0
  2753.7      .1       0  3072.8     .05       0  3597.3      .1       0
  4927.8     .05       0  5202.2     .12       0  5353.4     .07       0
  5359.4     .12       0  5706.6     .05       0  6548.2      .1       0
Bank Sta=4918.6,5202.2
XS Rating Curve= 0 ,0
Exp/Cntr=0.3,0.1

Type RM Length L Ch R = 1 ,39034   ,6980,6980,6980
BEGIN DESCRIPTION:
BIG CREEK 20.0
END DESCRIPTION:
XS GIS Cut Line= 3
      3611181.72     10150127.85      3612145.26     10146221.61
      3611806.71     10143304.91
#Sta/Elev= 30
    -725  249.16  -708.3  244.18  -646.5   240.7  -578.4  243.53  -481.7  235.86
   119.5  221.85   313.4  216.27   764.6  211.18   826.3  214.04   925.1   230.6
   960.2  231.05  1238.3  189.61  1824.6  185.09  1921.5  185.23  2066.9  185.62
  2434.6  184.29  2440.4  184.24  2443.2  183.74  2446.4  184.24  2534.9  184.49
  2623.7  184.83  4697.6  193.91  4939.2  187.23  4949.3  187.49  5029.8  187.63
    5201  184.59  5241.2  190.85  5801.8  186.61  6020.9  186.96  6234.6  186.67
#Mann= 15 ,-1 , 0
    -725     .05       0   119.5      .1       0   313.4     .05       0
  1824.6     .12       0  1921.5     .16       0  2066.9     .05       0
  2434.6     .12       0  2440.4    .035       0  2446.4     .12       0
  2534.9      .1       0  2623.7     .05       0  4939.2    .035       0
  5029.8     .05       0  5801.8      .1       0  6020.9     .05       0
Bank Sta=4949.3,5029.8
XS Rating Curve= 0 ,0
Exp/Cntr=0.3,0.1

Type RM Length L Ch R = 1 ,32054   ,1390,1390,1390
BEGIN DESCRIPTION:
Mapping XS 6a998c99
END DESCRIPTION:
XS GIS Cut Line= 3
      3614582.72      10149607.8      3615207.72     10141847.42
      3613211.19     10139347.42
#Sta/Elev= 30
 -2184.2  224.75 -2099.5  225.43 -2001.2  225.48 -1386.3  241.87 -1164.8  242.13
    -924  229.03  -683.2  192.98  -492.6  183.49  1791.8  182.99  1794.5  182.49
  1797.8  182.99  1899.3  184.24  2289.2  183.77    2652  183.89  2915.2  184.93
  3063.4  185.05  3897.4   184.8  4070.5  184.94  4172.5  184.91  4262.8  184.68
  4410.7  185.88  4585.6  187.64  4814.5  192.73    4843  186.89  5035.3  184.44
  5055.3  188.12  5085.4  192.73  5601.3  191.93  5936.9  191.26  8800.7  193.81
#Mann= 20 ,-1 , 0
 -2184.2     .05       0 -2099.5     .16       0 -2001.2     .05       0
  1791.8     .07       0  1797.8     .05       0  1899.3     .16       0
  2289.2     .07       0    2652     .16       0  2915.2     .07       0
  3063.4     .07       0  3897.4     .12       0  4070.5      .1       0
  4172.5     .07       0  4262.8     .05       0  4410.7     .07       0
  4585.6      .1       0    4843     .05       0  5085.4     .16       0
  5601.3     .12       0  5936.9     .05       0
Bank Sta=4843,5055.3
XS Rating Curve= 0 ,0
Exp/Cntr=0.3,0.1

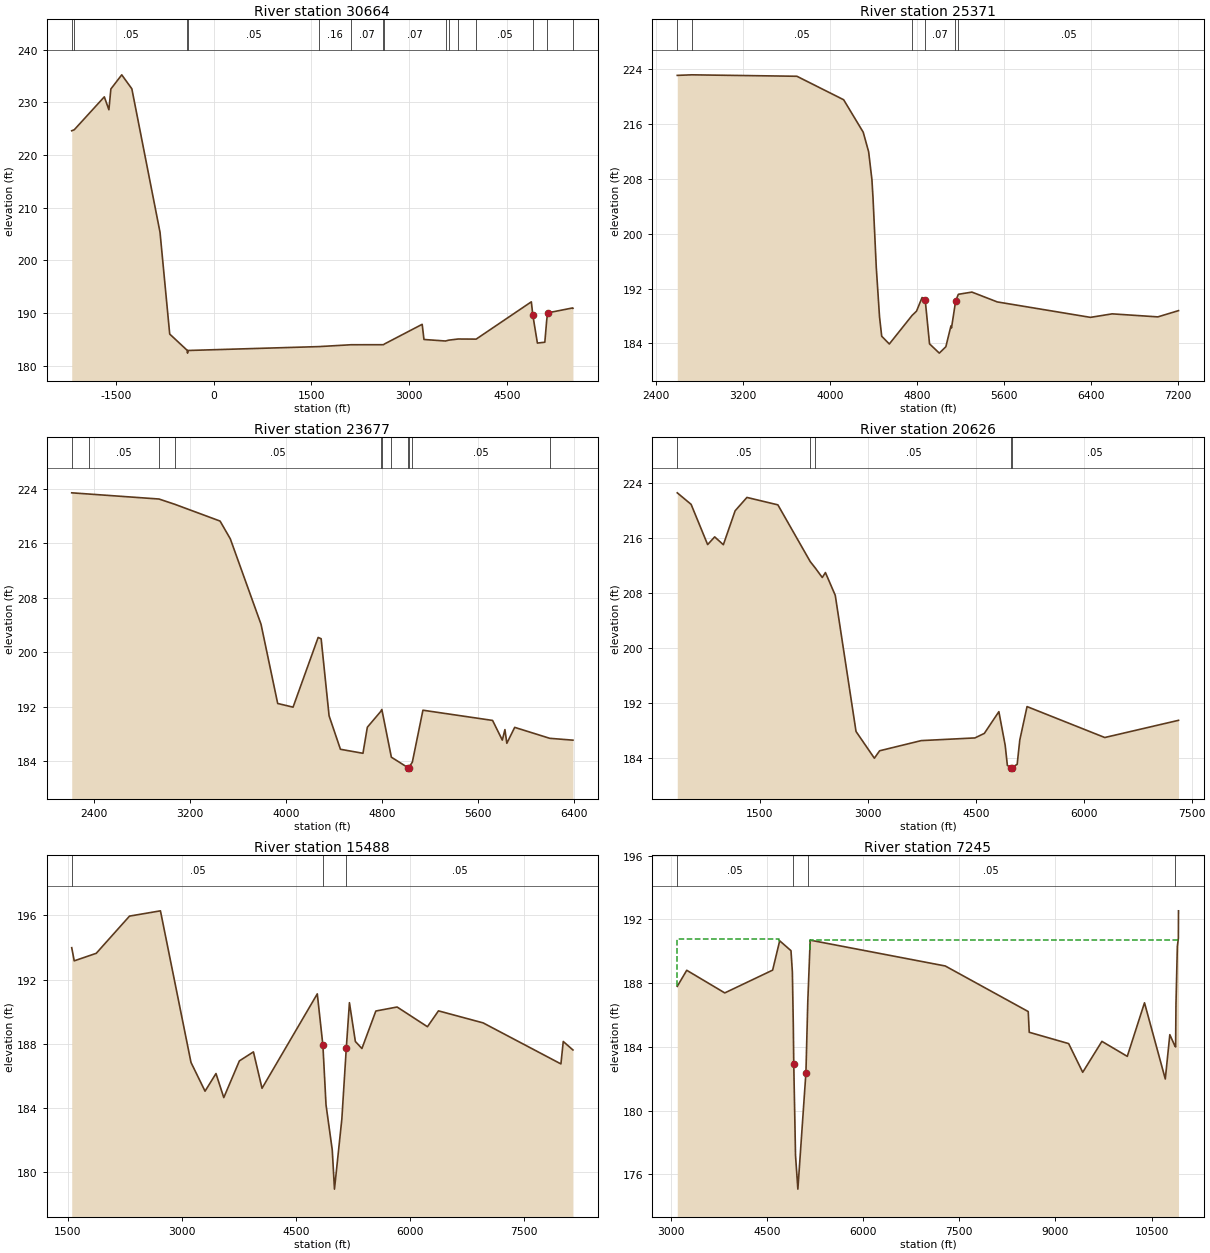
Type RM Length L Ch R = 1 ,30664   ,5293,5293,5293
BEGIN DESCRIPTION:
Mapping XS 157ab9e6
END DESCRIPTION:
XS GIS Cut Line= 3
      3614704.25     10149468.91      3615242.44     10143826.58
       3616822.3     10142576.58
#Sta/Elev= 30
 -2174.7  224.62 -2135.3  224.82 -1675.2  231.06 -1604.9  228.61 -1574.7  232.55
 -1408.2  235.24 -1253.3  232.59  -821.3  205.34  -672.9  186.03  -402.4  182.91
  -399.7  182.41  -396.4  182.91  1616.7  183.65  2105.8     184  2603.5  184.01
  2617.7  184.14  3196.8  187.88  3224.2     185  3554.8  184.71  3602.5  184.87
  3747.7  185.09  4024.4  185.07    4870  192.15  4892.2  189.65  4962.7  184.32
  5076.5  184.48  5105.3  188.64  5119.8  190.05  5504.4  190.99  5507.8  190.92
#Mann= 15 ,-1 , 0
 -2174.7      .1       0 -2135.3     .05       0  -402.4     .07       0
  -396.4     .05       0  1616.7     .16       0  2105.8     .07       0
  2603.5     .16       0  2617.7     .07       0  3554.8     .16       0
  3602.5     .07       0  3747.7     .16       0  4024.4     .05       0
  4892.2    .035       0  5105.3      .1       0  5504.4     .05       0
Bank Sta=4892.2,5119.8
XS Rating Curve= 0 ,0
Exp/Cntr=0.3,0.1

Type RM Length L Ch R = 1 ,25371   ,1694,1694,1694
BEGIN DESCRIPTION:
BIG CREEK 17.0
END DESCRIPTION:
XS GIS Cut Line= 3
      3616663.98     10149710.39      3616713.98     10149010.39
      3616806.72     10145101.78
#Sta/Elev= 30
  2593.2  223.05  2726.6  223.13  3693.8  222.92    4124   219.5    4304  214.77
    4354  211.91    4384  207.87    4394  205.25  4424.1   195.1  4454.1  187.86
  4474.1  185.05  4544.1  183.92  4754.1  188.09  4794.2   188.7  4845.6  190.69
  4874.2  190.35  4914.2  183.94    5004  182.59  5064.2  183.52  5111.2  186.56
  5116.2  186.26  5144.3  189.14  5154.3  190.19  5179.2  191.16  5304.3  191.48
    5537  190.05  6394.6   187.8  6594.7  188.31  7014.8  187.87  7204.7  188.78
#Mann= 6 ,-1 , 0
  2593.2      .1       0  2726.6     .05       0  4754.1     .12       0
  4874.2     .07       0  5144.3     .12       0  5179.2     .05       0
Bank Sta=4874.2,5154.3
XS Rating Curve= 0 ,0
Exp/Cntr=0.3,0.1

Type RM Length L Ch R = 1 ,23677   ,3051,3051,3051
BEGIN DESCRIPTION:
BIG CREEK 16.0
END DESCRIPTION:
XS GIS Cut Line= 3
      3619072.34     10148929.94      3618092.11     10146291.64
      3617431.73     10145101.83
#Sta/Elev= 30
  2216.6  223.42  2361.1  223.24  2943.7  222.51  3075.9  221.73  3452.3  219.27
  3537.6  216.66  3793.6   204.1  3932.3  192.47  4060.3  191.93  4269.3  202.17
  4294.3  201.98  4360.4  190.66    4455  185.74  4642.6  185.15  4679.1  188.98
  4789.3  191.27  4799.8  191.59  4879.1  184.58  5018.3  183.03    5021  182.53
  5024.3  183.03  5054.1  183.86  5142.1  191.48  5722.2  189.98  5803.5  187.09
  5825.2  188.63  5841.2  186.62  5906.5  188.96  6198.9  187.35  6391.9  187.08
#Mann= 11 ,-1 , 0
  2216.6      .1       0  2361.1     .05       0  2943.7      .1       0
  3075.9     .05       0  4789.3     .07       0  4799.8     .16       0
  4879.1     .07       0  5018.3     .07       0  5024.3     .07       0
  5054.1     .05       0  6198.9      .1       0
Bank Sta=5018.3,5024.3
XS Rating Curve= 0 ,0
Exp/Cntr=0.3,0.1

Type RM Length L Ch R = 1 ,20626   ,5138,5138,5138
BEGIN DESCRIPTION:
BIG CREEK 15.0
END DESCRIPTION:
XS GIS Cut Line= 3
      3621207.76     10147237.24       3620608.8     10144502.86
      3617098.97     10142258.64
#Sta/Elev= 30
   352.3  222.52   544.9  220.84   774.3  214.99   872.2  216.11   992.7  214.97
  1156.5  219.91  1320.3  221.85  1750.3  220.77  2200.3  212.51  2271.2  211.57
  2367.3   210.2  2411.1  210.92  2547.8  207.61  2836.4   187.8  3091.3  183.91
  3164.2  184.99  3742.8  186.47  4488.8  186.86  4619.4  187.52  4821.2  190.68
  4909.1  185.79  4939.5  182.86  4994.1  182.53  4996.8  182.03  5000.1  182.53
  5075.7  183.02  5112.1  186.56  5212.9  191.42    6293  186.92  7317.5  189.42
#Mann= 5 ,-1 , 0
   352.3     .05       0  2200.3      .1       0  2271.2     .05       0
  4994.1    .033       0  5000.1     .05       0
Bank Sta=4994.1,5000.1
XS Rating Curve= 0 ,0
Exp/Cntr=0.3,0.1

Type RM Length L Ch R = 1 ,15488   ,8243,8243,8243
BEGIN DESCRIPTION:
Mapping XS 64ba3f50
END DESCRIPTION:
XS GIS Cut Line= 3
      3622191.22     10139568.77      3620975.95     10138917.73
      3615897.84      10140067.9
#Sta/Elev= 30
  1552.6  193.99  1585.6  193.17  1874.8  193.64  2311.7  195.96  2718.1  196.29
  3119.8  186.83  3304.3  185.04  3447.9  186.14  3550.4  184.64  3755.5  186.93
    3940  187.49  4052.8  185.22    4779  191.11  4852.6   187.9  4893.6  184.19
  4975.6  181.37  5004.7  178.93  5101.5   183.3  5160.2  187.74  5201.2  190.56
  5279.2  188.14  5365.2   187.7  5548.3  190.04  5827.7  190.29  6226.2  189.06
    6371  190.05  6957.5   189.3  7979.8  186.74  8010.6  188.14    8138  187.61
#Mann= 3 , 0 , 0
  1552.6     .05       0  4852.6    .035       0  5160.2     .05       0
Bank Sta=4852.6,5160.2
XS Rating Curve= 0 ,0
Exp/Cntr=0.3,0.1

Type RM Length L Ch R = 1 ,7245    ,3200,3200,3200
BEGIN DESCRIPTION:
Mapping XS 6fb3f8b2
END DESCRIPTION:
XS GIS Cut Line= 3
      3621778.89     10132320.51       3620303.2      10132168.6
      3614834.21     10135357.13
#Sta/Elev= 30
  3104.2   187.8  3251.8  188.81  3844.9  187.39  4591.2  188.82  4700.9  190.66
  4877.1  190.04  4898.6  188.71  4913.1   185.4  4920.1  182.95  4947.8  177.19
  4984.4  175.08  5109.9  182.38  5139.3  186.88  5176.5   190.7  7282.1  189.08
  8575.6  186.22  8591.3  184.92  9205.8  184.21    9425  182.41  9724.4  184.35
 10119.7  183.41 10388.3  186.77 10712.4  181.99   10783  184.77 10860.2  184.08
 10873.1     184 10878.9  186.68 10900.4  190.31 10916.1  190.81 10918.3  192.54
#Mann= 4 ,-1 , 0
  3104.2     .05       0  4913.1    .035       0  5139.3     .05       0
 10860.2     .16       0
#XS Ineff= 2 , 0
          4687.5  190.75 5170.45          190.72
Permanent Ineff=
       F       F
Bank Sta=4920.1,5109.9
XS Rating Curve= 0 ,0
Exp/Cntr=0.3,0.1

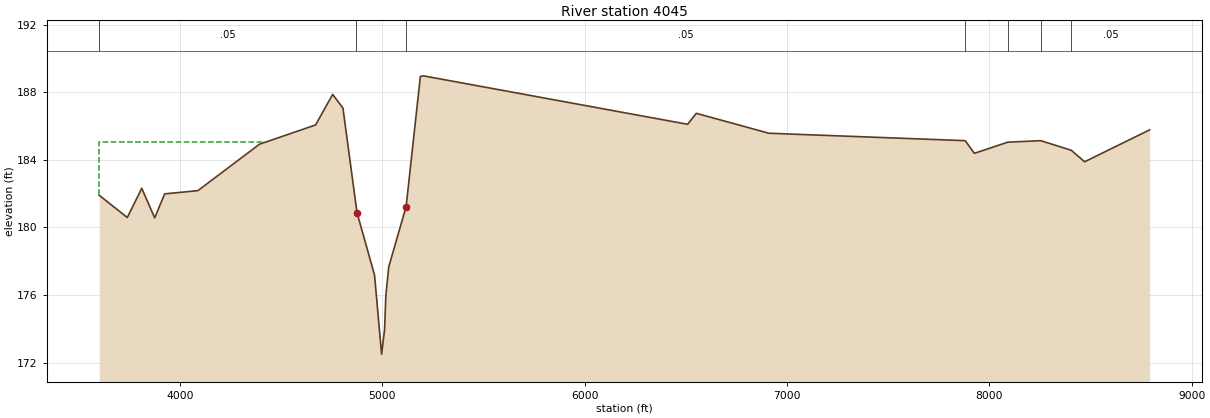
Type RM Length L Ch R = 1 ,4045    ,0,0,0
BEGIN DESCRIPTION:
BIG CREEK 1.0
END DESCRIPTION:
XS GIS Cut Line= 3
       3618276.4     10130129.79      3615740.05     10132254.79
      3614659.74     10133795.14
#Sta/Elev= 30
  3601.6  181.91  3740.5  180.59  3812.1  182.32  3875.8  180.57  3925.3  181.99
  4089.2  182.18  4393.7  184.93  4670.8  186.07  4755.4  187.88  4806.1  187.07
  4869.8  181.39  4876.4  180.84  4962.2  177.18  4997.1   172.5  5011.7  173.94
  5018.2  175.99  5032.5  177.67  5118.3  181.24  5188.6  188.94  5202.9  188.98
  6509.2  186.11  6552.1  186.76  6910.5  185.58  7880.9  185.14  7926.1  184.39
  8090.9  185.05    8254  185.14  8405.1  184.57  8470.9  183.89  8791.9  185.78
#Mann= 7 ,-1 , 0
  3601.6     .05       0  4869.8    .035       0  5118.3     .05       0
  7880.9      .1       0  8090.9     .05       0    8254      .1       0
  8405.1     .05       0
#XS Ineff= 2 , 0
         4411.36  185.04
Permanent Ineff=
       F       F
Bank Sta=4876.4,5118.3
XS Rating Curve= 0 ,0
Exp/Cntr=0.3,0.1

Chan Stop Cuts=-1
Use User Specified Reach Order=0
Composite Channel Slope=5