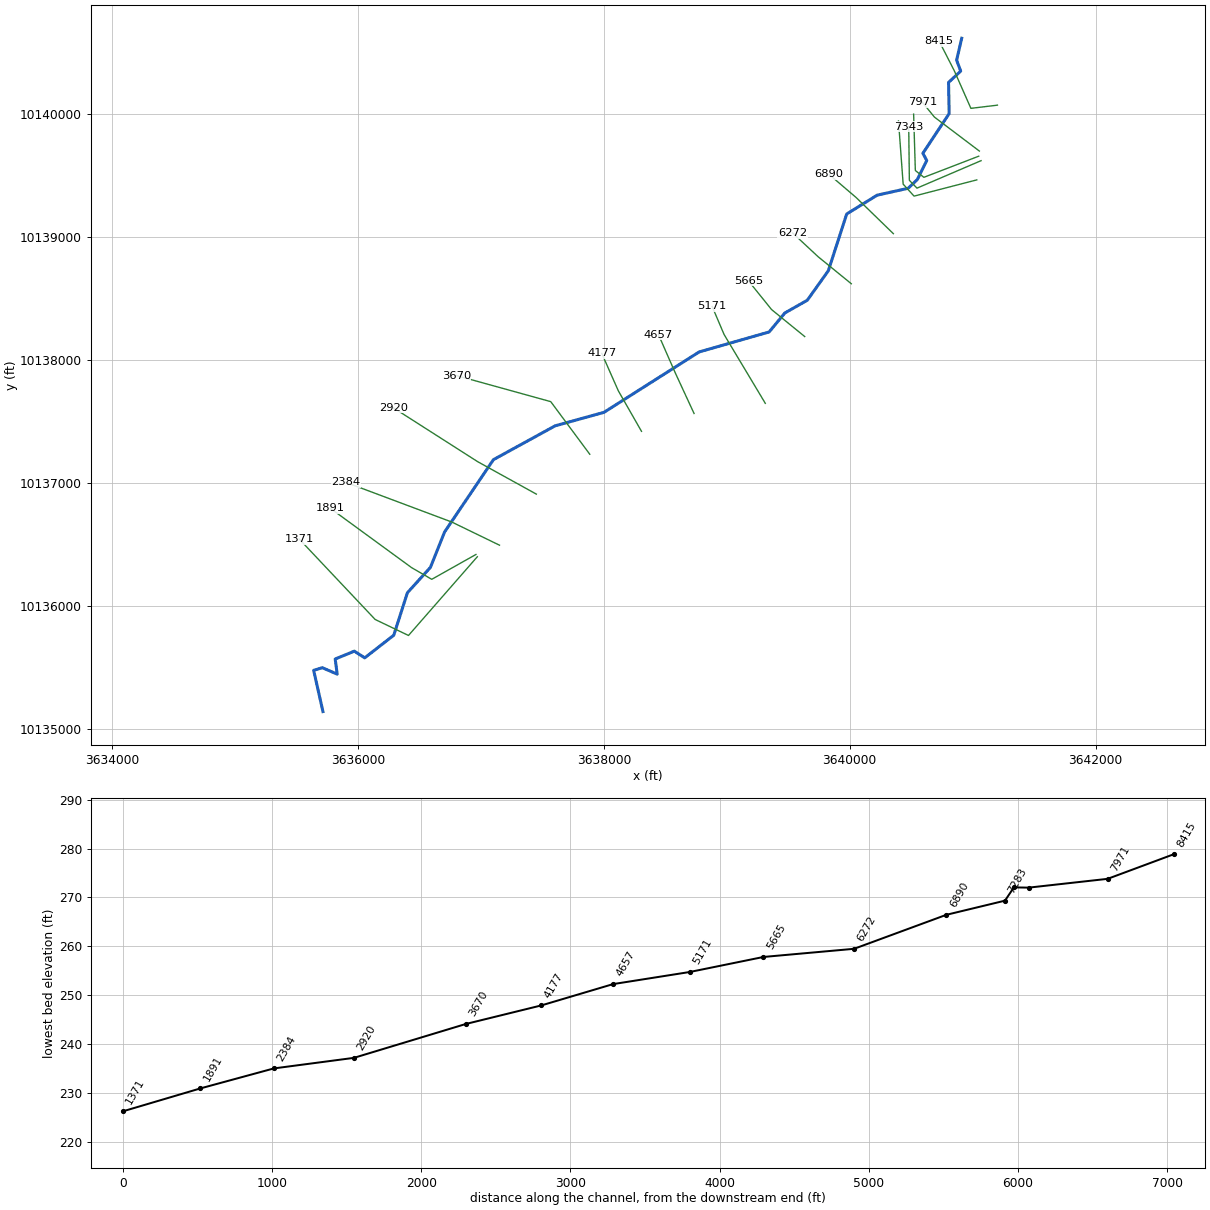
--- CEDAR CREEK TRIB 1.prj (project) ---

Proj Title=CEDAR CREEK TRIB 1 Base Level Engineering
Current Plan=p01
Default Exp/Contr=0.3,0.1
English Units
Geom File=g01
Flow File=f01
Plan File=p01
Y Axis Title=Elevation
X Axis Title(PF)=Main Channel Distance
X Axis Title(XS)=Station
BEGIN DESCRIPTION:
CEDAR CREEK TRIB 1
END DESCRIPTION:
DSS Export Rating Curves= 0
DSS Export Rating Curve Sorted= 0
DSS Export Volume Flow Curves= 0
DXF OffsetX= 0
DXF OffsetY= 0
DXF ScaleX= 1
DXF ScaleY= 10

--- CEDAR CREEK TRIB 1.p01 (plan) ---

Plan Title=Multiple Run
Short Identifier=Multiple
Geom File=g01
Flow File=f01
Subcritical Flow
K Sum by GR= 0
Std Step Tol= 0.01
Critical Tol= 0.01
Num of Std Step Trials= 20
Max Error Tol= 0.3
Flow Tol Ratio= 0.001
Split Flow NTrial= 30
Split Flow Tol= 0.02
Split Flow Ratio= 0.02
Log Output Level= 0
Friction Slope Method= 1
Unsteady Friction Slope Method= 2
Unsteady Bridges Friction Slope Method= 1
Parabolic Critical Depth
Global Vel Dist=  1 , 1 , 1
Global Log Level= 0
CheckData=True
Encroach Param= -1, 0, 0, 0
BEGIN DESCRIPTION:
Multiple Run
END DESCRIPTION:

--- CEDAR CREEK TRIB 1.f01 (steady flow) ---

Flow Title=Multiple
Program Version=4.10
Number of Profiles= 7
Profile Names=10-year,25-year,50-year,1pct_min,100-year,1pct_plu,500-year
River Rch & RM=CEDAR CREEK TRIB,Reach-1         ,8415
     394     517     614     536     725     981    1012
River Rch & RM=CEDAR CREEK TRIB,Reach-1         ,3670
     583     782     944     836    1131    1529    1623
River Rch & RM=CEDAR CREEK TRIB,Reach-1         ,2920
     583     782     944     836    1131    1529    1623
Boundary for River Rch & Prof#=CEDAR CREEK TRIB,Reach-1         , 1
Up Type= 0
Dn Type= 3
Dn Slope=0.005
Boundary for River Rch & Prof#=CEDAR CREEK TRIB,Reach-1         , 2
Up Type= 0
Dn Type= 3
Dn Slope=0.005
Boundary for River Rch & Prof#=CEDAR CREEK TRIB,Reach-1         , 3
Up Type= 0
Dn Type= 3
Dn Slope=0.005
Boundary for River Rch & Prof#=CEDAR CREEK TRIB,Reach-1         , 4
Up Type= 0
Dn Type= 3
Dn Slope=0.005
Boundary for River Rch & Prof#=CEDAR CREEK TRIB,Reach-1         , 5
Up Type= 0
Dn Type= 3
Dn Slope=0.005
Boundary for River Rch & Prof#=CEDAR CREEK TRIB,Reach-1         , 6
Up Type= 0
Dn Type= 3
Dn Slope=0.005
Boundary for River Rch & Prof#=CEDAR CREEK TRIB,Reach-1         , 7
Up Type= 0
Dn Type= 3
Dn Slope=0.005
DSS Import GetInterval= 0
DSS Import GetPeak= 0
DSS Import FillOption= 0

--- CEDAR CREEK TRIB 1.g01 (geometry) ---

Geom Title=Existing Conditions
Program Version=4.10

River Reach=CEDAR CREEK TRIB,Reach-1
Reach XY= 30
      3640911.12     10140615.07       3640869.8     10140436.92
      3640902.78     10140347.94      3640804.18     10140255.89
       3640809.1     10140002.95      3640595.39     10139679.71
      3640626.69     10139620.92      3640550.62     10139467.32
      3640475.97     10139395.27      3640223.27     10139339.24
      3639975.62     10139186.25       3639826.2     10138724.83
      3639655.37     10138485.19      3639472.19     10138381.15
      3639344.75     10138227.05       3638774.8     10138064.34
      3638001.34     10137573.49      3637604.31     10137464.01
      3637101.84     10137188.67      3636704.56     10136600.64
      3636589.24     10136312.77      3636402.31     10136106.62
       3636291.3     10135761.32      3636054.77     10135577.25
      3635970.81     10135631.89      3635814.77     10135567.91
      3635831.26     10135445.02      3635710.08     10135497.39
      3635639.77     10135475.69      3635715.29     10135140.62

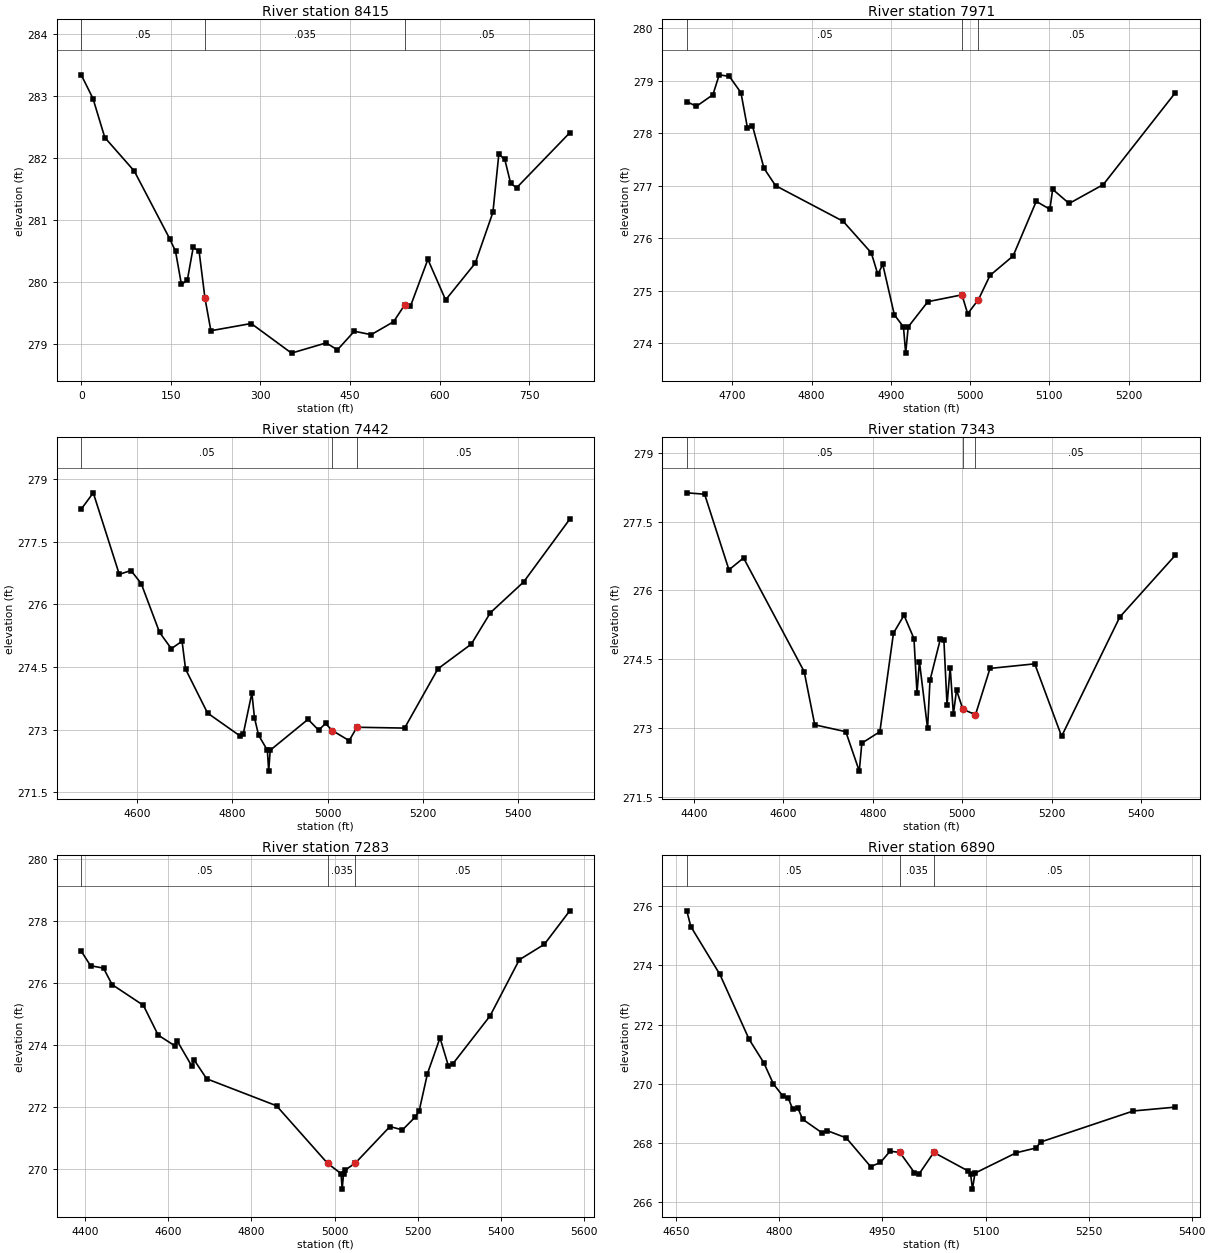
Type RM Length L Ch R = 1 ,8415    ,444,444,444
BEGIN DESCRIPTION:
CEDAR CREEK TRIB 1 13.0
END DESCRIPTION:
XS GIS Cut Line= 4
     3641201.617     10140071.08     3640985.873    10140045.151
     3640849.934    10140352.352     3640728.406      10140590.2
#Sta/Elev= 30
       0 283.33819.73804282.955339.47609 282.32888.82119281.7885148.0353280.7006
157.9043280.4964167.7734279.9629177.6424280.0284187.5114280.5578197.3804280.4976
207.2495 279.739217.1185 279.217284.6342279.3331  352.15278.8562410.0207279.0207
429.0674278.9093457.2721279.2089485.4768279.1532523.0831279.3617541.8863279.6368
551.2878  279.61580.4888280.3662610.1877279.7135659.6861280.3033689.3851281.1228
699.2847282.0589709.1844281.9787 719.084281.5913728.9837281.5181818.0807282.4048
#Mann= 3 ,-1 , 0
       0     .05       0207.2495    .035       0541.8863     .05       0
Bank Sta=207.2495,541.8863
XS Rating Curve= 0 ,0
Exp/Cntr=0.3,0.1

Type RM Length L Ch R = 1 ,7971    ,529,529,529
BEGIN DESCRIPTION:
CEDAR CREEK TRIB 1 12.0
END DESCRIPTION:
XS GIS Cut Line= 3
      3641054.76     10139697.92      3640689.32     10139974.02
      3640589.32     10140096.71
#Sta/Elev= 30
  4642.6   278.6  4654.6  278.51  4675.5  278.73  4683.5  279.11  4696.3  279.08
  4710.9  278.77  4719.1   278.1  4725.4  278.14    4740  277.33  4754.5     277
  4839.9  276.32  4875.3  275.72  4883.6  275.31  4889.8   275.5  4904.4  274.54
  4915.9  274.31  4918.7  273.81  4921.9  274.31  4946.7  274.79  4989.7  274.92
  4996.9  274.56  5010.5  274.83  5025.1  275.29  5054.2  275.66  5083.4   276.7
  5100.6  276.55  5104.1  276.93  5124.9  276.66    5168  277.02  5258.9  278.77
#Mann= 3 , 0 , 0
  4642.6     .05       0  4989.7    .035       0  5010.5     .05       0
Bank Sta=4989.7,5010.5
XS Rating Curve= 0 ,0
Exp/Cntr=0.3,0.1

Type RM Length L Ch R = 1 ,7442    ,99,99,99
BEGIN DESCRIPTION:
Mapping XS bde1bc72
END DESCRIPTION:
XS GIS Cut Line= 4
      3641049.61     10139656.18      3640603.41      10139484.3
      3640533.96     10139539.85      3640520.12     10139998.25
#Sta/Elev= 30
  4482.4  278.28  4507.7  278.67  4562.3  276.72  4586.9  276.81  4608.3   276.5
  4646.9  275.33  4671.6  274.94  4694.1  275.12  4701.5  274.45  4747.6   273.4
  4816.1  272.85  4822.6   272.9  4840.7  273.88  4846.1  273.29  4854.8  272.87
  4873.2  272.51    4876  272.01  4879.2  272.51  4958.6  273.25  4980.9  272.99
  4995.3  273.15  5009.7  272.98  5044.9  272.74  5061.3  273.06  5161.3  273.04
  5231.4  274.46  5301.4  275.05  5341.4   275.8  5411.5  276.54  5508.1  278.04
#Mann= 3 , 0 , 0
  4482.4     .05       0  5009.7    .035       0  5061.3     .05       0
Bank Sta=5009.7,5061.3
XS Rating Curve= 0 ,0
Exp/Cntr=0.3,0.1

Type RM Length L Ch R = 1 ,7343    ,60,60,60
BEGIN DESCRIPTION:
CEDAR CREEK TRIB 1 11.0
END DESCRIPTION:
XS GIS Cut Line= 4
      3641068.68     10139619.71      3640547.45     10139396.48
      3640485.35     10139459.99      3640480.14     10139895.81
#Sta/Elev= 30
  4384.2  278.13    4424   278.1  4478.4  276.45    4511  276.71  4646.5  274.23
  4670.1  273.07  4739.5  272.92  4769.6  272.06  4775.3  272.67  4815.6  272.92
    4846  275.07  4869.6  275.46  4891.8  274.95  4898.6  273.76    4904  274.45
  4922.2  272.99  4927.6  274.04    4951  274.95  4958.6  274.93  4965.7   273.5
  4972.7  274.32  4979.9   273.3  4986.9  273.83    5001  273.41  5029.3  273.29
  5061.7   274.3  5161.7   274.4  5221.7  272.82  5351.7  275.42  5475.9  276.77
#Mann= 3 , 0 , 0
  4384.2     .05       0    5001    .035       0  5029.3     .05       0
Bank Sta=5001,5029.3
XS Rating Curve= 0 ,0
Exp/Cntr=0.3,0.1

Type RM Length L Ch R = 1 ,7283    ,393,393,393
BEGIN DESCRIPTION:
Mapping XS 65ab4711
END DESCRIPTION:
XS GIS Cut Line= 4
      3641033.99     10139463.47      3640523.54     10139331.52
        3640435.     10139428.74      3640396.81      10139942.6
#Sta/Elev= 30
  4391.1  277.02  4413.5  276.55  4444.7  276.47  4465.3  275.94  4540.5  275.27
    4576  274.31  4616.6  273.96  4621.8  274.12  4657.3   273.3  4662.4  273.51
  4692.6   272.9  4860.4  272.03  4983.3  270.17  5015.5  269.84  5018.2  269.34
  5021.5  269.84  5025.9  269.96  5049.8  270.18    5133  271.36    5163  271.25
  5193.1  271.66  5203.1  271.86  5223.2  273.07  5253.3  274.22  5273.3  273.32
  5283.4  273.37  5373.6  274.93  5443.8  276.74    5504  277.24  5565.1  278.32
#Mann= 3 , 0 , 0
  4391.1     .05       0  4983.3    .035       0  5049.8     .05       0
Bank Sta=4983.3,5049.8
XS Rating Curve= 0 ,0
Exp/Cntr=0.3,0.1

Type RM Length L Ch R = 1 ,6890    ,618,618,618
BEGIN DESCRIPTION:
CEDAR CREEK TRIB 1 10.0
END DESCRIPTION:
XS GIS Cut Line= 3
      3640355.09     10139026.33      3640052.37     10139320.15
      3639832.36      10139507.9
#Sta/Elev= 30
  4665.2  275.84    4671  275.31  4713.4  273.69  4755.9   271.5  4777.2  270.71
  4791.3  269.99  4805.5  269.57  4812.5  269.53  4819.6  269.13  4826.6  269.19
  4833.8   268.8  4862.1  268.34    4869  268.42  4897.3  268.17  4932.8   267.2
    4947  267.34  4961.1  267.72  4975.3  267.68  4996.4     267  5003.5  266.96
  5024.7  267.68  5074.1  267.06  5078.3  266.94    5081  266.44  5084.6  266.98
  5144.9  267.67  5173.5  267.83  5180.1  268.03  5315.1  269.08  5376.3  269.21
#Mann= 3 ,-1 , 0
  4665.2     .05       0  4975.3    .035       0  5024.7     .05       0
Bank Sta=4975.3,5024.7
XS Rating Curve= 0 ,0
Exp/Cntr=0.3,0.1

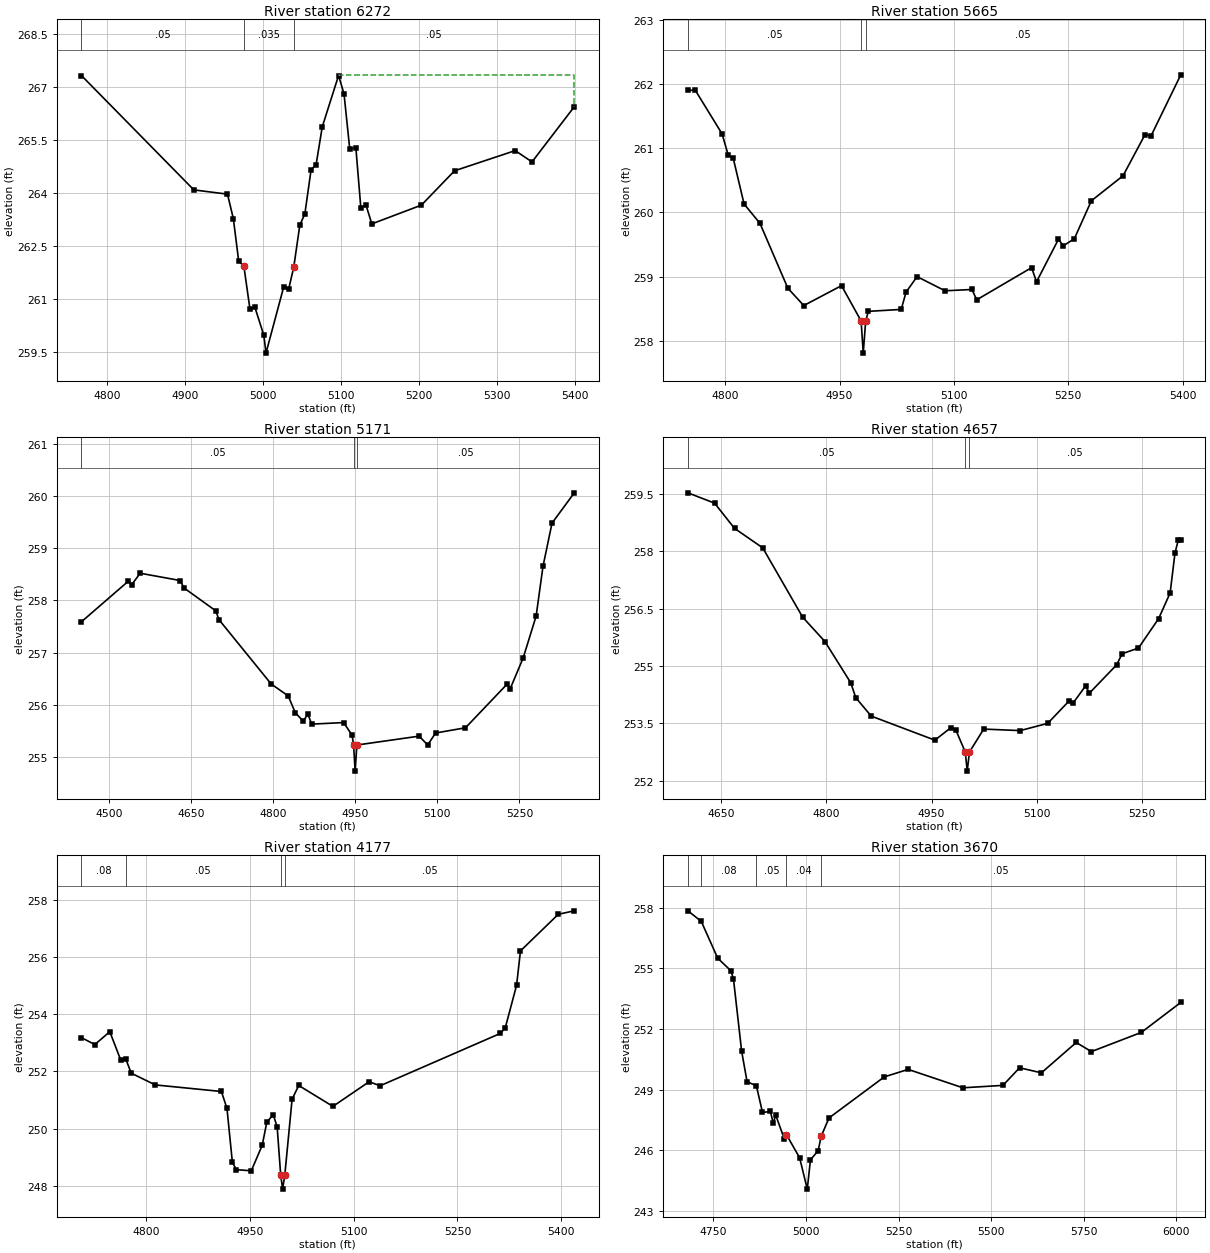
Type RM Length L Ch R = 1 ,6272    ,607,607,607
BEGIN DESCRIPTION:
CEDAR CREEK TRIB 1 9.0
END DESCRIPTION:
XS GIS Cut Line= 3
      3640013.07     10138619.18      3639743.88     10138838.18
      3639535.67     10139031.89
#Sta/Elev= 30
  4767.2  267.32  4911.2  264.09  4954.3  263.97  4961.8  263.28  4968.7  262.07
  4975.2  261.95  4983.1  260.72  4989.5  260.77  5000.9  259.98  5003.6  259.48
  5026.2  261.34  5032.6  261.28  5039.2  261.91    5047   263.1  5053.4  263.41
  5061.4  264.66  5067.8   264.8  5075.7  265.87  5096.6  267.32  5103.6   266.8
  5110.9  265.25  5118.8  265.27  5125.1  263.59  5131.9  263.65  5139.2  263.13
  5202.7  263.66  5245.2  264.63  5322.9   265.2  5344.4  264.88  5398.6  266.44
#Mann= 3 , 0 , 0
  4767.2     .05       0  4975.2    .035       0  5039.2     .05       0
#XS Ineff= 2 , 0
                         5096.53          267.34
Permanent Ineff=
       F       F
Bank Sta=4975.2,5039.2
XS Rating Curve= 0 ,0
Exp/Cntr=0.3,0.1

Type RM Length L Ch R = 1 ,5665    ,494,494,494
BEGIN DESCRIPTION:
CEDAR CREEK TRIB 1 8.0
END DESCRIPTION:
XS GIS Cut Line= 3
      3639633.96     10138189.92      3639364.81     10138408.89
      3639176.75     10138642.02
#Sta/Elev= 30
    4751   261.9  4760.7   261.9  4795.9  261.22  4803.9  260.89  4810.3  260.85
  4824.7  260.13  4845.5  259.83  4882.1  258.82    4903  258.55  4952.5  258.86
  4978.2  258.31    4981  257.81  4984.2  258.31  4987.7  258.46  5030.8  258.49
  5037.2  258.76  5051.6     259  5088.3  258.78  5123.5   258.8  5129.9  258.64
  5201.8  259.14  5208.3  258.92    5237  259.58  5243.5  259.48  5257.9  259.59
  5280.2  260.18  5321.8  260.57  5350.6  261.21  5358.5  261.19  5397.5  262.14
#Mann= 3 ,-1 , 0
    4751     .05       0  4978.2     .03       0  4984.2     .05       0
Bank Sta=4978.2,4984.2
XS Rating Curve= 0 ,0
Exp/Cntr=0.3,0.1

Type RM Length L Ch R = 1 ,5171    ,514,514,514
BEGIN DESCRIPTION:
CEDAR CREEK TRIB 1 7.0
END DESCRIPTION:
XS GIS Cut Line= 3
      3639313.49     10137646.74      3638978.39     10138206.25
      3638881.24     10138434.23
#Sta/Elev= 30
  4450.1  257.59    4536  258.37  4541.8   258.3  4557.4  258.52  4630.7  258.38
  4637.1  258.24  4695.4   257.8  4701.3  257.63  4796.5   256.4  4827.7  256.17
  4840.5  255.85  4854.9  255.69  4863.8  255.82  4870.4  255.63  4928.8  255.66
  4944.3  255.42  4947.1  255.23  4949.9  254.73  4953.1  255.23  5066.8   255.4
  5082.4  255.23  5096.7  255.46  5151.4  255.56  5227.7   256.4  5233.1  256.31
  5256.8   256.9  5280.4   257.7  5292.9  258.65  5309.4  259.48  5350.1  260.06
#Mann= 3 ,-1 , 0
  4450.1     .05       0  4947.1     .03       0  4953.1     .05       0
Bank Sta=4947.1,4953.1
XS Rating Curve= 0 ,0
Exp/Cntr=0.3,0.1

Type RM Length L Ch R = 1 ,4657    ,480,480,480
BEGIN DESCRIPTION:
CEDAR CREEK TRIB 1 6.0
END DESCRIPTION:
XS GIS Cut Line= 3
      3638734.03     10137564.03       3638581.5     10137893.79
      3638444.33     10138205.52
#Sta/Elev= 30
  4602.1  259.53  4640.2  259.26  4668.7   258.6    4709  258.09  4765.9  256.28
  4797.8  255.64  4834.7  254.56  4841.9  254.17  4863.9  253.69  4954.8  253.06
  4977.9  253.39  4984.9  253.32  4998.2  252.75    5001  252.25  5004.2  252.75
  5024.6  253.35  5076.7  253.31    5116   253.5  5146.7  254.09  5152.2  254.03
  5170.1  254.48  5175.5  254.29  5214.4  255.03  5222.2  255.32  5245.6  255.47
  5274.4  256.24  5290.8  256.91  5297.7  257.95  5302.5   258.3    5306   258.3
#Mann= 3 ,-1 , 0
  4602.1     .05       0  4998.2     .03       0  5004.2     .05       0
Bank Sta=4998.2,5004.2
XS Rating Curve= 0 ,0
Exp/Cntr=0.3,0.1

Type RM Length L Ch R = 1 ,4177    ,507,507,507
BEGIN DESCRIPTION:
CEDAR CREEK TRIB 1 5.0
END DESCRIPTION:
XS GIS Cut Line= 3
      3638306.39     10137419.12      3638118.23     10137748.06
       3637983.3     10138052.77
#Sta/Elev= 30
  4706.6  253.18    4726  252.94  4747.6  253.39  4763.5  252.39  4770.4  252.45
  4778.6  251.94  4813.2  251.53  4908.8   251.3  4916.9  250.71  4924.7  248.83
  4930.4  248.57    4952  248.53  4967.8  249.42  4974.5  250.23  4983.7  250.49
  4989.4  250.07  4994.5  248.39  4997.3  247.89  5000.5  248.39    5011  251.03
  5020.6  251.51    5070  250.78  5122.3  251.64  5138.2   251.5  5312.1  253.33
  5319.1  253.53  5335.4  255.01    5341  256.21  5395.7  257.49  5418.8  257.61
#Mann= 4 ,-1 , 0
  4706.6     .08       0  4770.4     .05       0  4994.5    .035       0
  5000.5     .05       0
Bank Sta=4994.5,5000.5
XS Rating Curve= 0 ,0
Exp/Cntr=0.3,0.1

Type RM Length L Ch R = 1 ,3670    ,750,750,750
BEGIN DESCRIPTION:
CEDAR CREEK TRIB 1 4.0
END DESCRIPTION:
XS GIS Cut Line= 3
      3637885.58     10137232.92       3637568.3     10137660.56
       3636799.6       10137873.
#Sta/Elev= 30
  4681.6  257.84  4717.6  257.32    4762   255.5  4797.4  254.88  4804.5  254.48
  4826.6   250.9  4841.3  249.39  4866.4  249.19  4882.9  247.87  4904.1  247.92
  4912.2  247.33  4918.4  247.75  4941.4  246.58  4947.6  246.77  4983.1  245.63
  5003.7  244.08  5012.3  245.53  5033.2  245.98  5041.1  246.69  5062.4   247.6
  5211.6  249.63    5276     250  5423.7  249.09  5531.8  249.21  5576.6  250.08
  5635.5  249.83  5729.5  251.33  5770.4  250.88  5905.3  251.83  6011.6  253.31
#Mann= 5 ,-1 , 0
  4681.6      .1       0  4717.6     .08       0  4866.4     .05       0
  4947.6     .04       0  5041.1     .05       0
Bank Sta=4947.6,5041.1
XS Rating Curve= 0 ,0
Exp/Cntr=0.3,0.1

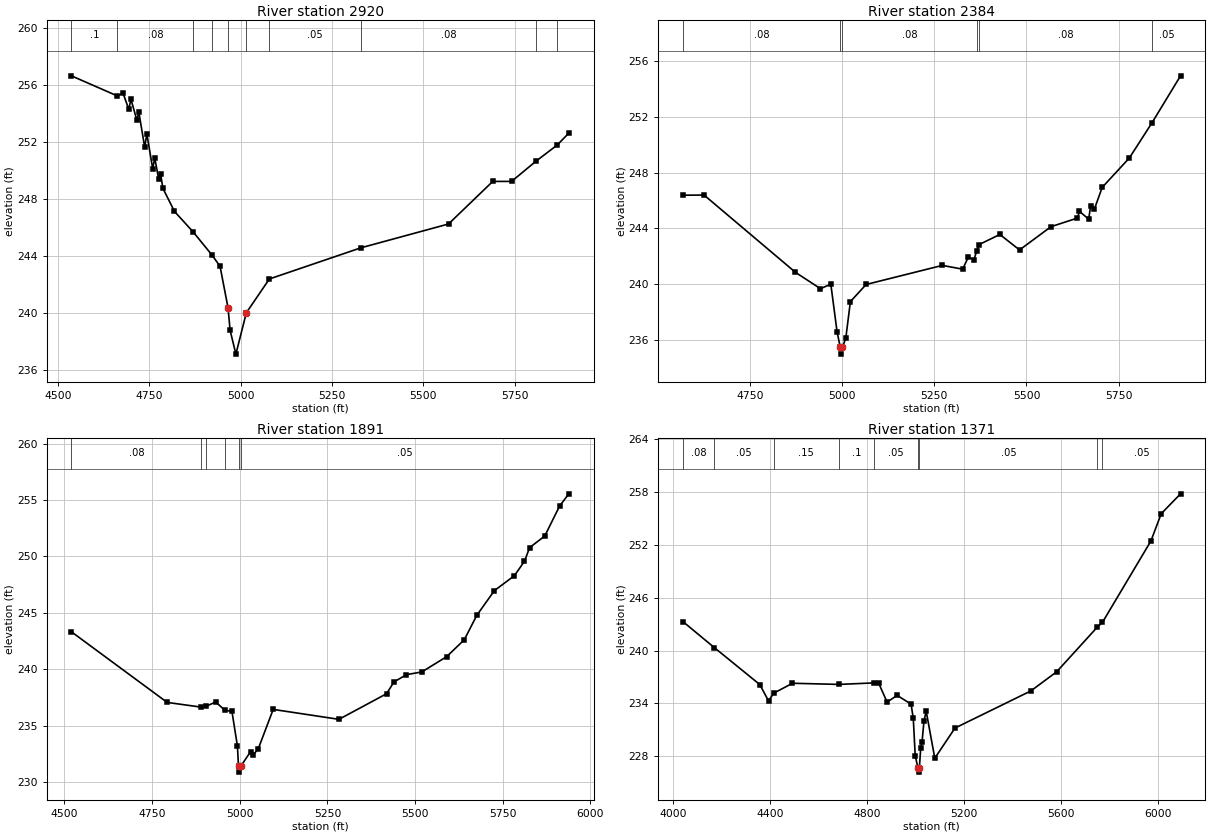
Type RM Length L Ch R = 1 ,2920    ,536,536,536
BEGIN DESCRIPTION:
CEDAR CREEK TRIB 1 3.0
END DESCRIPTION:
XS GIS Cut Line= 3
      3637451.04     10136908.68      3636974.55     10137171.97
      3636286.21     10137611.69
#Sta/Elev= 30
  4537.2  256.62  4663.2  255.21  4678.3  255.42  4694.3  254.27    4700  254.99
  4716.1  253.53  4721.8  254.06  4737.8  251.62  4743.6  252.56  4759.6  250.13
  4765.3  250.86  4775.7  249.43  4781.4  249.74  4787.3  248.76  4819.2  247.13
  4870.8  245.68  4922.7  244.05    4944  243.28  4965.8  240.38  4971.5   238.8
  4987.3  237.14  5015.8  240.03  5078.8   242.4  5329.2  244.58  5569.2  246.25
  5690.2  249.23  5741.7  249.23  5809.3  250.66  5866.3  251.77  5898.4  252.61
#Mann= 10 ,-1 , 0
  4537.2      .1       0  4663.2     .08       0  4870.8     .05       0
  4922.7     .08       0  4965.8     .05       0  5015.8     .08       0
  5078.8     .05       0  5329.2     .08       0  5809.3     .05       0
  5866.3     .08       0
Bank Sta=4965.8,5015.8
XS Rating Curve= 0 ,0
Exp/Cntr=0.3,0.1

Type RM Length L Ch R = 1 ,2384    ,493,493,493
BEGIN DESCRIPTION:
CEDAR CREEK TRIB 1 2.0
END DESCRIPTION:
XS GIS Cut Line= 3
      3637151.37     10136493.42      3636762.79     10136681.95
      3635902.87     10137003.86
#Sta/Elev= 30
  4568.1  246.39  4624.9   246.4  4873.1  240.85  4940.8  239.68    4969     240
    4986  236.57  4994.6  235.48  4997.4  234.98  5000.6  235.48  5009.7  236.14
  5022.1  238.75  5064.8  239.98  5271.6  241.35  5326.8  241.08  5342.4  241.96
  5357.1  241.74  5365.2   242.4    5371  242.84  5427.8  243.57  5481.2  242.46
  5566.6  244.13  5638.5  244.75  5643.8  245.23  5668.8  244.67  5674.1  245.59
  5684.1  245.37  5705.5  246.95  5779.2  249.06    5841   251.6  5918.2  254.96
#Mann= 6 ,-1 , 0
  4568.1     .08       0  4994.6     .07       0  5000.6     .08       0
  5365.2     .05       0    5371     .08       0    5841     .05       0
Bank Sta=4994.6,5000.6
XS Rating Curve= 0 ,0
Exp/Cntr=0.3,0.1

Type RM Length L Ch R = 1 ,1891    ,520,520,520
BEGIN DESCRIPTION:
Mapping XS 8b764d22
END DESCRIPTION:
XS GIS Cut Line= 4
      3636959.76     10136417.82      3636600.36     10136215.99
       3636436.3     10136311.04      3635776.59     10136792.48
#Sta/Elev= 30
  4519.9  243.32    4793  237.06  4890.3  236.64  4902.8   236.7  4931.4   237.1
  4957.1  236.37  4977.7  236.26  4993.4  233.17  4996.4  231.38  4999.2  230.88
  5002.4  231.38  5030.7  232.69  5036.5  232.37  5052.3  232.91  5095.3  236.44
  5282.8  235.56  5418.7  237.83  5439.6  238.87  5475.1  239.52  5519.1  239.76
  5590.2  241.12  5640.4  242.62  5675.9  244.78  5726.1  246.97    5783  248.29
  5811.9  249.57  5826.5  250.78  5869.7  251.81  5912.3  254.48  5938.4  255.55
#Mann= 6 ,-1 , 0
  4519.9     .08       0  4890.3     .05       0  4902.8     .08       0
  4957.1     .05       0  4996.4     .04       0  5002.4     .05       0
Bank Sta=4996.4,5002.4
XS Rating Curve= 0 ,0
Exp/Cntr=0.3,0.1

Type RM Length L Ch R = 1 ,1371    ,0,0,0
BEGIN DESCRIPTION:
CEDAR CREEK TRIB 1 1.0
END DESCRIPTION:
XS GIS Cut Line= 4
      3636971.05     10136399.61      3636411.12     10135759.39
      3636139.85      10135889.6      3635521.83     10136544.08
#Sta/Elev= 30
  4040.1  243.27  4168.5  240.34  4356.4  236.13  4392.5  234.27  4413.6  235.15
  4491.2  236.28    4683  236.15  4826.5  236.32  4846.2  236.32  4881.3  234.14
  4922.8   234.9  4980.3  233.91  4989.4  232.28  4997.4  228.03  5008.6  226.68
  5011.3  226.18  5014.6  226.68    5020   228.9  5025.6  229.63  5033.7  232.03
  5042.7  233.09  5078.1  227.76  5161.4  231.19  5474.3  235.41  5580.3  237.57
  5748.7  242.67  5769.6   243.2  5969.5  252.45  6011.9  255.55  6091.7  257.81
#Mann= 9 ,-1 , 0
  4040.1     .08       0  4168.5     .05       0  4413.6     .15       0
    4683      .1       0  4826.5     .05       0  5008.6     .04       0
  5014.6     .05       0  5748.7     .08       0  5769.6     .05       0
Bank Sta=5008.6,5014.6
XS Rating Curve= 0 ,0
Exp/Cntr=0.3,0.1

Chan Stop Cuts=-1
Use User Specified Reach Order=0
Composite Channel Slope=5