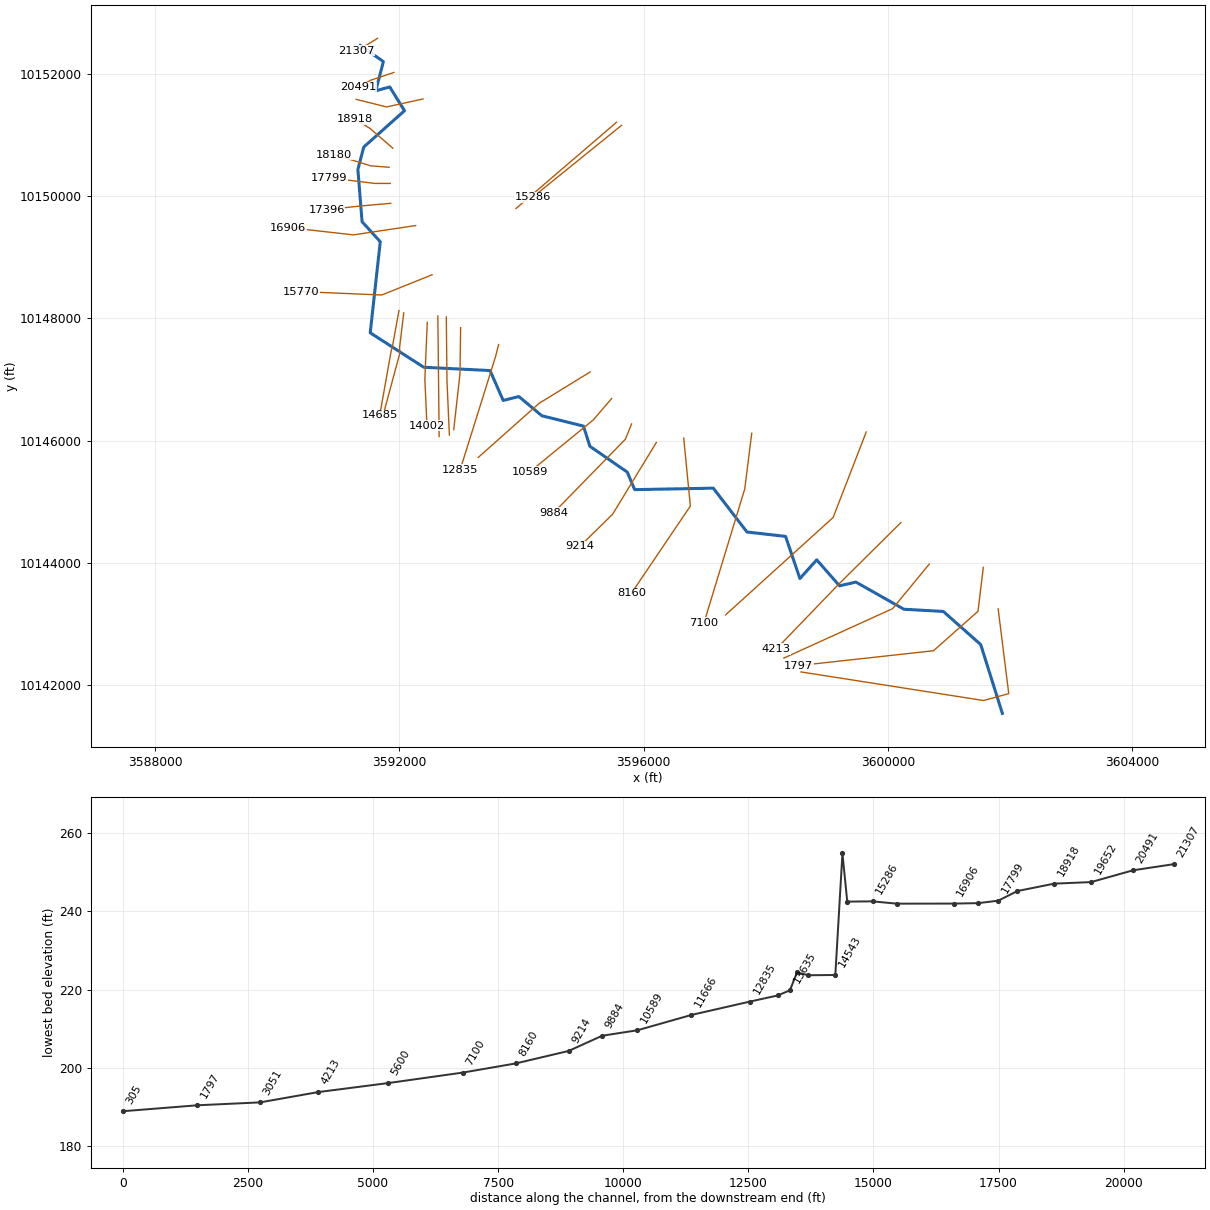
--- CLIFTY CREEK.prj (project) ---

Proj Title=CLIFTY CREEK Base Level Engineering
Current Plan=p01
Default Exp/Contr=0.3,0.1
English Units
Geom File=g01
Flow File=f01
Plan File=p01
Y Axis Title=Elevation
X Axis Title(PF)=Main Channel Distance
X Axis Title(XS)=Station
BEGIN DESCRIPTION:
CLIFTY CREEK
END DESCRIPTION:
DSS Export Rating Curves= 0
DSS Export Rating Curve Sorted= 0
DSS Export Volume Flow Curves= 0
DXF OffsetX= 0
DXF OffsetY= 0
DXF ScaleX= 1
DXF ScaleY= 10

--- CLIFTY CREEK.p01 (plan) ---

Plan Title=Multiple Run
Short Identifier=Multiple
Geom File=g01
Flow File=f01
Subcritical Flow
K Sum by GR= 0
Std Step Tol= 0.01
Critical Tol= 0.01
Num of Std Step Trials= 20
Max Error Tol= 0.3
Flow Tol Ratio= 0.001
Split Flow NTrial= 30
Split Flow Tol= 0.02
Split Flow Ratio= 0.02
Log Output Level= 0
Friction Slope Method= 1
Unsteady Friction Slope Method= 2
Unsteady Bridges Friction Slope Method= 1
Parabolic Critical Depth
Global Vel Dist=  1 , 1 , 1
Global Log Level= 0
CheckData=True
Encroach Param= -1, 0, 0, 0
BEGIN DESCRIPTION:
Multiple Run
END DESCRIPTION:

--- CLIFTY CREEK.f01 (steady flow) ---

Flow Title=Multiple
Program Version=4.10
Number of Profiles= 7
Profile Names=10-year,25-year,50-year,1pct_min,100-year,1pct_plu,500-year
River Rch & RM=CLIFTY CREEK,Reach-1         ,21307
     533     713     858     757    1023    1384    1459
River Rch & RM=CLIFTY CREEK,Reach-1         ,19652
     930    1279    1568    1406    1902    2572    2804
River Rch & RM=CLIFTY CREEK,Reach-1         ,11666
    1740    2458    3067    2795    3779    5111    5754
River Rch & RM=CLIFTY CREEK,Reach-1         ,3051
    1985    2814    3522    3215    4348    5881    6650
Boundary for River Rch & Prof#=CLIFTY CREEK,Reach-1         , 1
Up Type= 0
Dn Type= 3
Dn Slope=0.005
Boundary for River Rch & Prof#=CLIFTY CREEK,Reach-1         , 2
Up Type= 0
Dn Type= 3
Dn Slope=0.005
Boundary for River Rch & Prof#=CLIFTY CREEK,Reach-1         , 3
Up Type= 0
Dn Type= 3
Dn Slope=0.005
Boundary for River Rch & Prof#=CLIFTY CREEK,Reach-1         , 4
Up Type= 0
Dn Type= 3
Dn Slope=0.005
Boundary for River Rch & Prof#=CLIFTY CREEK,Reach-1         , 5
Up Type= 0
Dn Type= 3
Dn Slope=0.005
Boundary for River Rch & Prof#=CLIFTY CREEK,Reach-1         , 6
Up Type= 0
Dn Type= 3
Dn Slope=0.005
Boundary for River Rch & Prof#=CLIFTY CREEK,Reach-1         , 7
Up Type= 0
Dn Type= 3
Dn Slope=0.005
DSS Import GetInterval= 0
DSS Import GetPeak= 0
DSS Import FillOption= 0

--- CLIFTY CREEK.g01 (geometry) ---

Geom Title=Existing Conditions
Program Version=4.10

River Reach=CLIFTY CREEK    ,Reach-1
Reach XY= 30
      3591358.82      10152475.2      3591737.56     10152210.76
      3591612.74     10151731.54       3591841.9      10151794.9
      3592083.22     10151405.15      3591415.69     10150809.66
       3591320.2     10150441.61      3591388.78      10149585.7
      3591686.52     10149257.58      3591522.11     10147765.39
      3592398.88     10147200.59      3593484.89      10147146.6
      3593699.74     10146656.88      3593956.82      10146720.2
      3594333.79     10146404.83      3595014.63      10146236.7
      3595119.96      10145905.1      3595732.42     10145481.88
      3595853.53     10145194.75       3597141.1     10145218.91
      3597692.63     10144500.26      3598325.04     10144428.55
      3598559.55     10143737.42      3598835.53       10144044.
      3599209.12      10143617.8      3599476.18     10143679.87
      3600263.27     10143234.43      3600909.11      10143198.2
      3601521.09     10142655.67       3601875.8     10141527.61

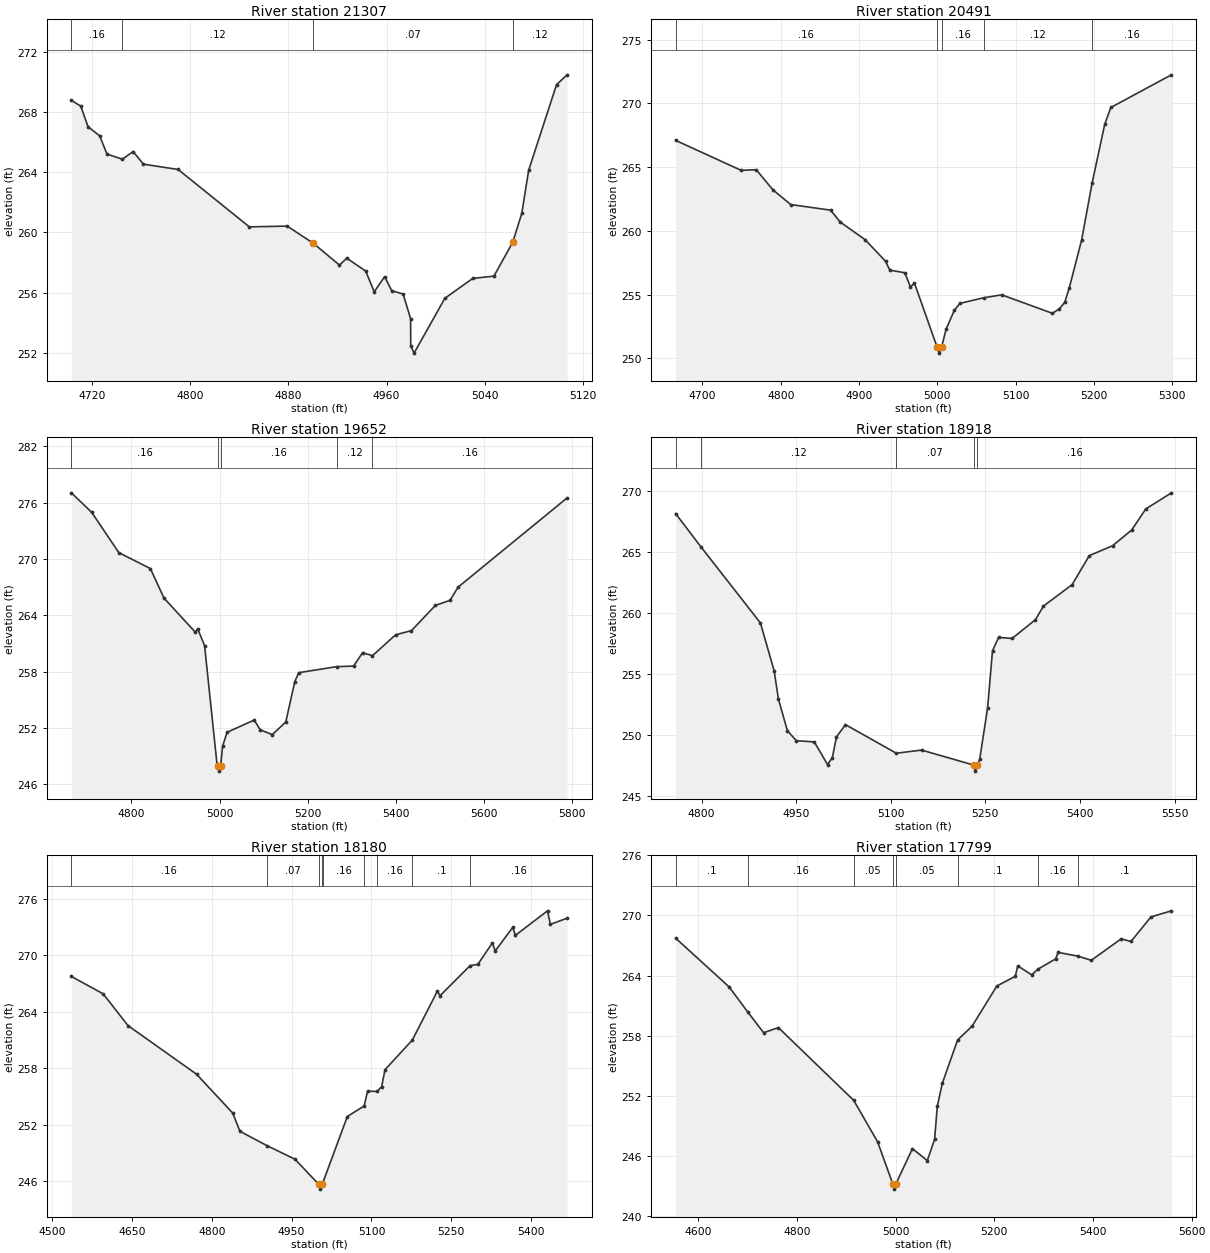
Type RM Length L Ch R = 1 ,21307   ,816,816,816
BEGIN DESCRIPTION:
CLIFTY CREEK 47.0
END DESCRIPTION:
XS GIS Cut Line= 3
       3591642.1     10152591.64      3591401.96     10152443.74
      3591292.12     10152391.65
#Sta/Elev= 30
  4703.4  268.77  4711.1  268.38    4717  267.01  4726.5  266.41  4732.4   265.2
    4745  264.86  4753.7  265.37  4762.1  264.53  4790.3  264.18  4848.3  260.37
  4879.1  260.42  4900.4  259.28  4921.7  257.83  4927.6  258.29    4943  257.44
    4950  256.06  4958.4  257.06  4964.2  256.14  4973.5  255.91  4979.6  254.27
  4979.7  252.49  4982.4  251.99  5007.5  255.63  5030.2  256.95  5047.4   257.1
  5062.7  259.34  5070.1  261.26  5075.7  264.13  5098.4  269.81    5107  270.46
#Mann= 4 ,-1 , 0
  4703.4     .16       0    4745     .12       0  4900.4     .07       0
  5062.7     .12       0
Bank Sta=4900.4,5062.7
XS Rating Curve= 0 ,0
Exp/Cntr=0.3,0.1

Type RM Length L Ch R = 1 ,20491   ,839,839,839
BEGIN DESCRIPTION:
CLIFTY CREEK 45.0
END DESCRIPTION:
XS GIS Cut Line= 3
      3591909.87     10152031.98      3591530.04     10151905.48
      3591328.32     10151788.94
#Sta/Elev= 30
  4665.8   267.1  4749.5  264.75  4768.8   264.8  4789.9  263.23  4812.8  262.07
  4863.7  261.63    4876   260.7  4907.7  259.32    4934  257.62  4939.3  256.93
  4958.6  256.72  4965.7  255.61  4970.9   255.9  4999.6  250.92  5002.3  250.42
  5005.6  250.92  5011.3   252.3  5021.8  253.78  5028.9  254.32  5059.2  254.76
  5082.4  254.99  5147.1  253.54  5156.1   253.9  5162.8   254.4  5168.6  255.53
  5184.4  259.29  5197.7  263.73  5213.9  268.36  5221.7  269.68  5299.1  272.24
#Mann= 5 ,-1 , 0
  4665.8     .16       0  4999.6     .07       0  5005.6     .16       0
  5059.2     .12       0  5197.7     .16       0
Bank Sta=4999.6,5005.6
XS Rating Curve= 0 ,0
Exp/Cntr=0.3,0.1

Type RM Length L Ch R = 1 ,19652   ,734,734,734
BEGIN DESCRIPTION:
CLIFTY CREEK 43.0
END DESCRIPTION:
XS GIS Cut Line= 3
      3592387.35     10151597.96      3591790.38     10151467.07
      3591292.07     10151591.65
#Sta/Elev= 30
  4663.7  277.06    4710  274.98  4771.4  270.69  4843.1  268.99  4873.8  265.85
  4945.2   262.2  4950.3  262.58    4966  260.78  4994.1   248.2  4996.3  247.91
    4999  247.41  5002.3  247.91  5006.9  250.08  5017.1  251.55  5078.6  252.85
    5092  251.82  5119.5   251.3  5150.2  252.64  5170.7  256.95  5179.7   257.9
  5265.4  258.54    5304   258.6  5324.6  260.03  5346.9  259.71  5399.3  261.93
  5435.4  262.38  5489.5  265.06    5523  265.61  5541.1  267.01  5788.5  276.52
#Mann= 5 ,-1 , 0
  4663.7     .16       0  4996.3     .07       0  5002.3     .16       0
  5265.4     .12       0  5346.9     .16       0
Bank Sta=4996.3,5002.3
XS Rating Curve= 0 ,0
Exp/Cntr=0.3,0.1

Type RM Length L Ch R = 1 ,18918   ,738,738,738
BEGIN DESCRIPTION:
CLIFTY CREEK 41.0
END DESCRIPTION:
XS GIS Cut Line= 3
      3591892.12     10150791.63      3591518.15     10151115.25
      3591268.16     10151265.25
#Sta/Elev= 30
    4759  268.18  4798.8  265.47  4893.4   259.2  4915.3  255.24  4921.9  252.95
  4936.2  250.34  4950.4  249.52  4978.9  249.42  4999.8  247.56  5007.4  248.12
    5014  249.83  5028.3  250.84  5108.9  248.49  5148.9  248.75  5231.4  247.52
  5234.2  247.02  5237.4  247.52  5241.1     248  5253.6   252.2  5261.4  256.91
  5271.1  258.01  5292.4  257.92  5329.4  259.46  5342.2  260.58  5387.7  262.35
  5414.9  264.73  5451.8  265.54  5482.2  266.84  5504.3  268.56  5545.1  269.89
#Mann= 5 ,-1 , 0
    4759     .16       0  4798.8     .12       0  5108.9     .07       0
  5231.4     .07       0  5237.4     .16       0
Bank Sta=5231.4,5237.4
XS Rating Curve= 0 ,0
Exp/Cntr=0.3,0.1

Type RM Length L Ch R = 1 ,18180   ,381,381,381
BEGIN DESCRIPTION:
CLIFTY CREEK 40.0
END DESCRIPTION:
XS GIS Cut Line= 3
      3591831.82     10150478.17       3591532.3     10150501.79
        3590929.     10150686.51
#Sta/Elev= 30
  4536.2  267.75  4596.1  265.89  4642.6  262.52  4771.4  257.35  4839.4  253.22
  4852.9  251.28  4903.9  249.75  4956.4  248.31  5001.2  245.63  5003.9  245.13
  5007.2  245.63  5008.4  245.77  5054.7  252.85  5086.3  253.97  5092.7  255.54
  5110.7  255.52  5119.2  256.03  5125.5  257.83  5176.8  260.98  5223.8  266.17
    5229   265.7  5285.5   268.9  5299.8  269.02  5327.3  271.32  5332.5  270.45
  5365.3  272.95  5370.5  272.12  5430.8  274.72  5436.1  273.28  5467.6  273.94
#Mann= 9 ,-1 , 0
  4536.2     .16       0  4903.9     .07       0  5001.2     .07       0
  5007.2     .07       0  5008.4     .16       0  5086.3     .07       0
  5110.7     .16       0  5176.8      .1       0  5285.5     .16       0
Bank Sta=5001.2,5007.2
XS Rating Curve= 0 ,0
Exp/Cntr=0.3,0.1

Type RM Length L Ch R = 1 ,17799   ,403,403,403
BEGIN DESCRIPTION:
CLIFTY CREEK 39.0
END DESCRIPTION:
XS GIS Cut Line= 3
      3591850.44     10150213.52      3591600.44     10150213.52
      3590850.85     10150304.56
#Sta/Elev= 30
  4553.9  267.73  4662.2  262.87  4700.2  260.35  4732.2  258.29  4762.2   258.8
    4915  251.53  4963.4  247.39  4994.2  243.17  4996.9  242.67  5000.2  243.17
  5033.9  246.71  5064.1  245.52  5078.9  247.65  5084.3  250.93  5094.4  253.22
  5125.5  257.56  5154.8  258.94  5205.2  262.96  5242.5  263.92  5247.5  264.96
  5275.7  264.07  5288.6  264.64  5324.2  265.66  5329.3  266.31  5369.8  265.93
  5396.6  265.52    5457  267.66  5477.1   267.4  5517.4  269.85    5559  270.46
#Mann= 8 ,-1 , 0
  4553.9      .1       0  4700.2     .16       0    4915     .05       0
  4994.2    .033       0  5000.2     .05       0  5125.5      .1       0
  5288.6     .16       0  5369.8      .1       0
Bank Sta=4994.2,5000.2
XS Rating Curve= 0 ,0
Exp/Cntr=0.3,0.1

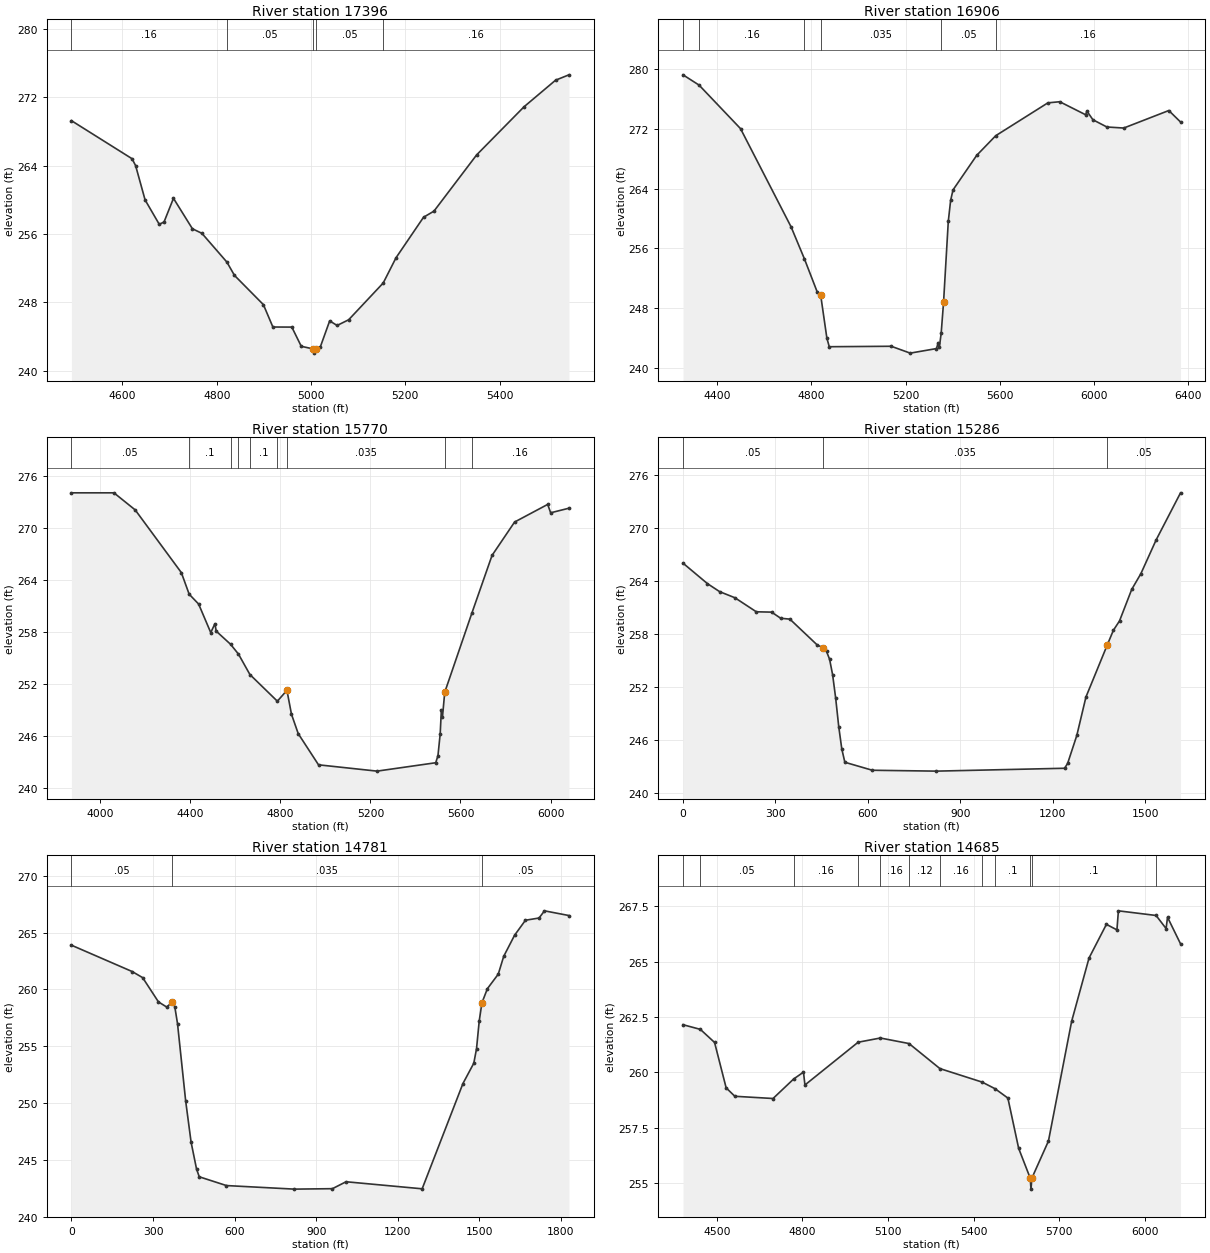
Type RM Length L Ch R = 1 ,17396   ,490,490,490
BEGIN DESCRIPTION:
CLIFTY CREEK 38.0
END DESCRIPTION:
XS GIS Cut Line= 3
      3591857.79     10149887.89      3591342.11     10149841.64
      3590807.49     10149783.73
#Sta/Elev= 30
  4491.7  269.28  4620.3  264.82  4627.9  264.01    4648  259.99  4678.1  257.13
  4688.2  257.41  4708.2  260.18  4748.4  256.61  4768.5  256.08  4821.5  252.71
  4837.6  251.15    4899  247.72  4919.1   245.1  4959.3  245.09  4979.3  242.84
  5003.9  242.54  5006.7  242.04  5009.9  242.54  5019.5  242.73  5039.6  245.82
  5055.3  245.28  5079.9  245.95  5153.2  250.26  5180.4  253.22  5238.7  257.96
  5260.9  258.68  5351.4  265.27    5452  270.91  5518.8  274.02  5547.2  274.65
#Mann= 5 ,-1 , 0
  4491.7     .16       0  4821.5     .05       0  5003.9    .033       0
  5009.9     .05       0  5153.2     .16       0
Bank Sta=5003.9,5009.9
XS Rating Curve= 0 ,0
Exp/Cntr=0.3,0.1

Type RM Length L Ch R = 1 ,16906   ,1136,1136,1136
BEGIN DESCRIPTION:
CLIFTY CREEK 37.0
END DESCRIPTION:
XS GIS Cut Line= 3
      3592265.85     10149523.32      3591247.82     10149370.32
      3590172.64     10149491.08
#Sta/Elev= 30
  4255.5  279.27  4323.7  277.89  4499.6  272.05  4714.3  258.86  4770.7  254.58
  4825.6  250.09  4839.7  249.72    4866  243.95  4876.1  242.79  5139.1  242.85
  5219.7  241.93    5331  242.54  5338.8  243.34  5343.8  242.81  5351.1  244.59
  5361.2  248.75  5381.3  259.61  5391.3  262.44  5401.4  263.83    5502  268.47
  5582.5   271.1  5803.9  275.51  5854.2  275.66  5964.3  273.91  5969.4  274.41
  5995.1  273.24  6054.4  272.27  6125.9  272.13  6317.1  274.48  6366.9  272.94
#Mann= 6 ,-1 , 0
  4255.5      .1       0  4323.7     .16       0  4770.7     .05       0
  4839.7    .035       0  5351.1     .05       0  5582.5     .16       0
Bank Sta=4839.7,5361.2
XS Rating Curve= 0 ,0
Exp/Cntr=0.3,0.1

Type RM Length L Ch R = 1 ,15770   ,484,484,484
BEGIN DESCRIPTION:
CLIFTY CREEK 34.0
END DESCRIPTION:
XS GIS Cut Line= 3
      3592534.93     10148716.03      3591711.64     10148384.74
      3590390.96     10148440.55
#Sta/Elev= 30
  3872.4  274.11  4061.2  274.11  4155.7  272.13  4360.5  264.88  4395.3  262.38
  4437.3  261.24  4491.1  257.94  4509.8  258.97  4515.2  258.11    4579  256.59
  4614.2  255.45  4664.9  253.09  4786.9     250  4829.4  251.26  4849.5   248.5
  4879.5  246.25  4969.6  242.64  5229.5  241.91    5490  242.88    5500  243.69
    5510  246.23  5515.2  249.01  5520.2  248.21  5530.1  251.03  5650.2  260.16
  5740.2  266.87  5840.3  270.73  5987.3  272.77  6000.5   271.8  6081.7  272.33
#Mann= 9 ,-1 , 0
  3872.4     .05       0  4395.3      .1       0    4579     .16       0
  4614.2     .05       0  4664.9      .1       0  4786.9     .05       0
  4829.4    .035       0  5530.1     .05       0  5650.2     .16       0
Bank Sta=4829.4,5530.1
XS Rating Curve= 0 ,0
Exp/Cntr=0.3,0.1

Type RM Length L Ch R = 1 ,15286   ,505,505,505
BEGIN DESCRIPTION:
CLIFTY CREEK 33.0
END DESCRIPTION:
XS GIS Cut Line= 2
3595637.6368354910151164.62289873594181.09354183 10149986.491033
#Sta/Elev= 30
       0266.042479.30911263.7248118.9637262.8146168.5319262.1246237.9273260.5358
287.4955260.4977317.2365259.8023346.9774259.7041436.2001256.7626456.0274256.4557
 465.941 256.045475.8546 255.165485.7683253.3939495.6819250.7355505.5956247.5219
515.5092245.0021525.4229243.5003614.6456242.5944822.7379242.49641238.781242.8206
1248.687243.37241278.404246.53161308.122250.88981377.462256.79461397.274258.4456
1417.085259.50111456.708263.06851486.426264.85041535.955268.67071615.201274.0039
#Mann= 3 , 0 , 0
       0     .05       0456.0274    .035       01377.462     .05       0
Bank Sta=456.0274,1377.462
XS Rating Curve= 0 ,0
Exp/Cntr=0.3,0.1

Type RM Length L Ch R = 1 ,14781   ,96,96,96
BEGIN DESCRIPTION:
Mapping XS c060f840
END DESCRIPTION:
XS GIS Cut Line= 2
 3595556.5565245 10151216.0656853593910.3049593610149802.9017448
#Sta/Elev= 30
       0263.8962223.1161261.5801261.9189261.0408320.1231258.9043350.1102 258.457
370.1016258.8631380.0973258.4861 390.093257.0015420.0801 250.195440.0716 246.562
 460.063244.2033470.0587243.5179570.0157242.7458819.9084 242.432959.8483242.4715
1009.827243.08111289.707242.46051439.642251.72171479.625253.51371489.621254.7829
1499.616257.24781509.612258.83141529.604260.07031569.586261.34851589.578262.9151
1629.561 264.7711669.543266.09151719.522266.28631739.513266.91921829.475266.5051
#Mann= 3 , 0 , 0
       0     .05       0370.1016    .035       01509.612     .05       0
Bank Sta=370.1016,1509.612
XS Rating Curve= 0 ,0
Exp/Cntr=0.3,0.1

Type RM Length L Ch R = 1 ,14685   ,142,142,142
BEGIN DESCRIPTION:
Mapping XS 8d67aeb3
END DESCRIPTION:
XS GIS Cut Line= 4
      3591992.89     10148130.42      3591885.54     10147539.62
       3591866.2      10147474.4      3591678.43     10146415.83
#Sta/Elev= 30
  4381.3  262.15  4442.1  261.94  4491.9  261.35  4532.5   259.3    4563  258.92
  4696.8  258.82    4769   259.7  4803.5  260.01  4808.6  259.43    4995  261.36
  5072.9  261.55  5173.4   261.3  5281.6  260.17  5429.6  259.56  5475.1  259.26
  5519.8  258.84  5557.6  256.57    5598  255.23  5600.8  254.73    5604  255.23
    5662   256.9  5743.2   262.3  5804.2  265.16  5865.1  266.68    5902  266.43
  5907.1  267.29  6039.2  267.08  6074.3  266.49  6079.3     267  6124.9   265.8
#Mann= 12 ,-1 , 0
  4381.3      .1       0  4442.1     .05       0    4769     .16       0
    4995     .05       0  5072.9     .16       0  5173.4     .12       0
  5281.6     .16       0  5429.6     .05       0  5475.1      .1       0
    5598    .033       0    5604      .1       0  6039.2     .16       0
Bank Sta=5598,5604
XS Rating Curve= 0 ,0
Exp/Cntr=0.3,0.1

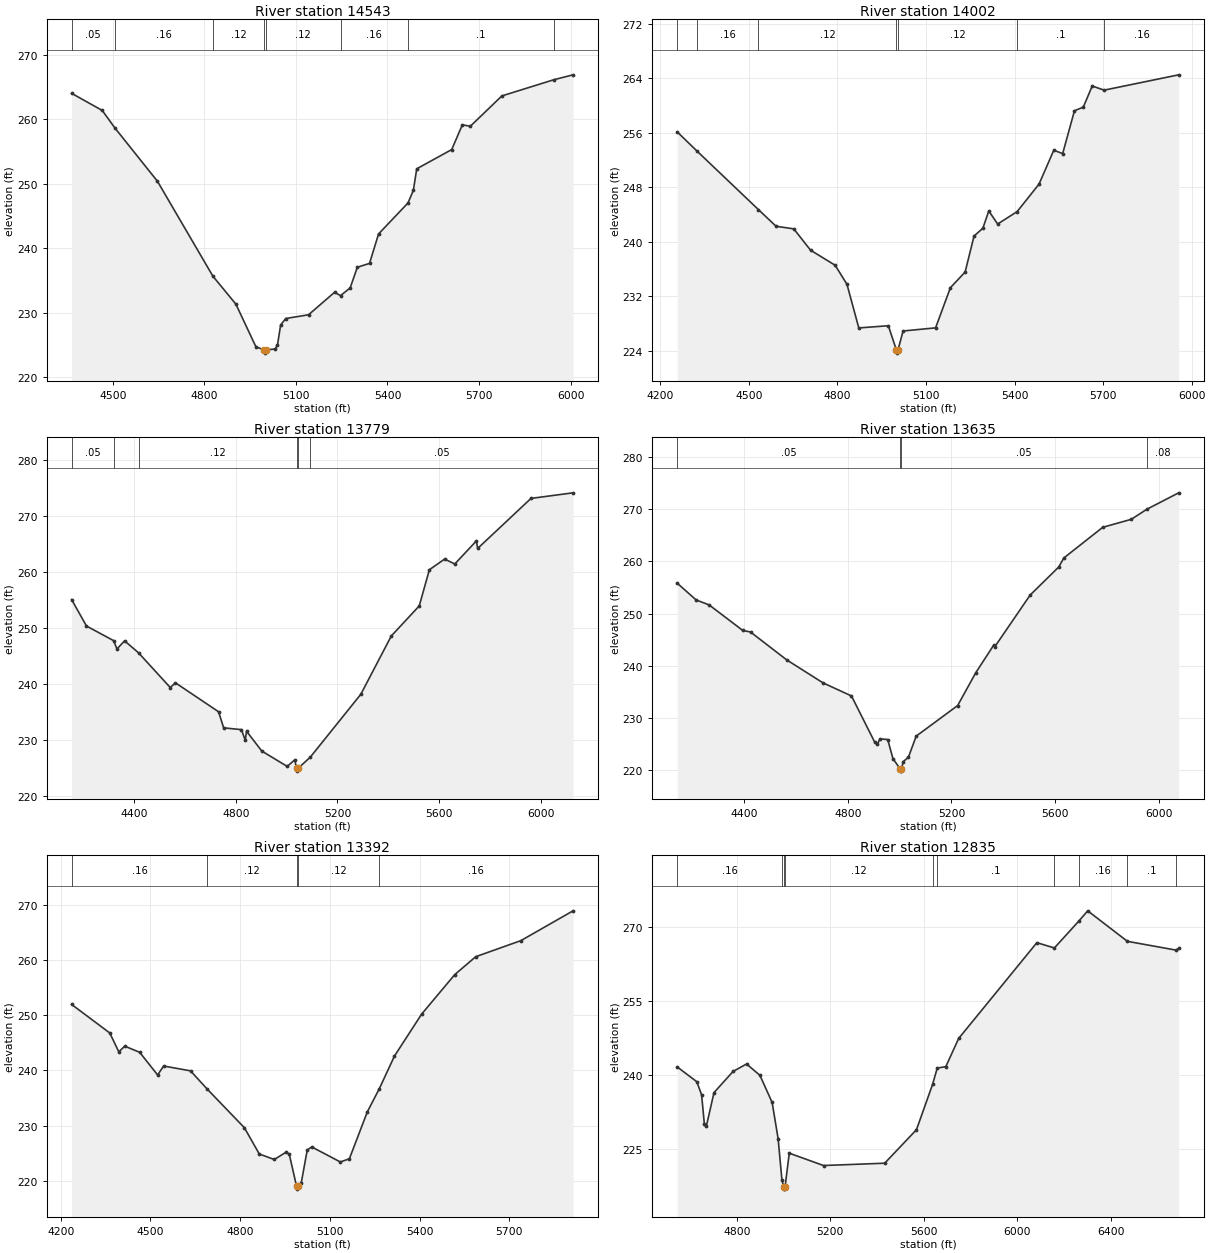
Type RM Length L Ch R = 1 ,14543   ,541,541,541
BEGIN DESCRIPTION:
Mapping XS ca6a19ff
END DESCRIPTION:
XS GIS Cut Line= 4
      3592071.12     10148091.33      3592002.92     10147522.14
      3592008.12     10147435.34      3591752.89     10146486.59
#Sta/Elev= 30
  4365.2  264.01  4465.6  261.35  4506.8  258.65  4646.5  250.36  4828.1  235.64
  4903.5   231.3    4969  224.69  4996.1  224.21  4998.8  223.71  5002.1  224.21
  5031.9  224.35  5039.6  224.97    5050  228.07  5066.7  229.08  5141.4  229.66
  5226.5  233.14  5246.3  232.63  5277.8  233.83  5301.2  237.03  5341.2  237.63
  5370.8   242.2  5467.3  247.01  5484.9  248.98  5495.8   252.3  5610.5  255.29
  5645.3  259.13  5671.3   258.9  5774.8  263.61    5945  266.12  6007.9  266.88
#Mann= 8 ,-1 , 0
  4365.2     .05       0  4506.8     .16       0  4828.1     .12       0
  4996.1     .07       0  5002.1     .12       0  5246.3     .16       0
  5467.3      .1       0    5945     .16       0
Bank Sta=4996.1,5002.1
XS Rating Curve= 0 ,0
Exp/Cntr=0.3,0.1

Type RM Length L Ch R = 1 ,14002   ,223,223,223
BEGIN DESCRIPTION:
CLIFTY CREEK 31.0
END DESCRIPTION:
XS GIS Cut Line= 3
      3592455.98     10147936.12      3592416.92     10146998.62
      3592451.64     10146239.03
#Sta/Elev= 30
  4257.4  256.11  4325.5  253.25  4532.6   244.7  4592.2  242.26  4652.2  241.88
    4709  238.75  4792.3  236.54  4832.4  233.74  4872.4  227.34  4972.5  227.66
  4999.5  224.14  5002.3  223.64  5005.5  224.14  5022.5  226.89  5132.6  227.35
  5182.7  233.24  5232.7  235.55  5262.8  240.82  5292.8  241.98  5312.8  244.51
  5342.8  242.59  5408.8  244.41    5483  248.45    5533  253.42  5563.1  252.93
  5603.1  259.22    5633  259.75  5663.2  262.85  5703.5  262.24  5956.1  264.49
#Mann= 7 ,-1 , 0
  4257.4     .05       0  4325.5     .16       0  4532.6     .12       0
  4999.5     .07       0  5005.5     .12       0  5408.8      .1       0
  5703.5     .16       0
Bank Sta=4999.5,5005.5
XS Rating Curve= 0 ,0
Exp/Cntr=0.3,0.1

Type RM Length L Ch R = 1 ,13779   ,144,144,144
BEGIN DESCRIPTION:
Mapping XS 7d4c196d
END DESCRIPTION:
XS GIS Cut Line= 2
      3592629.59     10148040.25      3592651.29     10146066.07
#Sta/Elev= 30
  4153.6   255.1  4212.2  250.36  4318.8  247.75  4332.2  246.26  4362.2  247.71
    4417  245.57  4542.2  239.34  4562.2   240.2  4732.2  235.01  4752.2  232.13
  4822.3  231.81  4837.3  229.89  4842.3  231.53  4902.3  227.98  5002.3  225.23
  5032.3   226.4  5039.3  224.88    5042  224.38  5045.3  224.88  5093.3  226.88
  5292.3  238.14  5412.3  248.58  5522.3  253.96  5562.3  260.44  5622.3  262.35
  5662.3  261.47  5747.3   265.6  5752.3  264.25  5962.3  273.21  6127.9  274.21
#Mann= 6 ,-1 , 0
  4153.6     .05       0  4318.8     .16       0    4417     .12       0
  5039.3     .07       0  5045.3     .12       0  5093.3     .05       0
Bank Sta=5039.3,5045.3
XS Rating Curve= 0 ,0
Exp/Cntr=0.3,0.1

Type RM Length L Ch R = 1 ,13635   ,243,243,243
BEGIN DESCRIPTION:
Mapping XS b87412b7
END DESCRIPTION:
XS GIS Cut Line= 3
      3592768.28     10148024.61      3592779.09     10146980.27
      3592818.67     10146088.65
#Sta/Elev= 30
    4141  255.83    4214  252.61    4264  251.67    4394  246.77    4424  246.47
    4564  241.12    4704  236.72    4814  234.21    4904  225.33    4914  224.92
    4924  225.98    4954  225.86    4974  222.22    5001   220.3  5003.8   219.8
    5007   220.3    5014  221.62    5034  222.47    5064  226.51  5224.1  232.37
  5294.1  238.66  5362.7   243.9  5367.7  243.65  5504.3  253.56  5614.4  258.92
  5634.5  260.67  5784.6  266.54  5894.7  268.07  5955.3  270.01  6077.9  273.15
#Mann= 4 ,-1 , 0
    4141     .05       0    5001     .04       0    5007     .05       0
  5955.3     .08       0
Bank Sta=5001,5007
XS Rating Curve= 0 ,0
Exp/Cntr=0.3,0.1

Type RM Length L Ch R = 1 ,13392   ,557,557,557
BEGIN DESCRIPTION:
CLIFTY CREEK 29.0
END DESCRIPTION:
XS GIS Cut Line= 3
      3593002.86     10147849.32      3592992.11     10147091.64
      3592890.01     10146178.28
#Sta/Elev= 30
  4236.5  251.96  4364.2  246.78  4394.2  243.37  4414.2   244.4  4464.2  243.28
  4524.2  239.17  4544.2   240.8  4634.2  239.92  4690.6  236.58  4814.2  229.62
  4864.2  224.85  4914.2  223.86  4954.2   225.2  4964.2  224.84  4988.8  218.99
  4991.5  218.49  4994.8  218.99  5004.3  219.58  5024.4  225.57  5039.4  226.14
  5135.1  223.41  5165.3  223.99  5225.7  232.53  5265.3  236.67  5316.2  242.61
  5406.8  250.19  5517.5  257.35  5587.9  260.61  5738.9  263.52  5913.3  268.92
#Mann= 5 ,-1 , 0
  4236.5     .16       0  4690.6     .12       0  4988.8     .07       0
  4994.8     .12       0  5265.3     .16       0
Bank Sta=4988.8,4994.8
XS Rating Curve= 0 ,0
Exp/Cntr=0.3,0.1

Type RM Length L Ch R = 1 ,12835   ,1169,1169,1169
BEGIN DESCRIPTION:
CLIFTY CREEK 27.0
END DESCRIPTION:
XS GIS Cut Line= 3
      3593624.39     10147572.86       3593574.4     10147372.89
      3592994.96     10145519.79
#Sta/Elev= 30
  4544.3  241.67    4628  238.68  4648.6  236.03  4660.4  230.15  4669.2  229.73
  4701.7  236.47  4783.2  240.75  4841.3  242.27  4898.4  239.97  4950.8  234.47
  4976.4  227.13  4992.6  218.82  5000.2  217.42  5002.9  216.92  5006.2  217.42
  5024.1   224.2  5170.8   221.7  5432.8  222.17    5569  228.96  5638.3  238.18
    5658  241.44  5694.7  241.73  5749.5  247.43  6084.6  266.84  6159.6  265.77
  6263.9  271.19  6302.4  273.29  6472.5  267.11    6681  265.33    6692  265.67
#Mann= 10 ,-1 , 0
  4544.3     .16       0  4992.6     .12       0  5000.2     .07       0
  5006.2     .12       0  5638.3     .16       0    5658      .1       0
  6159.6     .05       0  6263.9     .16       0  6472.5      .1       0
    6681     .16       0
Bank Sta=5000.2,5006.2
XS Rating Curve= 0 ,0
Exp/Cntr=0.3,0.1

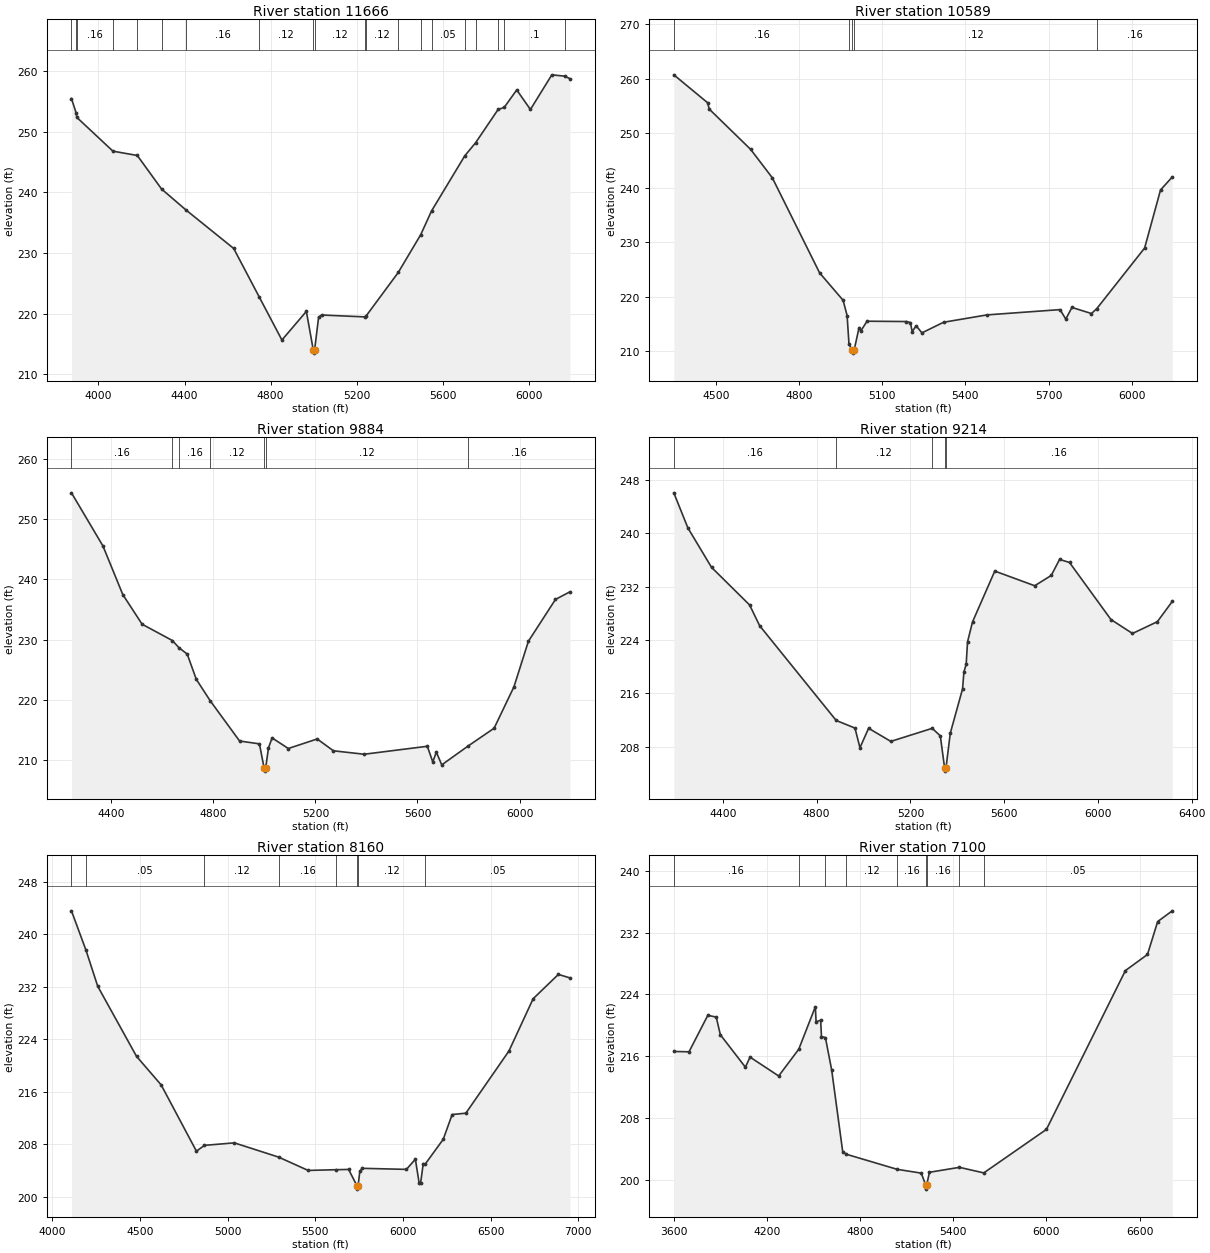
Type RM Length L Ch R = 1 ,11666   ,1077,1077,1077
BEGIN DESCRIPTION:
CLIFTY CREEK 25.0
END DESCRIPTION:
XS GIS Cut Line= 3
      3595125.15     10147123.99      3594286.64     10146608.38
      3593291.86     10145722.97
#Sta/Elev= 30
  3874.5  255.46  3896.4  253.08  3899.5  252.35  4067.3  246.79  4180.4  246.08
  4293.5  240.54  4406.6   237.1  4628.3  230.76    4746  222.83  4852.4  215.67
    4966  220.39  4998.2  214.01  5000.9  213.51  5004.2  214.01  5022.9  219.44
  5037.1  219.79  5238.2  219.48  5242.1  219.56  5392.9   226.8  5497.4  233.03
  5547.5  236.93  5702.2  246.03  5752.7  248.19  5856.9  253.66    5885  253.99
  5943.5  256.88  6007.1  253.66  6106.6  259.37  6166.3  259.15  6190.6  258.74
#Mann= 20 ,-1 , 0
  3874.5     .16       0  3896.4      .1       0  3899.5     .16       0
  4067.3      .1       0  4180.4     .12       0  4293.5     .05       0
  4406.6     .16       0    4746     .12       0  4998.2     .07       0
  5004.2     .12       0  5238.2     .05       0  5242.1     .12       0
  5392.9     .05       0  5497.4     .16       0  5547.5     .05       0
  5702.2     .16       0  5752.7      .1       0  5856.9     .16       0
    5885      .1       0  6166.3     .16       0
Bank Sta=4998.2,5004.2
XS Rating Curve= 0 ,0
Exp/Cntr=0.3,0.1

Type RM Length L Ch R = 1 ,10589   ,705,705,705
BEGIN DESCRIPTION:
CLIFTY CREEK 23.0
END DESCRIPTION:
XS GIS Cut Line= 3
      3595476.49     10146688.52      3595176.48     10146338.52
      3594142.12     10145491.66
#Sta/Elev= 30
  4348.6  260.71  4470.1   255.6  4476.7   254.4  4625.9  247.01  4703.9   241.8
  4874.5  224.34  4959.2  219.31  4973.6  216.51  4980.5   211.2  4992.8  210.11
  4995.6  209.61  4998.8  210.11  5016.7   214.3  5023.1  213.68  5045.4  215.47
  5187.5  215.41  5201.8  215.22  5208.3  213.56  5222.7  214.63  5243.5  213.33
  5321.7  215.28  5478.2  216.63  5741.6   217.6  5762.4  215.86  5784.5     218
    5855  216.88  5874.4   217.8  6046.7  228.91  6104.1  239.58  6146.4  241.95
#Mann= 5 ,-1 , 0
  4348.6     .16       0  4980.5     .12       0  4992.8     .07       0
  4998.8     .12       0  5874.4     .16       0
Bank Sta=4992.8,4998.8
XS Rating Curve= 0 ,0
Exp/Cntr=0.3,0.1

Type RM Length L Ch R = 1 ,9884    ,670,670,670
BEGIN DESCRIPTION:
CLIFTY CREEK 21.0
END DESCRIPTION:
XS GIS Cut Line= 3
      3595802.51     10146271.83      3595702.52     10146021.85
      3594526.64     10144817.13
#Sta/Elev= 30
  4244.4  254.34  4367.6  245.54  4445.6  237.47  4521.2  232.56  4639.6  229.86
  4665.2  228.68  4697.9  227.61  4733.3  223.44  4787.8  219.88  4903.1   213.2
  4980.8  212.73  4999.1  208.71  5001.8  208.21  5005.1  208.71  5016.2  212.06
  5030.4  213.72  5093.9  211.96  5207.1  213.54  5270.7  211.58    5391  211.01
  5638.5  212.33  5659.8  209.74  5673.8  211.36    5695  209.25  5798.5  212.38
  5900.1  215.32  5977.9  222.19  6034.5  229.74  6140.5  236.67  6197.1  237.93
#Mann= 7 ,-1 , 0
  4244.4     .16       0  4639.6     .12       0  4665.2     .16       0
  4787.8     .12       0  4999.1     .07       0  5005.1     .12       0
  5798.5     .16       0
Bank Sta=4999.1,5005.1
XS Rating Curve= 0 ,0
Exp/Cntr=0.3,0.1

Type RM Length L Ch R = 1 ,9214    ,1054,1054,1054
BEGIN DESCRIPTION:
CLIFTY CREEK 19.0
END DESCRIPTION:
XS GIS Cut Line= 3
      3596208.53     10145967.78      3595492.11     10144791.64
      3594956.93     10144266.86
#Sta/Elev= 30
  4190.6  246.08  4250.7  240.81  4351.5   234.9  4513.9  229.26  4556.7  226.15
  4883.4  211.93  4963.5  210.79  4984.8  207.84  5021.6  210.76  5116.5  208.79
  5293.1  210.75  5327.6  209.62  5345.9  204.83  5348.7  204.33  5351.9  204.83
  5370.2  210.02  5422.5  216.66  5428.3  219.19    5438  220.37  5443.8  223.73
  5465.1  226.72    5560  234.34  5730.4  232.14  5801.1  233.69  5836.4  236.09
  5878.9  235.63  6055.7  227.07  6147.6  224.98  6253.7  226.75  6317.3  229.79
#Mann= 5 ,-1 , 0
  4190.6     .16       0  4883.4     .12       0  5293.1     .16       0
  5345.9     .07       0  5351.9     .16       0
Bank Sta=5345.9,5351.9
XS Rating Curve= 0 ,0
Exp/Cntr=0.3,0.1

Type RM Length L Ch R = 1 ,8160    ,1060,1060,1060
BEGIN DESCRIPTION:
CLIFTY CREEK 17.0
END DESCRIPTION:
XS GIS Cut Line= 3
      3596656.43     10146040.71      3596765.81     10144926.09
      3595802.26     10143498.99
#Sta/Elev= 30
    4110  243.56  4192.8  237.56  4259.8  232.06  4480.8  221.39  4621.5  217.03
  4822.5  206.93  4868.1  207.82  5038.5   208.2    5291  206.03  5459.3     204
  5620.2  204.11  5690.1  204.15    5738  201.65  5740.7  201.15    5744  201.65
  5754.2  203.87    5768  204.32  6019.8  204.16  6070.8  205.71    6092  202.12
  6100.7  202.09  6115.7  205.05  6125.2  204.91  6229.6  208.74  6280.5  212.52
  6358.5  212.72  6604.3   222.2  6742.1  230.16    6886  233.87  6951.9  233.34
#Mann= 8 ,-1 , 0
    4110     .16       0  4192.8     .05       0  4868.1     .12       0
    5291     .16       0  5620.2     .12       0    5738     .07       0
    5744     .12       0  6125.2     .05       0
Bank Sta=5738,5744
XS Rating Curve= 0 ,0
Exp/Cntr=0.3,0.1

Type RM Length L Ch R = 1 ,7100    ,1500,1500,1500
BEGIN DESCRIPTION:
CLIFTY CREEK 15.0
END DESCRIPTION:
XS GIS Cut Line= 3
      3597771.02     10146118.81      3597656.43     10145207.34
      3596990.08     10143015.64
#Sta/Elev= 30
  3601.6  216.62  3699.5  216.58  3820.5   221.3  3874.7  221.07  3901.1  218.79
  4062.4  214.59  4092.6  215.89  4276.7  213.45    4406  216.91  4512.9  222.41
  4517.6  220.46  4547.1  220.66  4552.3  218.55  4577.7  218.42  4618.1  214.21
    4689  203.66  4712.9  203.32    5040  201.37  5195.1  200.88  5223.5  199.31
  5226.2  198.81  5229.5  199.31  5247.4  200.99  5440.8  201.63  5597.4  200.91
  6000.7  206.54  6509.3  227.09  6651.3  229.17    6717  233.43    6811  234.82
#Mann= 9 ,-1 , 0
  3601.6     .16       0    4406      .1       0  4577.7     .16       0
  4712.9     .12       0    5040     .16       0  5223.5     .07       0
  5229.5     .16       0  5440.8      .1       0  5597.4     .05       0
Bank Sta=5223.5,5229.5
XS Rating Curve= 0 ,0
Exp/Cntr=0.3,0.1

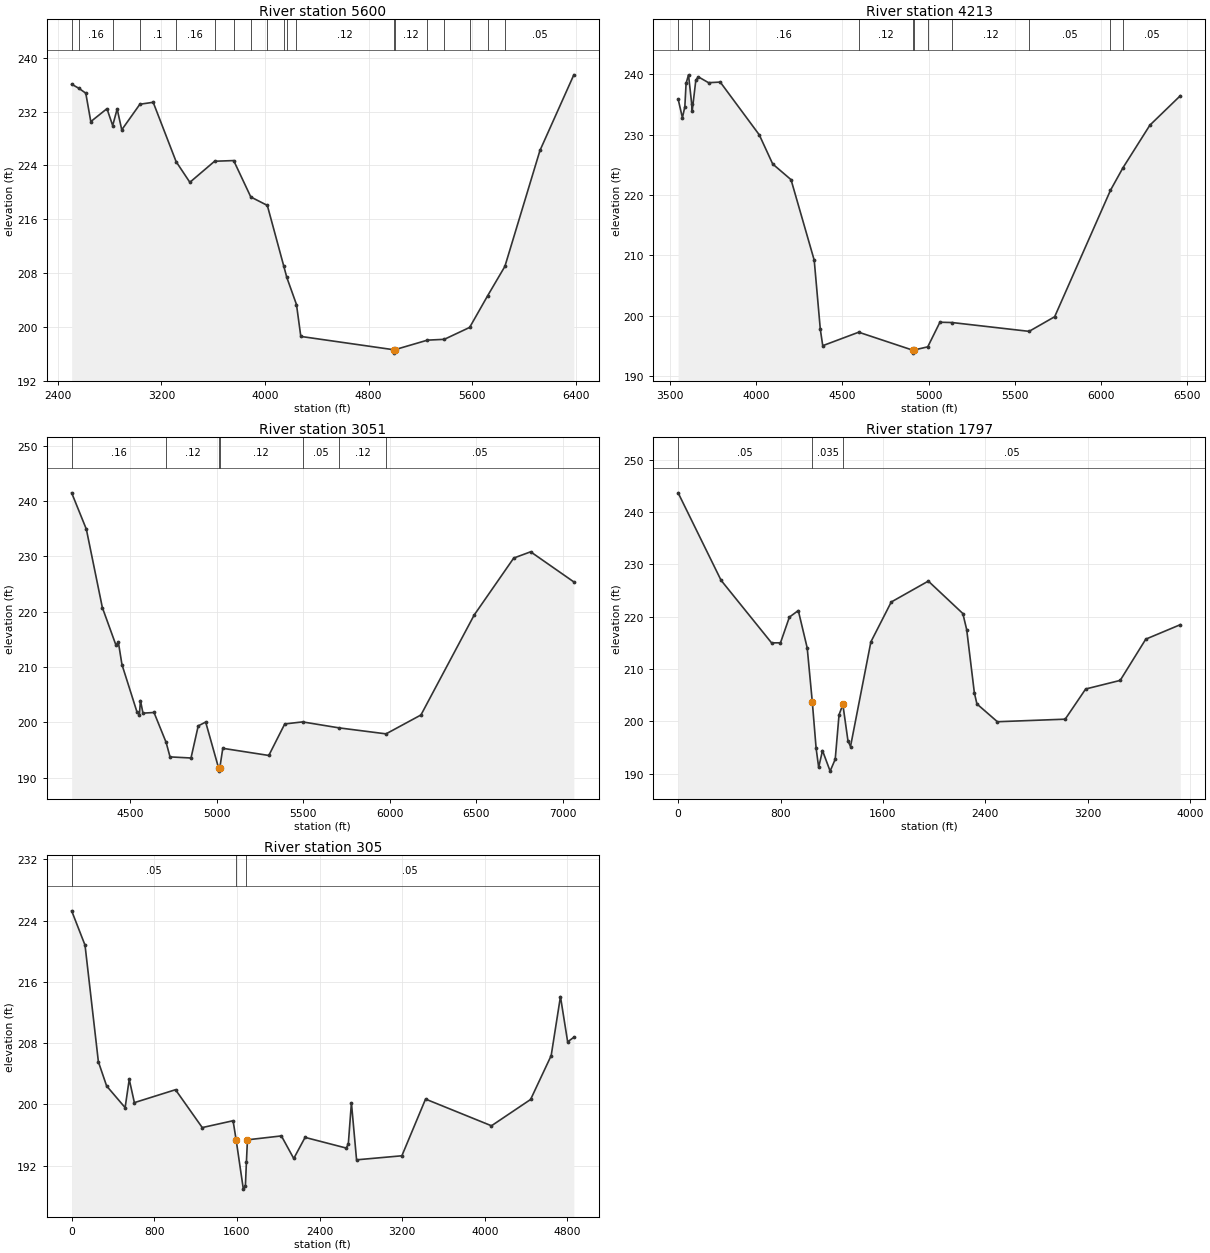
Type RM Length L Ch R = 1 ,5600    ,1387,1387,1387
BEGIN DESCRIPTION:
CLIFTY CREEK 12.0
END DESCRIPTION:
XS GIS Cut Line= 3
      3599646.03     10146139.67      3599104.35     10144738.59
      3597342.13     10143141.67
#Sta/Elev= 30
  2505.8  236.08  2563.9  235.44    2615  234.74  2653.8  230.52  2778.6  232.44
  2822.9  229.93  2857.5   232.4    2893   229.3    3033   233.1  3135.8  233.39
    3313  224.57  3419.2   221.5  3610.2  224.63  3757.8  224.73  3890.2  219.32
  4017.7  218.07  4144.1   209.1  4168.4  207.36    4243  203.34  4276.5   198.6
  4995.3  196.62  4998.1  196.12  5001.3  196.62  5255.1  198.05  5385.1  198.17
    5581  199.94  5719.9  204.64  5853.4  209.01  6124.3  226.23  6386.1  237.47
#Mann= 19 ,-1 , 0
  2505.8      .1       0  2563.9     .16       0  2822.9     .05       0
    3033      .1       0    3313     .16       0  3610.2      .1       0
  3757.8     .16       0  3890.2      .1       0  4017.7     .16       0
  4144.1      .1       0  4168.4     .16       0    4243     .12       0
  4995.3     .07       0  5001.3     .12       0  5255.1     .05       0
  5385.1     .16       0    5581     .05       0  5719.9      .1       0
  5853.4     .05       0
Bank Sta=4995.3,5001.3
XS Rating Curve= 0 ,0
Exp/Cntr=0.3,0.1

Type RM Length L Ch R = 1 ,4213    ,1162,1162,1162
BEGIN DESCRIPTION:
CLIFTY CREEK 9.0
END DESCRIPTION:
XS GIS Cut Line= 3
       3600213.7     10144655.22      3599192.11     10143641.64
      3598172.05     10142582.32
#Sta/Elev= 30
  3548.7  235.88  3573.6  232.77  3587.7  234.59  3594.8  238.44  3608.9  239.87
  3627.5  235.04  3630.1  233.83  3651.3  238.98  3665.5  239.54    3725  238.57
  3792.8  238.67    4019  229.94  4096.8  225.12  4202.9  222.53  4337.3  209.21
  4372.6  197.77  4386.7  195.07    4595   197.3    4907  194.34  4909.8  193.84
    4913  194.34  4995.1  194.88  5065.6  198.95  5135.9   198.9  5582.3  197.44
  5730.4  199.86  6053.9  220.78  6126.2   224.5    6282  231.54  6458.4  236.41
#Mann= 11 ,-1 , 0
  3548.7     .16       0  3627.5     .05       0    3725     .16       0
    4595     .12       0    4907     .03       0    4913     .12       0
  4995.1     .05       0  5135.9     .12       0  5582.3     .05       0
  6053.9     .16       0  6126.2     .05       0
Bank Sta=4907,4913
XS Rating Curve= 0 ,0
Exp/Cntr=0.3,0.1

Type RM Length L Ch R = 1 ,3051    ,1254,1254,1254
BEGIN DESCRIPTION:
CLIFTY CREEK 8.0
END DESCRIPTION:
XS GIS Cut Line= 3
      3600678.98     10143974.67      3600078.22     10143244.42
      3598298.07     10142434.12
#Sta/Elev= 30
  4161.7  241.47  4246.6   234.9  4339.1  220.75  4417.3  213.99  4431.7  214.47
  4452.5  210.44  4538.5  201.96  4552.9  201.37  4559.4  203.95  4573.7  201.68
  4637.6   201.8  4707.4  196.41  4730.1  193.78  4851.3  193.58    4893  199.38
    4936  200.07  5011.2  191.71    5014  191.21  5017.2  191.71    5035  195.33
  5300.8  194.04  5392.9  199.73  5496.1   200.1  5707.1  199.02  5978.1  197.94
  6179.8  201.35  6487.4   219.4  6715.9  229.69  6813.6  230.82  7063.2  225.38
#Mann= 7 ,-1 , 0
  4161.7     .16       0  4707.4     .12       0  5011.2     .07       0
  5017.2     .12       0  5496.1     .05       0  5707.1     .12       0
  5978.1     .05       0
Bank Sta=5011.2,5017.2
XS Rating Curve= 0 ,0
Exp/Cntr=0.3,0.1

Type RM Length L Ch R = 1 ,1797    ,1492,1492,1492
XS GIS Cut Line= 5
     3601563.775    10143921.401     3601476.969    10143200.915
     3600747.802    10142554.214     3598542.941    10142311.158
3598542.9407573310142311.1579732
#Sta/Elev= 30
       0243.6617335.4081 226.948730.0058214.9836799.6224214.9959869.2389219.9082
938.8555221.16151008.472214.00771048.253203.67921078.089194.81391097.979191.1857
1127.815   194.41187.486190.46921227.267192.74841257.103201.24791286.938203.2082
1326.719196.26761346.609195.16691505.733 215.1711664.857222.79331954.437226.7898
 2224.22220.58842254.196217.51392314.148205.43682334.132203.31012494.003199.9102
3023.577200.39843183.449206.16613453.232207.81053653.072 215.6933922.855218.4598
#Mann= 3 , 0 , 0
       0     .05       01048.253    .035       01286.938     .05       0
Bank Sta=1048.253,1286.938
XS Rating Curve= 0 ,0
Exp/Cntr=0.3,0.1

Type RM Length L Ch R = 1 ,305     ,0,0,0
XS GIS Cut Line= 5
      3601806.83    10143239.978     3601980.441    10141851.089
     3601568.115    10141738.242     3598577.664    10142206.992
3598577.6635176110142206.9920756
#Sta/Elev= 30
       0225.2825129.4472220.8007258.8944205.5747338.5543202.4205517.7889199.5874
557.6188203.2813607.4061200.24221005.705201.9278  1264.6196.9854 1563.07 197.879
1592.895195.37351662.487188.9494 1682.37189.34971692.312192.48751702.253195.3871
2030.919195.89672150.574192.94882260.257195.70392659.106194.31072679.049194.8552
2708.963200.22432758.819192.77473197.553193.30313426.891200.7052 4065.05197.2198
4443.957200.65284643.381206.38474733.123214.08924802.921208.17614862.749208.7778
#Mann= 3 ,-1 , 0
       0     .05       01592.895    .035       01692.312     .05       0
Bank Sta=1592.895,1702.253
XS Rating Curve= 0 ,0
Exp/Cntr=0.3,0.1

Chan Stop Cuts=-1
Use User Specified Reach Order=0
Composite Channel Slope=5