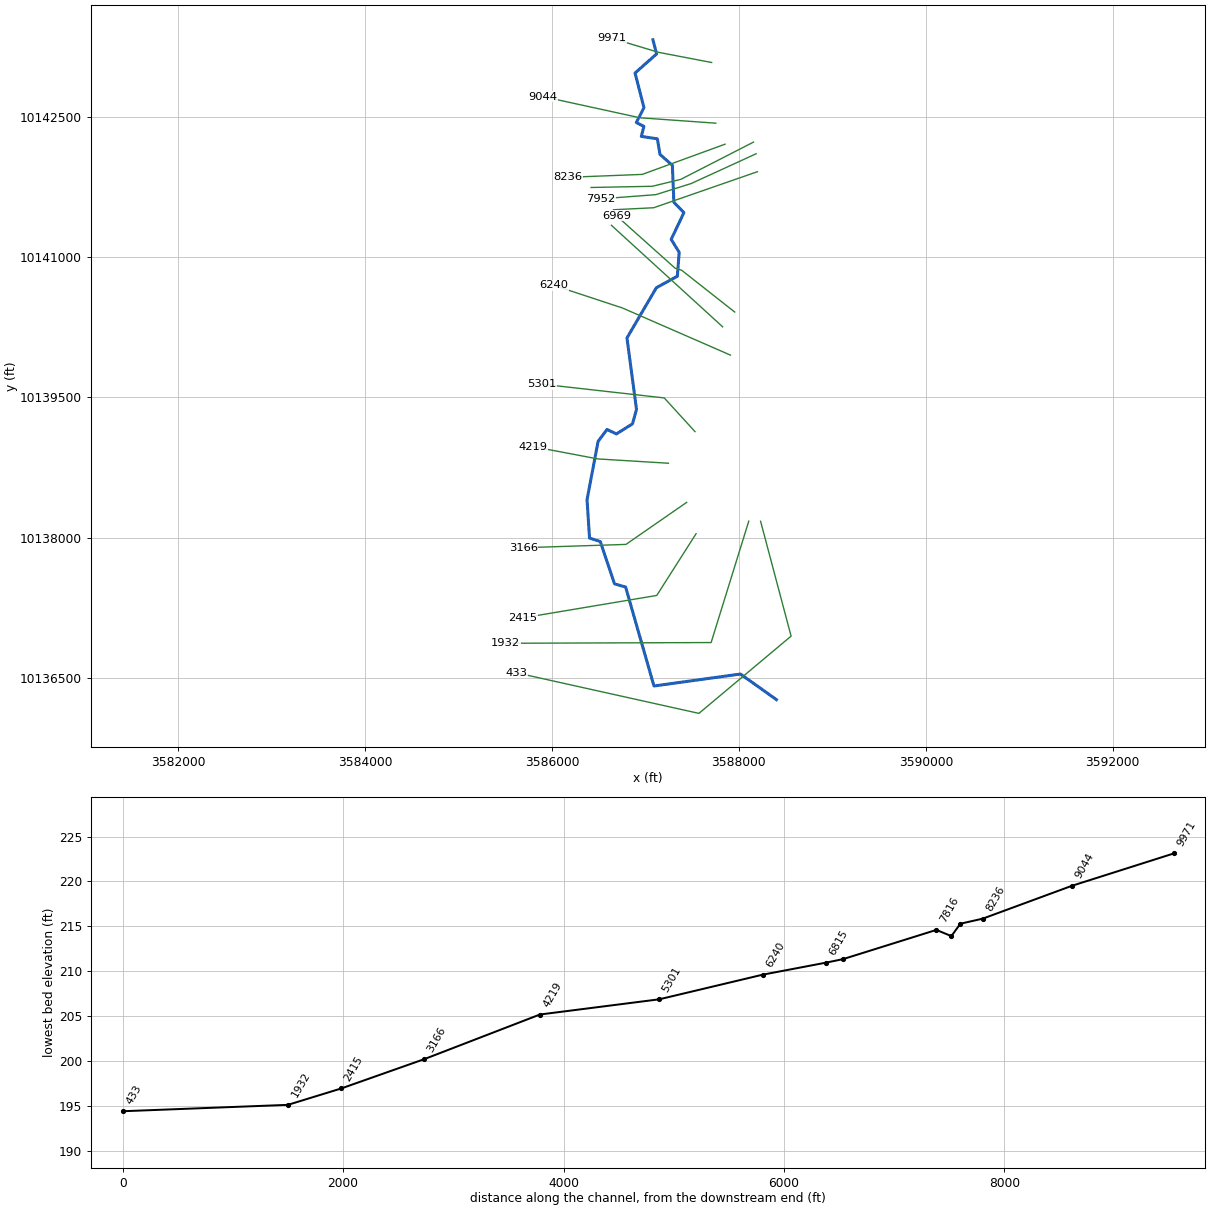
--- FRANKS CREEK TRIB 1.prj (project) ---

Proj Title=FRANKS CREEK TRIB 1 Base Level Engineering
Current Plan=p01
Default Exp/Contr=0.3,0.1
English Units
Geom File=g01
Flow File=f01
Plan File=p01
Y Axis Title=Elevation
X Axis Title(PF)=Main Channel Distance
X Axis Title(XS)=Station
BEGIN DESCRIPTION:
FRANKS CREEK TRIB 1
END DESCRIPTION:
DSS Export Rating Curves= 0
DSS Export Rating Curve Sorted= 0
DSS Export Volume Flow Curves= 0
DXF OffsetX= 0
DXF OffsetY= 0
DXF ScaleX= 1
DXF ScaleY= 10

--- FRANKS CREEK TRIB 1.p01 (plan) ---

Plan Title=Multiple Run
Short Identifier=Multiple
Geom File=g01
Flow File=f01
Subcritical Flow
K Sum by GR= 0
Std Step Tol= 0.01
Critical Tol= 0.01
Num of Std Step Trials= 20
Max Error Tol= 0.3
Flow Tol Ratio= 0.001
Split Flow NTrial= 30
Split Flow Tol= 0.02
Split Flow Ratio= 0.02
Log Output Level= 0
Friction Slope Method= 1
Unsteady Friction Slope Method= 2
Unsteady Bridges Friction Slope Method= 1
Parabolic Critical Depth
Global Vel Dist=  1 , 1 , 1
Global Log Level= 0
CheckData=True
Encroach Param= -1, 0, 0, 0
BEGIN DESCRIPTION:
Multiple Run
END DESCRIPTION:

--- FRANKS CREEK TRIB 1.f01 (steady flow) ---

Flow Title=Multiple
Program Version=4.10
Number of Profiles= 7
Profile Names=10-year,25-year,50-year,1pct_min,100-year,1pct_plu,500-year
River Rch & RM=FRANKS CREEK TRI,Reach-1         ,9971
     561     754     911     807    1091    1475    1568
River Rch & RM=FRANKS CREEK TRI,Reach-1         ,9044
     824    1125    1373    1226    1658    2242    2424
Boundary for River Rch & Prof#=FRANKS CREEK TRI,Reach-1         , 1
Up Type= 0
Dn Type= 1
Dn Known WS=196.63
Boundary for River Rch & Prof#=FRANKS CREEK TRI,Reach-1         , 2
Up Type= 0
Dn Type= 1
Dn Known WS=197.57
Boundary for River Rch & Prof#=FRANKS CREEK TRI,Reach-1         , 3
Up Type= 0
Dn Type= 1
Dn Known WS=198.03
Boundary for River Rch & Prof#=FRANKS CREEK TRI,Reach-1         , 4
Up Type= 0
Dn Type= 1
Dn Known WS=197.83
Boundary for River Rch & Prof#=FRANKS CREEK TRI,Reach-1         , 5
Up Type= 0
Dn Type= 1
Dn Known WS=198.48
Boundary for River Rch & Prof#=FRANKS CREEK TRI,Reach-1         , 6
Up Type= 0
Dn Type= 1
Dn Known WS=199.24
Boundary for River Rch & Prof#=FRANKS CREEK TRI,Reach-1         , 7
Up Type= 0
Dn Type= 1
Dn Known WS=199.57
DSS Import GetInterval= 0
DSS Import GetPeak= 0
DSS Import FillOption= 0

--- FRANKS CREEK TRIB 1.g01 (geometry) ---

Geom Title=Existing Conditions
Program Version=4.10

River Reach=FRANKS CREEK TRI,Reach-1
Reach XY= 30
      3587080.24      10143326.2      3587119.97     10143175.02
      3586889.08     10142970.47      3586984.56     10142599.81
      3586902.97     10142440.96       3586983.7     10142399.29
      3586955.92     10142292.52      3587127.79     10142266.48
      3587155.57     10142100.68      3587288.38     10141982.63
      3587304.48      10141588.1      3587411.91     10141476.45
      3587275.88     10141190.98      3587361.34     10141051.84
      3587341.71     10140796.18      3587117.19     10140673.47
      3586802.73     10140136.26      3586904.72     10139371.45
      3586862.08     10139217.54      3586689.44     10139108.95
      3586589.62       10139157.      3586493.93     10139030.36
      3586375.47     10138405.97      3586402.16     10137995.18
      3586516.74     10137957.85      3586669.88     10137504.89
      3586788.36     10137470.64      3587091.48     10136412.29
      3588016.74     10136540.31      3588401.52     10136266.52

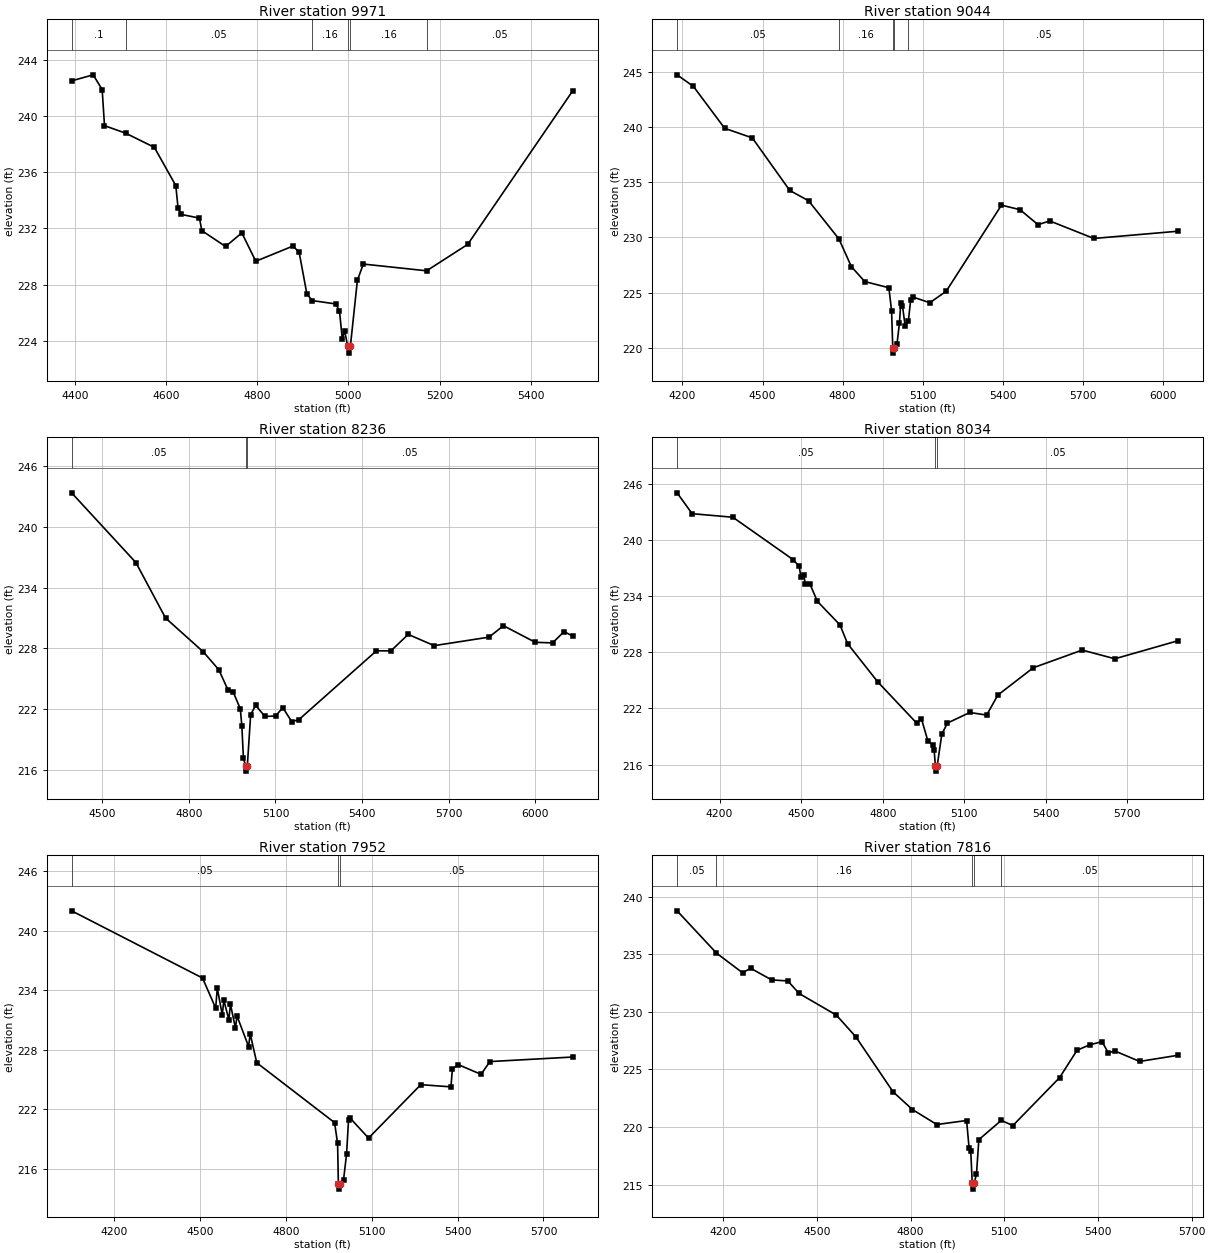
Type RM Length L Ch R = 1 ,9971    ,927,927,927
BEGIN DESCRIPTION:
FRANKS CREEK TRIB 1 16.0
END DESCRIPTION:
XS GIS Cut Line= 3
      3587708.58      10143083.2      3587142.11     10143191.64
      3586642.08     10143341.65
#Sta/Elev= 30
  4393.2   242.5  4440.5  242.93  4460.2  241.88  4465.3  239.31  4511.4  238.78
  4574.5  237.77  4621.5  235.05  4626.6  233.45    4634  232.99  4673.5  232.73
  4678.6  231.84  4730.7  230.71  4766.3  231.68  4796.9  229.66  4878.3  230.74
  4891.9  230.31  4908.9  227.33  4920.7  226.86  4972.6  226.62  4980.4  226.11
  4986.5  224.14  4991.7  224.71  4998.3  223.62    5001  223.12  5004.3  223.62
  5019.6   228.3  5032.6  229.46  5171.4  228.98  5261.4  230.86    5492  241.81
#Mann= 6 ,-1 , 0
  4393.2      .1       0  4511.4     .05       0  4920.7     .16       0
  4998.3     .07       0  5004.3     .16       0  5171.4     .05       0
Bank Sta=4998.3,5004.3
XS Rating Curve= 0 ,0
Exp/Cntr=0.3,0.1

Type RM Length L Ch R = 1 ,9044    ,808,808,808
BEGIN DESCRIPTION:
FRANKS CREEK TRIB 1 14.0
END DESCRIPTION:
XS GIS Cut Line= 3
      3587753.04     10142433.84      3586942.11     10142491.64
      3585902.86     10142718.48
#Sta/Elev= 30
  4180.1  244.75  4241.2   243.7  4358.3   239.9  4461.7  239.03  4602.1  234.26
  4672.3  233.33  4785.9  229.87  4832.7  227.35  4882.8     226    4973  225.44
  4983.1  223.35  4987.6  220.01  4990.3  219.51  4993.6  220.01  5003.3  220.32
  5012.5  222.22  5017.6  224.05  5023.8  223.81    5034  221.97  5045.9  222.39
  5054.5  224.32  5061.5  224.61  5126.2  224.08  5187.6  225.12  5394.5  232.93
  5463.9  232.52  5531.4  231.16  5575.3   231.5  5740.3  229.91  6056.8  230.57
#Mann= 5 ,-1 , 0
  4180.1     .05       0  4785.9     .16       0  4987.6     .07       0
  4993.6     .16       0  5045.9     .05       0
Bank Sta=4987.6,4993.6
XS Rating Curve= 0 ,0
Exp/Cntr=0.3,0.1

Type RM Length L Ch R = 1 ,8236    ,202,202,202
BEGIN DESCRIPTION:
Mapping XS 8442551d
END DESCRIPTION:
XS GIS Cut Line= 3
      3587851.45     10142208.77      3586966.02     10141885.85
      3586171.71      10141854.6
#Sta/Elev= 30
  4393.5  243.36  4616.3  236.47  4719.1  230.99  4850.5  227.63  4903.7  225.88
  4935.7  223.87  4952.9  223.72  4978.2  222.02  4983.5  220.34  4988.9  217.19
  4996.5  216.36  4999.3  215.86  5002.5  216.36  5014.1  221.45  5031.5  222.36
  5063.4  221.26  5100.4  221.31  5125.6  222.13  5156.2  220.76  5180.5  220.93
    5450  227.75    5500  227.74  5560.1  229.37  5650.1  228.26  5840.3   229.1
  5890.3  230.23  6000.4  228.59  6060.4  228.53  6100.5  229.65  6130.9  229.19
#Mann= 3 ,-1 , 0
  4393.5     .05       0  4996.5     .03       0  5002.5     .05       0
Bank Sta=4996.5,5002.5
XS Rating Curve= 0 ,0
Exp/Cntr=0.3,0.1

Type RM Length L Ch R = 1 ,8034    ,82,82,82
BEGIN DESCRIPTION:
FRANKS CREEK TRIB 1 13.0
END DESCRIPTION:
XS GIS Cut Line= 4
      3588156.75     10142231.67      3587378.15     10141832.65
      3587073.47     10141758.73      3586418.61     10141745.86
#Sta/Elev= 30
  4043.9  245.05  4099.2  242.82    4249  242.44    4471   237.9  4493.2  237.18
  4498.8  236.08  4509.8  236.25  4515.4  235.31    4532  235.33  4559.8  233.45
    4643  230.93  4670.8  228.93  4781.8  224.84    4925  220.43  4942.3  220.91
  4966.2  218.53  4984.1  218.09  4989.3  217.52    4994   215.8  4996.8   215.3
    5000   215.8  5017.6  219.27  5038.2  220.44  5120.5  221.57  5182.3  221.29
  5223.4  223.43  5353.7  226.35  5533.7  228.24  5653.8  227.31  5887.3  229.25
#Mann= 3 ,-1 , 0
  4043.9     .05       0    4994     .04       0    5000     .05       0
Bank Sta=4994,5000
XS Rating Curve= 0 ,0
Exp/Cntr=0.3,0.1

Type RM Length L Ch R = 1 ,7952    ,136,136,136
BEGIN DESCRIPTION:
Mapping XS 227ad5cf
END DESCRIPTION:
XS GIS Cut Line= 4
      3588184.53     10142106.68      3587490.38     10141788.41
      3587111.59     10141669.16      3586522.05     10141624.31
#Sta/Elev= 30
  4050.9     242  4508.5  235.22  4554.5  232.18    4560  234.21  4577.5   231.5
    4583  232.98  4600.5  231.01    4606  232.58  4623.5  230.16    4629  231.39
  4669.5  228.31    4675   229.6    4698  226.67    4970  220.63  4980.5  218.54
  4983.3  214.42  4986.1  213.92  4989.3  214.42  5001.4  214.88  5011.9  217.46
  5018.7  220.87  5023.9   221.1  5088.7  219.07  5271.3  224.46  5376.7  224.24
  5381.7  226.02  5401.7  226.49  5481.9   225.5  5512.8  226.79  5802.9  227.25
#Mann= 3 ,-1 , 0
  4050.9     .05       0  4983.3     .04       0  4989.3     .05       0
Bank Sta=4983.3,4989.3
XS Rating Curve= 0 ,0
Exp/Cntr=0.3,0.1

Type RM Length L Ch R = 1 ,7816    ,847,847,847
BEGIN DESCRIPTION:
Mapping XS ab768351
END DESCRIPTION:
XS GIS Cut Line= 3
      3588197.83     10141914.51      3587088.42     10141529.08
       3586658.1     10141507.76
#Sta/Elev= 30
  4052.2  238.78  4178.3  235.11  4261.8   233.4  4287.7  233.79  4355.2  232.78
  4406.8  232.69  4443.2   231.6  4562.4  229.72  4624.6  227.84  4743.8  223.06
    4806  221.52    4884  220.22  4979.3  220.57  4987.4  218.16  4992.7  217.93
  4997.4  215.11  5000.2  214.61  5003.4  215.11    5011  215.93  5018.6  218.91
  5090.4  220.58  5127.5  220.13    5277  224.29  5333.1  226.67  5373.1  227.14
  5413.2  227.42  5433.2  226.43  5453.2  226.62  5533.3   225.7  5657.5  226.24
#Mann= 5 ,-1 , 0
  4052.2     .05       0  4178.3     .16       0  4997.4     .07       0
  5003.4     .16       0  5090.4     .05       0
Bank Sta=4997.4,5003.4
XS Rating Curve= 0 ,0
Exp/Cntr=0.3,0.1

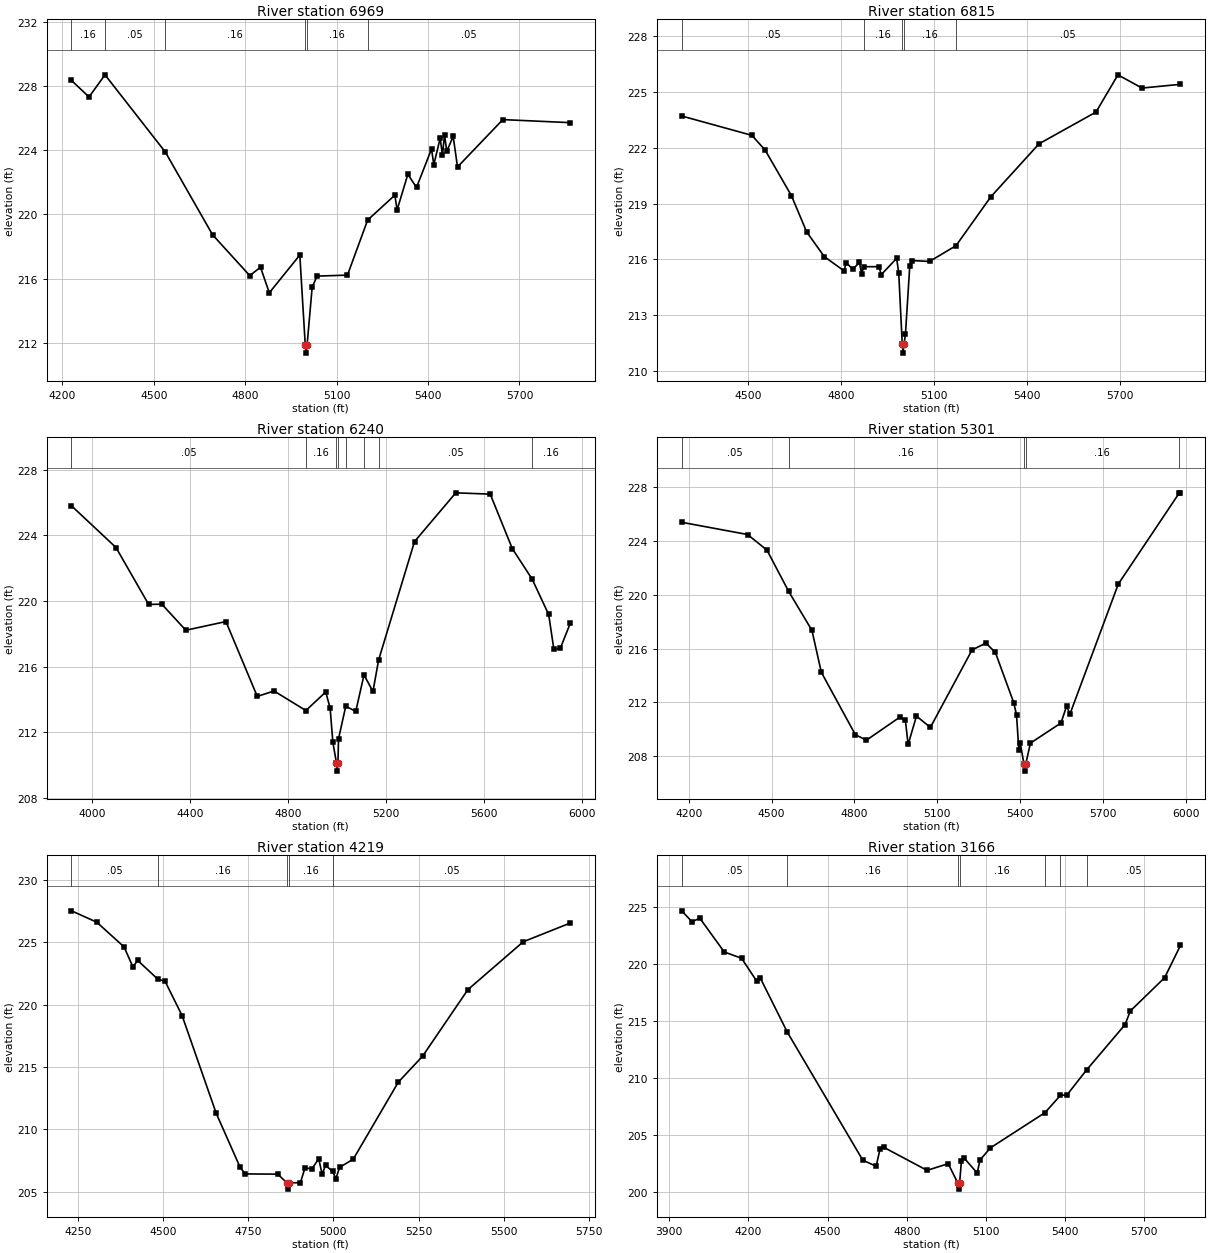
Type RM Length L Ch R = 1 ,6969    ,154,154,154
BEGIN DESCRIPTION:
FRANKS CREEK TRIB 1 12.0
END DESCRIPTION:
XS GIS Cut Line= 4
      3587955.22     10140413.35      3587386.94     10140861.17
      3587319.23     10140881.14      3586690.91     10141442.98
#Sta/Elev= 30
  4229.6  228.35  4287.1  227.32  4339.6   228.7  4537.6  223.89  4692.8  218.73
  4814.7  216.19    4850  216.71  4878.9  215.12    4979  217.47  4996.9  211.86
  4999.6  211.36  5002.9  211.86  5019.6  215.48    5036  216.16  5135.4  216.22
  5201.6  219.65  5290.9   221.2  5298.4  220.29  5333.6   222.5    5362  221.68
  5411.3  224.08  5418.8   223.1  5439.7  224.75  5447.2   223.7  5453.9  224.96
  5461.4  223.94  5482.4  224.86  5496.6  222.96  5645.4  225.91  5866.6  225.72
#Mann= 6 ,-1 , 0
  4229.6     .16       0  4339.6     .05       0  4537.6     .16       0
  4996.9     .07       0  5002.9     .16       0  5201.6     .05       0
Bank Sta=4996.9,5002.9
XS Rating Curve= 0 ,0
Exp/Cntr=0.3,0.1

Type RM Length L Ch R = 1 ,6815    ,575,575,575
BEGIN DESCRIPTION:
Mapping XS c3682782
END DESCRIPTION:
XS GIS Cut Line= 2
       3587826.3     10140255.25      3586636.23     10141341.23
#Sta/Elev= 30
  4285.1   223.7  4511.9  222.66  4554.5  221.87  4639.6  219.42  4688.9  217.47
  4745.7  216.15  4809.2  215.39  4816.6  215.83  4837.6  215.47  4859.2  215.84
  4865.9  215.24  4873.5  215.61  4922.7  215.61  4929.5  215.18  4979.4  216.06
  4986.2  215.25  4997.4  211.47  5000.1  210.97  5003.4  211.47  5007.8  211.99
  5021.8  215.65  5028.8  215.94  5085.5  215.89  5171.2  216.74  5283.5  219.36
  5439.5  222.21  5623.3  223.91  5694.2  225.91  5771.9   225.2  5896.2   225.4
#Mann= 5 ,-1 , 0
  4285.1     .05       0  4873.5     .16       0  4997.4     .07       0
  5003.4     .16       0  5171.2     .05       0
Bank Sta=4997.4,5003.4
XS Rating Curve= 0 ,0
Exp/Cntr=0.3,0.1

Type RM Length L Ch R = 1 ,6240    ,939,939,939
BEGIN DESCRIPTION:
FRANKS CREEK TRIB 1 11.0
END DESCRIPTION:
XS GIS Cut Line= 3
      3587909.87     10139952.41      3586751.89     10140457.65
      3586018.45     10140699.24
#Sta/Elev= 30
  3915.9  225.79  4097.5  223.25  4230.9  219.78  4284.4   219.8  4382.6  218.21
  4546.2  218.74  4674.2  214.18  4742.6  214.51  4872.6  213.32  4953.6  214.45
  4971.5  213.47  4982.7  211.38  4997.4  210.13  5000.1  209.63  5003.4  210.13
  5005.8   211.6  5035.3  213.58  5076.1  213.27  5109.8  215.49  5146.3  214.48
  5169.4   216.4  5315.9  223.61  5484.4  226.58    5625   226.5  5715.1  223.18
  5795.8  221.33  5863.4  219.17  5884.5  217.07    5911  217.11  5951.5  218.63
#Mann= 8 ,-1 , 0
  3915.9     .05       0  4872.6     .16       0  4997.4     .07       0
  5003.4     .16       0  5035.3     .05       0  5109.8     .16       0
  5169.4     .05       0  5795.8     .16       0
Bank Sta=4997.4,5003.4
XS Rating Curve= 0 ,0
Exp/Cntr=0.3,0.1

Type RM Length L Ch R = 1 ,5301    ,1082,1082,1082
BEGIN DESCRIPTION:
FRANKS CREEK TRIB 1 9.0
END DESCRIPTION:
XS GIS Cut Line= 3
       3587530.7     10139133.62      3587201.31     10139494.45
      3585892.13     10139641.64
#Sta/Elev= 30
  4174.4  225.39  4412.9  224.48  4483.1  223.32  4561.7  220.25    4646  217.35
  4679.9  214.24  4803.1   209.6  4843.3  209.19  4964.1   210.9  4984.2  210.69
  4994.2  208.87  5024.4  210.98  5074.8  210.14  5225.7   215.9    5276  216.41
  5310.2  215.71  5376.6  211.98  5386.7  211.07  5395.2  208.45  5400.2  208.98
  5413.9  207.39  5416.6  206.89  5419.9  207.39    5437  208.97  5547.7  210.47
  5567.8  211.71  5580.3  211.14  5755.3   220.8  5975.1  227.54  5980.4  227.58
#Mann= 5 ,-1 , 0
  4174.4     .05       0  4561.7     .16       0  5413.9     .07       0
  5419.9     .16       0  5975.1     .05       0
Bank Sta=5413.9,5419.9
XS Rating Curve= 0 ,0
Exp/Cntr=0.3,0.1

Type RM Length L Ch R = 1 ,4219    ,1053,1053,1053
BEGIN DESCRIPTION:
FRANKS CREEK TRIB 1 7.0
END DESCRIPTION:
XS GIS Cut Line= 3
      3587246.04     10138795.63      3586492.11     10138841.64
      3585796.63     10138973.44
#Sta/Elev= 30
  4231.9  227.51    4306   226.6  4386.1  224.62  4411.9  223.03  4426.2  223.53
  4485.6  222.02  4506.3  221.87  4556.4  219.11  4656.6  211.27  4726.8  206.94
  4741.4  206.42    4837   206.4    4864   205.7  4866.8   205.2    4870   205.7
  4903.6  205.72  4917.1  206.92  4937.1  206.81  4957.2  207.64  4967.2   206.4
  4977.2   207.1  4997.7  206.63  5007.6  206.04  5018.5  206.95  5058.5   207.6
  5190.8  213.78    5262  215.86  5394.8  221.19  5557.2  225.03  5695.1  226.53
#Mann= 5 ,-1 , 0
  4231.9     .05       0  4485.6     .16       0    4864     .03       0
    4870     .16       0  4997.7     .05       0
Bank Sta=4864,4870
XS Rating Curve= 0 ,0
Exp/Cntr=0.3,0.1

Type RM Length L Ch R = 1 ,3166    ,751,751,751
BEGIN DESCRIPTION:
FRANKS CREEK TRIB 1 5.0
END DESCRIPTION:
XS GIS Cut Line= 3
      3587441.66      10138377.1       3586791.7     10137927.12
       3585692.1     10137891.64
#Sta/Elev= 30
    3947   224.7    3986  223.74  4015.7  224.05  4108.3  221.08  4173.8  220.53
  4230.6  218.54  4245.5  218.76  4347.5  214.02  4633.3  202.77    4684  202.23
  4698.8  203.75  4712.7   203.9  4877.2  201.87  4957.2  202.46  4994.3  200.72
    4997  200.22  5000.3  200.72  5007.3  202.68  5017.3  202.96  5067.4  201.63
  5077.3  202.77  5117.3  203.85  5324.3  206.95  5382.7  208.47  5407.5  208.51
  5481.7   210.7  5627.6  214.69  5647.6  215.89  5777.7  218.82  5837.7  221.66
#Mann= 7 ,-1 , 0
    3947     .05       0  4347.5     .16       0  4994.3     .07       0
  5000.3     .16       0  5324.3     .05       0  5382.7     .16       0
  5481.7     .05       0
Bank Sta=4994.3,5000.3
XS Rating Curve= 0 ,0
Exp/Cntr=0.3,0.1

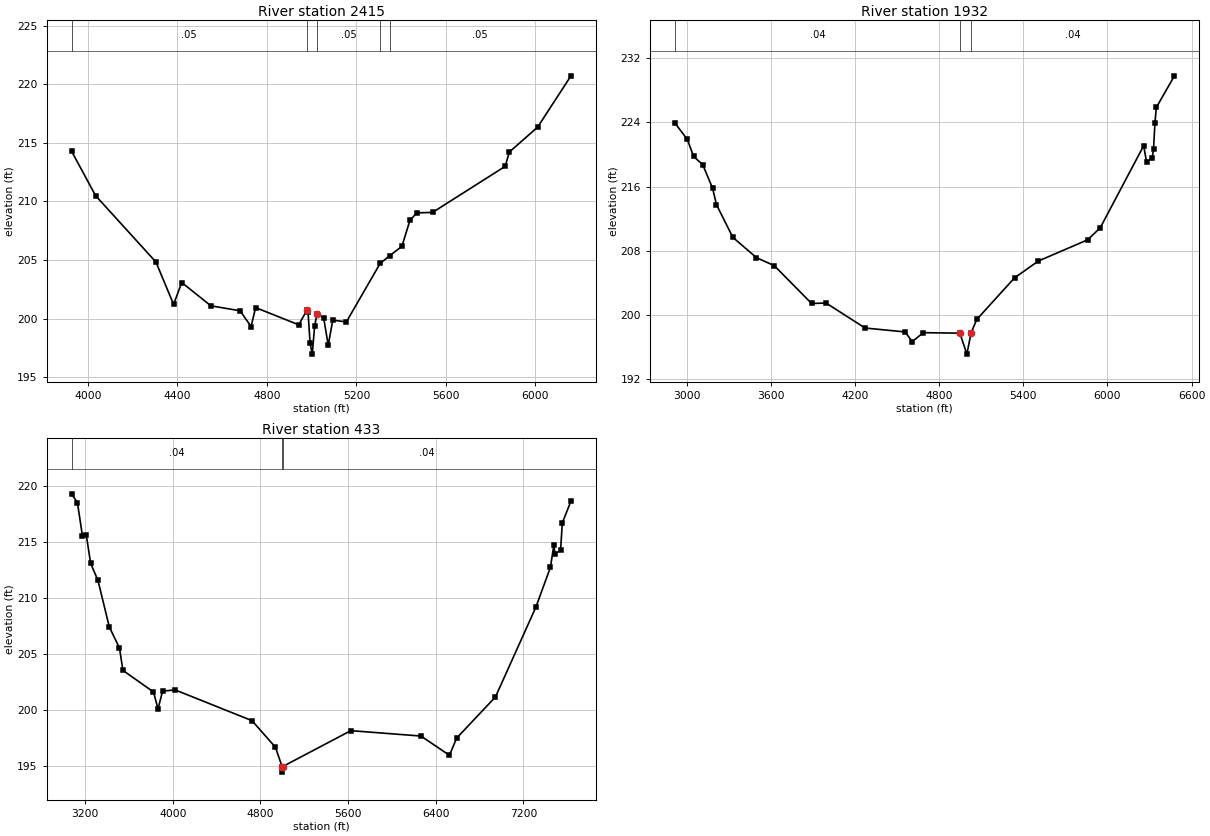
Type RM Length L Ch R = 1 ,2415    ,483,483,483
BEGIN DESCRIPTION:
FRANKS CREEK TRIB 1 3.0
END DESCRIPTION:
XS GIS Cut Line= 3
      3587542.08      10138041.6      3587121.48     10137381.27
      3585692.13     10137141.65
#Sta/Elev= 30
  3926.4  214.29  4033.9  210.49  4303.9  204.82  4382.6  201.21    4419  203.08
  4549.4  201.09  4679.7  200.67  4728.9  199.32  4749.2  200.94  4941.9  199.47
  4978.3  200.72  4983.4  200.58  4992.6   197.9  5002.5  196.97  5012.9  199.35
    5023  200.37  5053.4  200.07  5073.7  197.73    5094  199.87  5154.8  199.72
  5305.9  204.71  5347.9  205.36  5402.9  206.16  5438.7  208.37  5469.1  209.02
  5540.1  209.06  5864.6  212.99  5883.1  214.21  6009.5  216.33  6158.6  220.71
#Mann= 5 ,-1 , 0
  3926.4     .05       0  4978.3    .035       0    5023     .05       0
  5305.9     .16       0  5347.9     .05       0
Bank Sta=4978.3,5023
XS Rating Curve= 0 ,0
Exp/Cntr=0.3,0.1

Type RM Length L Ch R = 1 ,1932    ,1499,1499,1499
BEGIN DESCRIPTION:
Mapping XS 4f2dfc44
END DESCRIPTION:
XS GIS Cut Line= 3
      3588105.76     10138175.77      3587702.98     10136877.17
      3585503.02     10136869.36
#Sta/Elev= 30
  2917.7   223.9  3005.8  221.86  3050.5  219.75  3115.7  218.72  3186.1  215.77
  3213.4  213.75  3330.3  209.68  3497.9  207.16  3625.4  206.16  3891.3  201.45
  3994.3  201.51  4272.4   198.4  4558.2  197.91  4608.2  196.71  4688.2  197.82
  4948.2  197.76    4998  195.15  5028.2   197.8  5068.2  199.46  5338.2  204.65
  5508.2  206.74  5858.2  209.37  5948.2  210.86  6258.2  221.09  6278.2  219.08
  6318.2  219.53  6328.2  220.62  6338.2  223.88  6348.2  225.84  6477.3  229.78
#Mann= 3 , 0 , 0
  2917.7     .04       0  4948.2    .035       0  5028.2     .04       0
Bank Sta=4948.2,5028.2
XS Rating Curve= 0 ,0
Exp/Cntr=0.3,0.1

Type RM Length L Ch R = 1 ,433     ,0,0,0
BEGIN DESCRIPTION:
FRANKS CREEK TRIB 1 1.0
END DESCRIPTION:
XS GIS Cut Line= 4
      3588232.21      10138174.9       3588558.6     10136945.75
      3587572.49     10136119.36      3585619.32     10136553.63
#Sta/Elev= 30
  3075.3  219.27  3129.3  218.48  3174.6  215.55  3209.6  215.64  3249.8  213.06
  3316.6  211.55  3420.1   207.4  3513.2  205.51  3544.3  203.52  3823.6  201.59
    3865  200.08  3906.4  201.66  4020.2  201.78  4723.3  199.03  4936.7  196.66
  4997.4  194.94  5000.2  194.44  5003.4  194.94    5625  198.14  6265.1  197.66
  6525.3  195.94  6590.3  197.47  6945.3  201.15  7314.1  209.16  7447.3  212.72
    7478   214.7  7488.2  213.92  7539.5  214.23  7555.5  216.68  7634.5  218.63
#Mann= 3 , 0 , 0
  3075.3     .04       0  4997.4    .035       0  5003.4     .04       0
Bank Sta=4997.4,5003.4
XS Rating Curve= 0 ,0
Exp/Cntr=0.3,0.1

Chan Stop Cuts=-1
Use User Specified Reach Order=0
Composite Channel Slope=5