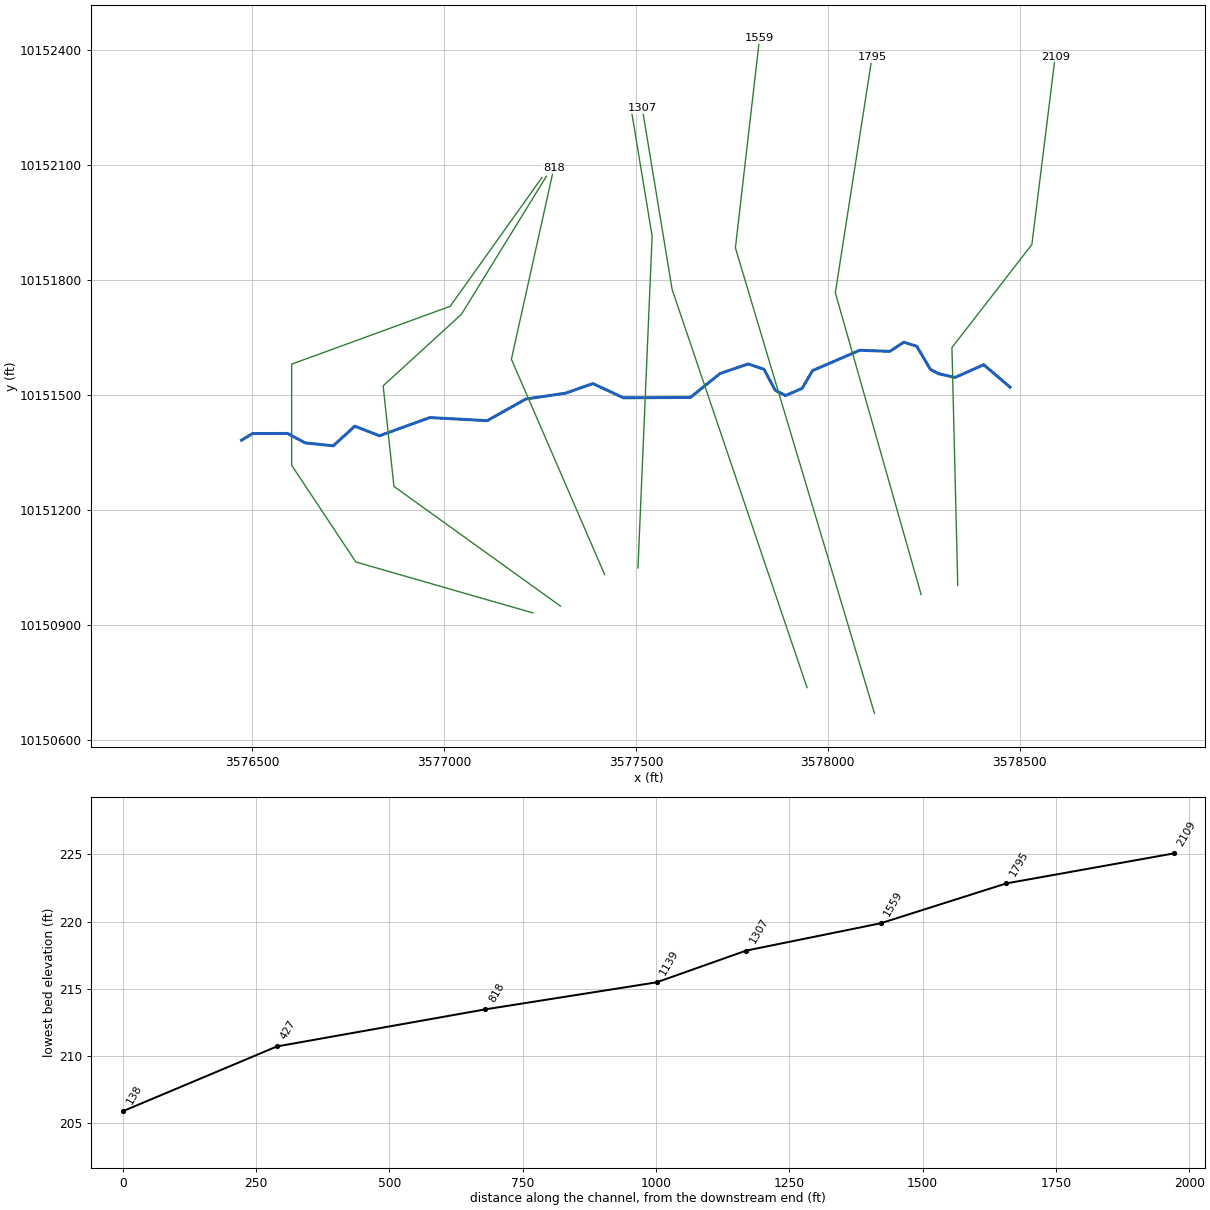
--- FRANKS CREEK TRIB 6.prj (project) ---

Proj Title=FRANKS CREEK TRIB 6 Base Level Engineering
Current Plan=p01
Default Exp/Contr=0.3,0.1
English Units
Geom File=g01
Flow File=f01
Plan File=p01
Y Axis Title=Elevation
X Axis Title(PF)=Main Channel Distance
X Axis Title(XS)=Station
BEGIN DESCRIPTION:
FRANKS CREEK TRIB 6
END DESCRIPTION:
DSS Export Rating Curves= 0
DSS Export Rating Curve Sorted= 0
DSS Export Volume Flow Curves= 0
DXF OffsetX= 0
DXF OffsetY= 0
DXF ScaleX= 1
DXF ScaleY= 10

--- FRANKS CREEK TRIB 6.p01 (plan) ---

Plan Title=Multiple Run
Short Identifier=Multiple
Geom File=g01
Flow File=f01
Subcritical Flow
K Sum by GR= 0
Std Step Tol= 0.01
Critical Tol= 0.01
Num of Std Step Trials= 20
Max Error Tol= 0.3
Flow Tol Ratio= 0.001
Split Flow NTrial= 30
Split Flow Tol= 0.02
Split Flow Ratio= 0.02
Log Output Level= 0
Friction Slope Method= 1
Unsteady Friction Slope Method= 2
Unsteady Bridges Friction Slope Method= 1
Parabolic Critical Depth
Global Vel Dist=  1 , 1 , 1
Global Log Level= 0
CheckData=True
Encroach Param= -1, 0, 0, 0
BEGIN DESCRIPTION:
Multiple Run
END DESCRIPTION:

--- FRANKS CREEK TRIB 6.f01 (steady flow) ---

Flow Title=Multiple
Number of Profiles=7
Profile Names=10-year,25-year,50-year,1pct_min,100-year,1pct_plu,500-year
River Rch & RM= FRANKS CREEK TRI,Reach-1,2109
     244     312     365     315     426     576     577
Boundary for River Rch & Prof#=FRANKS CREEK TRI,Reach-1,1
Up Type=0
Dn Type=3
Dn Slope=0.005
Boundary for River Rch & Prof#=FRANKS CREEK TRI,Reach-1,2
Up Type=0
Dn Type=3
Dn Slope=0.005
Boundary for River Rch & Prof#=FRANKS CREEK TRI,Reach-1,3
Up Type=0
Dn Type=3
Dn Slope=0.005
Boundary for River Rch & Prof#=FRANKS CREEK TRI,Reach-1,4
Up Type=0
Dn Type=3
Dn Slope=0.005
Boundary for River Rch & Prof#=FRANKS CREEK TRI,Reach-1,5
Up Type=0
Dn Type=3
Dn Slope=0.005
Boundary for River Rch & Prof#=FRANKS CREEK TRI,Reach-1,6
Up Type=0
Dn Type=3
Dn Slope=0.005
Boundary for River Rch & Prof#=FRANKS CREEK TRI,Reach-1,7
Up Type=0
Dn Type=3
Dn Slope=0.005

--- FRANKS CREEK TRIB 6.g01 (geometry) ---

Geom Title=Existing Conditions
Program Version=4.10

River Reach=FRANKS CREEK TRI,Reach-1
Reach XY= 30
      3578474.82     10151520.06      3578406.21     10151578.67
      3578331.39     10151545.37      3578288.93     10151555.18
      3578267.24     10151566.43      3578231.81     10151626.66
      3578198.24     10151637.35      3578161.31     10151613.48
      3578083.13     10151616.37      3577960.13      10151563.3
      3577933.17       10151517.      3577889.72     10151498.14
      3577862.99     10151511.61      3577833.72     10151566.63
      3577792.76     10151580.65       3577719.6     10151555.85
       3577641.8     10151493.27      3577467.37     10151492.28
      3577387.65      10151529.4      3577316.35     10151504.32
      3577213.15     10151489.13      3577112.23     10151432.56
      3576962.59     10151440.67      3576831.69     10151393.14
      3576767.34     10151418.21      3576711.24     10151366.97
      3576638.13     10151374.55       3576592.1     10151399.12
      3576500.95     10151399.06      3576472.11     10151381.64

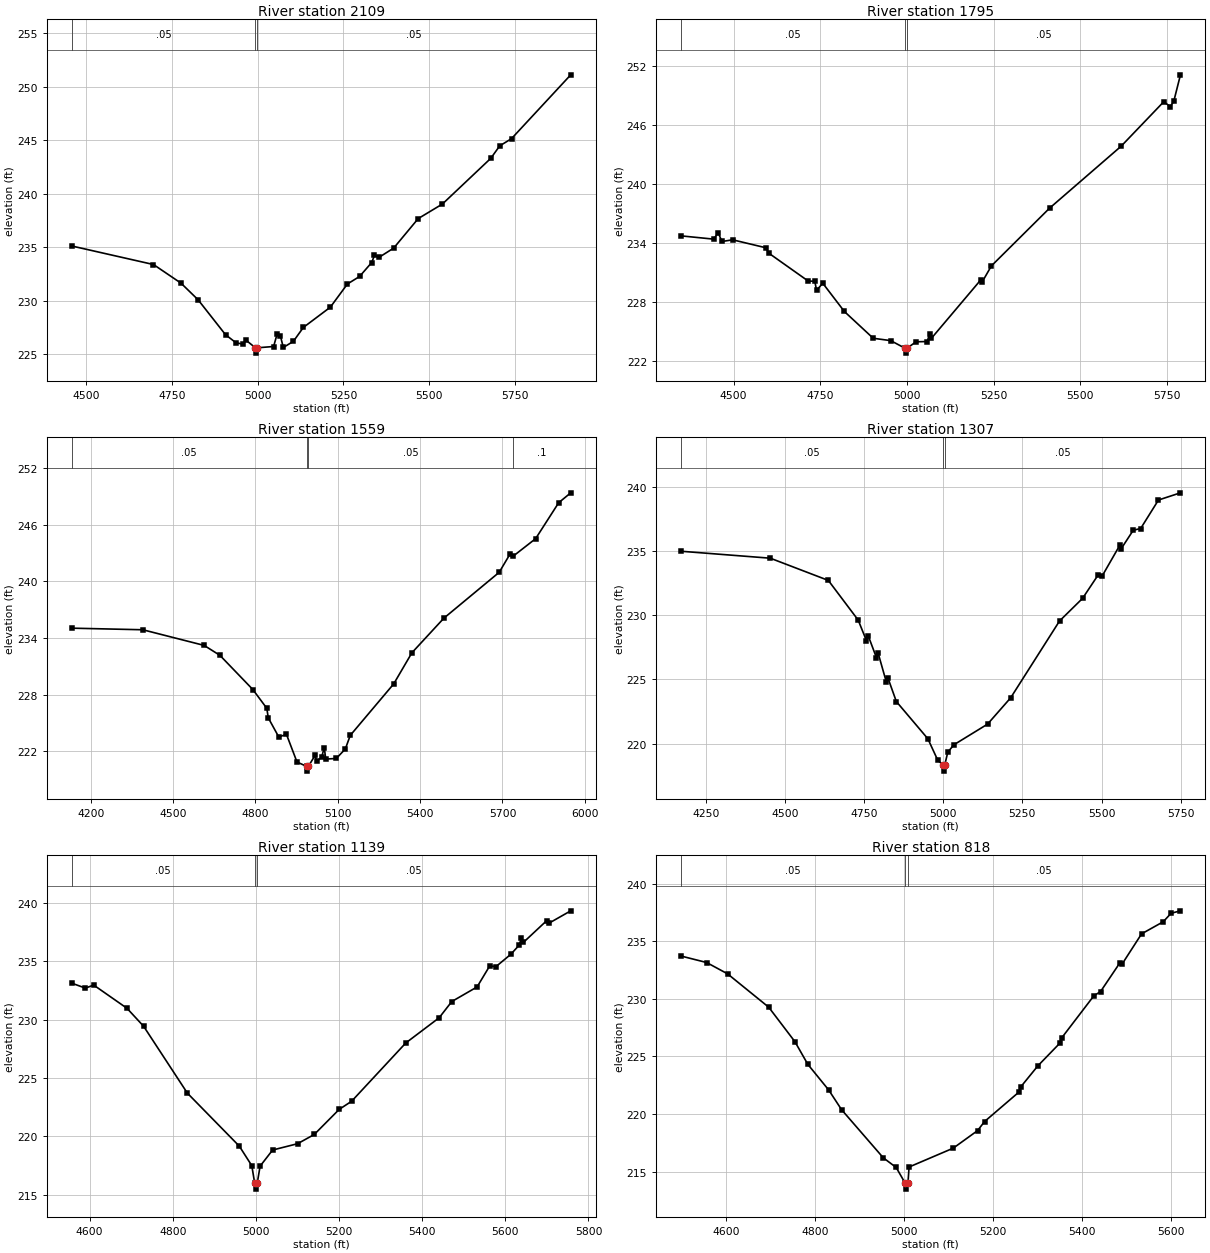
Type RM Length L Ch R = 1 ,2109    ,314,314,314
BEGIN DESCRIPTION:
FRANKS CREEK TRIB 6 4.0
END DESCRIPTION:
XS GIS Cut Line= 4
      3578338.56     10151002.67      3578323.37     10151623.36
       3578531.7     10151892.45      3578592.47     10152382.91
#Sta/Elev= 30
  4457.3  235.11  4696.3  233.37  4776.4  231.63  4826.4  230.07  4906.4   226.8
  4936.4  226.06  4956.4  225.92  4966.4  226.28  4993.4  225.58  4996.2  225.08
  4999.4  225.58  5046.5   225.7  5056.5  226.84  5066.5  226.66  5074.8  225.61
  5104.1  226.18  5133.1  227.48  5211.9  229.38  5261.7  231.55    5297  232.25
  5332.3  233.55  5340.5  234.22  5354.2  234.05  5396.6  234.91  5468.1  237.67
  5538.6  239.03  5679.7  243.31  5705.6  244.47  5740.1  245.15  5912.7  251.12
#Mann= 3 ,-1 , 0
  4457.3     .05       0  4993.4    .035       0  4999.4     .05       0
Bank Sta=4993.4,4999.4
XS Rating Curve= 0 ,0
Exp/Cntr=0.3,0.1

Type RM Length L Ch R = 1 ,1795    ,236,236,236
BEGIN DESCRIPTION:
Mapping XS 6a7803ae
END DESCRIPTION:
XS GIS Cut Line= 3
      3578243.09     10150978.78      3578019.55     10151766.58
      3578115.03      10152380.7
#Sta/Elev= 30
  4348.7  234.76    4442  234.43  4455.6  235.07    4466  234.19  4497.2  234.36
  4593.2  233.55  4601.1  233.01  4715.5  230.16    4734  230.16  4739.2  229.23
  4757.1  229.95  4819.4  227.08  4902.6  224.36  4953.1  224.12  4994.4  223.35
  4997.1  222.85  5000.4  223.35  5026.1     224  5058.5  224.03  5065.2  224.83
  5070.4  224.35  5212.5  230.27  5217.5  230.11  5243.6  231.71  5411.3  237.57
    5618  243.87    5741  248.39  5759.7  247.89  5769.8  248.43  5789.1  251.12
#Mann= 3 ,-1 , 0
  4348.7     .05       0  4994.4     .03       0  5000.4     .05       0
Bank Sta=4994.4,5000.4
XS Rating Curve= 0 ,0
Exp/Cntr=0.3,0.1

Type RM Length L Ch R = 1 ,1559    ,252,252,252
BEGIN DESCRIPTION:
Mapping XS a2821f4b
END DESCRIPTION:
XS GIS Cut Line= 3
      3578121.55     10150668.47      3577759.13     10151883.77
      3577822.07     10152430.67
#Sta/Elev= 30
    4130  235.04  4389.7  234.87  4613.3  233.21  4670.6  232.16  4790.7  228.53
  4841.5  226.54  4846.8  225.53  4885.1   223.5  4913.1  223.78  4951.4  220.85
  4986.8  220.38  4989.5  219.88  4992.8  220.38  5017.7  221.57  5022.9  220.92
  5041.2  221.36  5050.9  222.38  5056.1  221.16  5094.5  221.22  5127.6  222.23
  5145.5  223.67  5303.8  229.13  5370.1  232.43  5486.6   236.1    5688  240.96
  5726.8  242.86  5738.9  242.67  5820.8  244.53  5904.8  248.34  5948.7  249.39
#Mann= 4 ,-1 , 0
    4130     .05       0  4986.8     .03       0  4992.8     .05       0
  5738.9      .1       0
Bank Sta=4986.8,4992.8
XS Rating Curve= 0 ,0
Exp/Cntr=0.3,0.1

Type RM Length L Ch R = 1 ,1307    ,168,168,168
BEGIN DESCRIPTION:
Mapping XS 00bcaba8
END DESCRIPTION:
XS GIS Cut Line= 3
      3577945.75     10150735.82       3577594.2     10151775.27
      3577516.39     10152248.62
#Sta/Elev= 30
  4172.4  234.97  4453.7  234.43  4637.1   232.7  4731.4  229.61  4757.5  228.01
  4762.8  228.41    4789  226.69  4794.3  227.05  4820.4  224.78  4825.7  225.08
  4851.9  223.27  4951.5  220.37  4982.9  218.69    4999  218.35  5001.7  217.85
    5005  218.35  5014.4  219.32  5033.6   219.9  5140.1  221.51  5213.1  223.56
  5367.4  229.54  5440.1   231.3    5489  233.11  5501.3  233.01  5557.4  235.42
  5562.5  235.18  5600.4  236.61  5623.7  236.74  5679.9  238.96  5749.4  239.52
#Mann= 3 ,-1 , 0
  4172.4     .05       0    4999     .03       0    5005     .05       0
Bank Sta=4999,5005
XS Rating Curve= 0 ,0
Exp/Cntr=0.3,0.1

Type RM Length L Ch R = 1 ,1139    ,321,321,321
BEGIN DESCRIPTION:
Mapping XS bd749d00
END DESCRIPTION:
XS GIS Cut Line= 3
      3577505.23     10151048.31      3577542.12     10151914.15
      3577487.87     10152243.99
#Sta/Elev= 30
  4556.5  233.14  4589.9  232.71  4609.9  232.97    4690  230.98    4730  229.44
  4835.3  223.71  4960.2  219.17  4990.2   217.5  4997.2  215.99    5000  215.49
  5003.2  215.99  5010.2  217.46  5040.3  218.84  5100.3  219.38  5140.4  220.17
  5200.4  222.32  5230.4  223.02  5360.6  228.01  5440.9  230.17  5471.3  231.56
  5532.1  232.81  5562.5  234.61  5577.5  234.55  5613.1   235.6  5633.4  236.39
  5638.7  237.02  5643.7  236.63  5699.9   238.5    5705  238.27  5757.4  239.33
#Mann= 3 ,-1 , 0
  4556.5     .05       0  4997.2     .03       0  5003.2     .05       0
Bank Sta=4997.2,5003.2
XS Rating Curve= 0 ,0
Exp/Cntr=0.3,0.1

Type RM Length L Ch R = 1 ,818     ,391,391,391
BEGIN DESCRIPTION:
Mapping XS a625b83c
END DESCRIPTION:
XS GIS Cut Line= 3
       3577418.4     10151030.95      3577175.37     10151592.97
      3577286.05     10152092.13
#Sta/Elev= 30
  4498.6  233.72  4555.8  233.16  4602.8  232.18  4695.5  229.28  4754.6  226.28
  4783.5  224.32  4830.5  222.09  4859.5  220.38  4953.4   216.2  4982.4  215.36
  5002.9  213.98  5005.6  213.48  5008.9  213.98  5011.4   215.4  5110.9  217.04
  5165.5  218.56  5181.3  219.35  5257.8  221.88  5263.2  222.38  5301.4  224.19
  5350.1  226.13  5355.4  226.64  5427.1  230.26  5442.4  230.64    5486  233.14
  5491.1  233.04  5534.7  235.65  5583.4   236.7  5601.2  237.44  5622.2  237.65
#Mann= 3 ,-1 , 0
  4498.6     .05       0  5002.9    .035       0  5008.9     .05       0
Bank Sta=5002.9,5008.9
XS Rating Curve= 0 ,0
Exp/Cntr=0.3,0.1

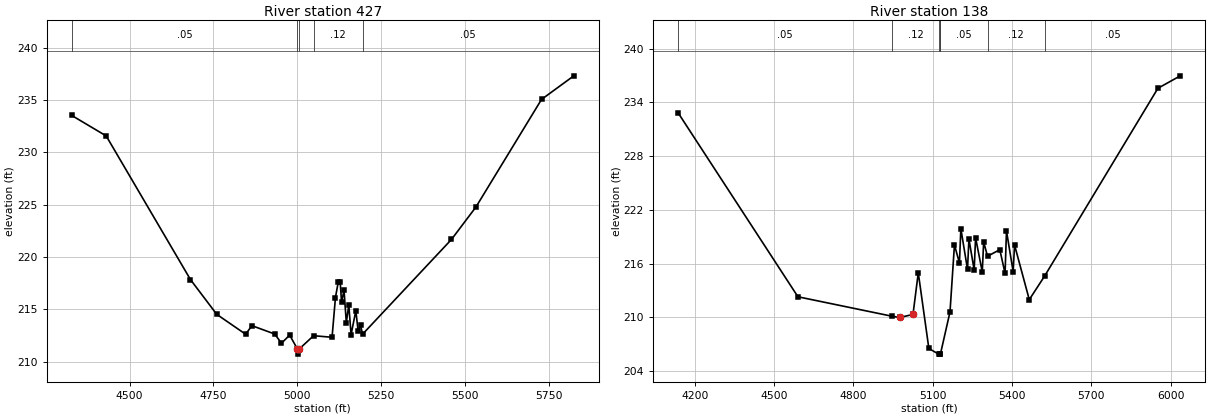
Type RM Length L Ch R = 1 ,427     ,289,289,289
BEGIN DESCRIPTION:
Mapping XS b8f3e35f
END DESCRIPTION:
XS GIS Cut Line= 5
      3577303.39     10150948.45      3576869.38     10151260.94
      3576841.16     10151523.53      3577045.16     10151710.16
      3577266.51      10152070.4
#Sta/Elev= 30
  4326.9  233.53  4429.9  231.57  4681.4  217.84  4759.8  214.52    4846  212.62
  4864.6  213.44  4932.8  212.64  4952.9  211.76  4977.3  212.54  5000.2  211.22
    5003  210.72  5006.2  211.22  5048.7  212.48  5103.8  212.33  5113.9  216.13
  5122.3  217.62  5128.1  217.62  5132.1  215.68  5139.5  216.83  5146.3  213.74
  5153.7  215.41  5160.5  212.58  5174.7  214.87  5181.5  212.95  5188.9  213.46
  5194.7  212.62  5460.1  221.68  5533.1  224.78  5728.8  235.06  5825.1  237.31
#Mann= 5 ,-1 , 0
  4326.9     .05       0  5000.2     .03       0  5006.2     .05       0
  5048.7     .12       0  5194.7     .05       0
Bank Sta=5000.2,5006.2
XS Rating Curve= 0 ,0
Exp/Cntr=0.3,0.1

Type RM Length L Ch R = 1 ,138     ,0,0,0
BEGIN DESCRIPTION:
FRANKS CREEK TRIB 6 1.0
END DESCRIPTION:
XS GIS Cut Line= 6
      3577231.26     10150930.78      3576769.98      10151063.7
      3576602.74     10151316.21      3576602.74      10151580.1
      3577015.93     10151731.14      3577255.07     10152067.32
#Sta/Elev= 30
  4137.1  232.83  4590.3   212.3  4947.6  210.12  4975.4  209.99  5025.4  210.33
  5045.4  214.98  5085.4  206.53  5122.4   205.9  5128.4   205.9  5129.3  205.92
  5165.4  210.62  5182.2   218.1  5201.1  216.06  5206.4   219.9  5231.6  215.36
  5236.9  218.75  5256.8  215.29  5262.1   218.9  5287.4  215.07  5292.7  218.43
  5307.2  216.82  5353.8  217.56  5373.6   214.9    5379  219.64  5404.2  215.12
  5409.5  218.08  5465.2  211.98  5523.6  214.63  5951.7  235.57  6036.4  236.96
#Mann= 7 ,-1 , 0
  4137.1     .05       0  4947.6     .12       0  5122.4     .07       0
  5128.4     .12       0  5129.3     .05       0  5307.2     .12       0
  5523.6     .05       0
#XS Ineff= 2 , 0
       0                 5040.94       0  209.63
Permanent Ineff=
       F       T
Bank Sta=4975.4,5025.4
XS Rating Curve= 0 ,0
Exp/Cntr=0.3,0.1

Chan Stop Cuts=-1
Use User Specified Reach Order=0
Composite Channel Slope=5