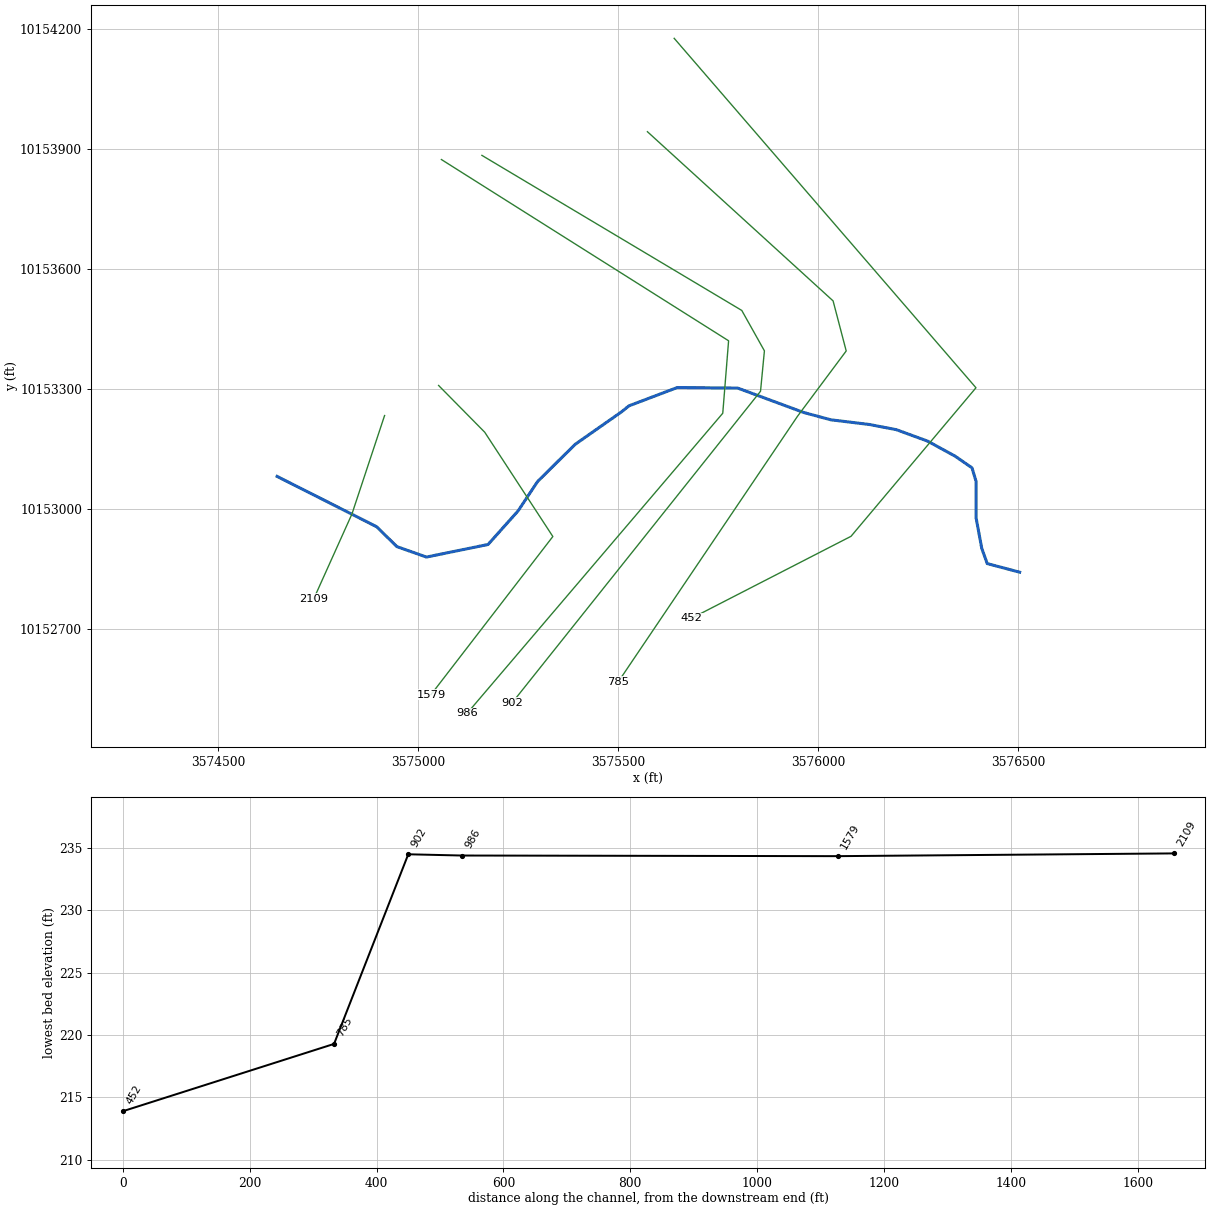
--- FRANKS CREEK TRIB 7.prj (project) ---

Proj Title=FRANKS CREEK TRIB 7 Base Level Engineering
Current Plan=p01
Default Exp/Contr=0.3,0.1
English Units
Geom File=g01
Flow File=f01
Plan File=p01
BEGIN DESCRIPTION:
FRANKS CREEK TRIB 7
END DESCRIPTION:

--- FRANKS CREEK TRIB 7.p01 (plan) ---

Plan Title=Multiple Run
Short Identifier=Multiple
Geom File=g01
Flow File=f01
Subcritical Flow
K Sum by GR= 0
Std Step Tol= 0.01
Critical Tol= 0.01
Num of Std Step Trials= 20
Max Error Tol= 0.3
Flow Tol Ratio= 0.001
Split Flow NTrial= 30
Split Flow Tol= 0.02
Split Flow Ratio= 0.02
Log Output Level= 0
Friction Slope Method= 1
Unsteady Friction Slope Method= 2
Unsteady Bridges Friction Slope Method= 1
Parabolic Critical Depth
Global Vel Dist=  1 , 1 , 1
Global Log Level= 0
CheckData=True
Encroach Param= -1, 0, 0, 0
BEGIN DESCRIPTION:
Multiple Run
END DESCRIPTION:

--- FRANKS CREEK TRIB 7.f01 (steady flow) ---

Flow Title=Multiple
Number of Profiles=7
Profile Names=10-year,25-year,50-year,1pct_min,100-year,1pct_plu,500-year
River Rch & RM= FRANKS CREEK TRI,Reach-1,2109
     150     187     214     181     245     331     319
Boundary for River Rch & Prof#=FRANKS CREEK TRI,Reach-1,1
Up Type=0
Dn Type=3
Dn Slope=0.005
Boundary for River Rch & Prof#=FRANKS CREEK TRI,Reach-1,2
Up Type=0
Dn Type=3
Dn Slope=0.005
Boundary for River Rch & Prof#=FRANKS CREEK TRI,Reach-1,3
Up Type=0
Dn Type=3
Dn Slope=0.005
Boundary for River Rch & Prof#=FRANKS CREEK TRI,Reach-1,4
Up Type=0
Dn Type=3
Dn Slope=0.005
Boundary for River Rch & Prof#=FRANKS CREEK TRI,Reach-1,5
Up Type=0
Dn Type=3
Dn Slope=0.005
Boundary for River Rch & Prof#=FRANKS CREEK TRI,Reach-1,6
Up Type=0
Dn Type=3
Dn Slope=0.005
Boundary for River Rch & Prof#=FRANKS CREEK TRI,Reach-1,7
Up Type=0
Dn Type=3
Dn Slope=0.005

--- FRANKS CREEK TRIB 7.g01 (geometry) ---

Geom Title=Existing Conditions

River Reach=FRANKS CREEK TRI,Reach-1
Reach XY= 24
      3574646.51     10153081.58      3574895.41     10152955.73
      3574946.41     10152905.81      3575020.20     10152879.77
      3575174.28     10152911.24      3575249.42     10152995.34
      3575297.98     10153068.57      3575392.38     10153161.89
      3575508.48     10153243.27      3575526.60     10153257.96
      3575647.47     10153303.81      3575798.51     10153302.51
      3575963.87     10153241.31      3576031.58     10153223.08
      3576127.93     10153211.36      3576195.64     10153198.34
      3576273.77     10153169.69      3576342.78     10153131.93
      3576384.66     10153102.96      3576394.98     10153068.57
      3576394.98     10152977.43      3576409.09     10152901.47
      3576422.73     10152863.42      3576503.84     10152841.92

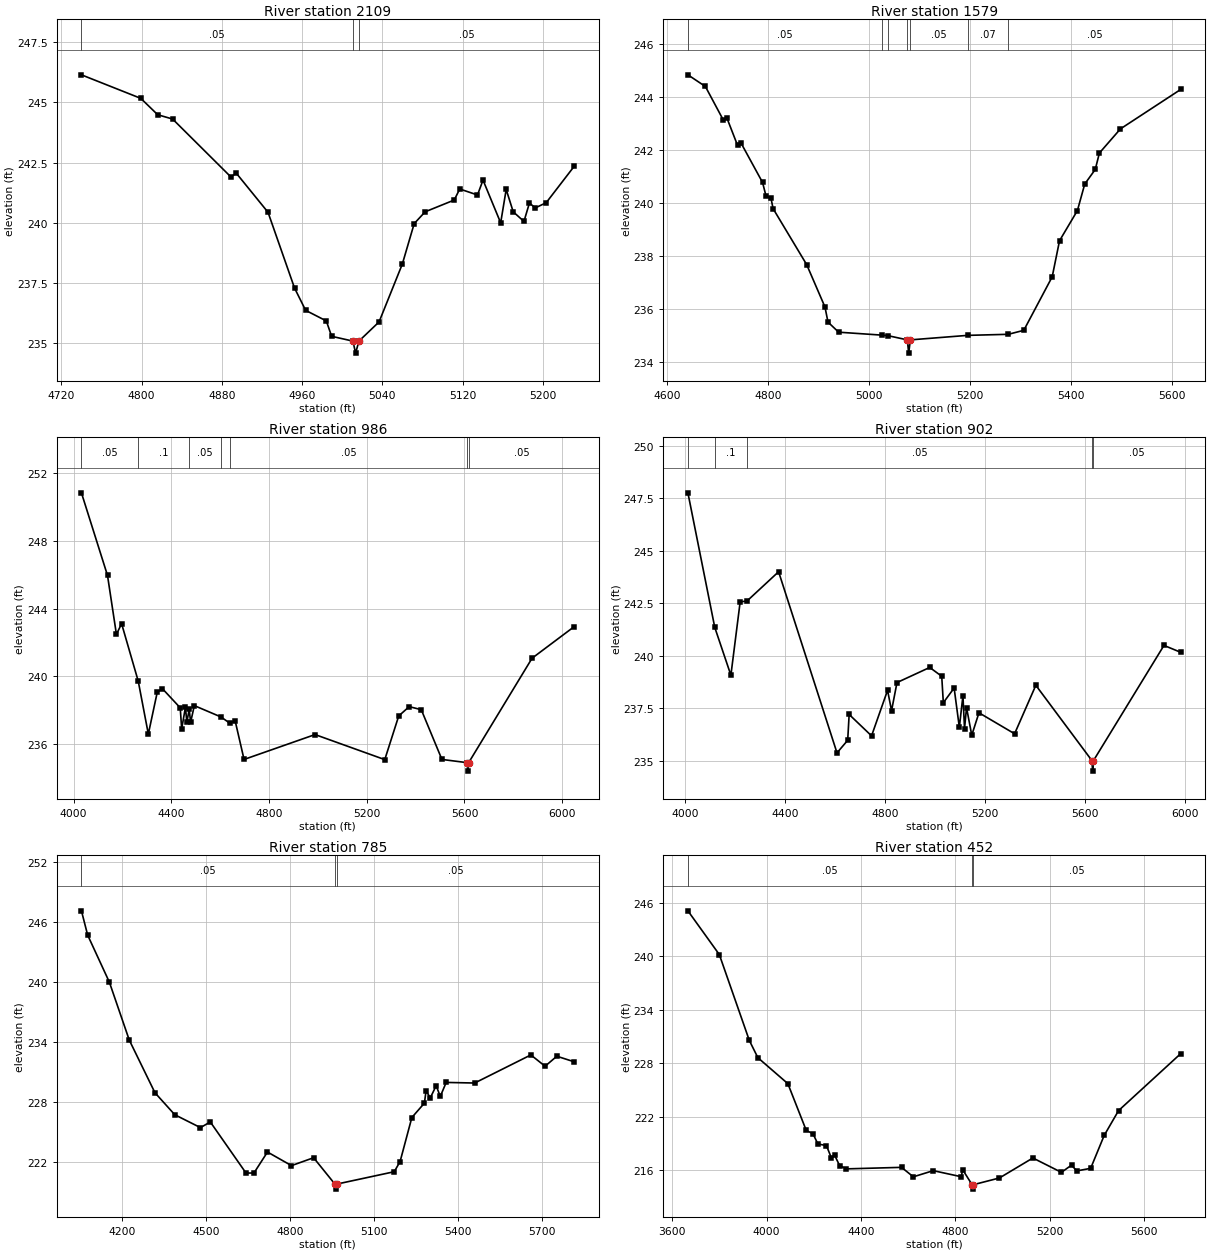
Type RM Length L Ch R = 1,2109,530,530,530
BEGIN DESCRIPTION:
FRANKS CREEK TRIB 7 4.0
END DESCRIPTION:
XS GIS Cut Line= 3
      3574915.44     10153233.77      3574833.75     10152987.35
      3574738.64     10152776.07
#Sta/Elev= 30
  4740.0  246.15  4799.2  245.17  4816.0  244.49  4830.9  244.31  4889.0  241.90
  4894.3  242.06  4926.0  240.43  4952.4  237.28  4963.5  236.35  4984.1  235.91
  4989.4  235.27  5010.6  235.07  5013.3  234.57  5016.6  235.07  5036.7  235.87
  5059.9  238.28  5071.7  239.96  5082.6  240.45  5111.6  240.94  5117.1  241.40
  5134.8  241.15  5140.3  241.77  5157.9  239.99  5163.4  241.38  5170.4  240.45
  5181.1  240.05  5186.6  240.82  5192.3  240.61  5203.3  240.83  5231.3  242.35
#Mann=3,-1,0
  4740.0    0.05       0  5010.6    0.03       0  5016.6    0.05       0
Bank Sta=5010.6,5016.6
Exp/Cntr=0.3,0.1

Type RM Length L Ch R = 1,1579,593,593,593
BEGIN DESCRIPTION:
FRANKS CREEK TRIB 7 3.0
END DESCRIPTION:
XS GIS Cut Line= 4
      3575050.54     10153308.97      3575165.91     10153192.04
      3575336.29     10152931.16      3575031.50     10152535.62
#Sta/Elev= 30
  4641.6  244.85  4676.2  244.41  4711.5  243.15  4718.6  243.23  4739.8  242.19
  4746.9  242.27  4789.3  240.79  4796.4  240.26  4805.9  240.20  4810.2  239.80
  4876.6  237.69  4912.8  236.09  4918.8  235.52  4939.9  235.14  5024.7  235.03
  5037.2  235.01  5075.7  234.85  5078.5  234.35  5081.7  234.85  5195.0  235.02
  5275.5  235.06  5306.2  235.21  5362.4  237.23  5376.9  238.59  5412.3  239.73
  5426.8  240.73  5447.6  241.28  5455.8  241.90  5497.4  242.81  5616.8  244.30
#Mann=7,-1,0
  4641.6    0.05       0  5024.7    0.07       0  5037.2    0.05       0
  5075.7    0.03       0  5081.7    0.05       0  5195.0    0.07       0
  5275.5    0.05       0
Bank Sta=5075.7,5081.7
Exp/Cntr=0.3,0.1

Type RM Length L Ch R = 1,986,84,84,84
BEGIN DESCRIPTION:
FRANKS CREEK TRIB 7 2.0
END DESCRIPTION:
XS GIS Cut Line= 4
      3575057.59     10153874.05      3575775.87     10153420.74
      3575761.29     10153239.49      3575121.71     10152488.80
#Sta/Elev= 30
  4032.3  250.84  4139.0  245.96  4175.5  242.48  4196.7  243.11  4264.9  239.71
  4306.1  236.59  4342.6  239.06  4363.8  239.27  4436.7  238.14  4442.6  236.89
  4457.9  238.17  4463.8  237.29  4473.4  238.05  4479.1  237.28  4494.4  238.27
  4603.5  237.60  4638.8  237.24  4661.5  237.37  4697.9  235.09  4988.5  236.56
  5273.9  235.08  5331.0  237.66  5373.9  238.21  5423.3  238.03  5507.8  235.09
  5611.3  234.90  5614.1  234.40  5617.3  234.90  5876.8  241.07  6049.7  242.94
#Mann=7,-1,0
  4032.3    0.05       0  4264.9     0.1       0  4473.4    0.05       0
  4603.5     0.1       0  4638.8    0.05       0  5611.3   0.033       0
  5617.3    0.05       0
Bank Sta=5611.3,5617.3
Exp/Cntr=0.3,0.1

Type RM Length L Ch R = 1,902,117,117,117
BEGIN DESCRIPTION:
Mapping XS c0dad86c
END DESCRIPTION:
XS GIS Cut Line= 5
      3575158.92     10153884.42      3575808.86     10153496.61
      3575865.45     10153395.62      3575855.74     10153294.52
      3575234.40     10152515.15
#Sta/Elev= 30
  4012.8  247.76  4120.2  241.35  4184.7  239.07  4221.7  242.56  4249.6  242.61
  4375.5  244.00  4609.0  235.37  4651.8  235.97  4657.6  237.20  4747.2  236.18
  4811.2  238.35  4827.2  237.38  4848.9  238.72  4979.8  239.44  5027.8  239.02
  5034.2  237.76  5077.4  238.46  5098.2  236.59  5112.6  238.09  5119.0  236.53
  5127.0  237.53  5147.9  236.21  5176.7  237.28  5319.2  236.28  5404.1  238.59
  5628.5  235.00  5631.2  234.50  5634.5  235.00  5916.5  240.49  5983.7  240.16
#Mann=5,-1,0
  4012.8    0.05       0  4120.2     0.1       0  4249.6    0.05       0
  5628.5   0.033       0  5634.5    0.05       0
Bank Sta=5628.5,5634.5
Exp/Cntr=0.3,0.1

Type RM Length L Ch R = 1,785,333,333,333
BEGIN DESCRIPTION:
Mapping XS 523cf71b
END DESCRIPTION:
XS GIS Cut Line= 5
      3575572.82     10153943.69      3576037.24     10153520.50
      3576070.05     10153395.29      3575948.00     10153231.57
      3575500.08     10152567.95
#Sta/Elev= 30
  4053.3  247.12  4075.6  244.69  4153.3  239.98  4224.3  234.20  4316.2  228.93
  4387.1  226.73  4479.0  225.44  4514.1  226.01  4641.8  220.90  4670.2  220.90
  4718.6  223.00  4804.5  221.64  4883.6  222.43  4959.8  219.79  4962.6  219.29
  4965.8  219.79  5171.9  221.03  5192.9  222.05  5234.9  226.45  5279.8  227.89
  5285.8  229.13  5300.8  228.41  5321.8  229.63  5336.7  228.56  5357.7  229.96
  5459.6  229.90  5660.5  232.71  5711.4  231.58  5753.4  232.58  5815.9  232.02
#Mann=3,-1,0
  4053.3    0.05       0  4959.8    0.03       0  4965.8    0.05       0
Bank Sta=4959.8,4965.8
Exp/Cntr=0.3,0.1

Type RM Length L Ch R = 1,452,0,0,0
BEGIN DESCRIPTION:
FRANKS CREEK TRIB 7 1.0
END DESCRIPTION:
XS GIS Cut Line= 4
      3575639.77     10154177.20      3576394.62     10153303.25
      3576082.12     10152931.72      3575682.22     10152726.23
#Sta/Elev= 30
  3666.5  245.08  3799.7  240.18  3927.0  230.55  3963.2  228.62  4090.4  225.71
  4168.3  220.47  4196.8  220.10  4217.7  218.95  4253.9  218.77  4274.7  217.40
  4289.0  217.67  4309.8  216.53  4338.3  216.16  4572.4  216.33  4622.4  215.27
  4706.9  215.96  4825.6  215.28  4831.5  216.07  4871.4  214.39  4874.1  213.89
  4877.4  214.39  4987.5  215.14  5129.3  217.38  5250.3  215.77  5293.2  216.58
  5315.2  215.93  5374.3  216.22  5431.7  219.91  5492.6  222.69  5756.4  229.08
#Mann=3,-1,0
  3666.5    0.05       0  4871.4    0.03       0  4877.4    0.05       0
Bank Sta=4871.4,4877.4
Exp/Cntr=0.3,0.1

Chan Stop Cuts=-1