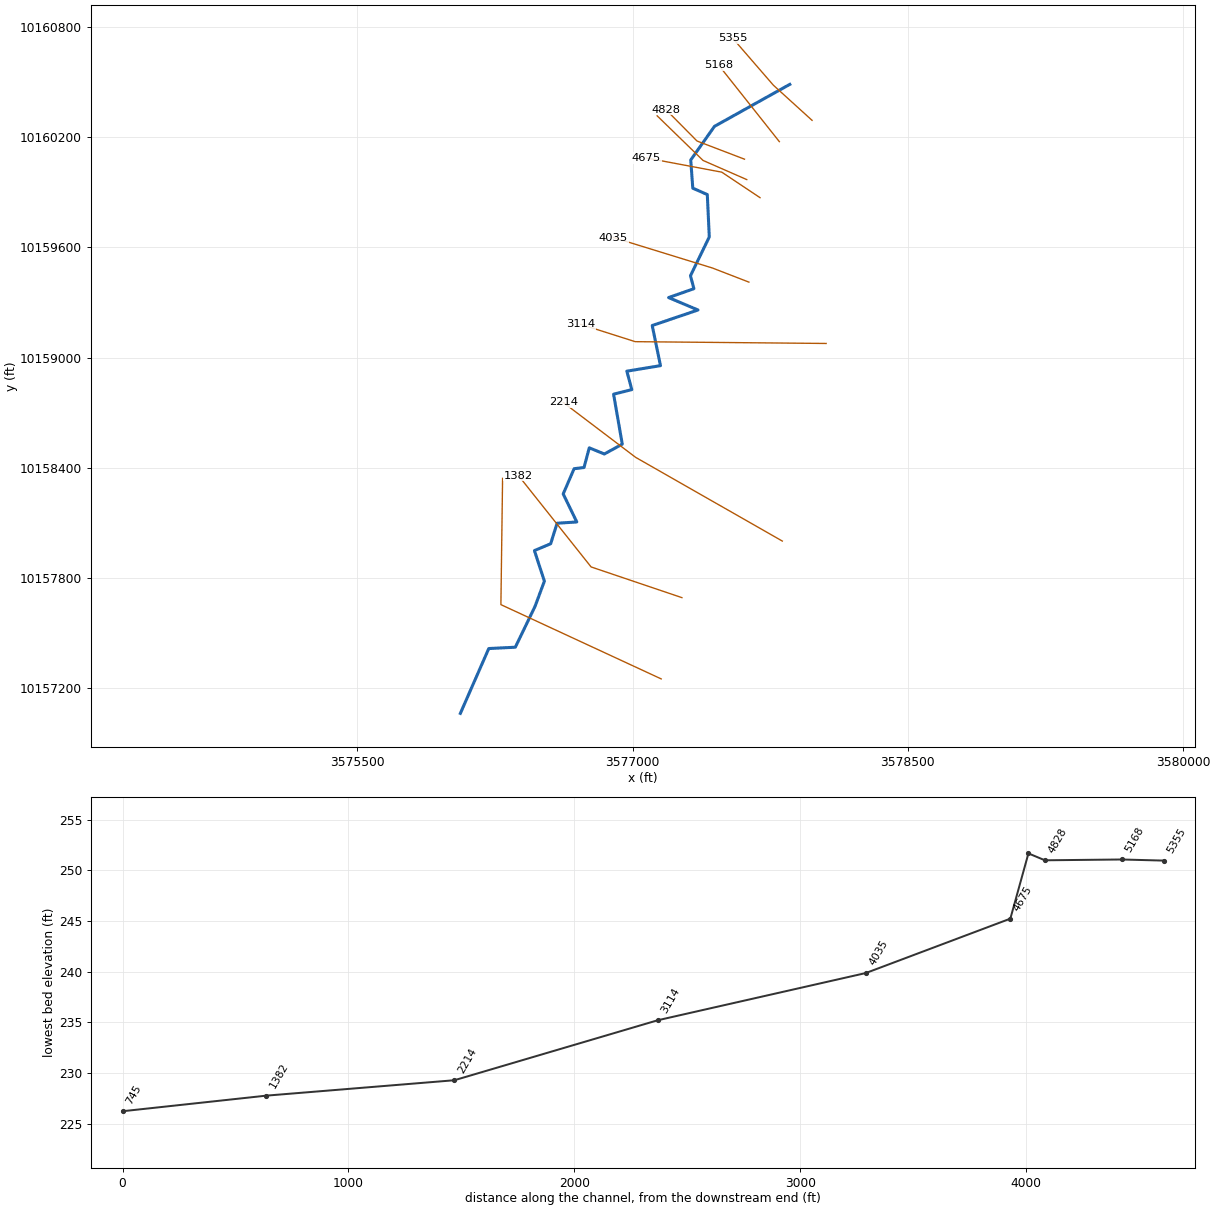
--- FRANKS CREEK TRIB 9.prj (project) ---

Proj Title=FRANKS CREEK TRIB 9 Base Level Engineering
Current Plan=p01
Default Exp/Contr=0.3,0.1
English Units
Geom File=g01
Flow File=f01
Plan File=p01
Y Axis Title=Elevation
X Axis Title(PF)=Main Channel Distance
X Axis Title(XS)=Station
BEGIN DESCRIPTION:
FRANKS CREEK TRIB 9
END DESCRIPTION:
DSS Export Rating Curves= 0
DSS Export Rating Curve Sorted= 0
DSS Export Volume Flow Curves= 0
DXF OffsetX= 0
DXF OffsetY= 0
DXF ScaleX= 1
DXF ScaleY= 10

--- FRANKS CREEK TRIB 9.p01 (plan) ---

Plan Title=Multiple Run
Short Identifier=Multiple
Geom File=g01
Flow File=f01
Subcritical Flow
K Sum by GR= 0
Std Step Tol= 0.01
Critical Tol= 0.01
Num of Std Step Trials= 20
Max Error Tol= 0.3
Flow Tol Ratio= 0.001
Split Flow NTrial= 30
Split Flow Tol= 0.02
Split Flow Ratio= 0.02
Log Output Level= 0
Friction Slope Method= 1
Unsteady Friction Slope Method= 2
Unsteady Bridges Friction Slope Method= 1
Parabolic Critical Depth
Global Vel Dist=  1 , 1 , 1
Global Log Level= 0
CheckData=True
Encroach Param= -1, 0, 0, 0
BEGIN DESCRIPTION:
Multiple Run
END DESCRIPTION:

--- FRANKS CREEK TRIB 9.f01 (steady flow) ---

Flow Title=Multiple
Program Version=4.10
Number of Profiles= 7
Profile Names=10-year,25-year,50-year,1pct_min,100-year,1pct_plu,500-year
River Rch & RM=FRANKS CREEK TRI,Reach-1         ,5355
     422     559     668     587     794    1074    1120
Boundary for River Rch & Prof#=FRANKS CREEK TRI,Reach-1         , 1
Up Type= 0
Dn Type= 3
Dn Slope=0.0065
Boundary for River Rch & Prof#=FRANKS CREEK TRI,Reach-1         , 2
Up Type= 0
Dn Type= 3
Dn Slope=0.0065
Boundary for River Rch & Prof#=FRANKS CREEK TRI,Reach-1         , 3
Up Type= 0
Dn Type= 3
Dn Slope=0.0065
Boundary for River Rch & Prof#=FRANKS CREEK TRI,Reach-1         , 4
Up Type= 0
Dn Type= 3
Dn Slope=0.0065
Boundary for River Rch & Prof#=FRANKS CREEK TRI,Reach-1         , 5
Up Type= 0
Dn Type= 3
Dn Slope=0.0065
Boundary for River Rch & Prof#=FRANKS CREEK TRI,Reach-1         , 6
Up Type= 0
Dn Type= 3
Dn Slope=0.0065
Boundary for River Rch & Prof#=FRANKS CREEK TRI,Reach-1         , 7
Up Type= 0
Dn Type= 3
Dn Slope=0.0065
DSS Import GetInterval= 0
DSS Import GetPeak= 0
DSS Import FillOption= 0

--- FRANKS CREEK TRIB 9.g01 (geometry) ---

Geom Title=Existing Conditions
Program Version=4.10

River Reach=FRANKS CREEK TRI,Reach-1
Reach XY= 30
      3577856.51     10160487.99      3577446.33     10160259.24
      3577316.99     10160076.08      3577328.28     10159922.43
      3577407.27     10159887.71       3577418.1     10159656.83
      3577315.53     10159445.44      3577334.37     10159375.06
      3577196.48     10159326.61      3577356.55     10159258.91
      3577107.25     10159174.39      3577152.19     10158955.83
      3576969.02      10158925.7        3576996.     10158825.31
      3576896.76     10158800.29      3576944.15     10158528.11
      3576846.39     10158474.61      3576764.36     10158508.06
      3576735.65     10158400.82      3576681.78     10158394.56
      3576622.33     10158256.89      3576696.32     10158104.29
      3576589.01     10158097.38      3576554.04     10157985.64
      3576465.52     10157948.37      3576519.94     10157781.84
      3576468.28     10157643.09      3576361.52     10157421.99
      3576216.87      10157414.8      3576062.11     10157061.64

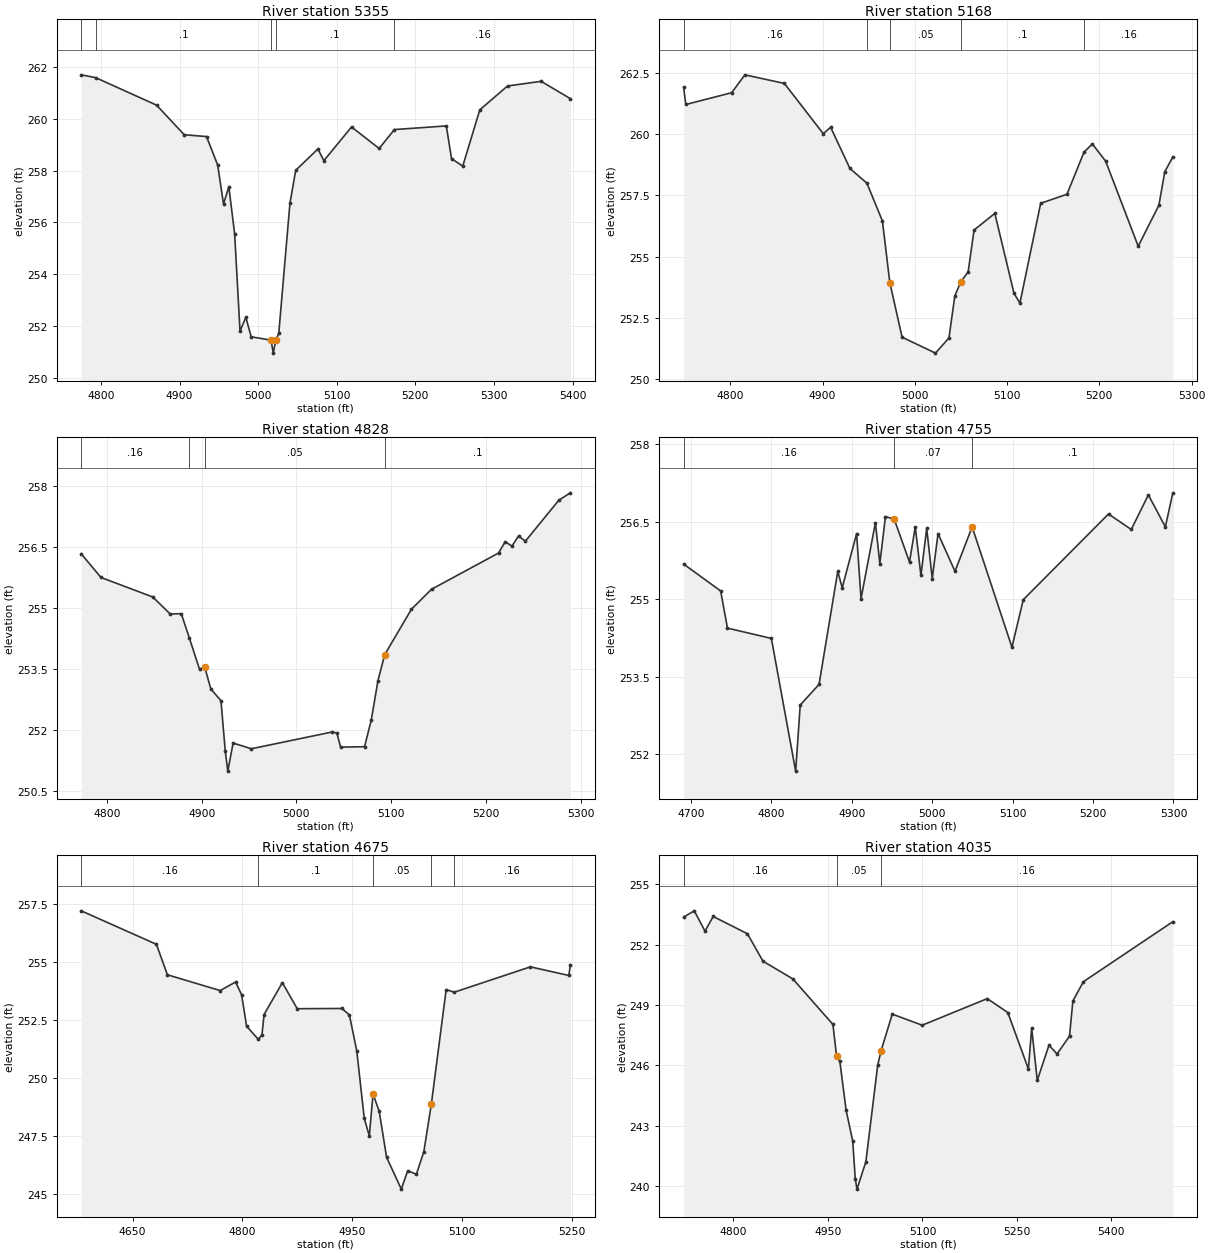
Type RM Length L Ch R = 1 ,5355    ,187,187,187
BEGIN DESCRIPTION:
FRANKS CREEK TRIB 9 8.0
END DESCRIPTION:
XS GIS Cut Line= 3
      3577977.96     10160292.08      3577767.34     10160483.32
      3577546.14     10160738.77
#Sta/Elev= 30
  4774.9  261.69  4793.3  261.58  4870.8  260.52  4905.9  259.38  4934.3  259.31
  4948.5  258.21  4955.9  256.71  4962.7  257.37  4970.1  255.55  4976.9  251.81
  4984.3  252.34  4991.1  251.59  5016.4  251.46  5019.2  250.96  5022.4  251.46
  5026.2  251.72  5040.4  256.73  5047.8  258.01    5076  258.83  5083.6  258.38
  5118.8  259.68  5153.9  258.85  5173.4  259.58  5239.4  259.72    5246  258.46
  5260.3  258.17    5282  260.34  5317.3  261.26    5360  261.44  5397.3  260.77
#Mann= 5 ,-1 , 0
  4774.9     .16       0  4793.3      .1       0  5016.4     .07       0
  5022.4      .1       0  5173.4     .16       0
Bank Sta=5016.4,5022.4
XS Rating Curve= 0 ,0
Exp/Cntr=0.3,0.1

Type RM Length L Ch R = 1 ,5168    ,340,340,340
BEGIN DESCRIPTION:
Mapping XS f0d9100c
END DESCRIPTION:
XS GIS Cut Line= 2
      3577799.59     10160176.18      3577470.19     10160591.51
#Sta/Elev= 30
  4749.5  261.91  4751.8  261.21  4801.5  261.69  4815.9  262.42  4858.6  262.07
  4900.8  260.02  4908.8  260.28  4929.7   258.6  4948.1     258  4964.9  256.46
  4972.9  253.95  4986.2  251.72  5022.4  251.07    5037  251.69  5043.4  253.41
    5050  253.99  5057.8  254.38  5064.2  256.09  5086.7  256.77  5107.5  253.51
  5113.9  253.11  5136.4  257.18  5164.9  257.55  5183.4  259.27  5192.4   259.6
  5206.8   258.9  5242.1  255.43  5264.5   257.1  5270.9  258.47  5279.6  259.07
#Mann= 5 ,-1 , 0
  4749.5     .16       0  4948.1      .1       0  4972.9     .05       0
    5050      .1       0  5183.4     .16       0
Bank Sta=4972.9,5050
XS Rating Curve= 0 ,0
Exp/Cntr=0.3,0.1

Type RM Length L Ch R = 1 ,4828    ,73,73,73
BEGIN DESCRIPTION:
Mapping XS aba64151
END DESCRIPTION:
XS GIS Cut Line= 3
      3577609.89     10160080.53      3577351.17      10160179.5
      3577182.76     10160349.64
#Sta/Elev= 30
  4772.9  256.33  4793.7  255.75  4848.4  255.27  4866.9  254.85  4878.5  254.86
  4886.9  254.27  4897.8  253.49  4903.2  253.55  4909.7  253.01  4920.4  252.72
  4924.9  251.49  4927.6  250.99  4933.2  251.68  4952.5  251.54  5037.4  251.95
  5042.7  251.93  5046.7  251.58    5072  251.59  5079.1  252.25  5086.1  253.21
  5093.2  253.85  5121.5  254.97  5142.7  255.46  5213.4  256.35  5220.5  256.63
  5227.5  256.52  5234.6  256.77  5241.7  256.64  5277.1  257.65  5289.3  257.83
#Mann= 4 ,-1 , 0
  4772.9     .16       0  4886.9      .1       0  4903.2     .05       0
  5093.2      .1       0
Bank Sta=4903.2,5093.2
XS Rating Curve= 0 ,0
Exp/Cntr=0.3,0.1

Type RM Length L Ch R = 1 ,4755    ,80,80,80
BEGIN DESCRIPTION:
Mapping XS cdb33d1b
END DESCRIPTION:
XS GIS Cut Line= 3
      3577622.04     10159969.41      3577384.16     10160073.59
      3577134.14     10160316.67
#Sta/Elev= 30
  4690.8  255.68  4736.8  255.16  4745.3  254.44  4799.9  254.24  4830.1  251.67
  4835.8  252.95  4859.2  253.35  4882.5  255.54    4888  255.22  4905.9  256.27
  4911.4  255.01  4929.3  256.48  4934.8  255.69  4941.8   256.6  4952.7  256.55
  4971.7  255.72  4978.9   256.4  4985.9  255.46  4993.1  256.37    5000   255.4
  5007.2  256.27  5028.3  255.54  5049.6   256.4  5099.1  254.07  5113.2  254.99
  5219.2  256.65  5247.5  256.35  5268.8  257.02  5289.9   256.4  5299.2  257.06
#Mann= 3 , 0 , 0
  4690.8     .16       0  4952.7     .07       0  5049.6      .1       0
Bank Sta=4952.7,5049.6
XS Rating Curve= 0 ,0
Exp/Cntr=0.3,0.1

Type RM Length L Ch R = 1 ,4675    ,640,640,640
BEGIN DESCRIPTION:
FRANKS CREEK TRIB 9 7.0
END DESCRIPTION:
XS GIS Cut Line= 3
      3577694.41     10159870.91      3577486.09     10160009.79
      3577075.27     10160087.13
#Sta/Elev= 30
  4579.8   257.2  4682.5  255.76  4697.5  254.45  4769.6  253.77  4790.7  254.14
  4798.9  253.59  4805.7  252.24  4821.5  251.68  4826.7  251.86  4829.6  252.74
  4854.6  254.11  4874.9  252.99    4936     253  4946.2  252.72  4956.3  251.17
  4966.5  248.27  4973.4  247.52  4978.5  249.32  4986.9  248.58    4997   246.6
  5017.1  245.23  5025.9  246.02  5037.7  245.87  5047.9  246.84  5058.1  248.87
  5078.4  253.81  5089.5   253.7  5193.5  254.79    5246  254.42  5248.2  254.88
#Mann= 5 ,-1 , 0
  4579.8     .16       0  4821.5      .1       0  4978.5     .05       0
  5058.1      .1       0  5089.5     .16       0
Bank Sta=4978.5,5058.1
XS Rating Curve= 0 ,0
Exp/Cntr=0.3,0.1

Type RM Length L Ch R = 1 ,4035    ,921,921,921
BEGIN DESCRIPTION:
FRANKS CREEK TRIB 9 6.0
END DESCRIPTION:
XS GIS Cut Line= 3
      3577633.67     10159410.83       3577436.3     10159487.32
      3576896.43      10159653.7
#Sta/Elev= 30
  4720.9  253.37  4737.8  253.68  4754.8  252.67  4767.8   253.4  4822.2  252.54
  4846.8  251.18  4894.2   250.3  4957.9  248.04  4963.7  246.46  4968.9   246.2
  4978.8  243.78  4989.3  242.25  4993.4  240.36  4996.1  239.86  5010.2  241.22
    5029  246.02  5034.3  246.73  5052.1  248.55  5099.6     248  5202.9  249.32
  5235.5  248.63  5268.2  245.83  5273.4  247.86  5282.3  245.26  5300.9  247.01
  5313.7  246.57  5333.5  247.46  5338.8   249.2  5355.5  250.16  5497.5  253.14
#Mann= 3 , 0 , 0
  4720.9     .16       0  4963.7     .05       0  5034.3     .16       0
Bank Sta=4963.7,5034.3
XS Rating Curve= 0 ,0
Exp/Cntr=0.3,0.1

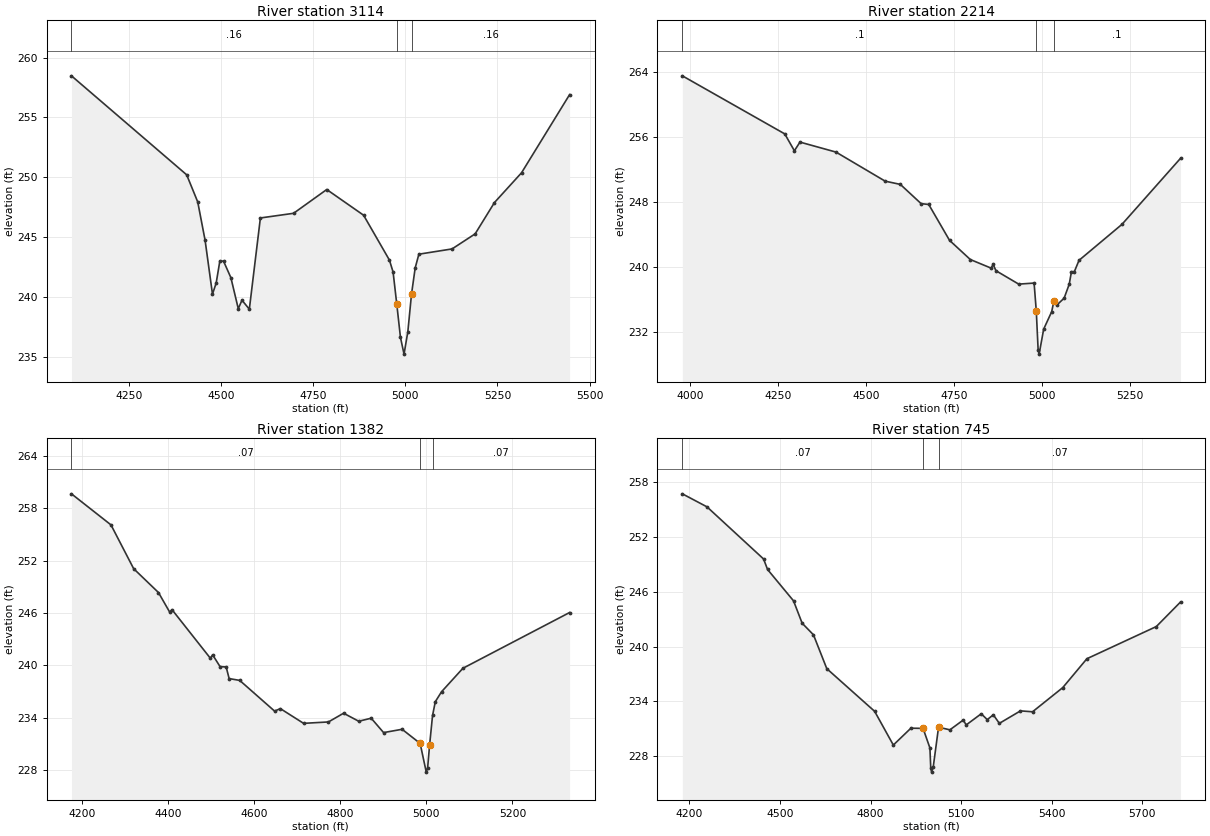
Type RM Length L Ch R = 1 ,3114    ,900,900,900
BEGIN DESCRIPTION:
FRANKS CREEK TRIB 9 5.0
END DESCRIPTION:
XS GIS Cut Line= 3
      3578054.65     10159076.63      3577014.68     10159086.45
      3576717.83     10159180.81
#Sta/Elev= 30
  4094.2  258.48  4406.8   250.2  4436.8  247.93  4456.8  244.72  4476.8  240.22
  4486.8  241.14  4496.8  242.99  4506.8  242.98  4526.8  241.59  4546.8     239
  4556.8  239.71  4576.8  238.96  4606.8  246.59  4696.8  246.98  4786.8  248.97
  4886.8  246.82  4956.8  243.07  4966.8  242.07  4976.8  239.38  4986.8   236.6
  4996.5   235.2  5006.8  237.07  5016.8  240.22  5026.8  242.42  5036.8  243.56
  5126.8     244  5189.4  245.26  5241.8  247.88  5315.3  250.37  5445.7  256.91
#Mann= 3 , 0 , 0
  4094.2     .16       0  4976.8     .05       0  5016.8     .16       0
Bank Sta=4976.8,5016.8
XS Rating Curve= 0 ,0
Exp/Cntr=0.3,0.1

Type RM Length L Ch R = 1 ,2214    ,832,832,832
BEGIN DESCRIPTION:
FRANKS CREEK TRIB 9 3.0
END DESCRIPTION:
XS GIS Cut Line= 3
      3577815.91     10158000.27      3577017.34     10158455.97
      3576622.38     10158755.44
#Sta/Elev= 30
  3978.5  263.55  4269.4   256.4  4296.8  254.32  4312.6  255.39  4414.9  254.16
  4554.6  250.58  4597.8  250.18  4656.8  247.81  4678.4  247.71  4737.5  243.29
  4796.5  240.93  4855.6  239.87  4861.3  240.33  4869.4  239.55    4934   237.9
  4977.7  238.03  4983.9   234.6  4989.2  229.78    4992  229.28  5004.9  232.36
  5027.6   234.5  5033.9  235.79  5042.2  235.32    5063  236.17  5077.5  237.89
  5083.8  239.43  5092.1  239.44  5105.3  240.83  5227.3  245.26  5393.6  253.39
#Mann= 3 , 0 , 0
  3978.5      .1       0  4983.9     .05       0  5033.9      .1       0
Bank Sta=4983.9,5033.9
XS Rating Curve= 0 ,0
Exp/Cntr=0.3,0.1

Type RM Length L Ch R = 1 ,1382    ,637,637,637
BEGIN DESCRIPTION:
FRANKS CREEK TRIB 9 2.0
END DESCRIPTION:
XS GIS Cut Line= 3
      3577269.03      10157692.1      3576774.22     10157859.36
      3576379.34     10158356.12
#Sta/Elev= 30
    4176  259.65  4267.8  256.09  4320.5  251.07  4378.1  248.34  4404.2  246.09
  4409.5  246.38  4498.6  240.81  4503.9   241.2  4521.1  239.85  4535.3  239.81
  4542.2  238.48  4566.8  238.27  4647.8  234.75  4661.1  235.04  4715.1  233.35
  4772.8  233.51    4808  234.51  4843.2  233.59  4872.1  233.94  4900.9  232.29
  4943.9  232.67  4985.8  231.05    5000  227.76  5003.2  228.26  5007.8  230.89
  5014.6  234.25    5021  235.83  5035.5  236.97  5085.1  239.66  5332.9  246.05
#Mann= 3 ,-1 , 0
    4176     .07       0  4985.8    .035       0  5014.6     .07       0
Bank Sta=4985.8,5007.8
XS Rating Curve= 0 ,0
Exp/Cntr=0.3,0.1

Type RM Length L Ch R = 1 ,745     ,0,0,0
BEGIN DESCRIPTION:
FRANKS CREEK TRIB 9 1.0
END DESCRIPTION:
XS GIS Cut Line= 3
      3577156.23     10157249.37      3576282.96       10157654.
      3576292.11     10158341.69
#Sta/Elev= 30
  4176.5  256.75  4258.2  255.32  4445.6   249.6  4458.8  248.45  4544.8  245.01
  4573.3  242.56  4610.9  241.28    4655  237.57  4813.5  232.89  4875.4  229.19
  4933.6  231.04  4973.9  231.02  4996.6  228.87  4999.3  226.72  5002.1  226.22
  5007.8  226.83  5025.2  231.15  5062.8  230.86  5106.8  231.93  5116.9   231.4
  5166.6  232.62  5186.6  231.98  5206.6  232.51  5226.6  231.57  5296.6  232.94
  5336.6  232.84  5436.6  235.49  5516.6  238.66  5746.6  242.19  5826.7  244.88
#Mann= 3 , 0 , 0
  4176.5     .07       0  4973.9    .035       0  5025.2     .07       0
Bank Sta=4973.9,5025.2
XS Rating Curve= 0 ,0
Exp/Cntr=0.3,0.1

Chan Stop Cuts=-1
Use User Specified Reach Order=0
Composite Channel Slope=5