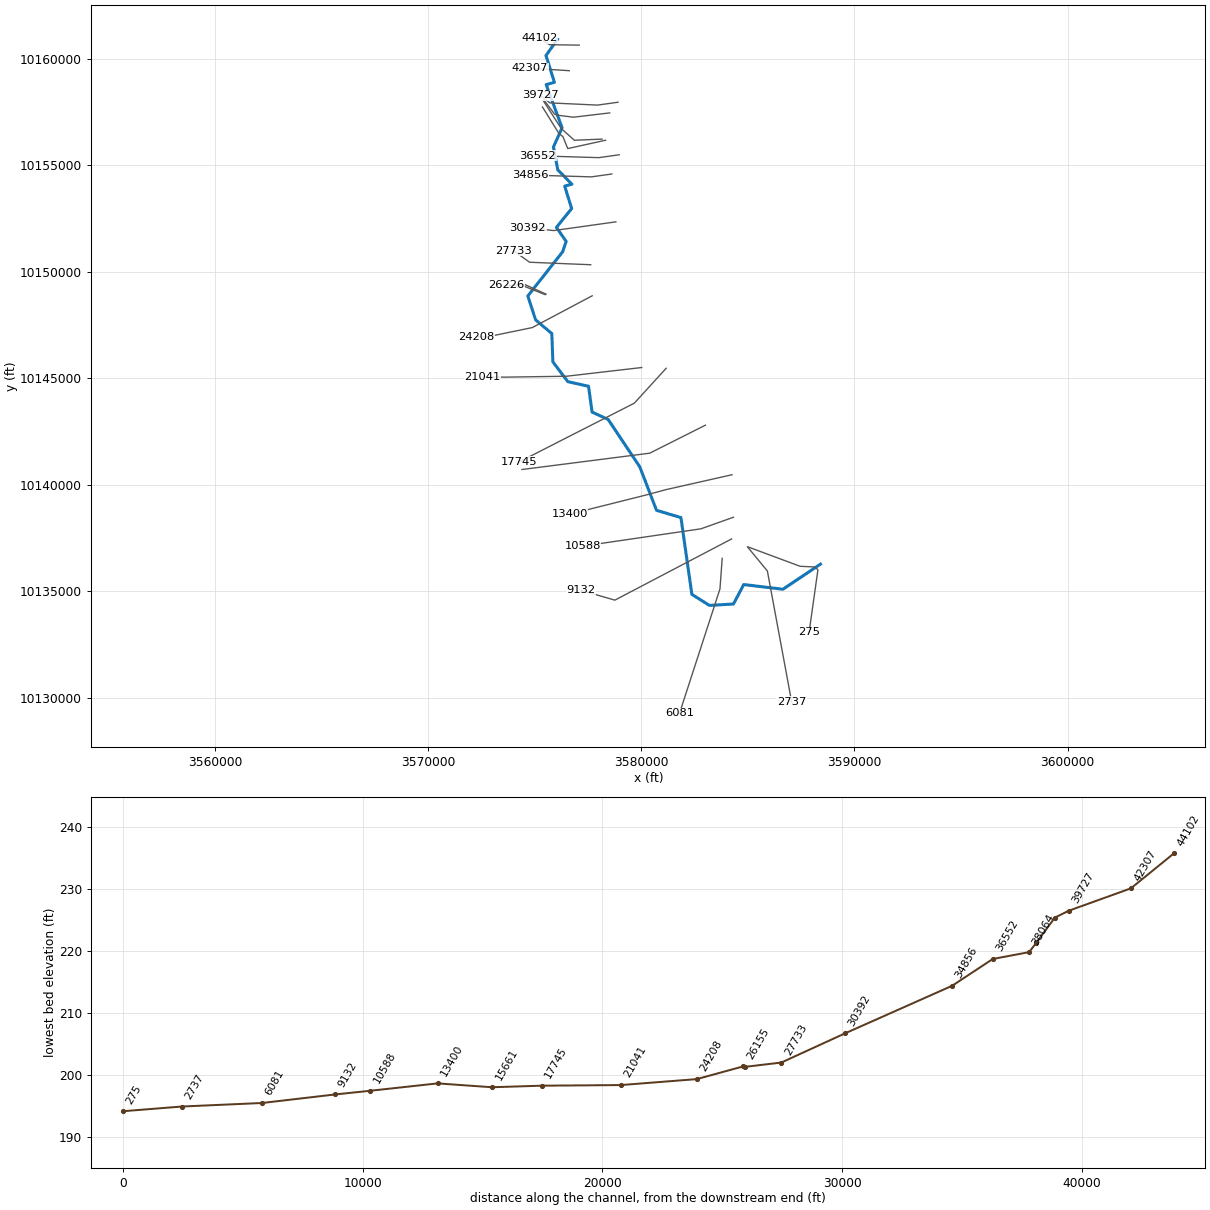
--- FRANKS CREEK.prj (project) ---

Proj Title=FRANKS CREEK Base Level Engineering
Current Plan=p01
Default Exp/Contr=0.3,0.1
English Units
Geom File=g01
Flow File=f01
Plan File=p01
Y Axis Title=Elevation
X Axis Title(PF)=Main Channel Distance
X Axis Title(XS)=Station
BEGIN DESCRIPTION:
FRANKS CREEK
END DESCRIPTION:
DSS Export Rating Curves= 0
DSS Export Rating Curve Sorted= 0
DSS Export Volume Flow Curves= 0
DXF OffsetX= 0
DXF OffsetY= 0
DXF ScaleX= 1
DXF ScaleY= 10

--- FRANKS CREEK.p01 (plan) ---

Plan Title=Multiple Run
Short Identifier=Multiple
Geom File=g01
Flow File=f01
Subcritical Flow
K Sum by GR= 0
Std Step Tol= 0.01
Critical Tol= 0.01
Num of Std Step Trials= 20
Max Error Tol= 0.3
Flow Tol Ratio= 0.001
Split Flow NTrial= 30
Split Flow Tol= 0.02
Split Flow Ratio= 0.02
Log Output Level= 0
Friction Slope Method= 1
Unsteady Friction Slope Method= 2
Unsteady Bridges Friction Slope Method= 1
Parabolic Critical Depth
Global Vel Dist=  1 , 1 , 1
Global Log Level= 0
CheckData=True
Encroach Param= -1, 0, 0, 0
BEGIN DESCRIPTION:
Multiple Run
END DESCRIPTION:

--- FRANKS CREEK.f01 (steady flow) ---

Flow Title=Multiple
Program Version=4.10
Number of Profiles= 7
Profile Names=10-year,25-year,50-year,1pct_min,100-year,1pct_plu,500-year
River Rch & RM=FRANKS CREEK,Reach-1         ,44102
     574     746     879     600    1017    1434    1350
River Rch & RM=FRANKS CREEK,Reach-1         ,39727
     928    1206    1420     969    1642    2316    2178
River Rch & RM=FRANKS CREEK,Reach-1         ,38356
     928    1206    1420     969    1642    2316    2178
River Rch & RM=FRANKS CREEK,Reach-1         ,30392
    1055    1455    1788    1606    2172    2938    3214
River Rch & RM=FRANKS CREEK,Reach-1         ,27733
    1297    1684    1982    1353    2293    3233    3040
River Rch & RM=FRANKS CREEK,Reach-1         ,21041
    2218    2878    3385    2311    3916    5522    5187
River Rch & RM=FRANKS CREEK,Reach-1         ,17745
    2449    3178    3737    2551    4323    6096    5725
River Rch & RM=FRANKS CREEK,Reach-1         ,13400
    2593    3364    3955    2700    4576    6453    6060
River Rch & RM=FRANKS CREEK,Reach-1         ,6081
    2763    3585    4215    2877    4876    6875    6456
Boundary for River Rch & Prof#=FRANKS CREEK,Reach-1         , 1
Up Type= 0
Dn Type= 1
Dn Known WS=196.93
Boundary for River Rch & Prof#=FRANKS CREEK,Reach-1         , 2
Up Type= 0
Dn Type= 1
Dn Known WS=197.57
Boundary for River Rch & Prof#=FRANKS CREEK,Reach-1         , 3
Up Type= 0
Dn Type= 1
Dn Known WS=198.03
Boundary for River Rch & Prof#=FRANKS CREEK,Reach-1         , 4
Up Type= 0
Dn Type= 1
Dn Known WS=197.83
Boundary for River Rch & Prof#=FRANKS CREEK,Reach-1         , 5
Up Type= 0
Dn Type= 1
Dn Known WS=198.48
Boundary for River Rch & Prof#=FRANKS CREEK,Reach-1         , 6
Up Type= 0
Dn Type= 1
Dn Known WS=199.24
Boundary for River Rch & Prof#=FRANKS CREEK,Reach-1         , 7
Up Type= 0
Dn Type= 1
Dn Known WS=199.57
DSS Import GetInterval= 0
DSS Import GetPeak= 0
DSS Import FillOption= 0

--- FRANKS CREEK.g01 (geometry) ---

Geom Title=Existing Conditions
Program Version=4.10

River Reach=FRANKS CREEK    ,Reach-1
Reach XY= 30
       3576065.2     10160916.54      3575523.98     10160152.29
       3575919.3     10158892.74      3575532.17     10158786.94
      3576278.31     10156758.12      3575873.39     10155857.69
      3576075.05      10154783.5      3576739.37     10154110.69
      3576401.45     10154016.82      3576727.74     10152963.81
      3576013.23     10152082.23      3576469.99     10151419.92
      3576306.97     10150939.37      3574671.61     10148862.14
      3575036.19     10147735.84      3575796.61     10147096.95
      3575846.08     10145766.57       3576547.1     10144837.29
      3577519.32     10144620.28      3577687.44     10143406.68
      3578441.34      10143061.5      3579924.85     10140836.53
      3580710.09     10138795.01      3581856.53     10138454.05
      3582369.47     10134846.65      3583194.44     10134328.66
      3584320.94     10134394.45      3584803.59     10135307.85
      3586641.97      10135087.7      3588401.52     10136266.52

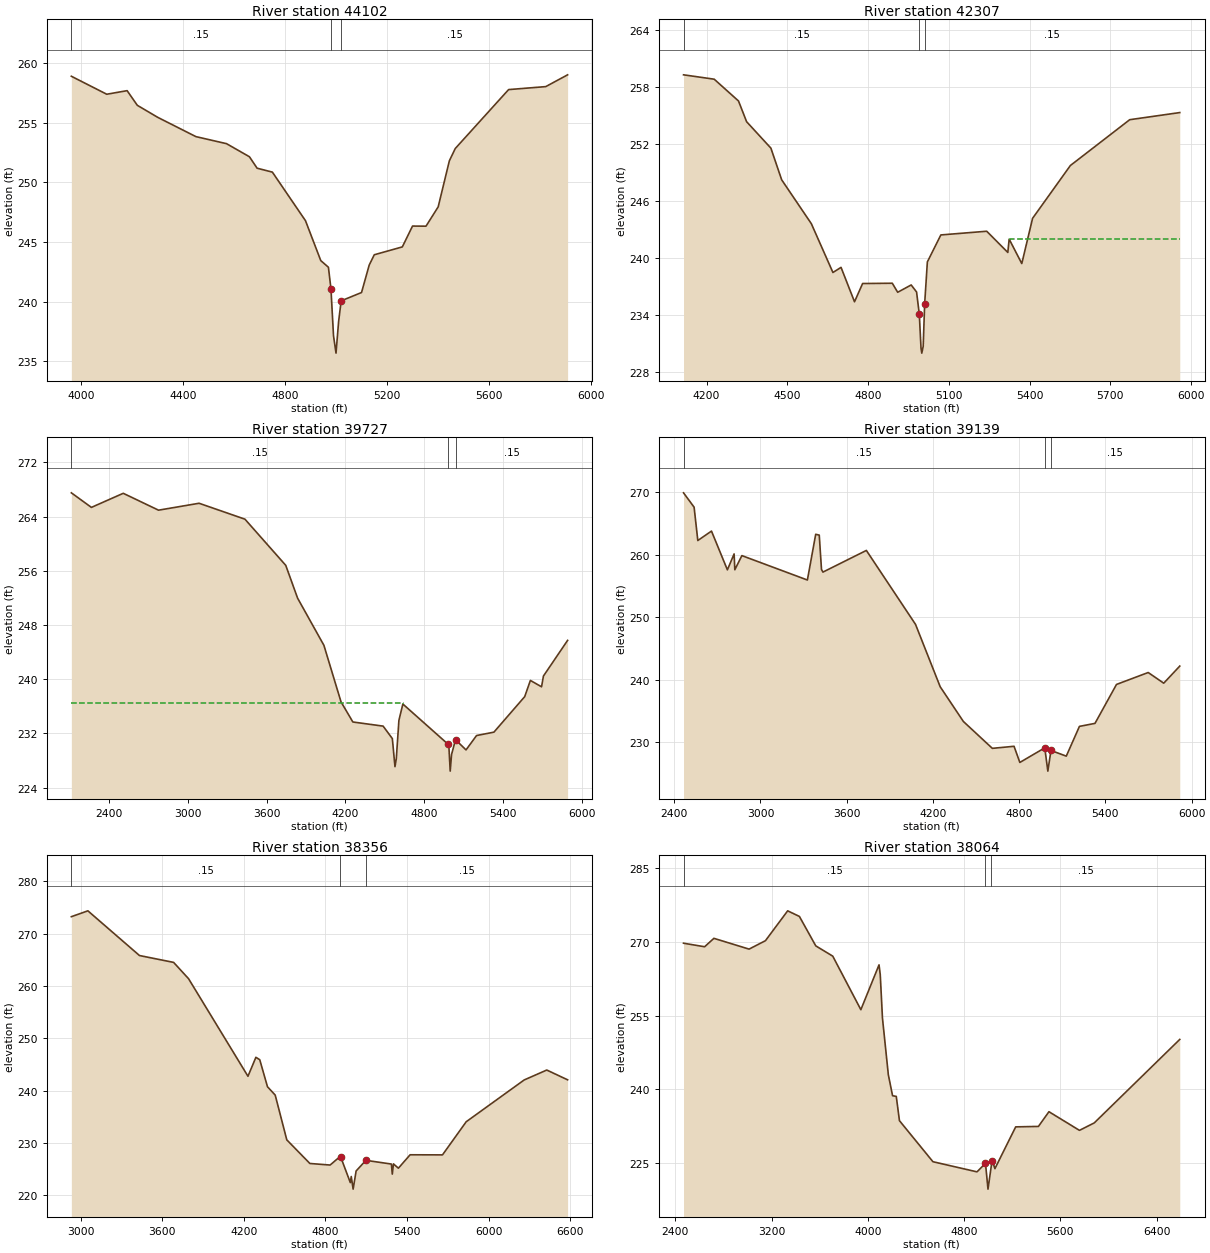
Type RM Length L Ch R = 1 ,44102   ,1795,1795,1795
BEGIN DESCRIPTION:
FRANKS CREEK 29.0
END DESCRIPTION:
XS GIS Cut Line= 3
      3577081.02     10160640.01      3575692.13     10160660.84
      3575219.87     10160959.48
#Sta/Elev= 30
  3960.8  258.92  4099.7  257.41  4179.7  257.71  4219.7  256.48  4299.8  255.47
  4449.8  253.85  4569.8  253.26  4659.8  252.16  4689.8   251.2  4749.8  250.87
  4879.8  246.79  4939.8  243.44  4969.8  242.88  4979.8  241.06  4989.8  237.12
  4999.6  235.67  5009.8  238.32  5019.8  240.06  5099.8  240.76  5129.8  243.06
  5149.8  243.93  5259.9  244.59  5299.9  246.34  5352.8  246.33  5400.6  247.95
  5444.5  251.82  5467.6  252.85    5677   257.8  5822.8  258.05  5908.6  259.04
#Mann= 3 , 0 , 0
  3960.8     .15       0  4979.8     .05       0  5019.8     .15       0
Bank Sta=4979.8,5019.8
XS Rating Curve= 0 ,0
Exp/Cntr=0.3,0.1

Type RM Length L Ch R = 1 ,42307   ,2580,2580,2580
BEGIN DESCRIPTION:
FRANKS CREEK 25.0
END DESCRIPTION:
XS GIS Cut Line= 3
      3576615.78     10159438.62      3576428.24     10159452.51
      3574776.57     10159556.61
#Sta/Elev= 30
  4114.6   259.3  4228.6  258.84  4318.8  256.55  4348.9  254.37  4439.1  251.59
  4479.1  248.26  4589.4  243.64  4669.5  238.51  4699.6  239.05  4749.7  235.43
  4779.7  237.35    4890  237.38    4910  236.43  4960.1   237.2  4980.1  236.46
  4990.2  234.14  4996.7  230.53  4999.5  230.03  5004.7  230.74  5010.2  235.24
  5020.2  239.62  5070.3  242.46  5240.6  242.85    5319  240.62    5324  242.02
  5370.9  239.45    5411  244.21  5551.3  249.76  5771.7  254.58  5957.6  255.33
#Mann= 3 , 0 , 0
  4114.6     .15       0  4990.2     .05       0  5010.2     .15       0
#XS Ineff= 2 , 0
                         5326.14          242.02
Permanent Ineff=
       F       F
Bank Sta=4990.2,5010.2
XS Rating Curve= 0 ,0
Exp/Cntr=0.3,0.1

Type RM Length L Ch R = 1 ,39727   ,588,588,588
BEGIN DESCRIPTION:
FRANKS CREEK 24.0
END DESCRIPTION:
XS GIS Cut Line= 4
      3578903.08     10157958.95       3577944.3     10157824.34
      3575705.55     10157928.03      3575263.14     10158281.01
#Sta/Elev= 30
  2115.2   267.5  2267.7  265.35    2510  267.43  2778.4  264.94    3087  265.96
    3436  263.61  3746.3   256.8  3836.4  251.96  4036.6     245  4166.7  236.66
  4256.8  233.69  4487.1  233.08  4557.2  231.24  4577.2   227.1  4587.2  228.25
  4607.2  233.94  4637.2  236.34  4977.6  230.47  4987.6  229.98  4997.4  226.44
  5007.6  228.88  5037.7  231.08  5117.8  229.57  5197.8  231.69  5329.9  232.19
  5564.2  237.43  5607.4  239.82  5692.3  238.88  5706.7  240.47  5890.5  245.73
#Mann= 3 , 0 , 0
  2115.2     .15       0  4977.6     .05       0  5037.7     .15       0
#XS Ineff= 2 , 0
         4640.91  236.46
Permanent Ineff=
       F       F
Bank Sta=4977.6,5037.7
XS Rating Curve= 0 ,0
Exp/Cntr=0.3,0.1

Type RM Length L Ch R = 1 ,39139   ,783,783,783
BEGIN DESCRIPTION:
Mapping XS 465c1b0b
END DESCRIPTION:
XS GIS Cut Line= 5
       3578515.3     10157458.51      3576816.39     10157255.75
      3576053.33     10157350.37      3575928.36     10157400.35
      3575421.68     10158068.12
#Sta/Elev= 30
  2464.8  269.91  2538.5  267.61  2564.3  262.27  2659.4  263.78  2770.1  257.57
  2816.8  260.12  2821.8  257.59  2870.9  259.85  3326.7  255.94  3384.5  263.27
  3409.2  263.13  3424.8  257.64  3434.8  257.21    3737  260.68  4079.1  248.83
  4250.6  238.84  4411.8  233.28  4613.4  228.97  4764.5   229.3  4804.8  226.71
  4978.3  229.05  4999.6  225.32  5021.4  228.63  5127.9  227.72  5219.5  232.49
  5327.6  232.97  5477.3  239.21  5697.9  241.12    5806  239.41  5917.5  242.15
#Mann= 3 , 0 , 0
  2464.8     .15       0  4978.3     .05       0  5021.4     .15       0
Bank Sta=4978.3,5021.4
XS Rating Curve= 0 ,0
Exp/Cntr=0.3,0.1

Type RM Length L Ch R = 1 ,38356   ,292,292,292
BEGIN DESCRIPTION:
Mapping XS 3f600d4a
END DESCRIPTION:
XS GIS Cut Line= 4
      3578153.51     10156228.03      3576854.51       10156173.
        3576243.     10156720.44      3575413.52     10158004.63
#Sta/Elev= 30
  2931.8  273.25  3053.3  274.37  3432.9  265.83  3683.9  264.52    3794   261.4
  4230.7  242.77    4289  246.39  4317.4  245.93  4374.2  240.77  4431.1  239.17
  4516.3  230.62    4686  226.11  4834.8  225.81  4905.8  227.38  4912.5  227.37
  4983.6  222.45  4990.3  223.62  5004.2  221.21  5026.2  224.68  5098.1  226.71
  5285.5     226  5292.2  224.08  5300.7  226.03    5337  225.21  5423.2  227.77
  5661.3  227.75  5835.8  234.08    6262  242.06  6428.3  243.96  6581.5  242.09
#Mann= 3 ,-1 , 0
  2931.8     .15       0  4905.8     .05       0  5098.1     .15       0
Bank Sta=4912.5,5098.1
XS Rating Curve= 0 ,0
Exp/Cntr=0.3,0.1

Type RM Length L Ch R = 1 ,38064   ,1512,1512,1512
BEGIN DESCRIPTION:
FRANKS CREEK 23.0
END DESCRIPTION:
XS GIS Cut Line= 5
      3578318.86     10156174.37      3576544.57     10155782.01
      3576316.89     10156342.37       3576127.9     10156495.56
      3575357.11     10157735.07
#Sta/Elev= 30
  2468.2  269.72  2643.5     269  2720.9  270.71  3013.1  268.52  3149.2  270.23
    3334   276.3  3431.5  275.16  3567.5  269.18  3708.7  267.09  3942.3  256.21
  4093.3  265.32  4103.5  263.32  4121.9   254.5  4170.7  242.99  4205.9  238.73
  4236.7  238.59  4263.1  233.66  4541.4  225.32  4907.8  223.26  4978.2     225
  4999.1  219.75  5027.8  224.69  5035.7  225.48  5056.5  223.91  5229.3   232.4
  5418.2  232.49  5505.7  235.48  5759.4  231.69  5882.5  233.21  6593.1  250.17
#Mann= 3 ,-1 , 0
  2468.2     .15       0  4978.2     .05       0  5027.8     .15       0
Bank Sta=4978.2,5035.7
XS Rating Curve= 0 ,0
Exp/Cntr=0.3,0.1

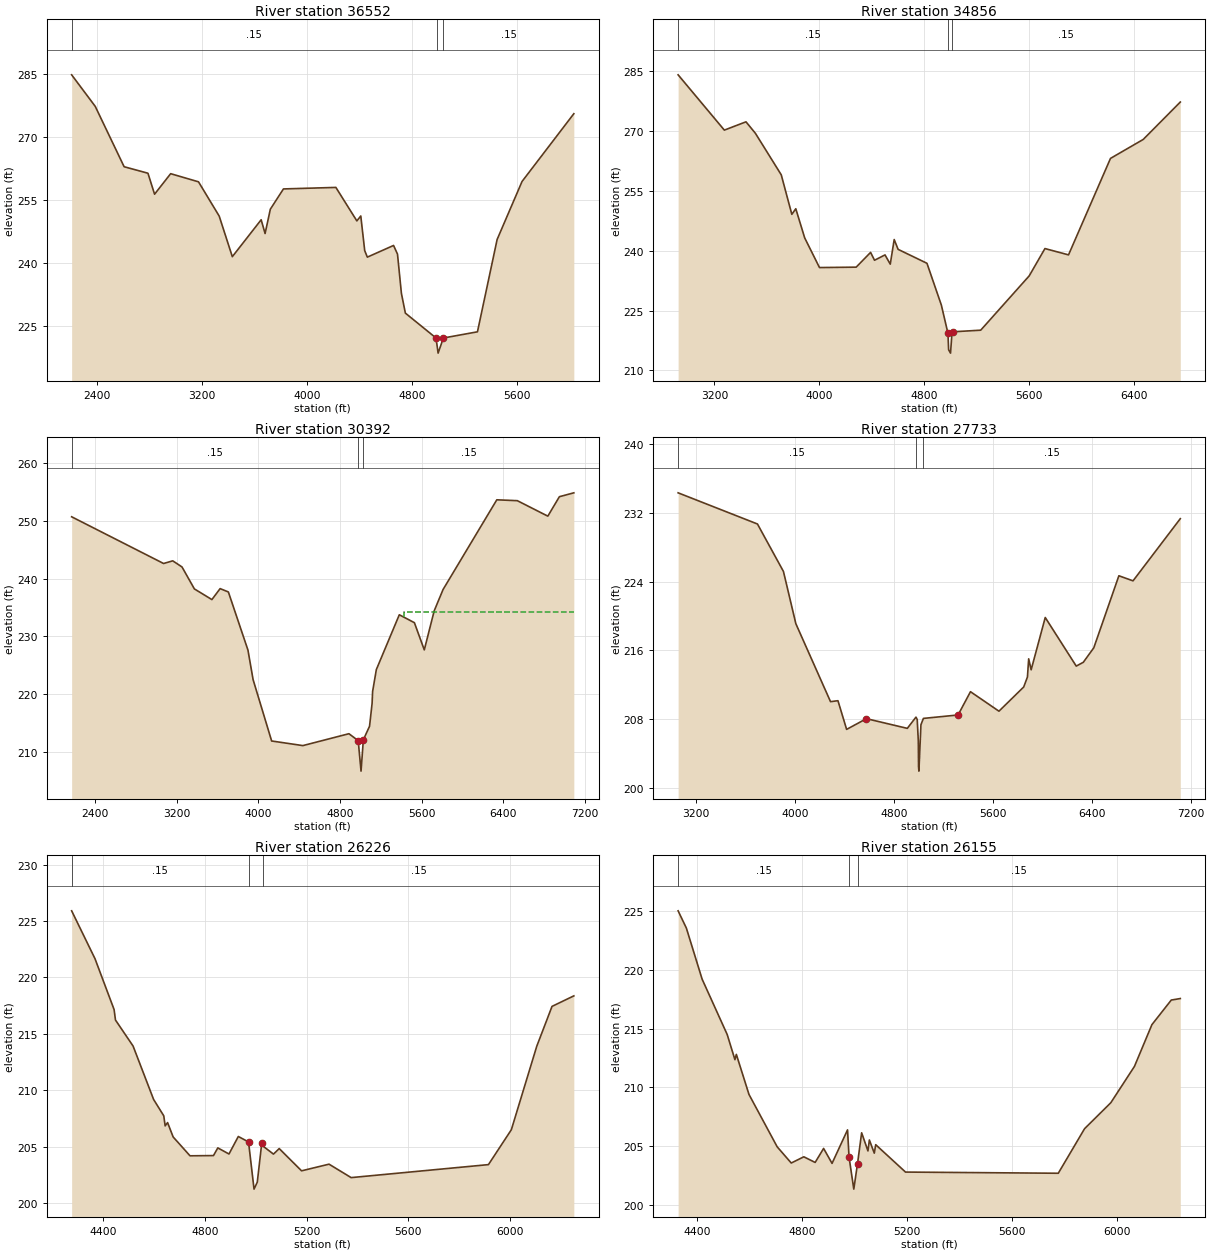
Type RM Length L Ch R = 1 ,36552   ,1696,1696,1696
BEGIN DESCRIPTION:
FRANKS CREEK 22.0
END DESCRIPTION:
XS GIS Cut Line= 3
      3578958.75     10155491.22      3577999.95     10155356.61
      3575136.94      10155442.3
#Sta/Elev= 30
  2203.5  284.72  2383.6  277.23    2604   262.9  2785.8  261.36  2836.3  256.38
  2959.1  261.25  3171.6  259.32  3329.6  251.18  3429.7  241.55  3649.8  250.31
  3679.8  247.04  3719.8  252.82  3819.8  257.63    4220  257.99  4380.1  250.04
  4410.1  251.21  4440.1  242.98  4460.1  241.44  4660.2  244.21  4690.2  242.16
  4720.2  232.82  4750.3  228.15  4980.4  222.34  4990.4   220.9  5000.1  218.65
  5040.4  222.24  5300.5  223.71  5450.6  245.63  5640.7   259.4    6036  275.49
#Mann= 3 ,-1 , 0
  2203.5     .15       0  4990.4     .05       0  5040.4     .15       0
Bank Sta=4980.4,5040.4
XS Rating Curve= 0 ,0
Exp/Cntr=0.3,0.1

Type RM Length L Ch R = 1 ,34856   ,4464,4464,4464
BEGIN DESCRIPTION:
FRANKS CREEK 21.0
END DESCRIPTION:
XS GIS Cut Line= 3
      3578611.53     10154588.45      3577652.73     10154453.83
      3574789.51     10154539.53
#Sta/Elev= 30
  2922.8  284.09  3275.6  270.23  3440.8  272.31  3512.1  269.46  3709.9  259.03
  3790.7  249.12  3820.9  250.52  3888.8  243.22  4001.7  235.78  4281.8  235.88
  4391.8  239.58  4421.9  237.61  4501.9  238.95  4541.9  236.63  4571.9   242.8
  4601.9  240.34    4822  236.85  4932.1  226.35  4982.1   219.3  4987.4  215.18
  5001.9  214.33  5012.1  219.03  5022.1  219.68  5232.2  220.08  5602.4   233.7
  5722.4  240.54  5902.5  238.96  6222.7  263.14  6472.8   267.9  6755.5  277.27
#Mann= 3 ,-1 , 0
  2922.8     .15       0  4982.1     .05       0  5012.1     .15       0
Bank Sta=4982.1,5022.1
XS Rating Curve= 0 ,0
Exp/Cntr=0.3,0.1

Type RM Length L Ch R = 1 ,30392   ,2659,2659,2659
BEGIN DESCRIPTION:
FRANKS CREEK 20.0
END DESCRIPTION:
XS GIS Cut Line= 3
       3578803.2     10152341.39      3575887.38     10151932.03
     3574665.464    10152063.593
#Sta/Elev= 30
  2168.8  250.71  3069.9  242.62  3159.5  243.08  3250.4  242.02  3371.6  238.22
  3543.2  236.37    3624  238.27  3704.8  237.69  3896.7  227.62  3947.2   222.5
  4128.9  211.88  4434.8  211.08  4886.3  213.14  4977.2  211.94    5005  206.66
  5027.7  212.09  5088.3  214.43  5113.2  218.38  5118.5  220.47    5155  224.25
    5380  233.74  5527.9  232.37  5624.9  227.66    5722  234.42  5808.8  238.11
  6335.5  253.65  6536.7   253.5  6835.6  250.82    6949  254.19  7090.5  254.86
#Mann= 3 , 0 , 0
  2168.8     .15       0  4977.2     .05       0  5027.7     .15       0
#XS Ineff= 2 , 0
                         5429.93          234.15
Permanent Ineff=
       F       F
Bank Sta=4977.2,5027.7
XS Rating Curve= 0 ,0
Exp/Cntr=0.3,0.1

Type RM Length L Ch R = 1 ,27733   ,1507,1507,1507
BEGIN DESCRIPTION:
FRANKS CREEK 19.0
END DESCRIPTION:
XS GIS Cut Line= 3
      3577622.73     10150327.51      3574754.12     10150444.33
      3574002.05    10150984.547
#Sta/Elev= 30
  3054.4  234.36  3695.6  230.73  3905.7   225.2  4005.8  219.12    4286  210.04
  4346.1  210.15  4416.2  206.81  4576.3  208.06  4906.6  206.93  4976.6  208.24
  4986.6  207.96  4995.4  205.48  4997.4  202.45  5000.2  201.95  5016.7  207.35
  5036.7  208.09  5316.9  208.49    5417   211.2  5647.2  208.93  5847.3  211.75
  5877.4  212.91  5887.4  215.03  5907.4  213.75  6021.3  219.84  6271.8  214.18
  6329.1  214.63  6413.6  216.31  6616.3   224.7  6730.7  224.11  7112.7  231.35
#Mann= 3 ,-1 , 0
  3054.4     .15       0  4976.6     .05       0  5036.7     .15       0
Bank Sta=4576.3,5316.9
XS Rating Curve= 0 ,0
Exp/Cntr=0.3,0.1

Type RM Length L Ch R = 1 ,26226   ,71,71,71
BEGIN DESCRIPTION:
Mapping XS bd26050d
END DESCRIPTION:
XS GIS Cut Line= 3
      3575525.74       10148946.      3574549.15     10149389.85
      3573646.31     10149358.63
#Sta/Elev= 30
    4275   225.9  4366.9  221.66    4442  217.16  4447.5  216.23  4516.7  213.93
  4597.5   209.2  4637.5  207.75    4643  206.86  4652.5  207.15  4674.4  205.88
  4740.8  204.21  4833.1  204.23  4850.2  204.91  4894.1  204.37  4930.8  205.92
    4971  205.44  4992.7  201.26  5005.5  201.88  5023.1  205.34  5028.6  205.06
  5069.2  204.36  5091.8  204.85  5179.7  202.88  5287.8  203.47  5374.8  202.28
  5915.1  203.43  6005.2  206.52  6105.2  213.91  6165.3  217.44  6251.1  218.37
#Mann= 3 ,-1 , 0
    4275     .15       0    4971     .05       0  5028.6     .15       0
Bank Sta=4971,5023.1
XS Rating Curve= 0 ,0
Exp/Cntr=0.3,0.1

Type RM Length L Ch R = 1 ,26155   ,1947,1947,1947
BEGIN DESCRIPTION:
Mapping XS 96774bba
END DESCRIPTION:
XS GIS Cut Line= 3
      3575477.09     10148925.18      3574520.12     10149310.67
      3573637.65     10149249.22
#Sta/Elev= 30
  4326.2  225.01  4357.7  223.54  4417.8   219.2  4513.5  214.49    4543  212.35
  4548.4   212.8  4596.7  209.39  4704.2  204.94  4757.9  203.56  4805.9  204.09
  4849.1  203.61  4881.4   204.8  4913.6  203.53  4972.7  206.38  4978.4  204.07
  4996.6  201.34  5010.8  203.51  5026.5  206.13  5050.6  204.59    5056  205.52
  5074.8   204.4  5080.2  205.12    5194  202.79  5776.9  202.69  5877.2  206.48
  5977.4  208.69  6067.6  211.78  6134.2  215.33    6208  217.42  6242.5  217.55
#Mann= 3 , 0 , 0
  4326.2     .15       0  4978.4     .05       0  5010.8     .15       0
Bank Sta=4978.4,5010.8
XS Rating Curve= 0 ,0
Exp/Cntr=0.3,0.1

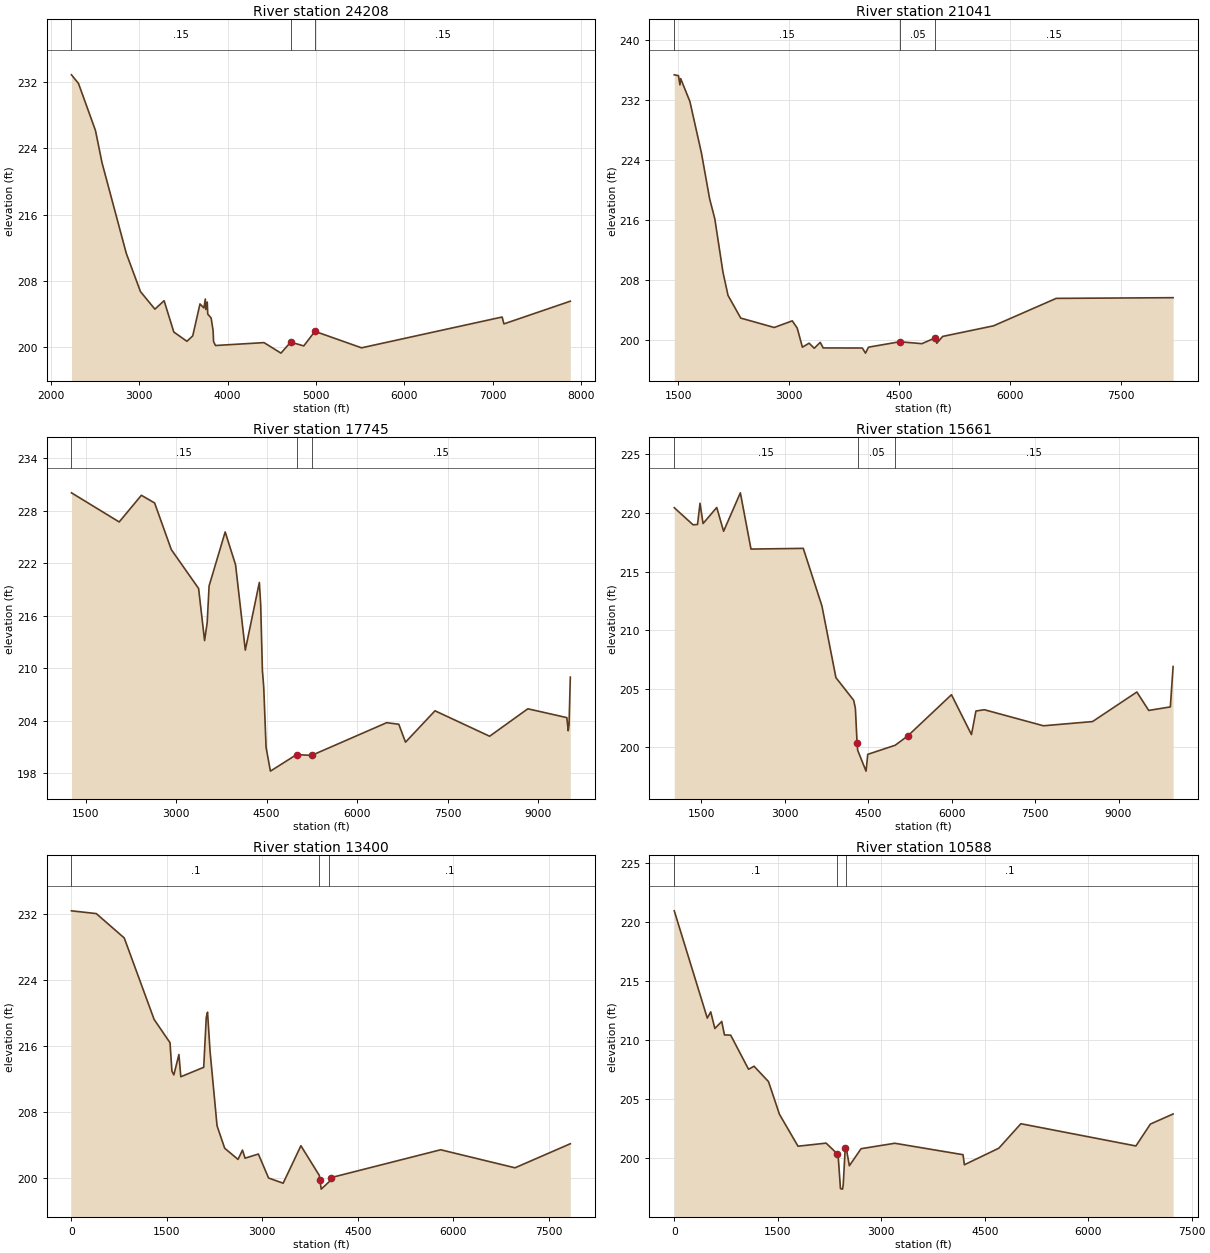
Type RM Length L Ch R = 1 ,24208   ,3167,3167,3167
BEGIN DESCRIPTION:
FRANKS CREEK 18.0
END DESCRIPTION:
XS GIS Cut Line= 4
      3577692.13     10148869.18      3574879.63     10147376.12
      3572783.68    10146943.477     3572252.665    10146944.942
#Sta/Elev= 30
  2231.7  232.88    2311  231.84  2503.5  226.16  2577.7  222.26  2852.2  211.33
  3012.9  206.71  3176.3  204.59  3280.6  205.61  3390.5  201.83  3538.7  200.71
  3604.7  201.36    3687  205.22  3730.9  204.74  3747.3  205.81  3752.9  204.55
  3769.2  205.45  3774.9  203.99  3813.2  203.52  3835.2  202.02  3840.9  200.67
  3862.8   200.2  4411.8  200.55  4603.8  199.28  4713.9  200.61  4862.2  200.15
  4988.4  201.91  5516.5  199.92  7108.4  203.64  7128.8  202.81  7880.7  205.55
#Mann= 3 , 0 , 0
  2231.7     .15       0  4713.9     .05       0  4988.4     .15       0
Bank Sta=4713.9,4988.4
XS Rating Curve= 0 ,0
Exp/Cntr=0.3,0.1

Type RM Length L Ch R = 1 ,21041   ,3296,3296,3296
BEGIN DESCRIPTION:
FRANKS CREEK 17.0
END DESCRIPTION:
XS GIS Cut Line= 4
      3580018.47     10145501.12      3576492.11     10145091.64
     3573639.925    10145049.598     3572541.815    10145057.471
#Sta/Elev= 30
  1445.6  235.32  1502.3  235.21  1522.5  233.98  1532.5  234.82  1658.1  231.76
  1814.4  224.91  1925.2  218.85  1995.6  216.17  2106.4  209.07  2174.9  205.99
  2347.2  202.98    2801  201.73  3046.3  202.61  3113.1  201.65  3183.6  199.11
  3274.2  199.64  3344.6  198.97  3425.2  199.75  3465.5  199.01  3996.3     199
    4039  198.32  4079.5  199.11  4502.4  199.83  4804.4  199.58  4985.6  200.35
  5005.7  199.63  5085.7  200.54  5775.7  201.95  6625.8   205.6  8211.1  205.69
#Mann= 3 , 0 , 0
  1445.6     .15       0  4502.4     .05       0  4985.6     .15       0
Bank Sta=4502.4,4985.6
XS Rating Curve= 0 ,0
Exp/Cntr=0.3,0.1

Type RM Length L Ch R = 1 ,17745   ,2084,2084,2084
BEGIN DESCRIPTION:
FRANKS CREEK 16.0
END DESCRIPTION:
XS GIS Cut Line= 3
      3581164.38     10145466.43      3579668.37     10143826.22
      3574280.91     10141075.84
#Sta/Elev= 30
  1265.7  230.05  2056.7  226.72  2424.3  229.77  2643.8  228.89  2920.2  223.56
  3372.8  219.11  3472.1  213.15  3515.2  215.21    3547  219.41  3813.7  225.58
  3985.9  221.81    4147  212.06  4379.7   219.8  4402.2  217.27  4430.3  209.77
  4452.6   207.8  4491.4  200.93  4563.4  198.22  4996.9  200.11    5247  200.02
  6490.5  203.76  6691.4  203.58  6802.5  201.53  7291.4  205.12  8197.1  202.21
  8830.3  205.35  9477.1  204.34  9499.6  202.84  9513.6  203.56  9534.6  208.97
#Mann= 3 , 0 , 0
  1265.7     .15       0  4996.9     .05       0    5247     .15       0
Bank Sta=4996.9,5247
XS Rating Curve= 0 ,0
Exp/Cntr=0.3,0.1

Type RM Length L Ch R = 1 ,15661   ,2261,2261,2261
BEGIN DESCRIPTION:
FRANKS CREEK 15.0
END DESCRIPTION:
XS GIS Cut Line= 3
      3583004.62     10142792.78      3580390.72     10141477.75
      3574395.45     10140710.62
#Sta/Elev= 30
  1010.9  220.45  1349.5  218.99  1429.3  219.02  1473.9  220.83  1528.6   219.1
  1774.9  220.47  1898.1  218.44  2199.3  221.72  2390.6  216.92  3330.9  216.98
  3666.7  212.06  3917.9  205.95    4238  204.01  4268.2  203.31  4298.5  200.36
  4308.6  199.76  4459.5  197.97    4490   199.4    4984  200.18  5208.6  200.97
  5995.7  204.49  6355.1  201.09  6435.8   203.1    6587  203.21  7649.7  201.84
  8532.7   202.2  9329.2  204.72  9542.8  203.15  9931.3  203.45  9981.1   206.9
#Mann= 3 ,-1 , 0
  1010.9     .15       0  4308.6     .05       0    4984     .15       0
Bank Sta=4298.5,5208.6
XS Rating Curve= 0 ,0
Exp/Cntr=0.3,0.1

Type RM Length L Ch R = 1 ,13400   ,2812,2812,2812
BEGIN DESCRIPTION:
FRANKS CREEK 14.0
END DESCRIPTION:
XS GIS Cut Line= 4
     3584252.757    10140465.431     3581152.757    10139765.431
     3580268.898    10139526.739     3576631.159     10138612.13
#Sta/Elev= 30
       0232.4229389.7208232.0878829.4059229.12531299.069219.21921548.891216.3897
1578.869212.94321608.848212.4778 1688.79214.95471718.769212.25192078.511213.3999
2118.482219.44612138.468220.10192178.439215.33742288.361206.28532408.275203.5609
2618.125202.20442688.074203.33692728.046202.35092937.896202.85733097.781 199.945
 3327.24199.31053606.336203.86353895.401200.26243905.369199.73063925.304198.5906
4054.885199.5204 4074.82199.98015803.145203.37536972.042 201.1837841.223204.1067
#Mann= 3 ,-1 , 0
       0      .1       03895.401     .05       04054.885      .1       0
Bank Sta=3905.369,4074.82
XS Rating Curve= 0 ,0
Exp/Cntr=0.3,0.1

Type RM Length L Ch R = 1 ,10588   ,1456,1456,1456
BEGIN DESCRIPTION:
FRANKS CREEK 10.0
END DESCRIPTION:
XS GIS Cut Line= 4
     3584321.272     10138469.42     3582789.042    10137924.478
      3581854.58    10137788.721     3577243.495    10137112.885
#Sta/Elev= 30
       0220.9311478.6277211.8587528.4847212.3858588.3132210.9827688.0273 211.578
 727.913210.4381817.6556210.41821076.912207.53411156.684207.79031366.083206.4892
1525.626 203.7171794.053201.0272 2200.95201.28872359.739200.40332379.588199.9214
2409.361197.44312439.134197.39822449.058197.75332478.831200.91432488.755201.0078
2538.377199.37572707.944200.81663197.223201.27634185.768200.31064205.738199.4594
4705.003200.85965024.532202.92846692.077201.04816901.768202.89927231.283203.7535
#Mann= 3 ,-1 , 0
       0      .1       02359.739     .05       02488.755      .1       0
Bank Sta=2359.739,2478.831
XS Rating Curve= 0 ,0
Exp/Cntr=0.3,0.1

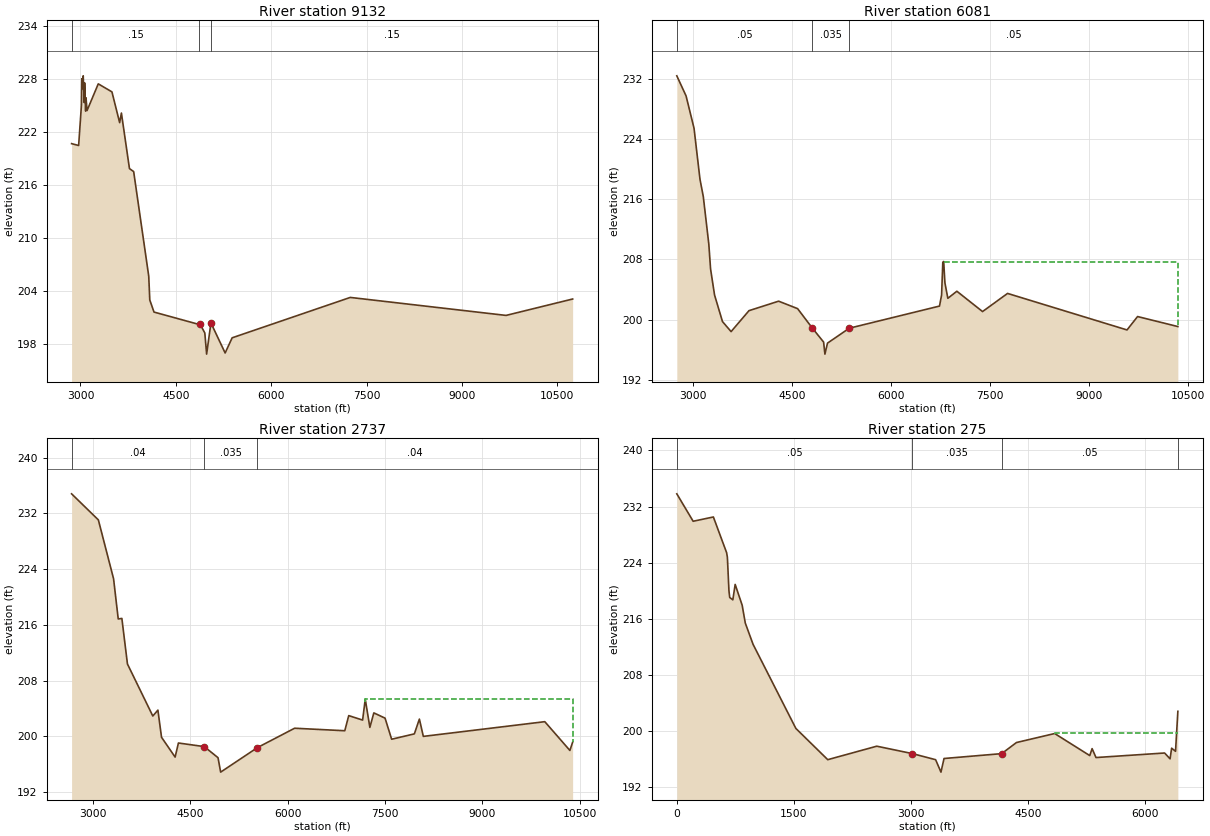
Type RM Length L Ch R = 1 ,9132    ,3051,3051,3051
BEGIN DESCRIPTION:
Mapping XS e36be6b3
END DESCRIPTION:
XS GIS Cut Line= 3
      3584232.26     10137449.62      3578754.84     10134576.36
3577162.2256517810135037.3801242
#Sta/Elev= 30
    2861  220.68  2971.7  220.47  3015.9  225.04  3021.5  228.04  3037.9  226.91
  3043.6  228.37    3060  225.34  3065.6  227.58    3082  224.37  3087.7  225.88
  3104.1  224.43  3280.5  227.46  3495.4  226.55  3616.5  223.06  3644.2  224.15
  3770.9  217.85    3837  217.51    4074  205.65  4090.4  202.95  4156.6  201.58
  4867.5  200.17  4882.5  200.19  4955.7  199.21  4984.1  196.81  5051.9  200.35
  5275.3  196.94  5385.5  198.66  7242.8  203.24    9692   201.2 10739.2  203.06
#Mann= 3 ,-1 , 0
    2861     .15       0  4867.5     .05       0  5051.9     .15       0
Bank Sta=4882.5,5051.9
XS Rating Curve= 0 ,0
Exp/Cntr=0.3,0.1

Type RM Length L Ch R = 1 ,6081    ,3344,3344,3344
BEGIN DESCRIPTION:
FRANKS CREEK 6.0
END DESCRIPTION:
XS GIS Cut Line= 3
       3583792.1      10136541.6      3583687.94     10135105.53
      3581787.71     10129258.82
#Sta/Elev= 30
  2756.9  232.38  2897.2  229.71  3017.5  225.43  3107.8  218.65  3157.9  216.35
  3241.9  210.01  3268.2  206.73  3328.4  203.28  3448.7  199.75    3579  198.42
  3849.7   201.2  4298.6  202.46  4586.1  201.47  4809.8  198.88    4980  197.03
  4999.7  195.43  5038.7  196.89  5368.7  198.87  6734.9  201.81  6766.5  203.28
  6784.9  207.61    6798  207.73  6816.9   204.9  6861.1  202.84  6997.8  203.78
  7386.8  201.08  7765.4  203.49  9574.6  198.64  9734.3  200.42 10344.5  199.09
#Mann= 3 , 0 , 0
  2756.9     .05       0  4809.8    .035       0  5368.7     .05       0
#XS Ineff= 2 , 0
                         6795.45          207.67
Permanent Ineff=
       F       F
Bank Sta=4809.8,5368.7
XS Rating Curve= 0 ,0
Exp/Cntr=0.3,0.1

Type RM Length L Ch R = 1 ,2737    ,2462,2462,2462
BEGIN DESCRIPTION:
Mapping XS 5d613d5d
END DESCRIPTION:
XS GIS Cut Line= 3
      3584977.88     10137078.55      3585912.76     10135945.75
      3587051.65     10129799.94
#Sta/Elev= 30
  2669.8   234.8  3082.1  231.06  3316.6  222.61  3388.3  216.84  3444.3  216.92
  3530.3  210.38  3921.2  202.91  3999.4  203.76  4055.4  199.86  4264.8  197.02
  4315.6  199.04  4714.3  198.52  4925.8  196.93  4966.3  194.86  5532.7  198.38
  6105.6  201.16  6878.5   200.8  6939.6  202.97  7153.1  202.33  7193.8  205.33
    7265  201.28    7326  203.36  7498.9  202.61  7600.6  199.58  7950.4  200.35
  8027.8  202.47  8088.8  199.99  9960.1   202.1 10346.6  197.97   10389  199.16
#Mann= 3 , 0 , 0
  2669.8     .04       0  4714.3    .035       0  5532.7     .04       0
#XS Ineff= 2 , 0
                          7187.5          205.39
Permanent Ineff=
       F       F
Bank Sta=4714.3,5532.7
XS Rating Curve= 0 ,0
Exp/Cntr=0.3,0.1

Type RM Length L Ch R = 1 ,275     ,0,0,0
XS GIS Cut Line= 5
     3585029.868     10137066.45     3587451.743    10136165.408
     3588139.243    10136134.158     3588285.076     10136003.95
3587871.0140682310133069.8354835
#Sta/Elev= 30
       0233.8082209.2544229.8933468.3312230.5053637.7276225.4145647.6921224.7604
 667.621219.9898677.5856219.0154717.4435218.6818 747.337220.8836837.0175217.9144
876.8754215.3732976.5203 212.3371524.568200.33651933.112 195.8782560.875197.8013
 3017.45196.74163314.459 195.8743382.939194.10053422.071196.04454160.167196.7379
4349.886198.32374839.161199.60885288.495196.4624 5318.45197.45235368.376196.1818
6247.074196.8283 6316.97195.99716336.941197.51416386.867197.07496416.822202.7794
#Mann= 4 ,-1 , 0
       0     .05       0 3017.45    .035       04160.167     .05       0
6416.822      .1       0
#XS Ineff= 2 , 0
                         4840.34           199.7
Permanent Ineff=
       F       F
Bank Sta=3017.45,4160.167
XS Rating Curve= 0 ,0
Exp/Cntr=0.3,0.1

Chan Stop Cuts=-1
Use User Specified Reach Order=0
Composite Channel Slope=5