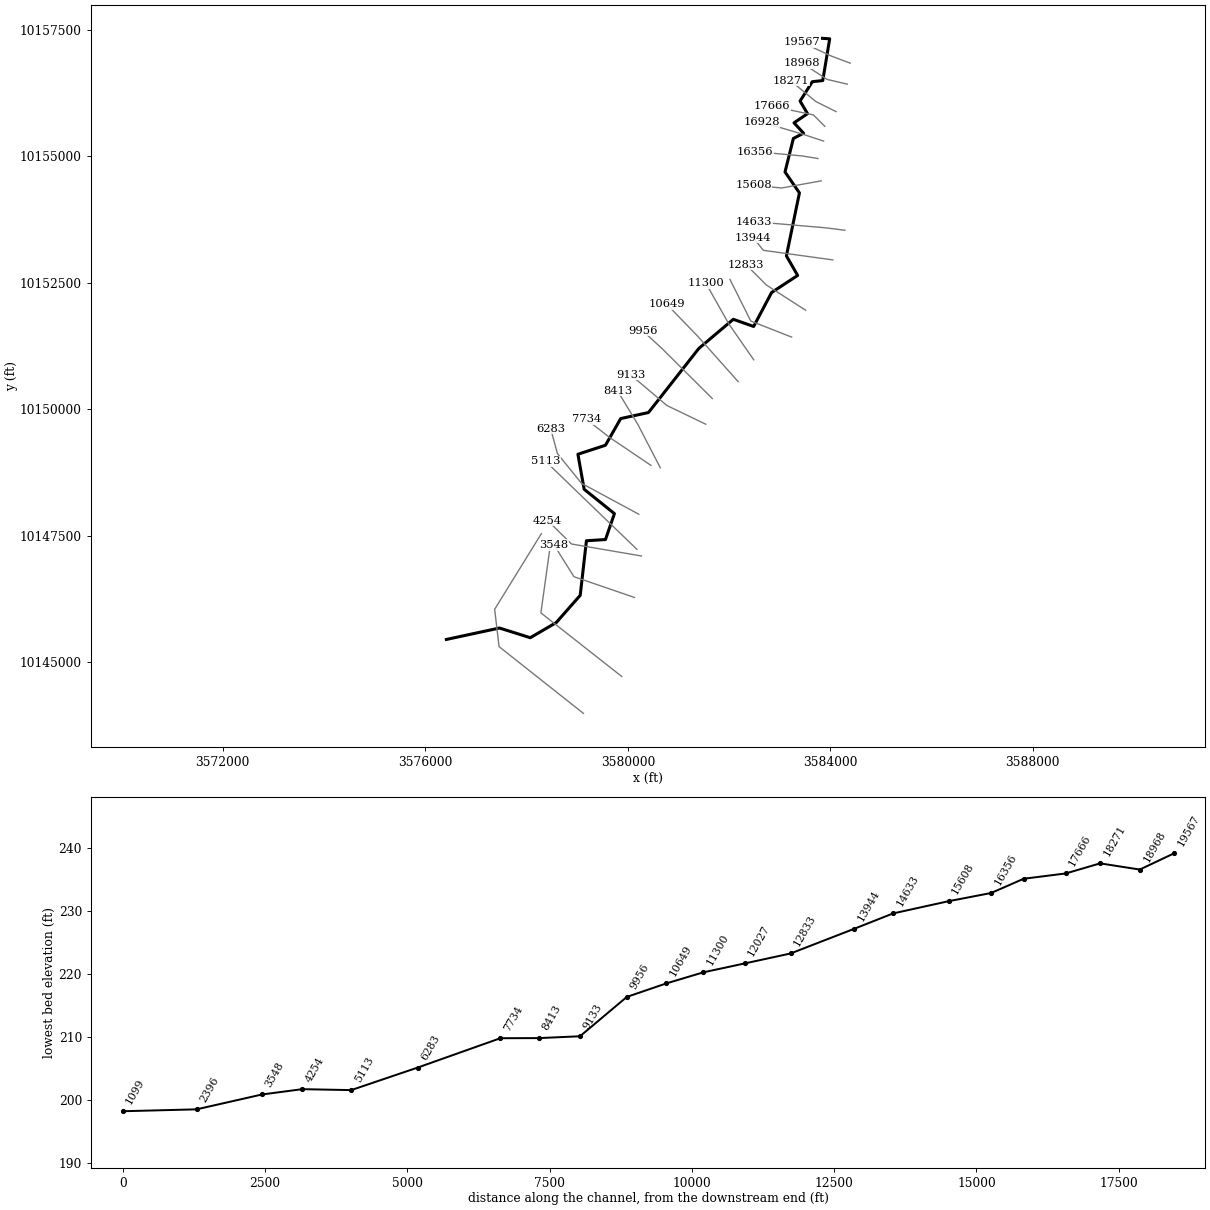
--- HIGH PRAIRIE CREEK.prj (project) ---

Proj Title=HIGH PRAIRIE CREEK Base Level Engineering
Current Plan=p01
Default Exp/Contr=0.3,0.1
English Units
Geom File=g01
Flow File=f01
Plan File=p01
BEGIN DESCRIPTION:
HIGH PRAIRIE CREEK
END DESCRIPTION:

--- HIGH PRAIRIE CREEK.p01 (plan) ---

Plan Title=Multiple Run
Short Identifier=Multiple
Geom File=g01
Flow File=f01
Subcritical Flow
K Sum by GR= 0
Std Step Tol= 0.01
Critical Tol= 0.01
Num of Std Step Trials= 20
Max Error Tol= 0.3
Flow Tol Ratio= 0.001
Split Flow NTrial= 30
Split Flow Tol= 0.02
Split Flow Ratio= 0.02
Log Output Level= 0
Friction Slope Method= 1
Unsteady Friction Slope Method= 2
Unsteady Bridges Friction Slope Method= 1
Parabolic Critical Depth
Global Vel Dist=  1 , 1 , 1
Global Log Level= 0
CheckData=True
Encroach Param= -1, 0, 0, 0
BEGIN DESCRIPTION:
Multiple Run
END DESCRIPTION:

--- HIGH PRAIRIE CREEK.f01 (steady flow) ---

Flow Title=Multiple
Number of Profiles=7
Profile Names=10-year,25-year,50-year,1pct_min,100-year,1pct_plu,500-year
River Rch & RM= HIGH PRAIRIE CRE,Reach-1,19567
    1024    1418    1748    1576    2131    2882    3176
River Rch & RM= HIGH PRAIRIE CRE,Reach-1,13944
    1231    1714    2118    1913    2588    3499    3873
River Rch & RM= HIGH PRAIRIE CRE,Reach-1,6283
    1278    1775    2190    1973    2669    3609    3975
Boundary for River Rch & Prof#=HIGH PRAIRIE CRE,Reach-1,1
Up Type=0
Dn Type=3
Dn Slope=0.005
Boundary for River Rch & Prof#=HIGH PRAIRIE CRE,Reach-1,2
Up Type=0
Dn Type=3
Dn Slope=0.005
Boundary for River Rch & Prof#=HIGH PRAIRIE CRE,Reach-1,3
Up Type=0
Dn Type=3
Dn Slope=0.005
Boundary for River Rch & Prof#=HIGH PRAIRIE CRE,Reach-1,4
Up Type=0
Dn Type=3
Dn Slope=0.005
Boundary for River Rch & Prof#=HIGH PRAIRIE CRE,Reach-1,5
Up Type=0
Dn Type=3
Dn Slope=0.005
Boundary for River Rch & Prof#=HIGH PRAIRIE CRE,Reach-1,6
Up Type=0
Dn Type=3
Dn Slope=0.005
Boundary for River Rch & Prof#=HIGH PRAIRIE CRE,Reach-1,7
Up Type=0
Dn Type=3
Dn Slope=0.005

--- HIGH PRAIRIE CREEK.g01 (geometry) ---

Geom Title=Existing Conditions

River Reach=HIGH PRAIRIE CRE,Reach-1
Reach XY= 30
      3583842.94     10157332.04      3583987.21     10157322.67
      3583850.35     10156497.32      3583644.57     10156474.86
      3583402.11     10156091.64      3583549.73     10155842.58
      3583283.05     10155662.08      3583471.15     10155457.19
      3583269.99     10155352.73      3583104.95     10154690.36
      3583389.51     10154276.36      3583132.22     10153031.37
      3583354.71     10152645.31      3582839.90     10152307.61
      3582485.35     10151636.40      3582083.64     10151778.23
      3581402.59     10151202.65      3580408.53     10149935.67
      3579859.44     10149815.95      3579558.69     10149288.79
      3579014.38     10149110.82      3579137.37     10148419.00
      3579735.26     10147937.02      3579558.91     10147425.15
      3579182.60     10147400.67      3579059.76     10146322.62
      3578586.48     10145784.16      3578073.58     10145484.28
      3577465.49     10145675.73      3576416.65     10145450.08

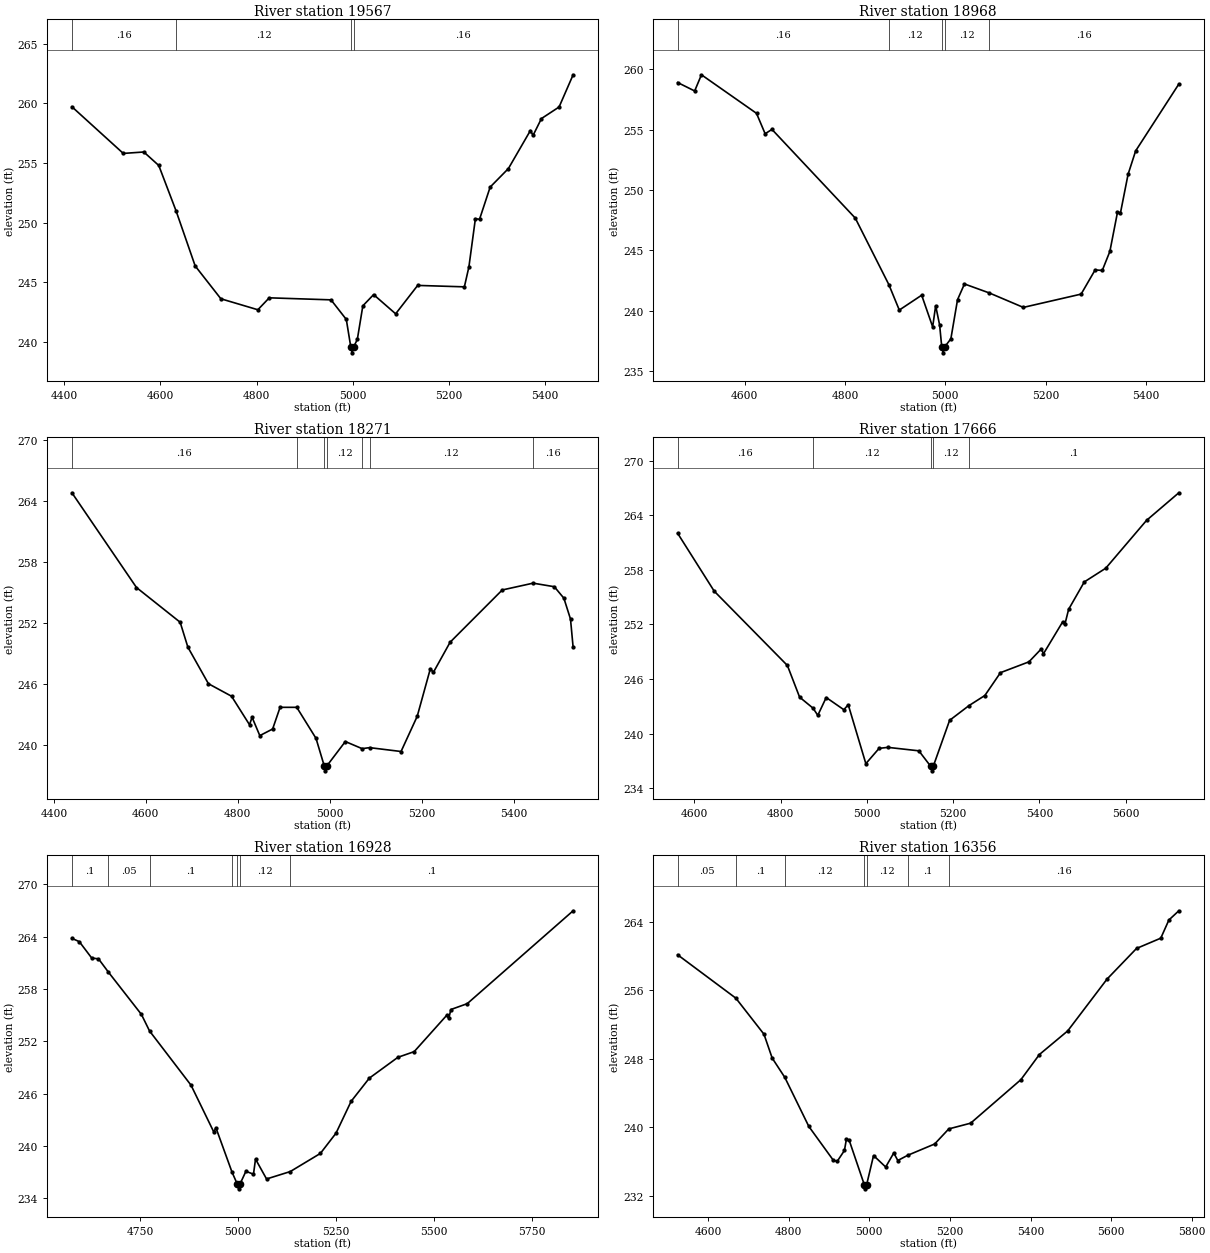
Type RM Length L Ch R = 1,19567,599,599,599
BEGIN DESCRIPTION:
HIGH PRAIRIE CREEK 40.0
END DESCRIPTION:
XS GIS Cut Line= 3
      3584392.08     10156841.65      3584027.95     10156978.28
      3583435.65     10157253.65
#Sta/Elev= 30
  4416.1  259.71  4522.9  255.80  4565.6  255.92  4596.7  254.79  4632.8  250.97
  4672.4  246.37  4725.8  243.62  4802.7  242.70  4826.4  243.70  4954.8  243.53
  4986.6  241.89  4995.9  239.59  4998.7  239.09  5001.9  239.59  5009.5  240.21
  5021.0  243.03  5043.4  243.97  5089.2  242.36  5135.0  244.74  5232.1  244.62
  5241.5  246.29  5255.0  250.33  5263.6  250.28  5285.7  252.98  5323.6  254.53
  5369.4  257.72  5374.9  257.31  5392.3  258.72  5429.0  259.69  5458.2  262.39
#Mann=4,-1,0
  4416.1    0.16       0  4632.8    0.12       0  4995.9    0.07       0
  5001.9    0.16       0
Bank Sta=4995.9,5001.9
Exp/Cntr=0.3,0.1

Type RM Length L Ch R = 1,18968,697,697,697
BEGIN DESCRIPTION:
HIGH PRAIRIE CREEK 38.0
END DESCRIPTION:
XS GIS Cut Line= 3
      3584335.20     10156426.21      3583937.94     10156519.77
      3583442.08     10156841.66
#Sta/Elev= 30
  4466.3  258.90  4500.3  258.20  4513.8  259.54  4623.6  256.35  4640.8  254.66
  4654.4  255.02  4820.5  247.68  4887.4  242.18  4908.3  240.07  4952.9  241.30
  4974.8  238.68  4980.8  240.43  4988.7  238.83  4992.9  237.03  4995.7  236.53
  4998.9  237.03  5011.1  237.69  5024.4  240.93  5038.2  242.23  5088.1  241.48
  5155.6  240.29  5270.8  241.39  5298.7  243.39  5313.0  243.35  5328.1  244.92
  5343.3  248.16  5349.3  248.12  5364.4  251.30  5379.5  253.24  5465.6  258.77
#Mann=5,-1,0
  4466.3    0.16       0  4887.4    0.12       0  4992.9    0.07       0
  4998.9    0.12       0  5088.1    0.16       0
Bank Sta=4992.9,4998.9
Exp/Cntr=0.3,0.1

Type RM Length L Ch R = 1,18271,605,605,605
BEGIN DESCRIPTION:
HIGH PRAIRIE CREEK 37.0
END DESCRIPTION:
XS GIS Cut Line= 3
      3584112.21     10155883.57      3583712.22     10156083.56
      3583216.25     10156493.25
#Sta/Elev= 30
  4439.1  264.83  4579.6  255.52  4674.6  252.11  4691.4  249.66  4736.1  246.07
  4786.4  244.84  4825.5  242.04  4831.1  242.77  4847.9  240.97  4875.8  241.62
  4892.0  243.75  4928.3  243.75  4970.2  240.70  4988.0  238.01  4990.8  237.51
  4994.0  238.01  5034.0  240.39  5070.5  239.69  5086.8  239.79  5155.2  239.41
  5190.4  242.87  5219.0  247.55  5225.5  247.18  5262.0  250.15  5375.4  255.28
  5442.5  255.95  5488.7  255.60  5509.5  254.47  5523.9  252.42  5529.6  249.65
#Mann=7,-1,0
  4439.1    0.16       0  4928.3    0.12       0  4988.0    0.07       0
  4994.0    0.12       0  5070.5    0.16       0  5086.8    0.12       0
  5442.5    0.16       0
Bank Sta=4988,4994
Exp/Cntr=0.3,0.1

Type RM Length L Ch R = 1,17666,738,738,738
BEGIN DESCRIPTION:
HIGH PRAIRIE CREEK 36.0
END DESCRIPTION:
XS GIS Cut Line= 3
      3583892.08     10155591.67      3583665.14     10155818.61
      3582842.07     10155991.65
#Sta/Elev= 30
  4561.2  262.02  4646.0  255.66  4815.7  247.49  4844.0  244.01  4875.1  242.80
  4886.2  242.01  4905.7  243.97  4946.5  242.63  4956.8  243.17  4997.6  236.70
  5028.3  238.38  5048.7  238.49  5120.5  238.11  5147.9  236.41  5150.7  235.91
  5153.9  236.41  5191.8  241.46  5236.7  243.08  5273.5  244.19  5309.7  246.70
  5375.7  247.89  5404.3  249.31  5409.4  248.78  5454.1  252.30  5459.2  252.04
  5467.7  253.66  5504.0  256.67  5553.8  258.18  5648.4  263.44  5723.2  266.47
#Mann=5,-1,0
  4561.2    0.16       0  4875.1    0.12       0  5147.9    0.07       0
  5153.9    0.12       0  5236.7     0.1       0
Bank Sta=5147.9,5153.9
Exp/Cntr=0.3,0.1

Type RM Length L Ch R = 1,16928,572,572,572
BEGIN DESCRIPTION:
HIGH PRAIRIE CREEK 34.0
END DESCRIPTION:
XS GIS Cut Line= 3
      3583866.53     10155301.19      3583442.11     10155441.64
      3582642.56     10155676.19
#Sta/Elev= 30
  4575.9  263.79  4594.8  263.41  4626.5  261.53  4643.8  261.44  4668.9  259.93
  4753.4  255.07  4774.2  253.17  4880.2  246.95  4938.4  241.58  4943.7  242.08
  4984.9  236.98  4998.8  235.57  5001.6  235.07  5004.8  235.57  5020.3  237.08
  5039.7  236.75  5044.9  238.48  5073.1  236.20  5133.6  237.05  5210.6  239.13
  5250.5  241.45  5289.1  245.10  5335.6  247.76  5408.6  250.15  5450.2  250.80
  5533.2  254.96  5538.5  254.61  5544.0  255.63  5585.7  256.30  5856.2  266.95
#Mann=7,-1,0
  4575.9     0.1       0  4668.9    0.05       0  4774.2     0.1       0
  4984.9    0.12       0  4998.8    0.07       0  5004.8    0.12       0
  5133.6     0.1       0
Bank Sta=4998.8,5004.8
Exp/Cntr=0.3,0.1

Type RM Length L Ch R = 1,16356,748,748,748
BEGIN DESCRIPTION:
HIGH PRAIRIE CREEK 33.0
END DESCRIPTION:
XS GIS Cut Line= 3
      3583753.58     10154956.22      3583453.56     10155006.23
      3582517.52     10155092.87
#Sta/Elev= 30
  4524.0  260.15  4668.6  255.08  4738.4  250.87  4758.7  248.09  4790.2  245.82
  4849.7  240.10  4910.0  236.18  4920.0  236.01  4938.1  237.29  4943.1  238.64
  4950.1  238.46  4987.3  233.31  4990.1  232.81  4993.3  233.31  5010.4  236.70
  5040.5  235.36  5060.6  237.00  5070.6  236.12  5095.3  236.73  5162.1  238.05
  5197.1  239.81  5251.4  240.48  5376.1  245.56  5422.1  248.50  5492.4  251.26
  5590.0  257.31  5663.2  260.89  5723.4  262.09  5743.5  264.21  5768.2  265.29
#Mann=7,-1,0
  4524.0    0.05       0  4668.6     0.1       0  4790.2    0.12       0
  4987.3    0.07       0  4993.3    0.12       0  5095.3     0.1       0
  5197.1    0.16       0
Bank Sta=4987.3,4993.3
Exp/Cntr=0.3,0.1

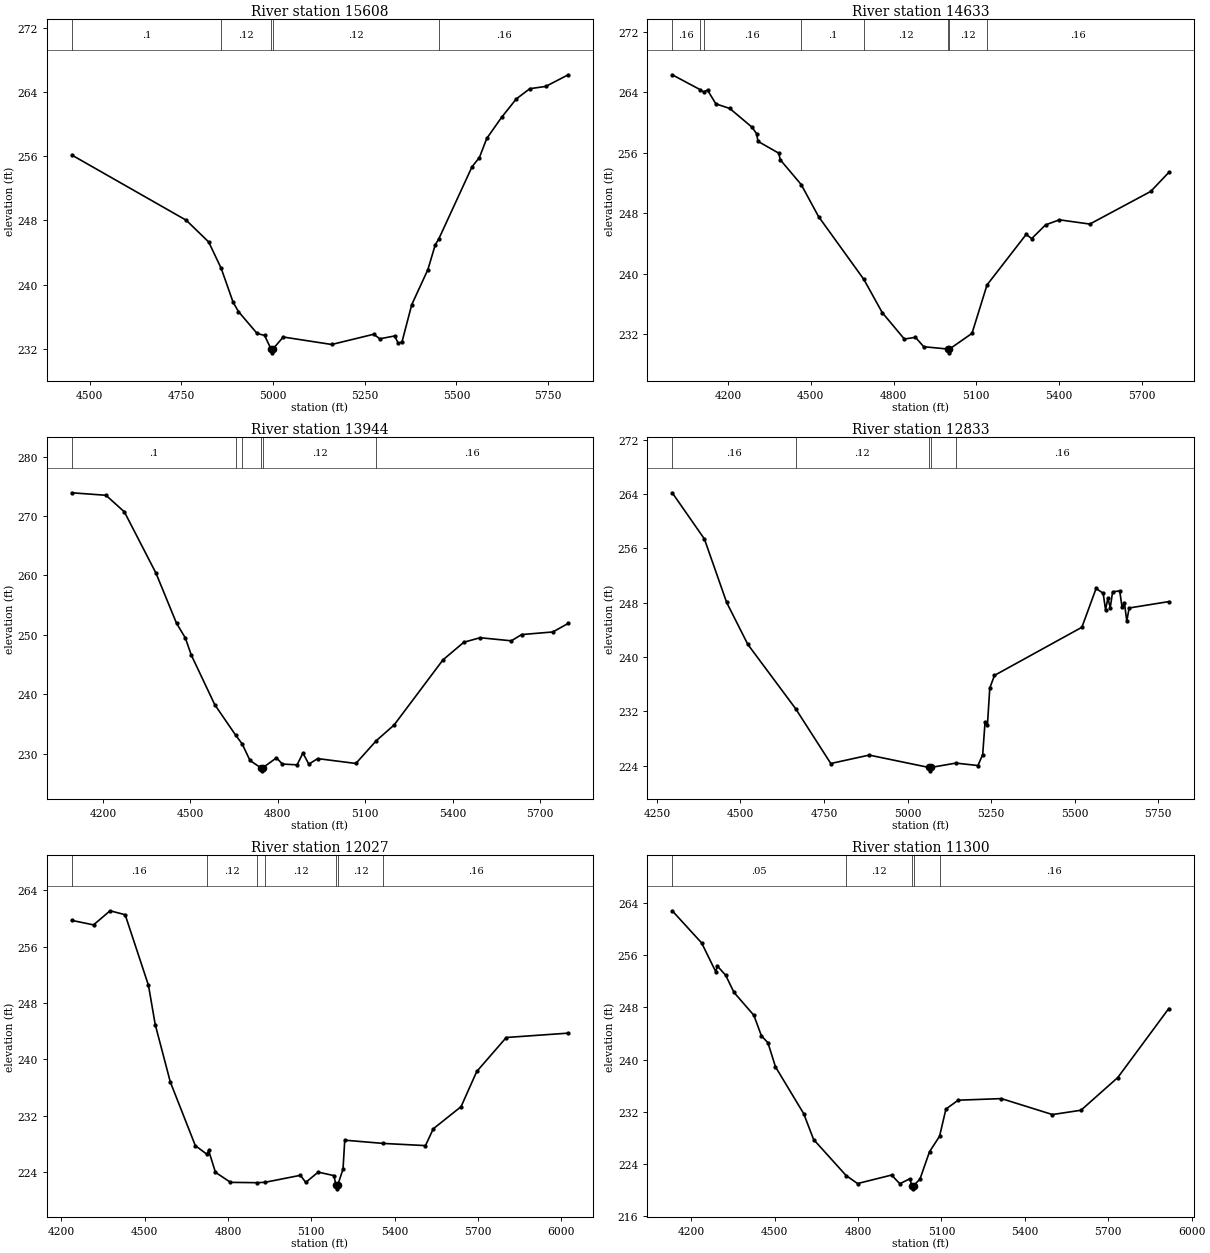
Type RM Length L Ch R = 1,15608,975,975,975
BEGIN DESCRIPTION:
HIGH PRAIRIE CREEK 31.0
END DESCRIPTION:
XS GIS Cut Line= 3
      3583819.57     10154514.74      3583038.36     10154374.12
      3582481.05     10154426.20
#Sta/Elev= 30
  4451.2  256.14  4763.6  248.01  4824.6  245.31  4858.8  242.02  4891.3  237.80
  4905.9  236.64  4956.7  233.92  4977.0  233.68  4994.3  232.01  4997.1  231.51
  5000.3  232.01  5027.8  233.48  5159.9  232.55  5274.2  233.82  5291.4  233.26
  5331.6  233.61  5341.6  232.68  5351.7  232.89  5378.2  237.51  5422.0  241.85
  5442.1  244.93  5452.0  245.70  5542.5  254.67  5562.6  255.82  5582.7  258.20
  5622.9  260.81  5663.0  263.11  5700.1  264.39  5743.4  264.67  5804.7  266.12
#Mann=5,-1,0
  4451.2     0.1       0  4858.8    0.12       0  4994.3    0.07       0
  5000.3    0.12       0  5452.0    0.16       0
Bank Sta=4994.3,5000.3
Exp/Cntr=0.3,0.1

Type RM Length L Ch R = 1,14633,689,689,689
BEGIN DESCRIPTION:
HIGH PRAIRIE CREEK 29.0
END DESCRIPTION:
XS GIS Cut Line= 3
      3584288.99     10153538.52      3583888.98     10153588.52
      3582496.87     10153707.44
#Sta/Elev= 30
  3997.4  266.30  4099.4  264.32  4111.4  264.03  4125.3  264.28  4155.5  262.46
  4205.9  261.85  4286.5  259.38  4303.2  258.52  4308.2  257.51  4383.8  255.94
  4388.9  255.08  4464.9  251.80  4527.9  247.57  4692.3  239.26  4758.7  234.89
  4839.0  231.39  4879.1  231.62  4909.2  230.38  4996.6  230.07  4999.3  229.57
  5002.6  230.07  5084.2  232.14  5138.7  238.54  5280.6  245.21  5300.7  244.66
  5350.8  246.47  5401.0  247.14  5511.4  246.58  5732.2  250.89  5797.7  253.40
#Mann=8,-1,0
  3997.4    0.16       0  4099.4     0.1       0  4111.4    0.16       0
  4464.9     0.1       0  4692.3    0.12       0  4996.6    0.07       0
  5002.6    0.12       0  5138.7    0.16       0
Bank Sta=4996.6,5002.6
Exp/Cntr=0.3,0.1

Type RM Length L Ch R = 1,13944,1111,1111,1111
BEGIN DESCRIPTION:
HIGH PRAIRIE CREEK 28.0
END DESCRIPTION:
XS GIS Cut Line= 3
      3584048.74     10152952.25      3582676.48     10153141.64
      3582476.81     10153391.23
#Sta/Elev= 30
  4092.4  273.90  4210.1  273.48  4273.3  270.69  4381.8  260.38  4452.4  251.94
  4482.7  249.47  4502.9  246.61  4583.7  238.24  4655.5  233.11  4677.8  231.64
  4704.7  228.85  4742.2  227.61  4744.9  227.11  4748.2  227.61  4795.6  229.30
  4815.8  228.25  4866.3  228.12  4886.5  230.10  4906.7  228.23  4937.0  229.17
  5068.2  228.35  5138.6  232.20  5199.4  234.82  5367.0  245.77  5438.9  248.75
  5494.8  249.51  5602.0  248.99  5637.2  250.04  5744.5  250.48  5797.3  251.92
#Mann=6,-1,0
  4092.4     0.1       0  4655.5    0.16       0  4677.8    0.12       0
  4742.2    0.07       0  4748.2    0.12       0  5138.6    0.16       0
Bank Sta=4742.2,4748.2
Exp/Cntr=0.3,0.1

Type RM Length L Ch R = 1,12833,806,806,806
BEGIN DESCRIPTION:
HIGH PRAIRIE CREEK 25.0
END DESCRIPTION:
XS GIS Cut Line= 3
      3583512.34     10151957.44      3582737.94     10152455.18
      3582337.91     10152855.22
#Sta/Elev= 30
  4295.7  264.18  4391.9  257.38  4458.6  248.02  4522.0  241.84  4664.8  232.39
  4770.3  224.30  4885.2  225.54  5063.9  223.72  5066.6  223.22  5069.9  223.72
  5144.7  224.36  5210.8  224.00  5225.0  225.62  5232.0  230.39  5239.1  229.90
  5246.2  235.42  5260.3  237.28  5521.9  244.37  5564.4  250.08  5585.6  249.38
  5592.7  246.95  5599.7  248.63  5606.8  247.26  5613.9  249.59  5635.1  249.73
  5642.2  247.32  5649.2  247.99  5656.3  245.28  5663.4  247.21  5782.0  248.15
#Mann=5,-1,0
  4295.7    0.16       0  4664.8    0.12       0  5063.9    0.07       0
  5069.9    0.12       0  5144.7    0.16       0
Bank Sta=5063.9,5069.9
Exp/Cntr=0.3,0.1

Type RM Length L Ch R = 1,12027,727,727,727
BEGIN DESCRIPTION:
HIGH PRAIRIE CREEK 23.0
END DESCRIPTION:
XS GIS Cut Line= 3
      3583236.28     10151426.20      3582428.99     10151743.91
      3582017.58     10152566.73
#Sta/Elev= 30
  4237.2  259.71  4315.9  259.07  4375.5  261.07  4429.7  260.51  4513.6  250.50
  4538.0  244.93  4592.2  236.80  4682.3  227.77  4724.0  226.54  4730.3  227.08
  4754.7  223.99  4808.9  222.56  4904.7  222.51  4933.7  222.57  5060.7  223.56
  5079.7  222.55  5124.6  224.01  5181.1  223.52  5188.7  222.14  5191.4  221.64
  5194.7  222.14  5214.0  224.44  5220.2  228.54  5358.8  228.08  5510.9  227.77
  5538.8  230.15  5638.9  233.29  5695.4  238.28  5801.6  243.10  6024.7  243.72
#Mann=7,-1,0
  4237.2    0.16       0  4724.0    0.12       0  4904.7    0.16       0
  4933.7    0.12       0  5188.7    0.07       0  5194.7    0.12       0
  5358.8    0.16       0
Bank Sta=5188.7,5194.7
Exp/Cntr=0.3,0.1

Type RM Length L Ch R = 1,11300,651,651,651
BEGIN DESCRIPTION:
HIGH PRAIRIE CREEK 22.0
END DESCRIPTION:
XS GIS Cut Line= 3
      3582486.31     10150978.25      3581992.11     10151691.64
      3581542.12     10152491.61
#Sta/Elev= 30
  4132.0  262.79  4237.7  257.87  4288.4  253.47  4294.5  254.32  4324.2  252.92
  4354.0  250.30  4425.6  246.79  4452.6  243.66  4476.2  242.58  4503.3  238.90
  4604.6  231.75  4640.4  227.78  4757.4  222.26  4798.5  221.04  4920.8  222.34
  4950.5  221.01  4986.3  221.77  4993.8  220.73  4996.6  220.23  4999.8  220.73
  5022.8  221.71  5057.2  225.91  5093.4  228.28  5116.2  232.44  5160.5  233.80
  5315.7  234.04  5499.3  231.60  5601.9  232.26  5734.2  237.26  5917.7  247.83
#Mann=5,-1,0
  4132.0    0.05       0  4757.4    0.12       0  4993.8    0.07       0
  4999.8    0.12       0  5093.4    0.16       0
Bank Sta=4993.8,4999.8
Exp/Cntr=0.3,0.1

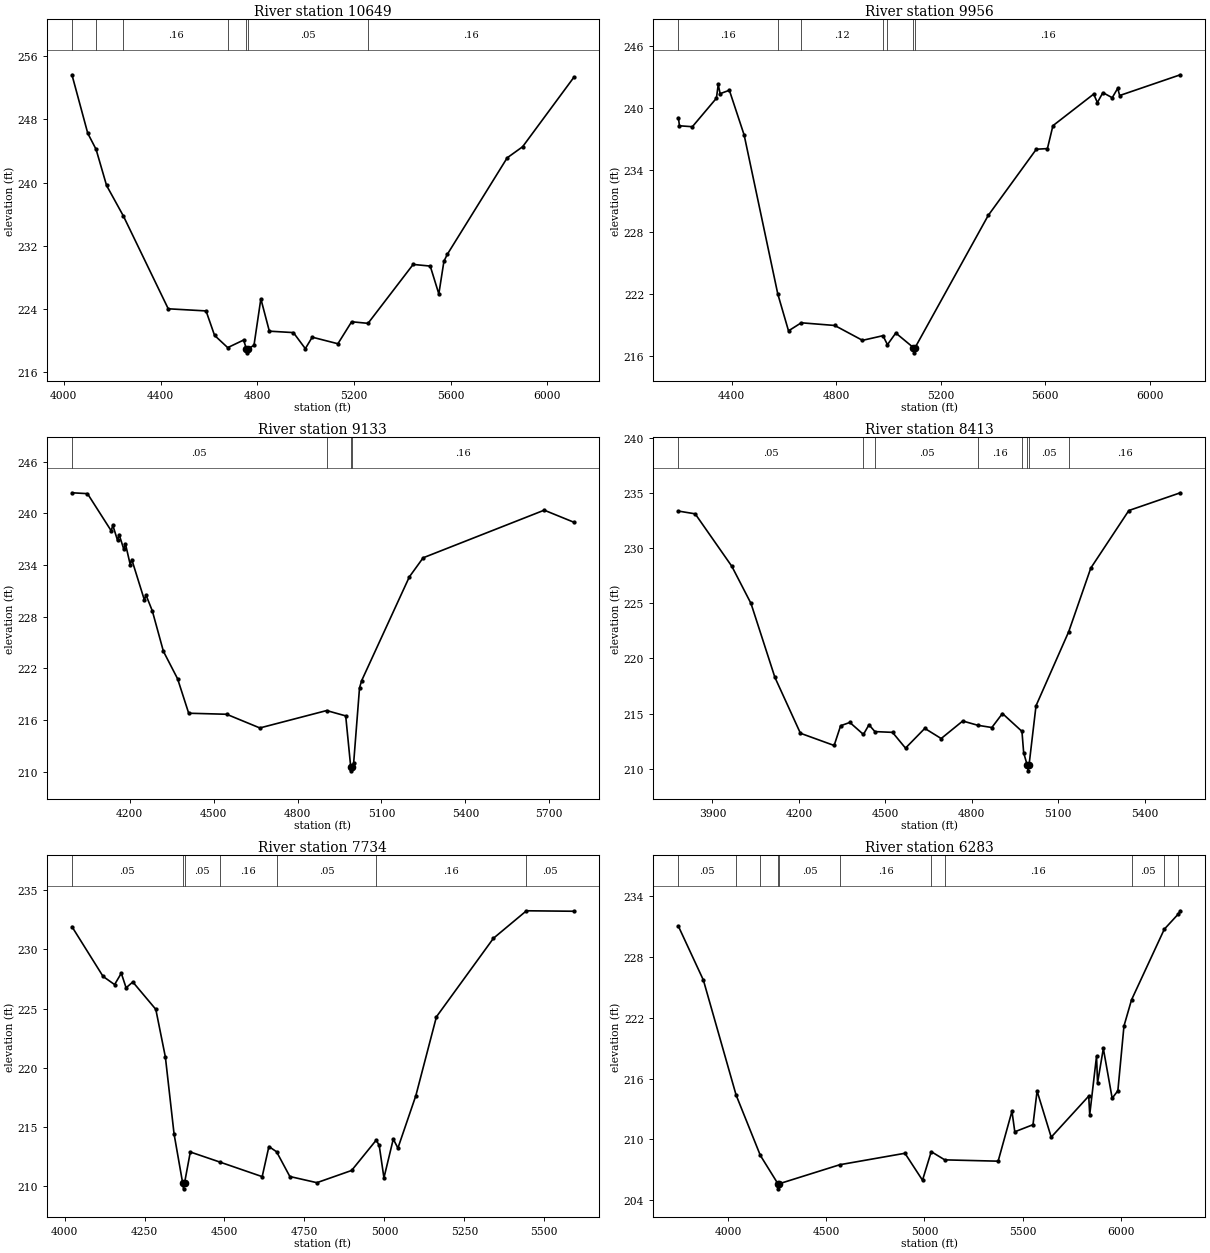
Type RM Length L Ch R = 1,10649,693,693,693
BEGIN DESCRIPTION:
HIGH PRAIRIE CREEK 20.0
END DESCRIPTION:
XS GIS Cut Line= 3
      3582179.00     10150545.99      3581382.11     10151441.83
      3580772.75     10152072.02
#Sta/Elev= 30
  4033.6  253.63  4099.0  246.23  4133.4  244.20  4176.8  239.63  4246.5  235.76
  4431.8  224.04  4588.2  223.77  4623.3  220.68  4677.7  219.13  4743.7  220.09
  4754.9  218.97  4757.7  218.47  4760.9  218.97  4786.4  219.42  4814.8  225.30
  4849.9  221.21  4949.4  221.03  4998.7  219.00  5027.2  220.45  5133.4  219.62
  5190.2  222.40  5258.0  222.20  5444.6  229.65  5515.3  229.44  5550.8  225.92
  5571.9  230.05  5586.0  230.93  5833.5  243.13  5897.3  244.53  6109.2  253.31
#Mann=7,-1,0
  4033.6    0.16       0  4133.4    0.05       0  4246.5    0.16       0
  4677.7    0.05       0  4754.9    0.03       0  4760.9    0.05       0
  5258.0    0.16       0
Bank Sta=4754.9,4760.9
Exp/Cntr=0.3,0.1

Type RM Length L Ch R = 1,9956,823,823,823
BEGIN DESCRIPTION:
HIGH PRAIRIE CREEK 18.0
END DESCRIPTION:
XS GIS Cut Line= 3
      3581668.58     10150212.65      3580684.20     10151191.83
      3580293.60     10151551.18
#Sta/Elev= 30
  4196.9  239.10  4200.8  238.32  4250.2  238.23  4342.2  240.99  4349.2  242.32
  4356.3  241.43  4391.7  241.76  4448.2  237.43  4576.9  222.03  4617.9  218.46
  4666.7  219.24  4794.7  218.98  4900.8  217.54  4979.1  217.99  4996.2  217.12
  5028.1  218.25  5095.8  216.83  5098.5  216.33  5101.8  216.83  5381.6  229.64
  5565.5  236.05  5607.9  236.11  5629.0  238.33  5784.8  241.39  5799.0  240.57
  5820.0  241.53  5855.7  241.04  5876.7  241.95  5884.1  241.25  6116.1  243.26
#Mann=7,-1,0
  4196.9    0.16       0  4576.9    0.05       0  4666.7    0.12       0
  4979.1    0.05       0  4996.2    0.16       0  5095.8    0.07       0
  5101.8    0.16       0
Bank Sta=5095.8,5101.8
Exp/Cntr=0.3,0.1

Type RM Length L Ch R = 1,9133,720,720,720
BEGIN DESCRIPTION:
HIGH PRAIRIE CREEK 17.0
END DESCRIPTION:
XS GIS Cut Line= 3
      3581540.09     10149703.98      3580773.35     10150073.67
      3580054.02     10150683.12
#Sta/Elev= 30
  3993.7  242.38  4049.2  242.28  4134.1  237.96  4139.7  238.61  4156.7  236.85
  4162.3  237.53  4179.3  235.80  4184.9  236.45  4201.9  234.05  4207.5  234.63
  4252.7  229.92  4258.3  230.51  4280.9  228.67  4320.6  223.97  4371.3  220.78
  4411.0  216.78  4546.5  216.66  4665.3  215.07  4904.1  217.09  4972.2  216.47
  4990.0  210.59  4992.7  210.09  4996.0  210.59  5000.7  211.03  5021.6  219.73
  5029.3  220.57  5199.6  232.61  5249.0  234.83  5681.8  240.36  5787.7  238.96
#Mann=4,-1,0
  3993.7    0.05       0  4904.1    0.16       0  4990.0    0.07       0
  4996.0    0.16       0
Bank Sta=4990,4996
Exp/Cntr=0.3,0.1

Type RM Length L Ch R = 1,8413,679,679,679
BEGIN DESCRIPTION:
HIGH PRAIRIE CREEK 16.0
END DESCRIPTION:
XS GIS Cut Line= 3
      3580642.11     10148841.63      3580199.82     10149697.03
      3579797.09     10150363.63
#Sta/Elev= 30
  3781.8  233.36  3840.0  233.11  3967.2  228.35  4033.7  224.98  4116.6  218.28
  4205.2  213.21  4322.2  212.10  4344.7  213.89  4376.7  214.19  4423.9  213.10
  4443.1  213.98  4463.6  213.36  4524.8  213.29  4569.9  211.86  4636.8  213.65
  4693.7  212.73  4768.5  214.32  4821.1  213.93  4869.5  213.73  4906.3  215.00
  4974.0  213.38  4980.0  211.43  4992.5  210.30  4995.3  209.80  4998.5  210.30
  5022.8  215.70  5136.4  222.43  5212.9  228.19  5344.9  233.41  5523.6  235.02
#Mann=8,-1,0
  3781.8    0.05       0  4423.9    0.16       0  4463.6    0.05       0
  4821.1    0.16       0  4974.0    0.05       0  4992.5   0.035       0
  4998.5    0.05       0  5136.4    0.16       0
Bank Sta=4992.5,4998.5
Exp/Cntr=0.3,0.1

Type RM Length L Ch R = 1,7734,1451,1451,1451
BEGIN DESCRIPTION:
HIGH PRAIRIE CREEK 14.0
END DESCRIPTION:
XS GIS Cut Line= 3
      3580456.75     10148891.49      3579642.11     10149441.64
      3579179.01     10149801.19
#Sta/Elev= 30
  4023.1  231.91  4120.4  227.71  4156.4  227.02  4177.4  227.98  4192.4  226.75
  4213.4  227.24  4285.3  224.93  4315.2  220.91  4342.4  214.41  4369.2  210.28
  4372.0  209.78  4375.2  210.28  4393.2  212.89  4485.6  212.04  4617.9  210.81
  4638.9  213.35  4662.9  212.91  4704.4  210.82  4788.9  210.30  4897.5  211.33
  4974.4  213.89  4983.7  213.46  4998.6  210.71  5027.8  213.98  5042.3  213.22
  5098.4  217.65  5162.7  224.30  5341.0  230.93  5444.2  233.25  5592.4  233.21
#Mann=7,-1,0
  4023.1    0.05       0  4369.2    0.07       0  4375.2    0.05       0
  4485.6    0.16       0  4662.9    0.05       0  4974.4    0.16       0
  5444.2    0.05       0
Bank Sta=4369.2,4375.2
Exp/Cntr=0.3,0.1

Type RM Length L Ch R = 1,6283,1170,1170,1170
BEGIN DESCRIPTION:
HIGH PRAIRIE CREEK 13.0
END DESCRIPTION:
XS GIS Cut Line= 5
      3580216.86     10147925.11      3579180.44     10148484.98
      3579091.90     10148527.95      3578609.47     10149124.56
      3578475.43     10149618.55
#Sta/Elev= 30
  3747.4  231.04  3874.5  225.73  4041.2  214.38  4164.5  208.43  4254.1  205.63
  4256.8  205.13  4260.1  205.63  4569.2  207.51  4900.8  208.64  4990.2  205.98
  5034.7  208.80  5103.5  207.99  5375.3  207.86  5445.7  212.79  5460.1  210.76
  5552.8  211.46  5573.6  214.78  5645.5  210.23  5836.5  214.28  5841.6  212.45
  5876.3  218.22  5881.5  215.58  5910.9  218.98  5955.9  214.07  5984.9  214.81
  6016.0  221.20  6054.5  223.78  6221.3  230.75  6292.1  232.24  6302.9  232.57
#Mann=11,-1,0
  3747.4    0.05       0  4041.2    0.16       0  4164.5    0.05       0
  4254.1    0.07       0  4260.1    0.05       0  4569.2    0.16       0
  5034.7    0.05       0  5103.5    0.16       0  6054.5    0.05       0
  6221.3    0.16       0  6292.1    0.05       0
Bank Sta=4254.1,4260.1
Exp/Cntr=0.3,0.1

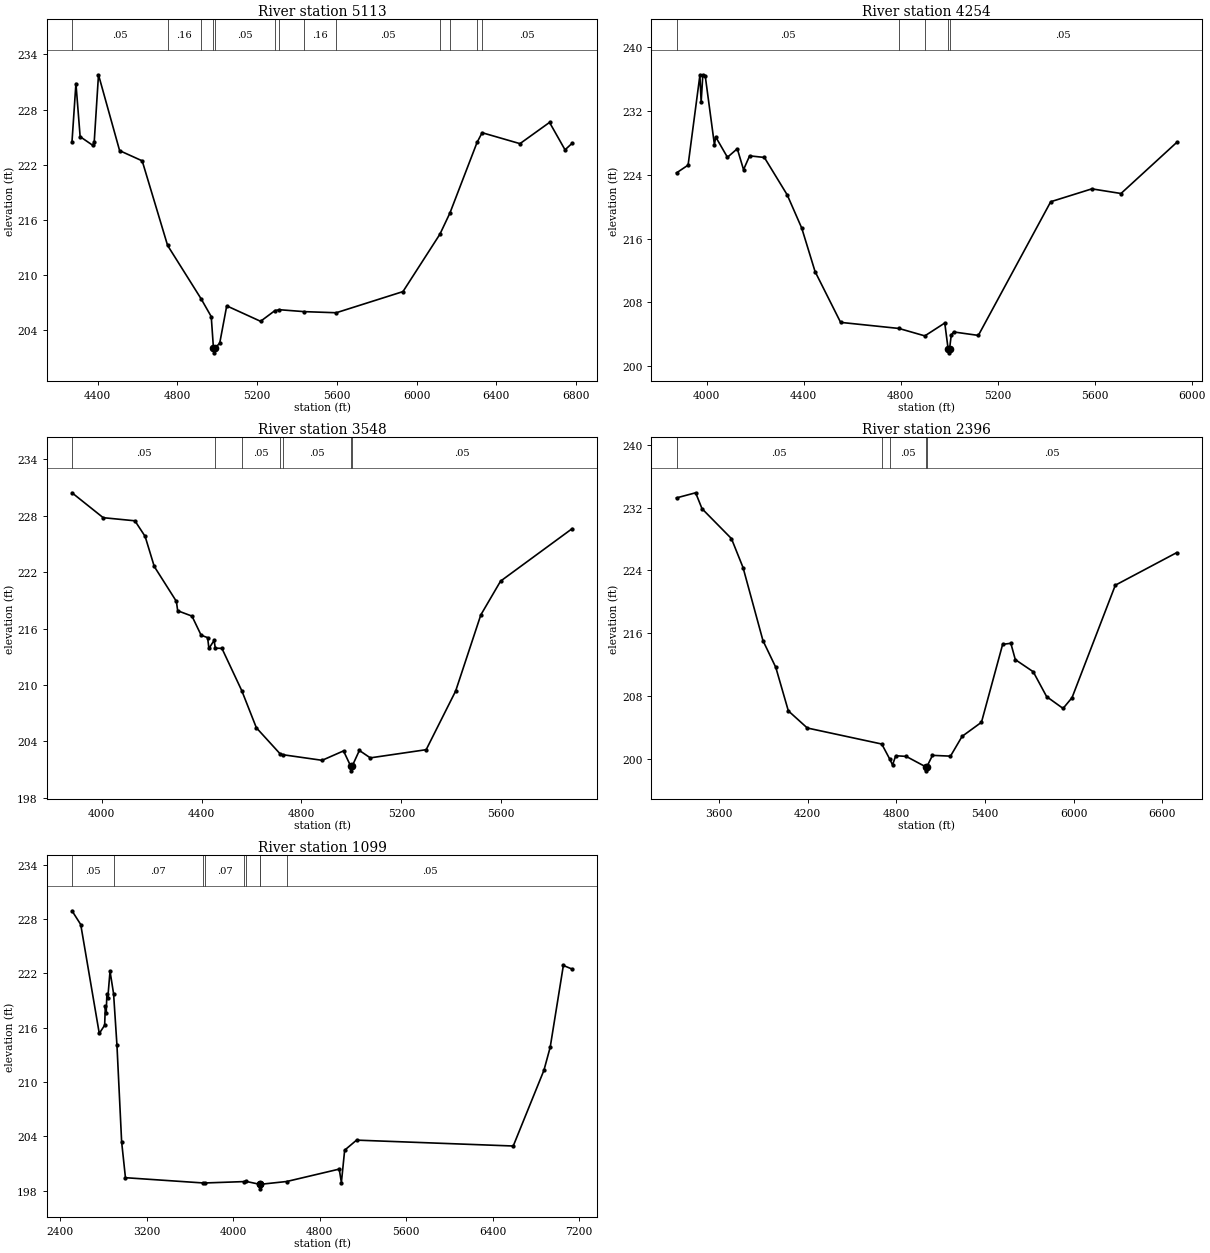
Type RM Length L Ch R = 1,5113,859,859,859
BEGIN DESCRIPTION:
HIGH PRAIRIE CREEK 11.0
END DESCRIPTION:
XS GIS Cut Line= 3
      3580179.65     10147231.27      3579040.33     10148329.36
      3578374.12     10148973.87
#Sta/Elev= 30
  4271.3  224.49  4291.1  230.84  4312.2  225.06  4376.0  224.11  4382.9  224.50
  4404.3  231.79  4510.3  223.54  4623.5  222.43  4751.0  213.23  4919.3  207.42
  4970.0  205.49  4981.1  202.05  4983.9  201.55  4987.1  202.05  5012.4  202.59
  5047.7  206.66  5217.5  204.98  5289.3  206.14  5312.1  206.24  5437.2  206.03
  5597.1  205.91  5931.9  208.21  6117.2  214.45  6167.6  216.76  6303.6  224.43
  6329.0  225.49  6518.9  224.30  6667.3  226.61  6745.0  223.63  6780.6  224.34
#Mann=13,-1,0
  4271.3    0.05       0  4751.0    0.16       0  4919.3    0.05       0
  4981.1   0.035       0  4987.1    0.05       0  5289.3    0.16       0
  5312.1    0.05       0  5437.2    0.16       0  5597.1    0.05       0
  6117.2    0.16       0  6167.6    0.05       0  6303.6    0.16       0
  6329.0    0.05       0
Bank Sta=4981.1,4987.1
Exp/Cntr=0.3,0.1

Type RM Length L Ch R = 1,4254,706,706,706
BEGIN DESCRIPTION:
HIGH PRAIRIE CREEK 9.0
END DESCRIPTION:
XS GIS Cut Line= 3
      3580269.23     10147099.82      3578887.37     10147336.86
      3578416.13     10147800.19
#Sta/Elev= 30
  3875.2  224.21  3923.0  225.18  3971.7  236.42  3976.8  233.06  3983.9  236.48
  3994.0  236.27  4031.7  227.72  4036.8  228.71  4085.3  226.16  4125.9  227.23
  4151.7  224.61  4176.7  226.34  4237.5  226.14  4331.8  221.46  4391.8  217.30
  4446.7  211.87  4552.1  205.51  4792.8  204.75  4899.5  203.82  4981.7  205.43
  4995.5  202.20  4998.2  201.70  5001.5  202.20  5008.6  203.95  5018.8  204.31
  5120.2  203.88  5418.7  220.60  5588.4  222.21  5708.6  221.63  5938.1  228.01
#Mann=5,-1,0
  3875.2    0.05       0  4792.8    0.16       0  4899.5    0.05       0
  4995.5   0.035       0  5001.5    0.05       0
Bank Sta=4995.5,5001.5
Exp/Cntr=0.3,0.1

Type RM Length L Ch R = 1,3548,1152,1152,1152
BEGIN DESCRIPTION:
HIGH PRAIRIE CREEK 7.0
END DESCRIPTION:
XS GIS Cut Line= 3
      3580130.39     10146280.36      3578935.93     10146690.09
      3578543.29     10147316.77
#Sta/Elev= 30
  3881.3  230.44  4006.3  227.79  4133.2  227.46  4174.1  225.80  4210.7  222.60
  4299.2  218.89  4304.5  217.89  4361.7  217.32  4398.3  215.29  4424.3  215.03
  4429.5  213.88  4450.2  214.73  4455.2  213.91  4481.5  213.89  4561.0  209.39
  4619.5  205.44  4714.5  202.67  4726.7  202.57  4882.7  201.98  4968.4  202.98
  4997.1  201.36  4999.9  200.86  5003.1  201.36  5031.8  203.03  5075.6  202.24
  5299.3  203.11  5417.3  209.35  5518.1  217.45  5597.1  221.04  5883.6  226.62
#Mann=7,-1,0
  3881.3    0.05       0  4455.2    0.12       0  4561.0    0.05       0
  4714.5    0.16       0  4726.7    0.05       0  4997.1   0.035       0
  5003.1    0.05       0
Bank Sta=4997.1,5003.1
Exp/Cntr=0.3,0.1

Type RM Length L Ch R = 1,2396,1297,1297,1297
BEGIN DESCRIPTION:
HIGH PRAIRIE CREEK 2.0
END DESCRIPTION:
XS GIS Cut Line= 3
      3579880.38     10144717.87      3578283.16     10145974.81
      3578469.43     10147312.51
#Sta/Elev= 30
  3312.6  233.23  3442.0  233.88  3485.3  231.85  3684.2  228.05  3762.8  224.36
  3897.4  215.07  3984.1  211.67  4069.1  206.13  4197.4  203.95  4701.1  201.91
  4754.6  200.01  4773.8  199.25  4795.6  200.42  4866.1  200.34  4999.5  199.00
  5002.2  198.50  5005.5  199.00  5044.1  200.47  5166.0  200.37  5244.6  202.89
  5375.5  204.68  5518.7  214.59  5574.1  214.73  5604.4  212.65  5725.6  211.11
  5816.4  207.94  5927.5  206.44  5988.1  207.81  6280.9  222.12  6695.7  226.26
#Mann=5,-1,0
  3312.6    0.05       0  4701.1     0.1       0  4754.6    0.05       0
  4999.5   0.035       0  5005.5    0.05       0
Bank Sta=4999.5,5005.5
Exp/Cntr=0.3,0.1

Type RM Length L Ch R = 1,1099,0,0,0
BEGIN DESCRIPTION:
HIGH PRAIRIE CREEK 1.0
END DESCRIPTION:
XS GIS Cut Line= 4
      3579123.42     10143988.71      3577456.77     10145308.15
      3577369.96     10146045.99      3578292.10     10147541.63
#Sta/Elev= 30
  2510.1  228.91  2591.0  227.39  2762.5  215.36  2812.2  216.27  2818.6  218.34
  2826.6  217.65  2833.0  219.73  2841.0  219.24  2861.9  222.24  2894.7  219.76
  2926.0  214.06  2969.3  203.39  3004.5  199.43  3722.5  198.85  3743.4  198.85
  4101.0  199.00  4116.3  199.03  4246.7  198.70  4249.5  198.20  4252.7  198.70
  4495.8  199.01  4981.7  200.38  5001.8  198.90  5032.0  202.47  5142.1  203.58
  6591.2  202.93  6875.0  211.29  6933.0  213.84  7054.8  222.87  7135.8  222.47
#Mann=9,-1,0
  2510.1    0.05       0  2894.7    0.07       0  3722.5    0.05       0
  3743.4    0.07       0  4101.0    0.05       0  4116.3    0.07       0
  4246.7   0.035       0  4252.7    0.07       0  4495.8    0.05       0
Bank Sta=4246.7,4252.7
Exp/Cntr=0.3,0.1

Chan Stop Cuts=-1