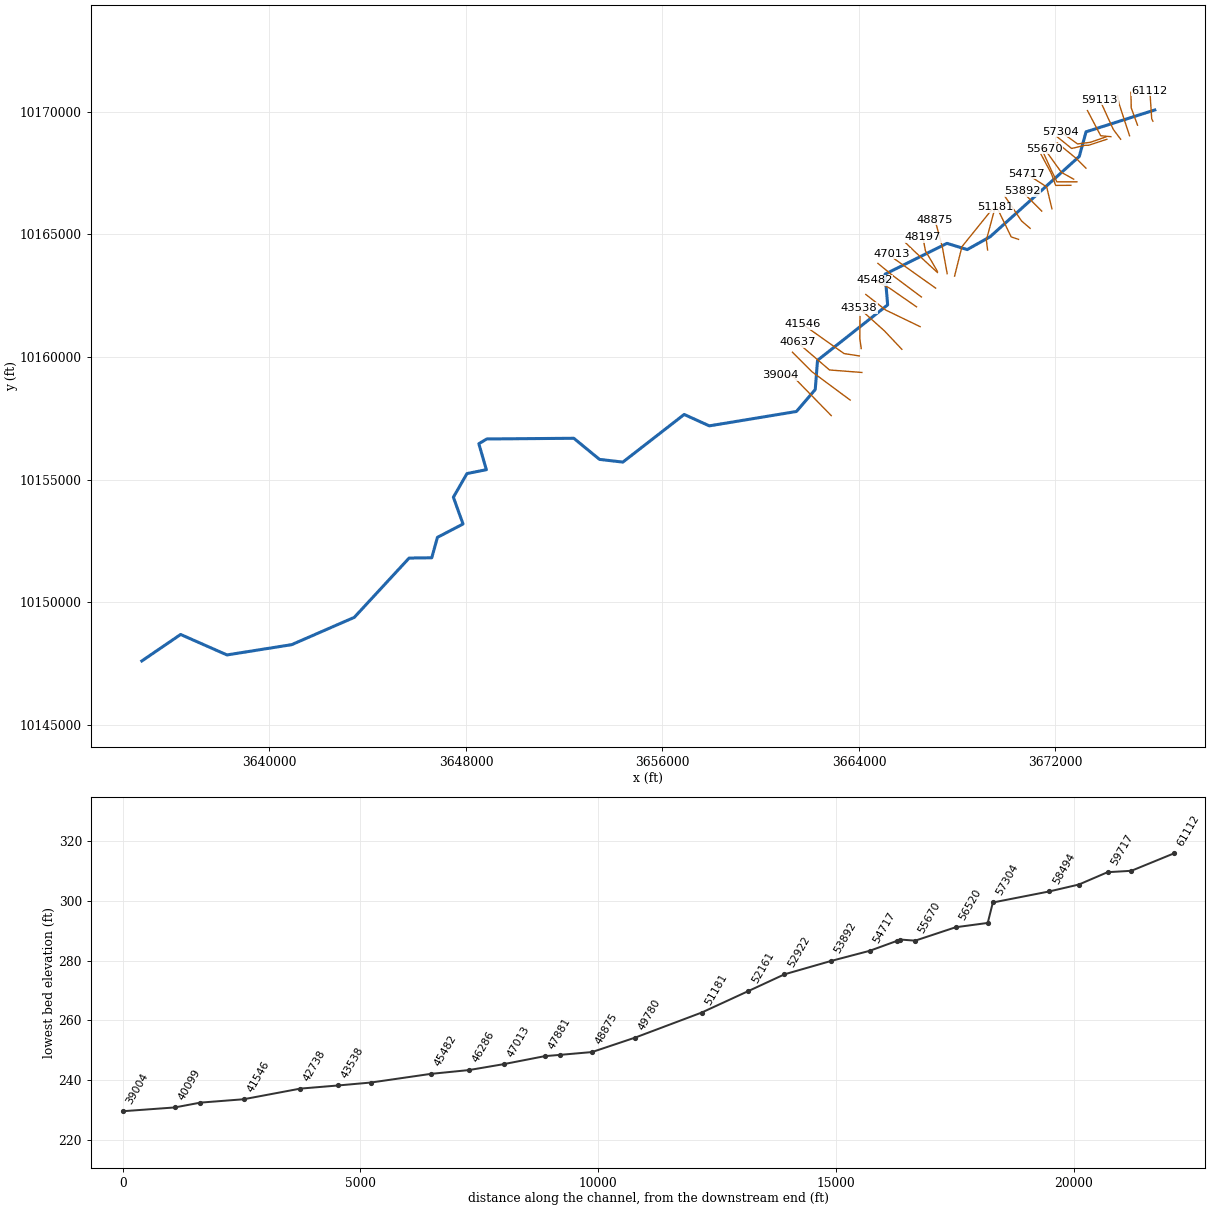
--- HOLLAND CREEK.prj (project) ---

Proj Title=HOLLAND CREEK Base Level Engineering
Current Plan=p01
Default Exp/Contr=0.3,0.1
English Units
Geom File=g01
Flow File=f01
Plan File=p01
Y Axis Title=Elevation
X Axis Title(PF)=Main Channel Distance
X Axis Title(XS)=Station
BEGIN DESCRIPTION:
HOLLAND CREEK
END DESCRIPTION:
DSS Export Rating Curves= 0
DSS Export Rating Curve Sorted= 0
DSS Export Volume Flow Curves= 0
DXF OffsetX= 0
DXF OffsetY= 0
DXF ScaleX= 1
DXF ScaleY= 10

--- HOLLAND CREEK.p01 (plan) ---

Plan Title=Multiple Run
Short Identifier=Multiple
Geom File=g01
Flow File=f01
Subcritical Flow
K Sum by GR= 0
Std Step Tol= 0.01
Critical Tol= 0.01
Num of Std Step Trials= 20
Max Error Tol= 0.3
Flow Tol Ratio= 0.001
Split Flow NTrial= 30
Split Flow Tol= 0.02
Split Flow Ratio= 0.02
Log Output Level= 0
Friction Slope Method= 1
Unsteady Friction Slope Method= 2
Unsteady Bridges Friction Slope Method= 1
Parabolic Critical Depth
Global Vel Dist=  1 , 1 , 1
Global Log Level= 0
CheckData=True
Encroach Param= -1, 0, 0, 0
BEGIN DESCRIPTION:
Multiple Run
END DESCRIPTION:

--- HOLLAND CREEK.f01 (steady flow) ---

Flow Title=Multiple
Program Version=4.10
Number of Profiles= 7
Profile Names=10-year,25-year,50-year,1pct_min,100-year,1pct_plu,500-year
River Rch & RM=HOLLAND CREEK,Reach-1         ,61112
     827    1132    1386    1244    1682    2275    2475
River Rch & RM=HOLLAND CREEK,Reach-1         ,60218
    1263    1763    2185    1981    2679    3623    4029
River Rch & RM=HOLLAND CREEK,Reach-1         ,54717
    1814    2579    3236    2966    4011    5424    6168
River Rch & RM=HOLLAND CREEK,Reach-1         ,53892
    1814    2579    3236    2966    4011    5424    6168
River Rch & RM=HOLLAND CREEK,Reach-1         ,49780
    3819    5589    7150    6666    9015   12191   14343
River Rch & RM=HOLLAND CREEK,Reach-1         ,48875
    3819    5589    7150    6666    9015   12191   14343
River Rch & RM=HOLLAND CREEK,Reach-1         ,41546
    4218    6167    7884    7341    9928   13426   15758
River Rch & RM=HOLLAND CREEK,Reach-1         ,32507
    4616    6765    8664    8081   10928   14779   17404
River Rch & RM=HOLLAND CREEK,Reach-1         ,31710
    4675    6852    8775    8183   11066   14966   17620
River Rch & RM=HOLLAND CREEK,Reach-1         ,29741
    6076    8980   11566   10842   14663   19830   23587
River Rch & RM=HOLLAND CREEK,Reach-1         ,28318
    6076    8980   11566   10842   14663   19830   23587
River Rch & RM=HOLLAND CREEK,Reach-1         ,26862
    6297    9309   11991   11241   15203   20560   24458
River Rch & RM=HOLLAND CREEK,Reach-1         ,26119
    6328    9344   12028   11267   15237   20606   24472
River Rch & RM=HOLLAND CREEK,Reach-1         ,24596
    6328    9344   12028   11267   15237   20606   24472
River Rch & RM=HOLLAND CREEK,Reach-1         ,19417
    6343    9339   11996   11212   15163   20506   24247
River Rch & RM=HOLLAND CREEK,Reach-1         ,16020
    6633    9778   12573   11761   15906   21511   25483
River Rch & RM=HOLLAND CREEK,Reach-1         ,9163
    7932   11753   15168   14237   19254   26039   31057
River Rch & RM=HOLLAND CREEK,Reach-1         ,6309
    8079   11976   15459   14514   19628   26545   31675
River Rch & RM=HOLLAND CREEK,Reach-1         ,2012
    8279   12275   15847   14880   20123   27214   32478
Boundary for River Rch & Prof#=HOLLAND CREEK,Reach-1         , 1
Up Type= 0
Dn Type= 3
Dn Slope=0.002
Boundary for River Rch & Prof#=HOLLAND CREEK,Reach-1         , 2
Up Type= 0
Dn Type= 3
Dn Slope=0.002
Boundary for River Rch & Prof#=HOLLAND CREEK,Reach-1         , 3
Up Type= 0
Dn Type= 3
Dn Slope=0.002
Boundary for River Rch & Prof#=HOLLAND CREEK,Reach-1         , 4
Up Type= 0
Dn Type= 3
Dn Slope=0.002
Boundary for River Rch & Prof#=HOLLAND CREEK,Reach-1         , 5
Up Type= 0
Dn Type= 3
Dn Slope=0.002
Boundary for River Rch & Prof#=HOLLAND CREEK,Reach-1         , 6
Up Type= 0
Dn Type= 3
Dn Slope=0.002
Boundary for River Rch & Prof#=HOLLAND CREEK,Reach-1         , 7
Up Type= 0
Dn Type= 3
Dn Slope=0.002
DSS Import GetInterval= 0
DSS Import GetPeak= 0
DSS Import FillOption= 0

--- HOLLAND CREEK.g01 (geometry) ---

Geom Title=Existing Conditions
Program Version=4.10

River Reach=HOLLAND CREEK   ,Reach-1
Reach XY= 30
      3676043.01     10170061.55      3673246.13      10169172.5
      3672968.57     10168168.35      3669342.96     10164899.45
      3668406.98     10164373.63      3667583.58     10164628.09
      3665062.13     10163371.44      3665167.59     10162118.49
      3662313.17     10159861.86      3662219.73     10158672.63
      3661454.74     10157776.76      3657907.22      10157191.2
      3656883.69     10157655.21      3654387.44     10155714.45
      3653434.54      10155825.3      3652390.35     10156685.24
        3648847.       10156657.      3648523.42     10156463.49
      3648829.15     10155404.86      3648039.77     10155246.41
      3647487.31     10154283.47      3647879.95      10153191.7
       3646838.5     10152648.25      3646606.35     10151815.71
      3645684.57      10151804.2      3643453.02     10149388.19
      3640904.58     10148275.84       3638268.8     10147857.13
       3636382.6     10148690.91      3634802.11     10147611.64

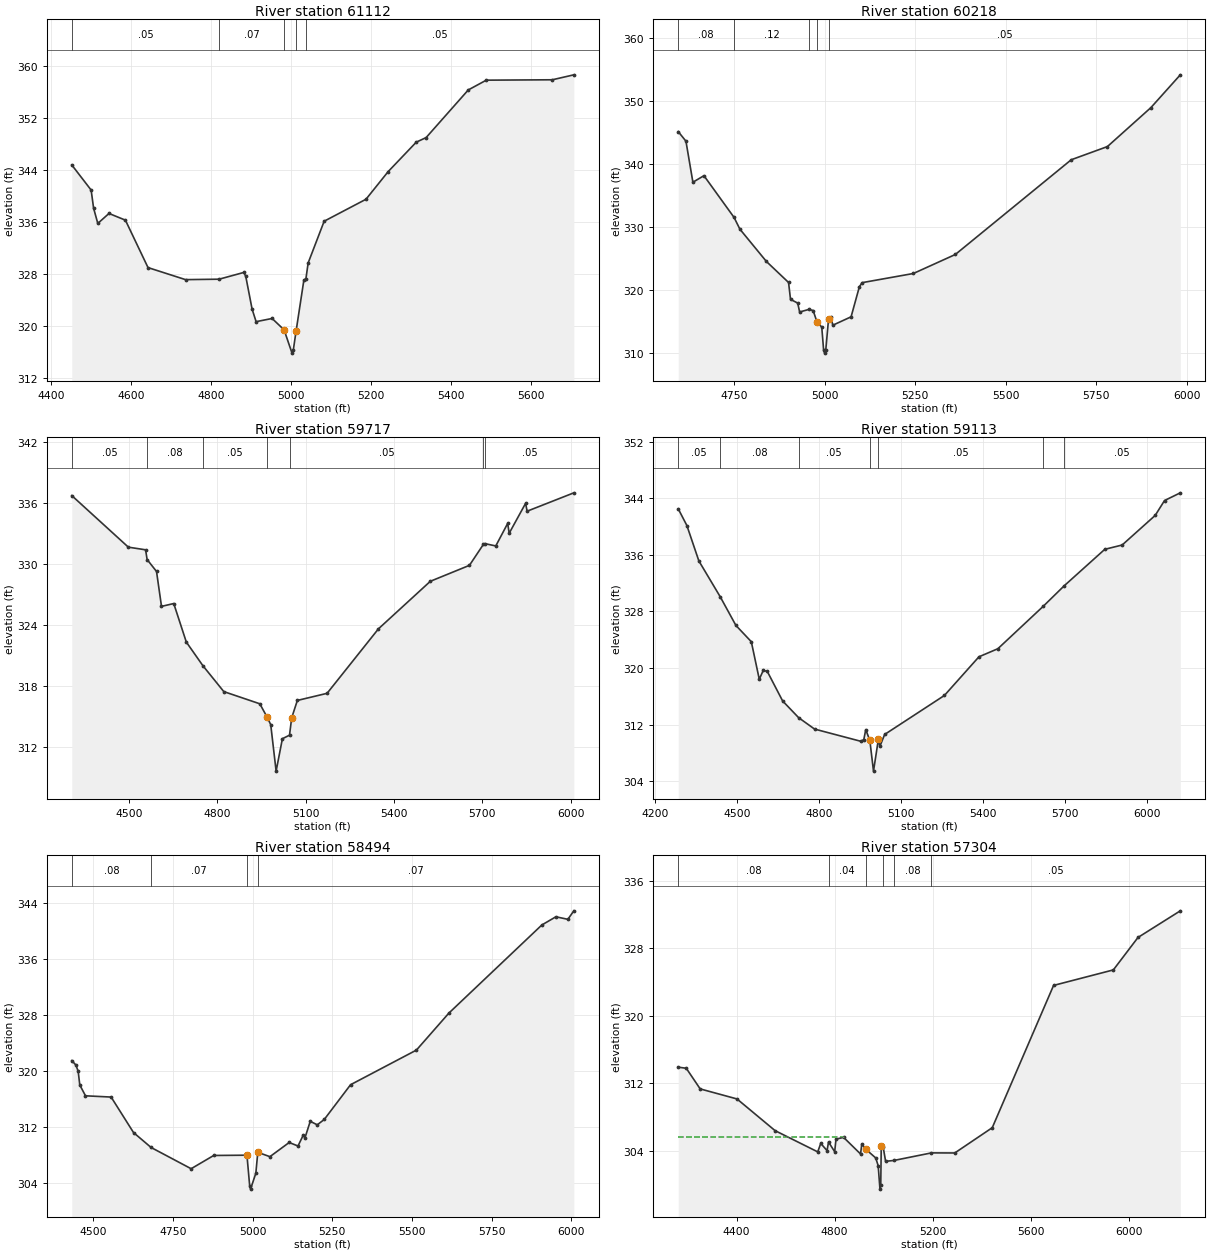
Type RM Length L Ch R = 1 ,61112   ,894,894,894
BEGIN DESCRIPTION:
HOLLAND CREEK 81.0
END DESCRIPTION:
XS GIS Cut Line= 3
      3675968.51     10169602.73      3675918.49     10169702.75
      3675842.58     10170845.41
#Sta/Elev= 30
  4451.4  344.76  4499.9   340.9  4506.1   338.1  4516.6  335.78  4544.6  337.31
  4585.7  336.28  4642.3     329  4736.3  327.15  4820.3  327.22  4881.8  328.25
  4886.9  327.69  4902.9  322.62  4912.9   320.7    4953  321.19    4983  319.44
  5002.8  315.87  5006.1  316.37  5013.1  319.29  5032.4  327.04  5037.7  327.31
  5043.2  329.71  5083.3  336.12    5188  339.49  5243.6  343.74  5313.8  348.25
  5338.6  348.96  5444.1  356.27  5489.2  357.77  5654.5  357.83  5708.4  358.59
#Mann= 5 ,-1 , 0
  4451.4     .05       0  4820.3     .07       0    4983     .05       0
  5013.1     .07       0  5037.7     .05       0
Bank Sta=4983,5013.1
XS Rating Curve= 0 ,0
Exp/Cntr=0.3,0.1

Type RM Length L Ch R = 1 ,60218   ,501,501,501
BEGIN DESCRIPTION:
HOLLAND CREEK 79.0
END DESCRIPTION:
XS GIS Cut Line= 3
      3675342.09     10169441.67      3675085.64     10170144.01
      3675071.75     10170782.86
#Sta/Elev= 30
  4595.6  345.13  4616.9  343.61  4636.1  337.11  4666.6  338.15  4749.9  331.53
  4765.9  329.68  4839.2  324.56  4900.3  321.24  4905.7  318.57  4925.6  317.97
  4930.9  316.56  4956.2  316.97  4968.2   316.8  4978.8  314.98    4992  314.18
  4997.1  310.55  4999.9  310.05  5003.1  310.55  5010.8  315.47  5017.2  315.78
  5022.5  314.47    5073   315.8  5095.9  320.56  5103.5  321.21    5245  322.66
  5360.9  325.67    5681  340.67    5781  342.76  5901.1  348.93  5982.3  354.12
#Mann= 5 ,-1 , 0
  4595.6     .08       0  4749.9     .12       0  4956.2     .05       0
  4978.8    .035       0  5010.8     .05       0
Bank Sta=4978.8,5010.8
XS Rating Curve= 0 ,0
Exp/Cntr=0.3,0.1

Type RM Length L Ch R = 1 ,59717   ,603,603,603
BEGIN DESCRIPTION:
HOLLAND CREEK 78.0
END DESCRIPTION:
XS GIS Cut Line= 3
      3675016.18     10169012.09      3674580.99     10170343.03
        3674531.     10170643.01
#Sta/Elev= 30
    4306  336.71  4498.1  331.63  4556.6  331.37  4561.8  330.41  4593.7  329.24
  4610.6   325.8  4652.2  326.08  4694.8  322.29  4751.1  319.96  4822.1  317.41
  4944.3  316.21  4968.3  314.94  4981.4  314.16  4999.7  309.58    5021  312.77
  5045.2  313.12  5052.5  314.82  5071.8  316.54  5172.7  317.24  5347.1  323.59
  5523.2  328.27    5656  329.84  5703.5  331.91  5708.1  331.98  5745.4  331.75
  5785.8  333.97  5790.9     333  5846.7  335.95  5851.7  335.17  6010.4  336.98
#Mann= 7 ,-1 , 0
    4306     .05       0  4561.8     .08       0  4751.1     .05       0
  4968.3    .035       0  5045.2     .05       0  5703.5     .08       0
  5708.1     .05       0
Bank Sta=4968.3,5052.5
XS Rating Curve= 0 ,0
Exp/Cntr=0.3,0.1

Type RM Length L Ch R = 1 ,59113   ,620,620,620
BEGIN DESCRIPTION:
HOLLAND CREEK 77.0
END DESCRIPTION:
XS GIS Cut Line= 3
      3674654.63     10168869.38      3674354.61     10169269.42
      3673800.93     10170484.25
#Sta/Elev= 30
  4285.2   342.5  4316.8  340.14  4360.6  335.14  4438.6  330.08    4496  326.03
  4552.3  323.73  4581.4  318.43    4596  319.68  4610.6  319.54  4666.8  315.36
  4725.3     313  4783.5  311.39    4953  309.66  4963.5  309.91  4970.6  311.31
  4985.5  309.79  4998.9  305.45  5016.7  309.94  5022.2  308.95  5039.7  310.63
  5258.1  316.14  5384.3   321.6  5453.5  322.74  5619.2  328.73  5695.7  331.62
  5844.2  336.78  5907.8  337.39  6028.5  341.57  6062.6  343.67  6120.3  344.76
#Mann= 7 ,-1 , 0
  4285.2     .05       0  4438.6     .08       0  4725.3     .05       0
  4985.5    .035       0  5016.7     .05       0  5619.2     .08       0
  5695.7     .05       0
Bank Sta=4985.5,5016.7
XS Rating Curve= 0 ,0
Exp/Cntr=0.3,0.1

Type RM Length L Ch R = 1 ,58494   ,1189,1189,1189
BEGIN DESCRIPTION:
HOLLAND CREEK 75.0
END DESCRIPTION:
XS GIS Cut Line= 3
      3674254.98     10168974.67       3673843.5     10169011.13
      3673301.77     10170038.23
#Sta/Elev= 30
  4433.1  321.48    4446  320.85  4453.2  319.96  4458.2  318.01  4476.1  316.46
  4556.5  316.28  4626.7  311.22  4681.8  309.09  4807.4  306.06  4878.2  307.95
  4982.4  307.99  4990.9  303.65  4993.7  303.15  5010.3  305.43  5016.4   308.4
  5054.4  307.78  5114.8   309.8  5142.5   309.3  5158.8  310.84  5164.5  310.49
  5180.9  312.82  5202.9  312.32  5224.9  313.09  5307.3  318.04  5513.8  322.98
  5615.7  328.26    5907  340.82  5951.1  341.99  5988.6  341.63  6007.4  342.84
#Mann= 4 ,-1 , 0
  4433.1     .08       0  4681.8     .07       0  4982.4     .04       0
  5016.4     .07       0
Bank Sta=4982.4,5016.4
XS Rating Curve= 0 ,0
Exp/Cntr=0.3,0.1

Type RM Length L Ch R = 1 ,57304   ,108,108,108
BEGIN DESCRIPTION:
HOLLAND CREEK 73.0
END DESCRIPTION:
XS GIS Cut Line= 4
      3674059.66     10168966.87      3673427.64     10168746.66
      3672898.77     10168678.52      3672213.32     10169175.17
#Sta/Elev= 30
  4161.9  313.91  4194.7  313.78  4251.5  311.33  4401.7  310.14  4557.1  306.38
  4731.2  303.86  4743.5  304.86  4769.3  304.01  4775.2  305.03  4800.4  303.88
  4805.7  305.37  4836.8  305.58  4905.9  303.61    4911  304.78  4927.5  304.17
  4967.8  303.14  4977.9  302.22  4985.1  299.44  4988.4  299.94  4990.4  304.53
  4998.1  304.47  5008.2  302.74  5041.8  302.84  5195.3  303.74  5290.5  303.73
  5443.5  306.73  5693.7  323.61  5937.6  325.45  6038.2   329.3  6210.9  332.46
#Mann= 6 ,-1 , 0
  4161.9     .08       0  4775.2     .04       0  4927.5    .035       0
  4998.1     .04       0  5041.8     .08       0  5195.3     .05       0
#XS Ineff= 2 , 0
         4838.07  305.66
Permanent Ineff=
       F       F
Bank Sta=4927.5,4990.4
XS Rating Curve= 0 ,0
Exp/Cntr=0.3,0.1

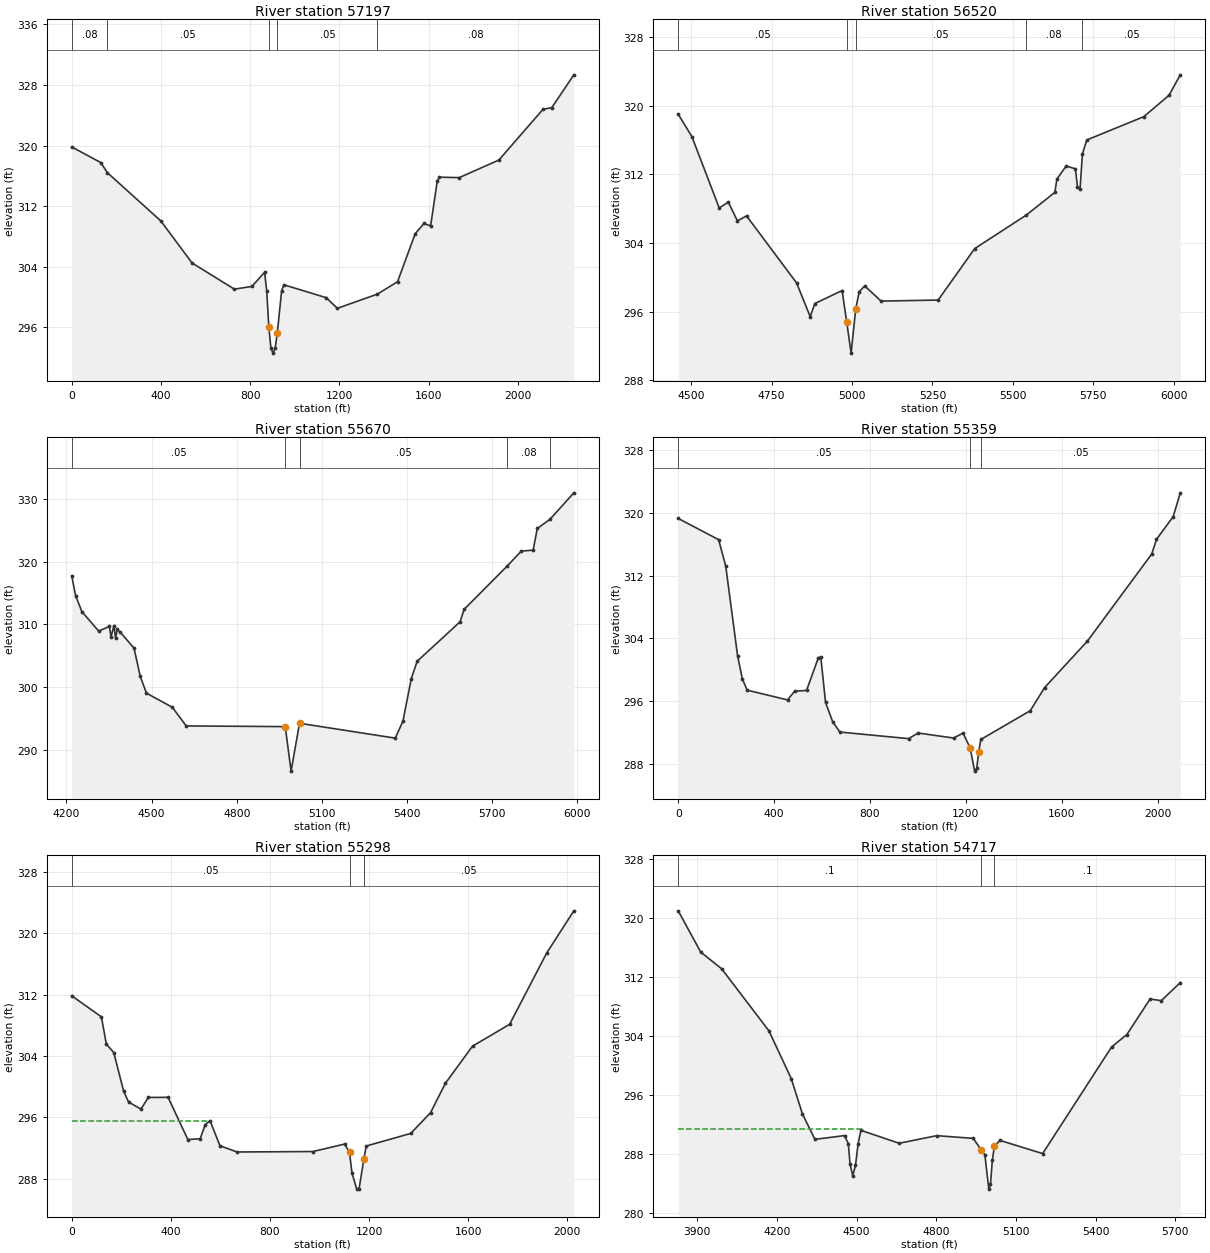
Type RM Length L Ch R = 1 ,57197   ,676,676,676
XS GIS Cut Line= 5
     3674091.407    10168868.325     3673348.352    10168623.533
     3673195.574    10168621.797     3672659.116    10168493.325
     3672061.893    10168974.228
#Sta/Elev= 30
       0319.8154129.8184317.7571159.7765316.4163399.4413 310.043539.2458304.4993
728.9804301.0421807.3937301.4033864.3598303.2678873.8542300.8229883.3485296.0379
892.8429293.2218902.3372292.5976911.8316293.2403921.3259295.2506940.8113300.8521
950.8022301.61911140.631299.91771190.586298.51141370.423 300.3911460.342302.0246
1539.583308.36891579.089309.71431608.718309.39351638.347315.31621648.224315.8263
1737.112315.76821914.888318.09582112.417324.78572151.922325.00992250.687329.3387
#Mann= 5 ,-1 , 0
       0     .08       0159.7765     .05       0883.3485    .035       0
921.3259     .05       01370.423     .08       0
Bank Sta=883.3485,921.3259
XS Rating Curve= 0 ,0
Exp/Cntr=0.3,0.1

Type RM Length L Ch R = 1 ,56520   ,850,850,850
BEGIN DESCRIPTION:
HOLLAND CREEK 71.0
END DESCRIPTION:
XS GIS Cut Line= 3
      3673242.13     10167691.61      3672842.11     10168091.64
      3672071.75      10168720.4
#Sta/Elev= 30
  4460.1  319.01  4502.6   316.4  4587.4  308.08  4615.7  308.76    4644  306.57
  4672.3  307.16  4827.8  299.34  4870.3  295.39  4884.4  296.93  4969.3  298.45
  4983.4  294.83  4997.3  291.15  5011.7  296.31  5022.3  298.31  5039.5  298.99
  5090.4  297.22  5267.8  297.34  5381.2  303.34  5541.2  307.24  5630.4   309.9
  5636.8  311.46  5665.6  312.98  5694.3  312.64  5700.7  310.53  5708.6   310.3
  5716.1  314.38  5729.5  316.01  5906.8  318.73    5985  321.22  6020.2  323.61
#Mann= 5 ,-1 , 0
  4460.1     .05       0  4983.4    .035       0  5011.7     .05       0
  5541.2     .08       0  5716.1     .05       0
Bank Sta=4983.4,5011.7
XS Rating Curve= 0 ,0
Exp/Cntr=0.3,0.1

Type RM Length L Ch R = 1 ,55670   ,312,312,312
BEGIN DESCRIPTION:
HOLLAND CREEK 69.0
END DESCRIPTION:
XS GIS Cut Line= 3
       3672742.1     10167241.64      3672242.74       10167520.
      3671542.11     10168491.63
#Sta/Elev= 30
  4218.7  317.67  4232.4  314.56  4254.1  312.05  4313.6  308.93  4351.3  309.69
    4357     308  4367.3  309.82    4373  307.77    4379  309.23    4389  308.79
  4438.2  306.22  4459.9  301.74    4482  299.06    4573  296.82  4622.2  293.85
  4971.1  293.74  4991.7  286.66  5021.4  294.27  5358.8  291.91  5385.9   294.6
  5415.3  301.37  5436.2  304.14  5587.1  310.41  5601.8   312.4  5754.4  319.33
    5803  321.66  5844.8  321.81  5859.5  325.26  5904.2  326.72  5988.3  330.93
#Mann= 5 ,-1 , 0
  4218.7     .05       0  4971.1    .035       0  5021.4     .05       0
  5754.4     .08       0  5904.2     .05       0
Bank Sta=4971.1,5021.4
XS Rating Curve= 0 ,0
Exp/Cntr=0.3,0.1

Type RM Length L Ch R = 1 ,55359   ,61,61,61
XS GIS Cut Line= 5
     3672871.591    10167135.043     3672055.619    10167135.043
     3671880.271    10167511.779      3671854.23    10167556.918
     3671515.688    10168299.974
#Sta/Elev= 30
       0319.2851168.4901316.5827198.2237 313.192247.7796301.7131267.6019 298.799
287.4243297.3722455.9144296.1304 485.648297.2348535.2039297.3398584.7598301.5268
 594.671301.5897614.4933295.8043644.2269 293.345673.9604292.0288960.8975291.1869
1000.412291.90241148.593291.26491188.107291.88851217.744289.98741236.308  287.04
1244.993287.37711253.678289.53821262.364 291.0851468.463294.75181528.062297.6959
1706.857303.6374 1975.05314.75221994.917316.61942064.448319.52022094.248322.5587
#Mann= 3 ,-1 , 0
       0     .05       01217.744    .035       01262.364     .05       0
Bank Sta=1217.744,1253.678
XS Rating Curve= 0 ,0
Exp/Cntr=0.3,0.1

Type RM Length L Ch R = 1 ,55298   ,581,581,581
XS GIS Cut Line= 5
     3672628.796    10166992.045     3672008.744    10166989.036
     3671832.355    10167469.476     3671810.653    10167515.049
      3671406.66    10168262.474
#Sta/Elev= 30
       0311.8638119.6279309.1172139.5659305.5683169.4729304.4694209.3488299.4271
229.2868298.0137279.1318297.0837309.0388298.6049388.7907298.6227468.5426293.1211
518.3876 293.214538.3256295.0307558.2635295.5761598.1395292.3053667.4031 291.493
973.2219291.55251101.469292.52471121.199291.45051131.064288.75141150.315 286.649
1159.941286.71961179.192290.57631188.818292.27391368.392293.91421448.202296.6134
 1508.06300.4457  1617.8305.29651767.445308.1432 1917.09317.43742026.829322.9491
#Mann= 3 , 0 , 0
       0     .05       01121.199    .035       01179.192     .05       0
#XS Ineff= 2 , 0
           548.3  295.51
Permanent Ineff=
       F       F
Bank Sta=1121.199,1179.192
XS Rating Curve= 0 ,0
Exp/Cntr=0.3,0.1

Type RM Length L Ch R = 1 ,54717   ,824,824,824
BEGIN DESCRIPTION:
HOLLAND CREEK 66.0
END DESCRIPTION:
XS GIS Cut Line= 3
      3671856.48     10166032.86      3671641.19     10166928.74
      3670828.65     10167456.54
#Sta/Elev= 30
  3828.7  320.96  3913.2  315.38    3992  313.12  4170.2  304.71  4254.1  298.25
  4296.1  293.49  4343.2  290.02  4454.8  290.53  4469.1  289.42  4475.4  286.73
  4485.7   285.1    4496  286.48  4505.9  289.41  4516.5  291.24  4660.5  289.49
    4802  290.52  4939.8  290.15  4968.1  288.64  4983.2  287.92  4998.1  283.28
  5004.3  283.91  5011.3  287.23  5019.4  289.15  5040.6  289.87  5200.7  288.09
  5460.3  302.53  5517.7  304.21  5605.3  309.02  5647.5   308.8    5719  311.25
#Mann= 3 ,-1 , 0
  3828.7      .1       0  4968.1     .05       0  5019.4      .1       0
#XS Ineff= 2 , 0
         4525.56  291.37
Permanent Ineff=
       F       F
Bank Sta=4968.1,5019.4
XS Rating Curve= 0 ,0
Exp/Cntr=0.3,0.1

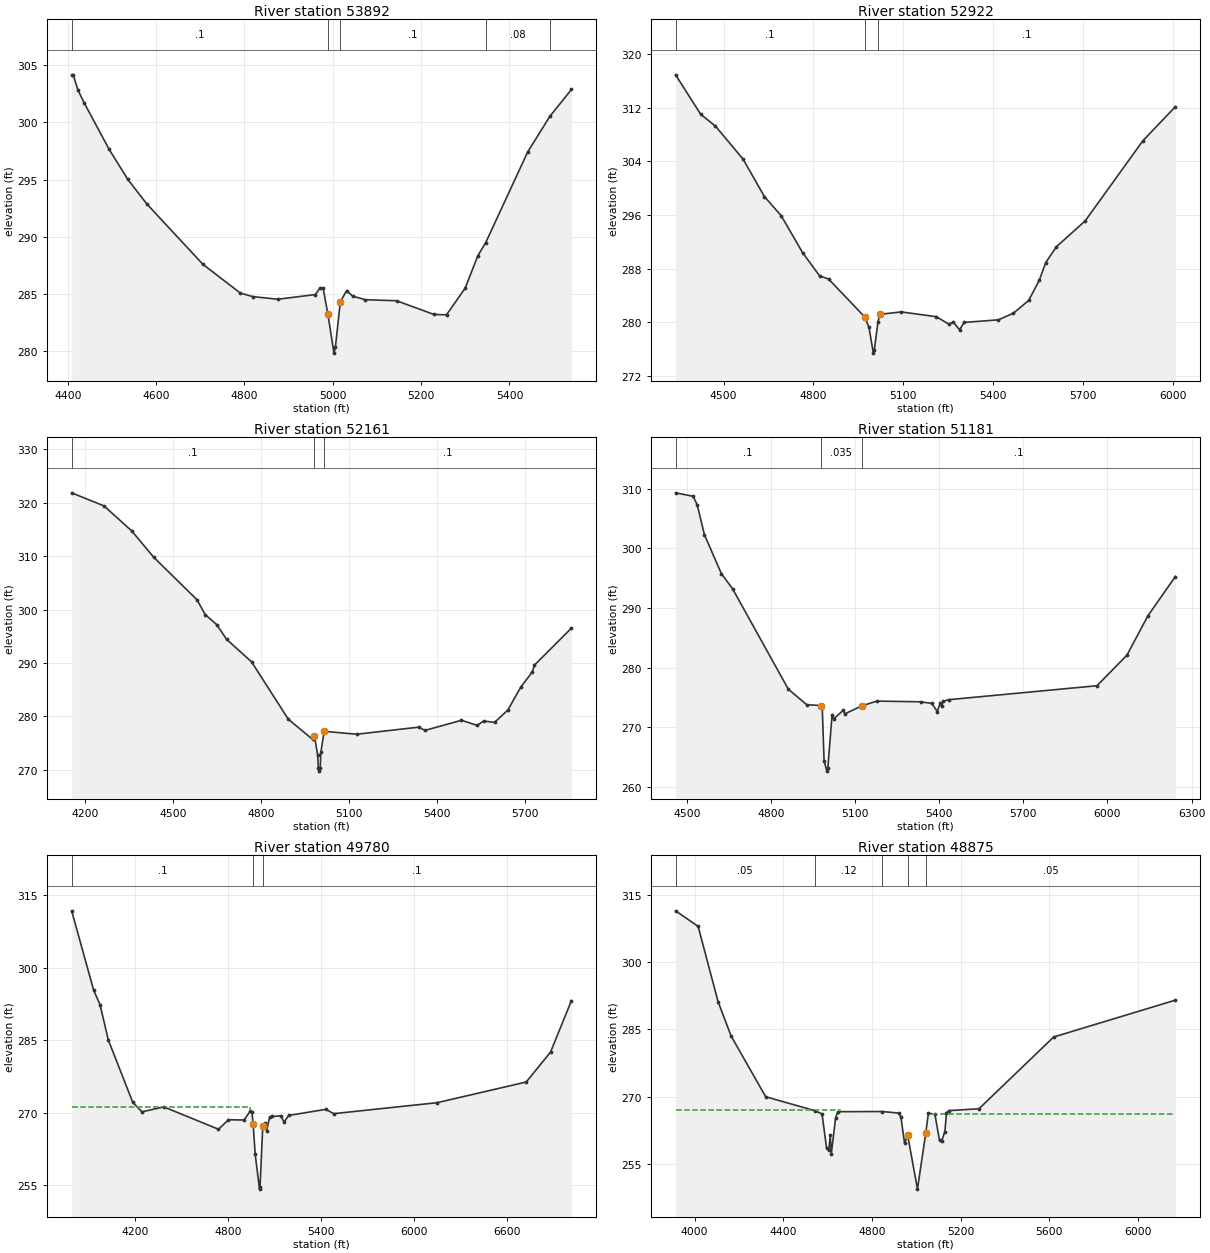
Type RM Length L Ch R = 1 ,53892   ,970,970,970
BEGIN DESCRIPTION:
HOLLAND CREEK 65.0
END DESCRIPTION:
XS GIS Cut Line= 3
      3671442.13     10165941.61      3671042.11     10166341.64
      3670642.11     10166741.63
#Sta/Elev= 30
  4408.9  304.16  4412.5  304.16  4423.1  302.84  4437.2  301.71  4493.8  297.64
  4536.2  295.01  4578.6  292.89  4705.9   287.6  4790.8  285.08  4819.1  284.77
  4875.6  284.54  4960.5  284.95  4971.1  285.51  4978.2  285.51  4988.8  283.27
  5002.7  279.83  5005.9  280.33  5017.1  284.32  5031.2  285.29  5045.3  284.81
  5073.6   284.5  5144.3  284.41  5229.2  283.21  5257.5  283.18  5299.9  285.52
  5328.2  288.33  5346.1  289.48  5441.3  297.42  5491.3  300.52  5540.3  302.88
#Mann= 5 ,-1 , 0
  4408.9      .1       0  4988.8     .05       0  5017.1      .1       0
  5346.1     .08       0  5491.3     .07       0
Bank Sta=4988.8,5017.1
XS Rating Curve= 0 ,0
Exp/Cntr=0.3,0.1

Type RM Length L Ch R = 1 ,52922   ,762,762,762
BEGIN DESCRIPTION:
HOLLAND CREEK 63.0
END DESCRIPTION:
XS GIS Cut Line= 3
       3670968.5     10165240.25      3670618.49     10165540.25
      3669942.11     10166541.64
#Sta/Elev= 30
  4339.9  316.93  4423.7  311.04    4473  309.28  4565.2  304.35  4636.6  298.76
  4692.6  295.91  4763.9  290.41  4820.9  286.93  4850.8  286.46  4971.5  280.81
  4985.8  279.24  5000.5   275.4  5003.8   275.9  5015.7  279.99  5021.8  281.19
  5093.7  281.55  5210.5  280.84  5252.5  279.73  5267.5  280.04  5288.5  278.88
  5303.5  279.98    5418  280.37  5468.3  281.36  5519.3  283.26  5555.2  286.33
  5576.2  288.91  5612.2  291.29  5707.6  295.11  5900.7  307.09  6009.3  312.18
#Mann= 3 ,-1 , 0
  4339.9      .1       0  4971.5     .05       0  5015.7      .1       0
Bank Sta=4971.5,5021.8
XS Rating Curve= 0 ,0
Exp/Cntr=0.3,0.1

Type RM Length L Ch R = 1 ,52161   ,980,980,980
BEGIN DESCRIPTION:
HOLLAND CREEK 61.0
END DESCRIPTION:
XS GIS Cut Line= 3
      3670497.66     10164790.25      3670197.66     10164890.25
      3669592.12     10166141.62
#Sta/Elev= 30
  4153.3  321.83  4263.8  319.38  4358.7  314.69  4433.2   309.8  4581.1  301.84
  4609.2  299.06  4648.8  297.17  4682.6  294.41  4767.4  290.23  4893.2  279.48
  4976.2  275.71  4982.1   276.4  4993.2  272.83  4995.8  270.28  4998.5  269.78
  5001.8  270.28  5004.3  273.34  5015.4  277.23  5126.5  276.68  5337.6     278
  5359.8   277.4  5484.2  279.29  5537.6  278.34  5559.8  279.15  5597.2   278.9
  5642.4  281.19  5687.5  285.56  5726.4  288.34  5732.7  289.57  5859.7  296.53
#Mann= 3 , 0 , 0
  4153.3      .1       0  4982.1    .035       0  5015.4      .1       0
Bank Sta=4982.1,5015.4
XS Rating Curve= 0 ,0
Exp/Cntr=0.3,0.1

Type RM Length L Ch R = 1 ,51181   ,1400,1400,1400
BEGIN DESCRIPTION:
HOLLAND CREEK 59.0
END DESCRIPTION:
XS GIS Cut Line= 3
      3669236.55     10164359.68      3669186.55      10164759.7
       3669542.1     10166091.63
#Sta/Elev= 30
  4460.3  309.33  4522.7  308.75  4537.2  307.34  4563.1  302.29  4623.5  295.77
  4663.8  293.19  4861.9  276.38  4927.5  273.76    4978  273.61  4983.2  273.21
  4989.6  264.35  4999.7   262.6    5003   263.1  5018.1  272.01  5023.3  271.35
  5058.2  272.83  5063.4  272.21  5124.2  273.56  5178.4  274.36  5333.6  274.24
  5373.7  273.97  5393.3   272.6  5403.4     274  5408.6   273.5    5414  274.33
  5434.7   274.6  5962.6  276.94  6069.4  282.08  6144.4  288.71    6242  295.28
#Mann= 3 , 0 , 0
  4460.3      .1       0    4978    .035       0  5124.2      .1       0
Bank Sta=4978,5124.2
XS Rating Curve= 0 ,0
Exp/Cntr=0.3,0.1

Type RM Length L Ch R = 1 ,49780   ,905,905,905
BEGIN DESCRIPTION:
HOLLAND CREEK 58.0
END DESCRIPTION:
XS GIS Cut Line= 3
       3667892.1      10163291.6      3668192.11     10164491.64
       3669442.1     10166041.64
#Sta/Elev= 30
  3789.7  311.75  3931.5  295.37  3972.7  292.36  4026.8  285.03    4184  272.18
  4243.3  270.19    4385  271.21  4738.1  266.59  4802.5  268.55    4903   268.5
  4944.2  270.37  4954.5   270.1  4962.2  267.61  4975.1  261.44  5003.2  254.21
  5006.5  254.71  5024.1  267.22  5040.3  267.86  5048.3   266.3  5069.1  269.14
  5083.5  269.23    5141  269.36  5161.8  268.04  5190.6  269.44  5432.1  270.71
  5481.7  269.81  6150.2  272.08    6726  276.36  6882.8  282.54  7017.9  293.18
#Mann= 3 , 0 , 0
  3789.7      .1       0  4962.2     .05       0  5024.1      .1       0
#XS Ineff= 2 , 0
         4943.44  271.13
Permanent Ineff=
       F       F
Bank Sta=4962.2,5024.1
XS Rating Curve= 0 ,0
Exp/Cntr=0.3,0.1

Type RM Length L Ch R = 1 ,48875   ,678,678,678
BEGIN DESCRIPTION:
HOLLAND CREEK 57.0
END DESCRIPTION:
XS GIS Cut Line= 3
       3667592.1     10163391.65      3667392.11     10164491.64
      3667093.18     10165588.21
#Sta/Elev= 30
  3914.2  311.42  4015.8  307.95    4106  291.14  4164.5  283.52  4320.7  269.97
  4540.9  266.89  4574.8  266.15  4595.2  258.55  4605.3  258.01  4611.7  261.36
  4616.8   257.3  4635.8  265.24    4646  266.64  4847.1  266.68  4920.4  266.33
  4930.6  265.46  4947.1  259.61  4961.1   261.4  5005.3  249.38  5042.6  261.85
  5054.7  266.34    5084  266.04  5104.8  260.26  5115.1  260.22    5129  262.21
  5135.9   266.3  5146.2  266.88  5282.8   267.3  5619.7  283.29  6168.8  291.51
#Mann= 5 ,-1 , 0
  3914.2     .05       0  4540.9     .12       0  4847.1     .05       0
  4961.1    .035       0  5042.6     .05       0
#XS Ineff= 2 , 0
         4655.68  267.03 5069.89          266.23
Permanent Ineff=
       F       F
Bank Sta=4961.1,5042.6
XS Rating Curve= 0 ,0
Exp/Cntr=0.3,0.1

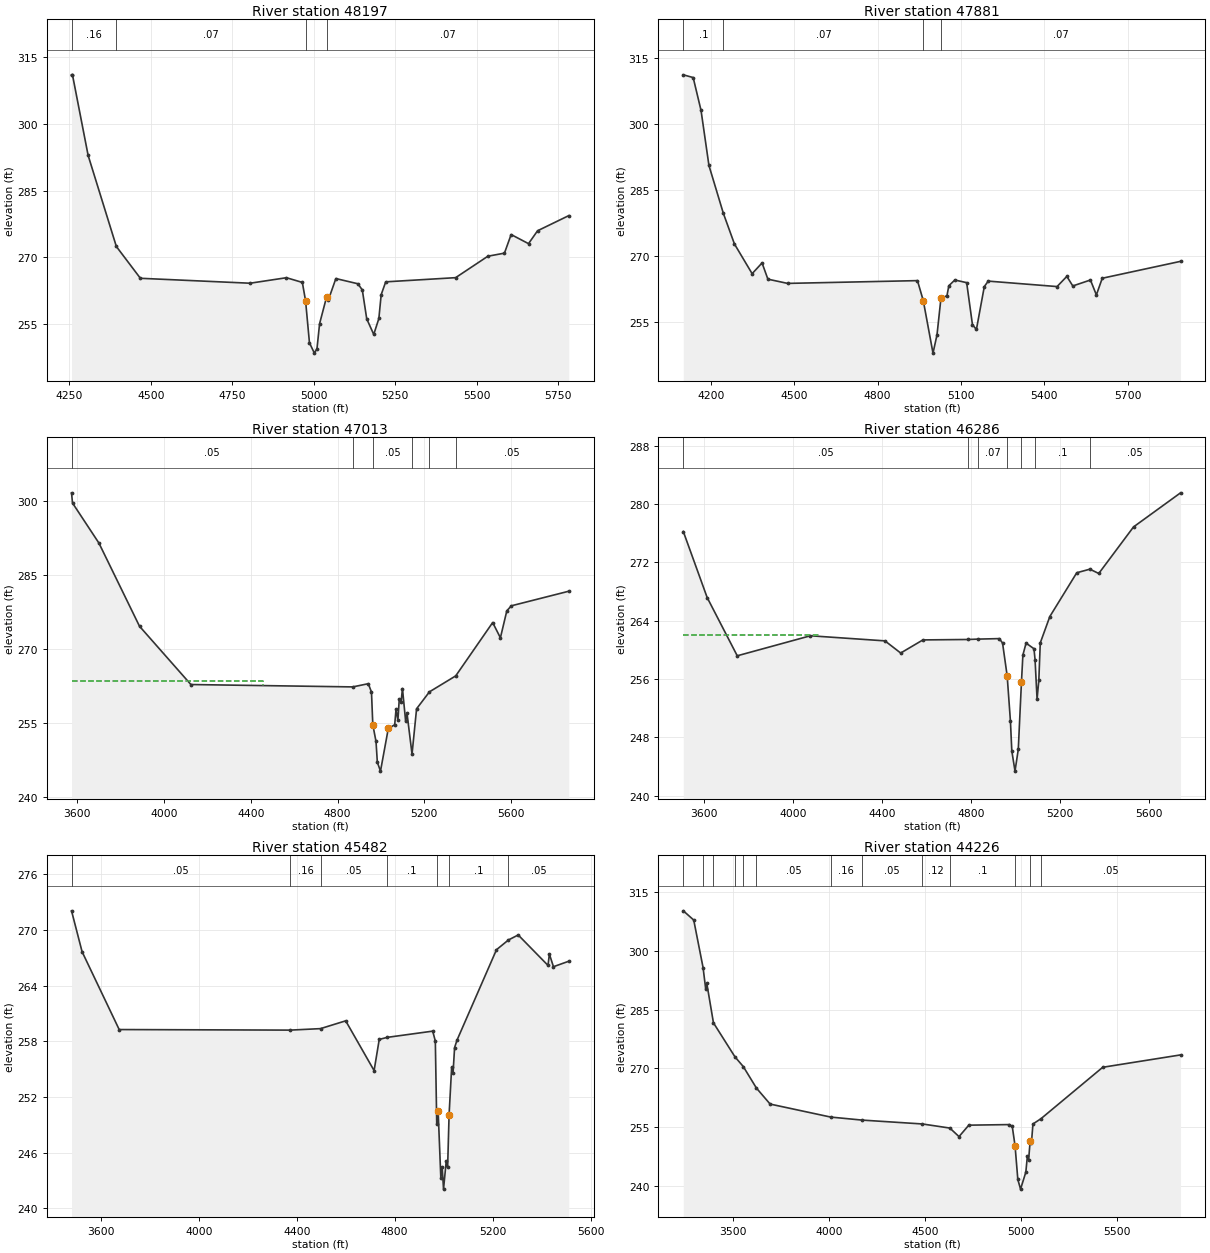
Type RM Length L Ch R = 1 ,48197   ,316,316,316
BEGIN DESCRIPTION:
HOLLAND CREEK 55.0
END DESCRIPTION:
XS GIS Cut Line= 3
      3667192.12     10163491.61      3666704.59     10164325.73
      3666604.58     10164875.77
#Sta/Elev= 30
    4257  311.09  4259.9  311.09  4307.9  292.95  4394.5  272.44  4468.2  265.28
  4804.6  264.17  4916.2  265.41    4965  264.35  4974.9   260.2  4986.8  250.75
  5001.9  248.43  5009.9  249.43  5017.9  255.06  5039.3  261.07  5045.1  260.47
  5067.8  265.22  5135.2  264.05  5148.9  262.66  5162.5  256.14    5184  252.64
  5199.7  256.23  5206.8  261.59  5220.7  264.48  5435.1  265.42  5534.1  270.25
  5584.9  270.94  5605.4  275.13  5658.7  273.08  5686.5  275.98  5782.2  279.39
#Mann= 4 ,-1 , 0
    4257     .16       0  4394.5     .07       0  4974.9     .05       0
  5039.3     .07       0
Bank Sta=4974.9,5039.3
XS Rating Curve= 0 ,0
Exp/Cntr=0.3,0.1

Type RM Length L Ch R = 1 ,47881   ,868,868,868
BEGIN DESCRIPTION:
HOLLAND CREEK 54.0
END DESCRIPTION:
XS GIS Cut Line= 3
      3667192.13     10163441.62      3666305.69     10164258.77
      3665885.66     10164663.49
#Sta/Elev= 30
  4101.2  311.23  4136.7  310.61    4165  303.14  4193.4  290.64  4245.3  279.76
  4285.2   272.8  4348.8  266.06  4384.5   268.5  4405.5  264.81  4476.4  263.85
  4943.6  264.48  4964.6  259.91  4999.5  248.01  5013.9  252.16  5028.1  260.48
  5049.7  261.05  5056.5  263.32    5078  264.62  5120.6  264.02  5141.5  254.45
  5155.7  253.39  5184.1  263.13  5198.2  264.37  5445.8  263.13    5481  265.44
  5502.4  263.27  5565.9  264.62  5587.3  261.23  5608.4  265.02  5890.1  268.86
#Mann= 4 ,-1 , 0
  4101.2      .1       0  4245.3     .07       0  4964.6    .035       0
  5028.1     .07       0
#XS Ineff= 2 , 0
                         5081.82          263.63
Permanent Ineff=
       F       F
Bank Sta=4964.6,5028.1
XS Rating Curve= 0 ,0
Exp/Cntr=0.3,0.1

Type RM Length L Ch R = 1 ,47013   ,727,727,727
BEGIN DESCRIPTION:
HOLLAND CREEK 52.0
END DESCRIPTION:
XS GIS Cut Line= 3
      3667120.34     10162803.75      3665435.16     10164001.36
      3665335.16     10164201.37
#Sta/Elev= 30
  3574.4  301.66  3578.9   299.6  3700.6  291.49  3887.6  274.65  4124.3  262.85
  4870.3  262.37  4941.6  263.02  4956.4  261.33  4962.5  254.72  4977.3  251.32
  4983.4  247.11  4997.9  245.32  5033.9  253.95  5063.4  254.71  5069.5  257.83
  5078.2  255.66  5084.3  259.85  5092.9  259.28  5099.1  262.04  5113.8  255.42
    5120  257.06  5143.2  248.77  5164.2  257.94  5223.4  261.37  5344.5   264.6
  5514.8   275.4  5550.4  272.31    5580  277.78  5600.9  278.79  5865.4  281.74
#Mann= 6 ,-1 , 0
  3574.4     .05       0  4870.3     .07       0  4962.5     .05       0
  5143.2     .07       0  5223.4      .1       0  5344.5     .05       0
#XS Ineff= 2 , 0
         4455.47  263.51
Permanent Ineff=
       F       F
Bank Sta=4962.5,5033.9
XS Rating Curve= 0 ,0
Exp/Cntr=0.3,0.1

Type RM Length L Ch R = 1 ,46286   ,805,805,805
BEGIN DESCRIPTION:
HOLLAND CREEK 51.0
END DESCRIPTION:
XS GIS Cut Line= 3
       3666542.1     10162441.65      3665342.11     10163341.64
      3664773.11      10163810.7
#Sta/Elev= 30
  3506.2  276.24  3613.5  267.18  3748.9  259.18  4078.1  261.93  4413.5  261.23
  4484.3  259.56  4584.3  261.36  4787.6  261.42  4830.8  261.47  4928.1  261.54
  4942.7  260.93  4963.5  256.41  4978.1  250.22  4984.3  246.13  4998.7  243.35
  5013.4  246.32  5027.7  255.57  5034.2  259.29  5048.5  260.92    5084  260.15
  5088.9  258.67    5098  253.23  5105.9  255.81  5112.4  260.95  5155.4  264.57
  5276.6  270.58  5335.5  271.07  5375.6  270.48    5532  276.87  5743.6  281.55
#Mann= 7 ,-1 , 0
  3506.2     .05       0  4787.6      .1       0  4830.8     .07       0
  4963.5     .05       0  5027.7     .07       0  5088.9      .1       0
  5335.5     .05       0
#XS Ineff= 2 , 0
         4111.71  262.01
Permanent Ineff=
       F       F
Bank Sta=4963.5,5027.7
XS Rating Curve= 0 ,0
Exp/Cntr=0.3,0.1

Type RM Length L Ch R = 1 ,45482   ,1255,1255,1255
BEGIN DESCRIPTION:
HOLLAND CREEK 49.0
END DESCRIPTION:
XS GIS Cut Line= 3
      3666342.07     10162041.67      3665229.56     10162813.49
      3664627.34     10163123.16
#Sta/Elev= 30
    3480  272.05  3523.2  267.64  3674.7  259.26  4373.7   259.2  4497.1  259.36
  4599.9   260.2    4716  254.84    4737   258.2    4770  258.42  4955.4  259.09
  4966.1  258.02  4971.9  249.04  4977.5  250.54  4988.5  243.32  4994.1  244.47
  4999.6  242.07  5010.7  245.12  5016.3   244.4  5022.3  250.09  5032.8   255.2
  5038.5  254.59  5044.8  257.32    5055  258.14  5215.9  267.86  5264.7  268.91
  5304.6  269.45  5426.4  266.17    5432  267.39  5448.6  266.03  5511.2  266.62
#Mann= 7 ,-1 , 0
    3480     .05       0  4373.7     .16       0  4497.1     .05       0
    4770      .1       0  4971.9     .05       0  5022.3      .1       0
  5264.7     .05       0
Bank Sta=4977.5,5022.3
XS Rating Curve= 0 ,0
Exp/Cntr=0.3,0.1

Type RM Length L Ch R = 1 ,44226   ,689,689,689
BEGIN DESCRIPTION:
HOLLAND CREEK 47.0
END DESCRIPTION:
XS GIS Cut Line= 3
      3666488.42     10161234.29      3665092.58      10161907.9
      3664278.25     10162545.78
#Sta/Elev= 30
  3244.2  310.28  3298.4  307.92  3346.9  295.79  3360.7  290.28  3366.2  291.76
  3400.9  281.66  3512.6  272.98  3556.1  270.48  3624.3  264.99  3695.4  260.91
    4010  257.59  4172.3  256.82  4486.3  255.83  4629.4  254.78  4677.1   252.6
    4728  255.52  4939.4  255.67  4953.8   255.2  4968.3   250.3  4982.8  241.64
    4997  239.18  5024.4  243.53  5032.5  247.65  5038.8  246.64  5046.9  251.49
  5053.3  250.85  5061.4  255.83    5103  257.17    5424  270.31  5828.5  273.47
#Mann= 13 ,-1 , 0
  3244.2     .05       0  3346.9     .16       0  3400.9     .05       0
  3512.6     .16       0  3556.1     .12       0  3624.3     .05       0
    4010     .16       0  4172.3     .05       0  4486.3     .12       0
  4629.4      .1       0  4968.3     .05       0  5046.9      .1       0
    5103     .05       0
Bank Sta=4968.3,5046.9
XS Rating Curve= 0 ,0
Exp/Cntr=0.3,0.1

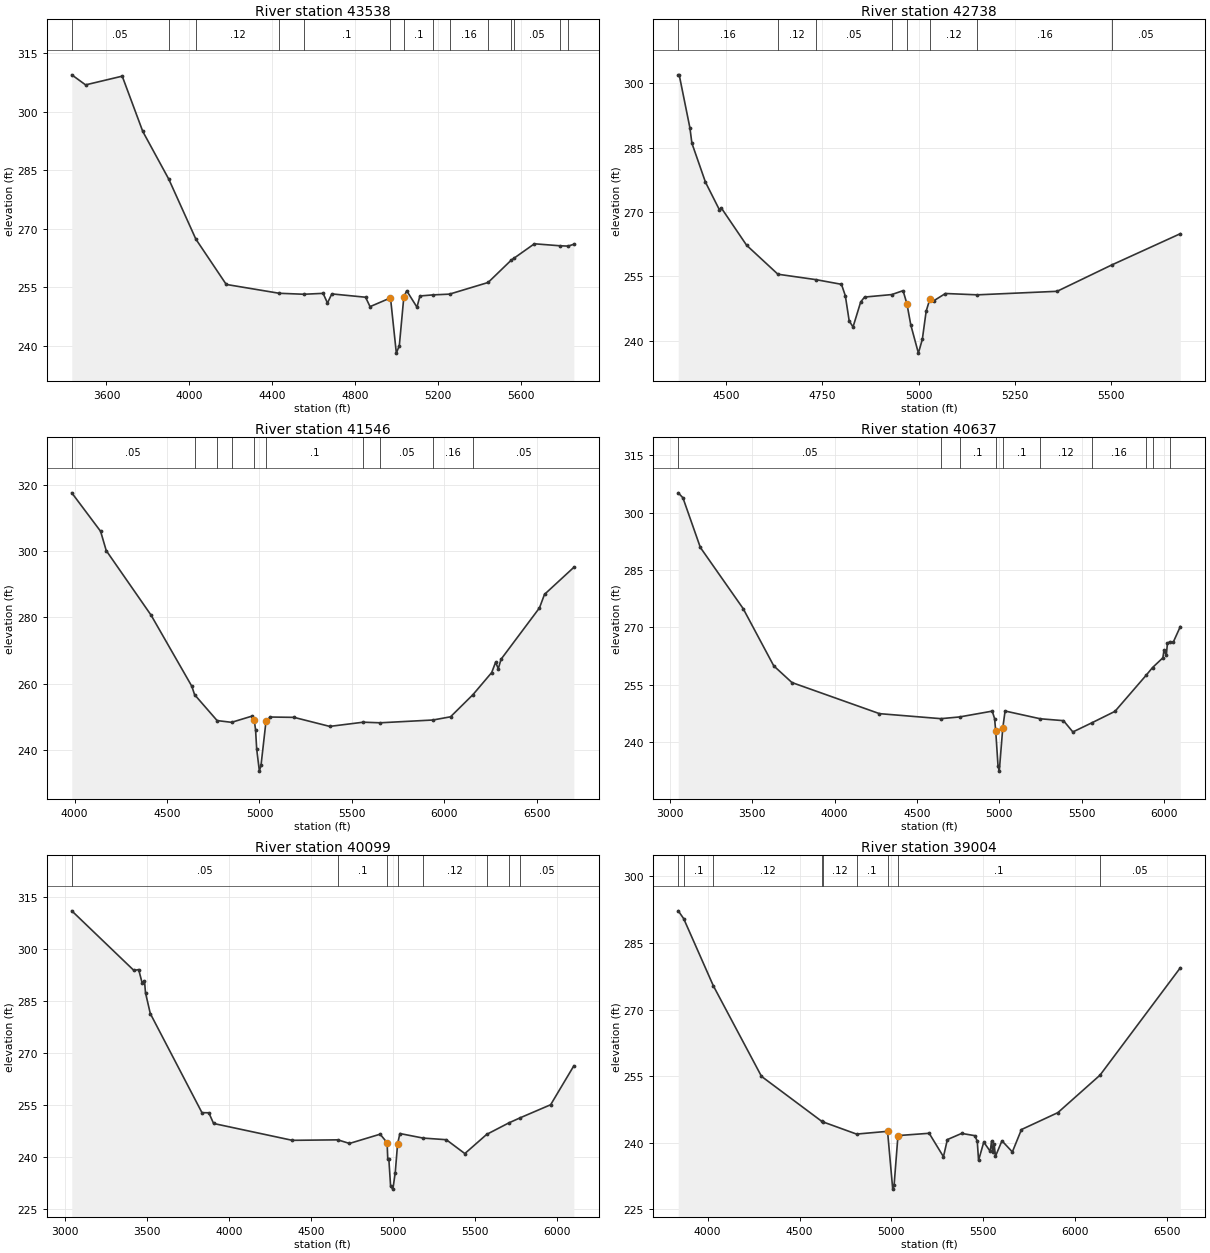
Type RM Length L Ch R = 1 ,43538   ,799,799,799
BEGIN DESCRIPTION:
HOLLAND CREEK 45.0
END DESCRIPTION:
XS GIS Cut Line= 3
      3665745.36     10160310.68      3665037.03     10161060.68
      3664002.33     10161991.22
#Sta/Elev= 30
  3432.5  309.39  3499.2  306.82    3676  309.05  3775.2  294.91    3901  282.67
  4031.4  267.36  4178.1  255.77  4433.8  253.51  4553.2  253.26  4645.6  253.49
  4666.6  251.01  4687.5  253.35  4850.5   252.5  4872.1  250.09  4970.8  252.33
    4999   238.2  5013.4  240.12  5035.1  252.55    5049  254.16  5098.6  249.95
  5112.8  252.82  5176.4   253.1  5255.6  253.29  5441.9  256.27  5554.2  262.02
  5568.8  262.55  5665.2  266.17  5788.5  265.66  5828.2  265.58  5855.7  266.05
#Mann= 14 ,-1 , 0
  3432.5     .05       0    3901      .1       0  4031.4     .12       0
  4433.8     .05       0  4553.2      .1       0  4970.8     .05       0
  5035.1      .1       0  5176.4     .12       0  5255.6     .16       0
  5441.9     .05       0  5554.2     .16       0  5568.8     .05       0
  5788.5     .16       0  5828.2     .05       0
Bank Sta=4970.8,5035.1
XS Rating Curve= 0 ,0
Exp/Cntr=0.3,0.1

Type RM Length L Ch R = 1 ,42738   ,1192,1192,1192
BEGIN DESCRIPTION:
HOLLAND CREEK 43.0
END DESCRIPTION:
XS GIS Cut Line= 3
       3664092.1     10160341.67      3664034.33     10160750.82
      3664042.11     10161641.68
#Sta/Elev= 30
  4375.8  301.97  4378.3  301.97  4406.1  289.62  4411.3  286.04  4446.5  276.97
  4482.4  270.59  4487.5  270.98  4553.5  262.26  4634.7  255.52  4733.4  254.26
  4799.8  253.17  4809.8  250.51  4819.8  244.67  4829.8  243.23  4849.8  249.08
  4859.8   250.2  4930.3  250.78  4959.8  251.69  4969.8  248.63  4979.8  243.73
  4999.6  237.14  5009.8  240.35  5019.8  246.92  5029.8  249.85  5039.8  249.35
  5069.8  251.03  5152.7  250.72  5359.8  251.54  5502.3   257.7  5679.9  264.96
#Mann= 8 ,-1 , 0
  4375.8     .16       0  4634.7     .12       0  4733.4     .05       0
  4930.3     .12       0  4969.8     .07       0  5029.8     .12       0
  5152.7     .16       0  5502.3     .05       0
Bank Sta=4969.8,5029.8
XS Rating Curve= 0 ,0
Exp/Cntr=0.3,0.1

Type RM Length L Ch R = 1 ,41546   ,910,910,910
BEGIN DESCRIPTION:
HOLLAND CREEK 42.0
END DESCRIPTION:
XS GIS Cut Line= 3
      3664016.21     10160039.84      3663391.19     10160137.07
       3661692.1     10161341.65
#Sta/Elev= 30
  3984.8  317.64  4140.8  306.01  4171.1   300.2    4414  280.66  4634.2   259.2
    4649  256.67  4770.8  248.85  4849.1  248.32  4957.9  250.17  4971.7  248.93
  4978.8  246.07  4984.9  240.24  4999.4  233.58  5008.3  235.35  5035.3  248.66
  5057.5  249.92  5186.7  249.82  5379.9  247.09  5561.3  248.36  5652.5  248.18
  5937.9  249.02  6033.2  249.99  6154.8   256.7  6255.9  263.36  6276.8  266.45
  6291.6  264.54  6306.4  267.37  6514.3   282.9  6541.4  286.97  6700.1  295.14
#Mann= 10 ,-1 , 0
  3984.8     .05       0    4649     .12       0  4770.8     .07       0
  4849.1      .1       0  4971.7     .05       0  5035.3      .1       0
  5561.3     .16       0  5652.5     .05       0  5937.9     .16       0
  6154.8     .05       0
Bank Sta=4971.7,5035.3
XS Rating Curve= 0 ,0
Exp/Cntr=0.3,0.1

Type RM Length L Ch R = 1 ,40637   ,537,537,537
BEGIN DESCRIPTION:
HOLLAND CREEK 40.0
END DESCRIPTION:
XS GIS Cut Line= 3
      3664120.38     10159366.23      3662799.31     10159468.54
      3661492.13     10160591.62
#Sta/Elev= 30
  3050.6  305.18    3079  303.89  3184.8  290.91  3444.7  274.93  3630.6  259.96
  3740.9   255.6  4272.5  247.47  4645.6  246.16  4758.6  246.61  4957.2  248.13
  4971.5  246.15  4978.4  242.85  4992.3  233.76  4999.8  232.45  5020.9  243.67
  5035.1  248.16  5248.8  246.13  5389.6  245.64  5446.7  242.69  5564.9  245.14
  5702.3  248.07  5890.9  257.47  5930.2  259.51  5993.1  262.06  5999.7  264.01
    6014   262.7  6020.6  265.82    6035  266.27  6056.8  266.21    6099  270.23
#Mann= 10 ,-1 , 0
  3050.6     .05       0  4645.6     .12       0  4758.6      .1       0
  4978.4     .05       0  5020.9      .1       0  5248.8     .12       0
  5564.9     .16       0  5890.9      .1       0  5930.2     .16       0
    6035      .1       0
Bank Sta=4978.4,5020.9
XS Rating Curve= 0 ,0
Exp/Cntr=0.3,0.1

Type RM Length L Ch R = 1 ,40099   ,1095,1095,1095
BEGIN DESCRIPTION:
HOLLAND CREEK 39.0
END DESCRIPTION:
XS GIS Cut Line= 3
      3663642.08     10158241.66      3662092.11     10159391.64
      3661292.08     10160191.67
#Sta/Elev= 30
  3042.7  311.14  3421.4  293.94  3450.6  294.19  3471.4   290.4  3486.1  290.93
  3492.3  287.48  3521.5   281.5  3836.6   252.9  3878.3  252.87  3907.5  249.78
  4387.5  244.92  4664.9  245.06  4736.1  244.02  4922.9  246.69  4965.4  244.25
  4969.6  239.42  4976.2  239.42  4986.8  231.68  5000.7  230.84  5015.1   235.6
  5029.3  243.84  5043.4  246.88  5184.8  245.57  5326.3   245.1  5439.4   241.1
  5572.5  246.63  5707.8  249.95  5778.8  251.46  5962.6  255.19  6104.1  266.42
#Mann= 8 ,-1 , 0
  3042.7     .05       0  4664.9      .1       0  4965.4     .05       0
  5029.3      .1       0  5184.8     .12       0  5572.5     .05       0
  5707.8      .1       0  5778.8     .05       0
Bank Sta=4965.4,5029.3
XS Rating Curve= 0 ,0
Exp/Cntr=0.3,0.1

Type RM Length L Ch R = 1 ,39004   ,1017,1017,1017
BEGIN DESCRIPTION:
HOLLAND CREEK 37.0
END DESCRIPTION:
XS GIS Cut Line= 3
      3662870.38     10157609.27      3661312.94     10159204.14
      3660812.92     10159254.14
#Sta/Elev= 30
  3840.2  292.26  3869.7  290.51  4031.2  275.37  4293.2  254.97  4621.8  244.82
  4625.9  244.74  4810.3  241.97  4979.1  242.59  5007.2  229.57  5014.6  230.41
  5035.7  241.63  5205.5  242.15  5283.2  236.87  5304.5  240.73  5382.2  242.12
  5452.9  241.62  5467.1  240.41  5474.2  236.04  5502.5  240.16  5537.8  238.08
  5544.9  240.39  5551.9  237.93  5559.1  239.69  5566.1  236.96  5601.5  240.45
  5658.1  237.95  5707.5  242.99  5905.6   246.8  6135.1  255.25  6571.9  279.43
#Mann= 9 ,-1 , 0
  3840.2     .05       0  3869.7      .1       0  4031.2     .12       0
  4621.8     .16       0  4625.9     .12       0  4810.3      .1       0
  4979.1     .05       0  5035.7      .1       0  6135.1     .05       0
Bank Sta=4979.1,5035.7
XS Rating Curve= 0 ,0
Exp/Cntr=0.3,0.1