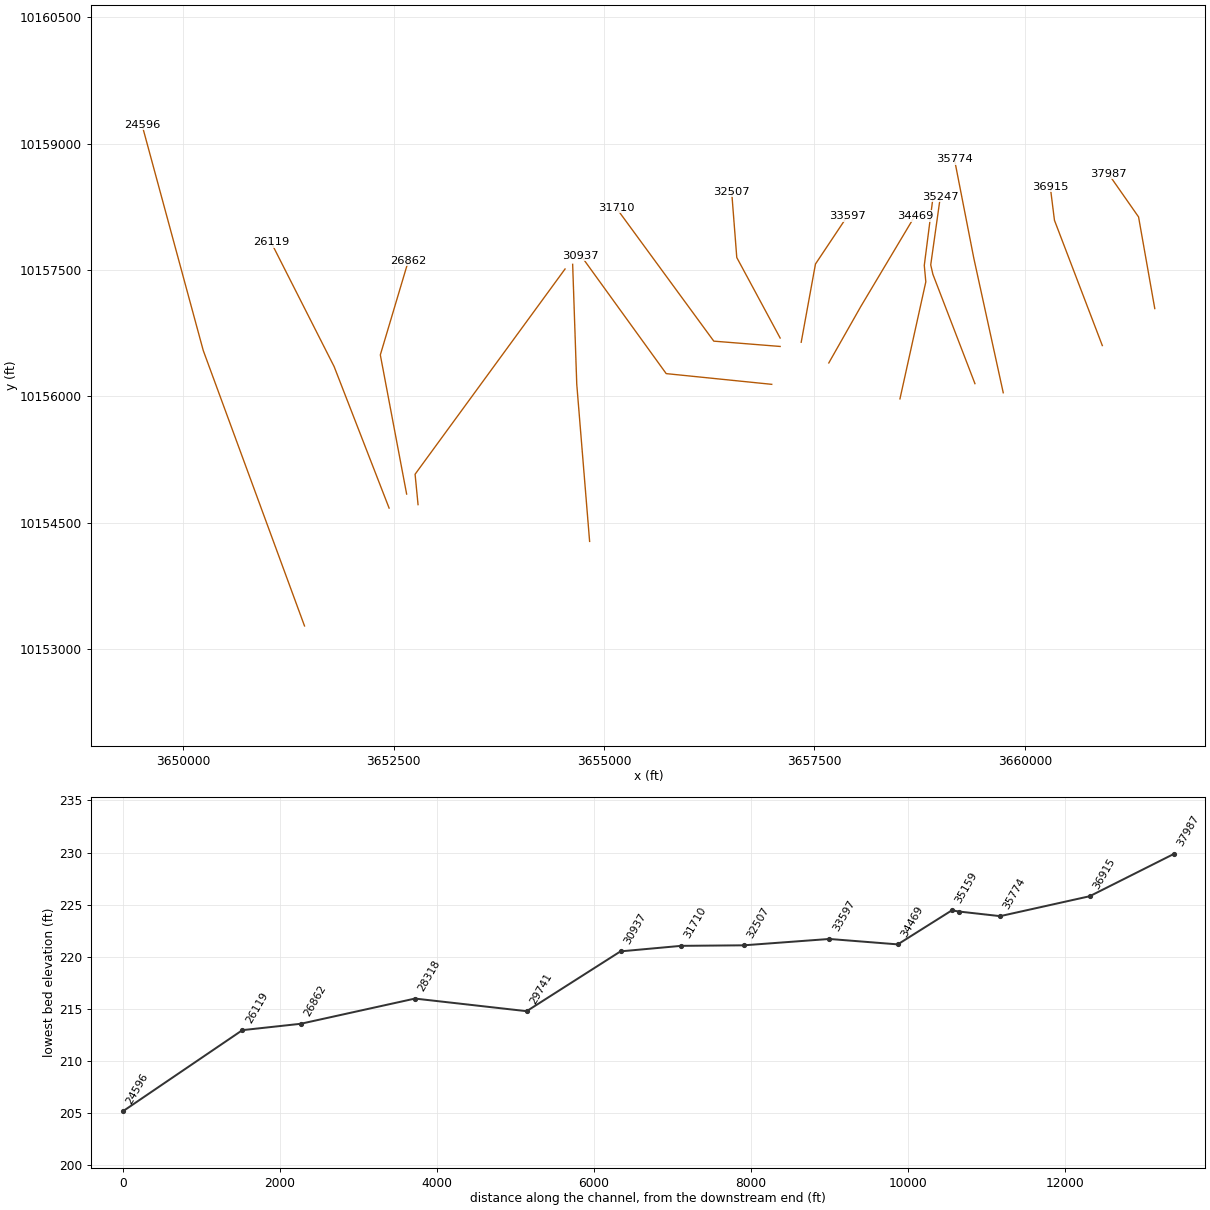
HEC-RAS study HOLLAND CREEK.prj: HOLLAND CREEK Base Level Engineering

--- HOLLAND CREEK.g01 (geometry) --- (continued)

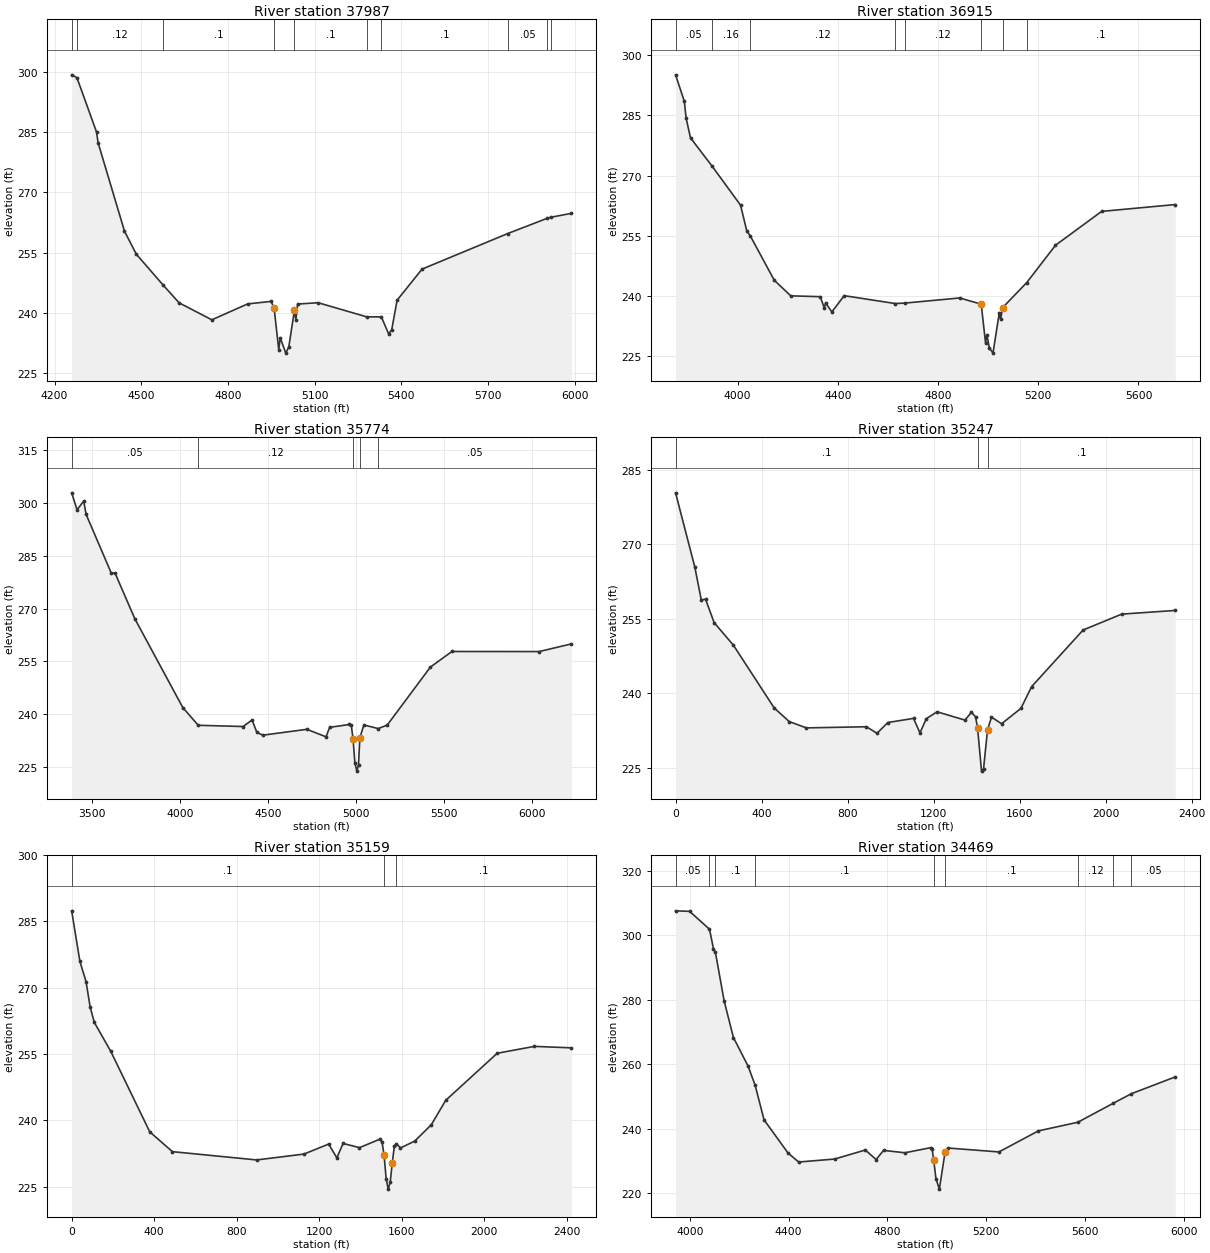
Type RM Length L Ch R = 1 ,37987   ,1073,1073,1073
BEGIN DESCRIPTION:
HOLLAND CREEK 35.0
END DESCRIPTION:
XS GIS Cut Line= 3
       3661542.1     10157041.66      3661349.53     10158130.12
       3660992.1     10158641.66
#Sta/Elev= 30
  4259.2  299.39  4277.4  298.69  4345.4  285.07  4350.6  282.45    4442  260.34
  4482.6  254.62  4574.9  246.94  4631.1  242.43  4744.3  238.19  4868.5  242.17
  4949.7  242.79  4959.9  241.04  4975.9  230.73    4981   233.7  5000.3  229.87
  5010.7  231.44    5030  240.52  5035.1  238.22  5041.1  242.13  5112.2  242.46
    5280  238.94  5330.9  238.92    5356   234.7  5366.7  235.67  5385.5   243.1
  5471.8  250.86  5768.6  259.75  5904.2  263.53  5916.8   263.8  5988.6  264.79
#Mann= 10 ,-1 , 0
  4259.2     .05       0  4277.4     .12       0  4574.9      .1       0
  4959.9     .05       0    5030      .1       0    5280     .12       0
  5330.9      .1       0  5768.6     .05       0  5904.2      .1       0
  5916.8     .05       0
Bank Sta=4959.9,5030
XS Rating Curve= 0 ,0
Exp/Cntr=0.3,0.1

Type RM Length L Ch R = 1 ,36915   ,1140,1140,1140
BEGIN DESCRIPTION:
HOLLAND CREEK 33.0
END DESCRIPTION:
XS GIS Cut Line= 3
      3660918.99      10156602.3      3660350.44     10158090.25
      3660300.66     10158488.48
#Sta/Elev= 30
  3752.7  295.08  3787.7  288.47  3794.8   284.3  3812.4  279.38  3898.6  272.34
  4012.2  262.62  4036.9  256.21  4050.4  255.05  4146.5  243.96  4212.3  240.07
  4330.1  239.86  4346.2  237.06  4351.6  238.31  4376.3  236.06  4425.7  240.11
  4629.7  238.15  4666.5  238.26  4886.7  239.54  4972.4  237.99  4989.6  228.41
  4994.9  230.42  5004.5  227.17  5019.4  225.81  5044.3  235.75  5049.7  234.27
    5058  237.14  5153.9  243.36  5268.8  252.66  5452.9  261.09  5746.9  262.79
#Mann= 8 ,-1 , 0
  3752.7     .05       0  3898.6     .16       0  4050.4     .12       0
  4629.7     .05       0  4666.5     .12       0  4972.4     .05       0
    5058     .12       0  5153.9      .1       0
Bank Sta=4972.4,5058
XS Rating Curve= 0 ,0
Exp/Cntr=0.3,0.1

Type RM Length L Ch R = 1 ,35774   ,528,528,528
BEGIN DESCRIPTION:
HOLLAND CREEK 31.0
END DESCRIPTION:
XS GIS Cut Line= 3
       3659742.1     10156041.66      3659392.11     10157641.64
      3659162.12     10158817.14
#Sta/Elev= 30
  3385.8  302.83  3416.5  298.02  3454.1  300.49  3467.7  296.74    3611  280.02
  3631.5  280.13  3744.1  267.13  4016.4  241.94  4104.1   236.9  4358.2  236.55
  4409.4   238.4  4436.8  234.88  4470.8   234.1  4720.5  235.76  4829.1  233.63
  4849.6  236.31  4962.2  237.14  4972.4  236.92  4982.7  232.95  4992.9  226.19
    5004   223.9  5013.4  225.74  5021.1  233.39    5044  236.99  5125.5  235.97
  5176.5  236.97    5421  253.39  5543.3  257.83  6038.3  257.81  6221.4  259.99
#Mann= 5 ,-1 , 0
  3385.8     .05       0  4104.1     .12       0  4982.7     .05       0
  5021.1     .12       0  5125.5     .05       0
Bank Sta=4982.7,5021.1
XS Rating Curve= 0 ,0
Exp/Cntr=0.3,0.1

Type RM Length L Ch R = 1 ,35247   ,87,87,87
XS GIS Cut Line= 4
     3659405.851    10156150.127     3658906.719     10157447.87
     3658880.677    10157560.718     3658994.711    10158369.253
#Sta/Elev= 30
       0280.350889.71451265.3765119.6193258.8015139.5559258.9334 179.429254.2329
269.1435249.6758458.5408237.0637528.3188234.3231 608.065233.0479887.1768233.2761
937.0182231.9589986.8596234.12771106.479234.95781136.384232.05571166.289234.9141
 1216.13236.28131345.718234.61521375.622236.17651394.863235.29631404.135233.0863
1422.679224.34461431.951224.75681450.495232.64131469.038235.20771516.097233.8867
1605.833236.96981655.686241.35481894.981252.74482074.453255.94152323.719256.6845
#Mann= 3 , 0 , 0
       0      .1       01404.135     .05       01450.495      .1       0
Bank Sta=1404.135,1450.495
XS Rating Curve= 0 ,0
Exp/Cntr=0.3,0.1

Type RM Length L Ch R = 1 ,35159   ,690,690,690
XS GIS Cut Line= 4
     3658515.117    10155968.921     3658822.409    10157359.546
      3658804.18    10157554.858     3658906.169    10158351.024
#Sta/Elev= 30
       0287.411739.85408275.987269.74464271.403489.67168265.6618109.5987262.1896
189.3069255.6523378.6138237.4108488.2125232.9363896.7168231.06071125.878232.3892
 1245.44234.64631285.294231.52471315.185234.79131394.893233.8417 1494.24235.7702
1504.162235.15071514.084232.12591524.006226.85311533.929224.45841543.851 226.033
1553.773230.42761563.696234.14191573.618234.76021593.463233.76761663.161235.3443
1743.026239.02341812.907244.55132062.482255.19552242.176256.7472 2421.87256.4177
#Mann= 3 ,-1 , 0
       0      .1       01514.084     .05       01573.618      .1       0
Bank Sta=1514.084,1553.773
XS Rating Curve= 0 ,0
Exp/Cntr=0.3,0.1

Type RM Length L Ch R = 1 ,34469   ,872,872,872
BEGIN DESCRIPTION:
HOLLAND CREEK 28.0
END DESCRIPTION:
XS GIS Cut Line= 3
      3657669.87     10156395.78      3658050.91     10157067.62
      3658692.08     10158141.61
#Sta/Elev= 30
  3942.6  307.62  3999.4  307.46    4080  301.91  4096.1  295.87    4104  294.71
  4139.4  279.61  4176.9  268.27    4236  259.42  4264.7  253.47  4300.9   242.7
  4397.6  232.44  4440.8  229.61  4586.5  230.53  4710.6  233.34  4754.6  230.39
  4784.7  233.22  4871.1  232.48  4975.4  234.06  4981.2  233.67  4987.5  230.38
  4996.8  224.42  5010.6  221.19  5033.7  232.69  5045.8  233.96  5251.7  232.74
  5411.2  239.27  5570.9  241.95  5715.4  247.89  5787.9  250.82  5965.8  256.05
#Mann= 9 ,-1 , 0
  3942.6     .05       0    4080     .16       0    4104      .1       0
  4264.7      .1       0  4987.5     .05       0  5033.7      .1       0
  5570.9     .12       0  5715.4      .1       0  5787.9     .05       0
Bank Sta=4987.5,5033.7
XS Rating Curve= 0 ,0
Exp/Cntr=0.3,0.1

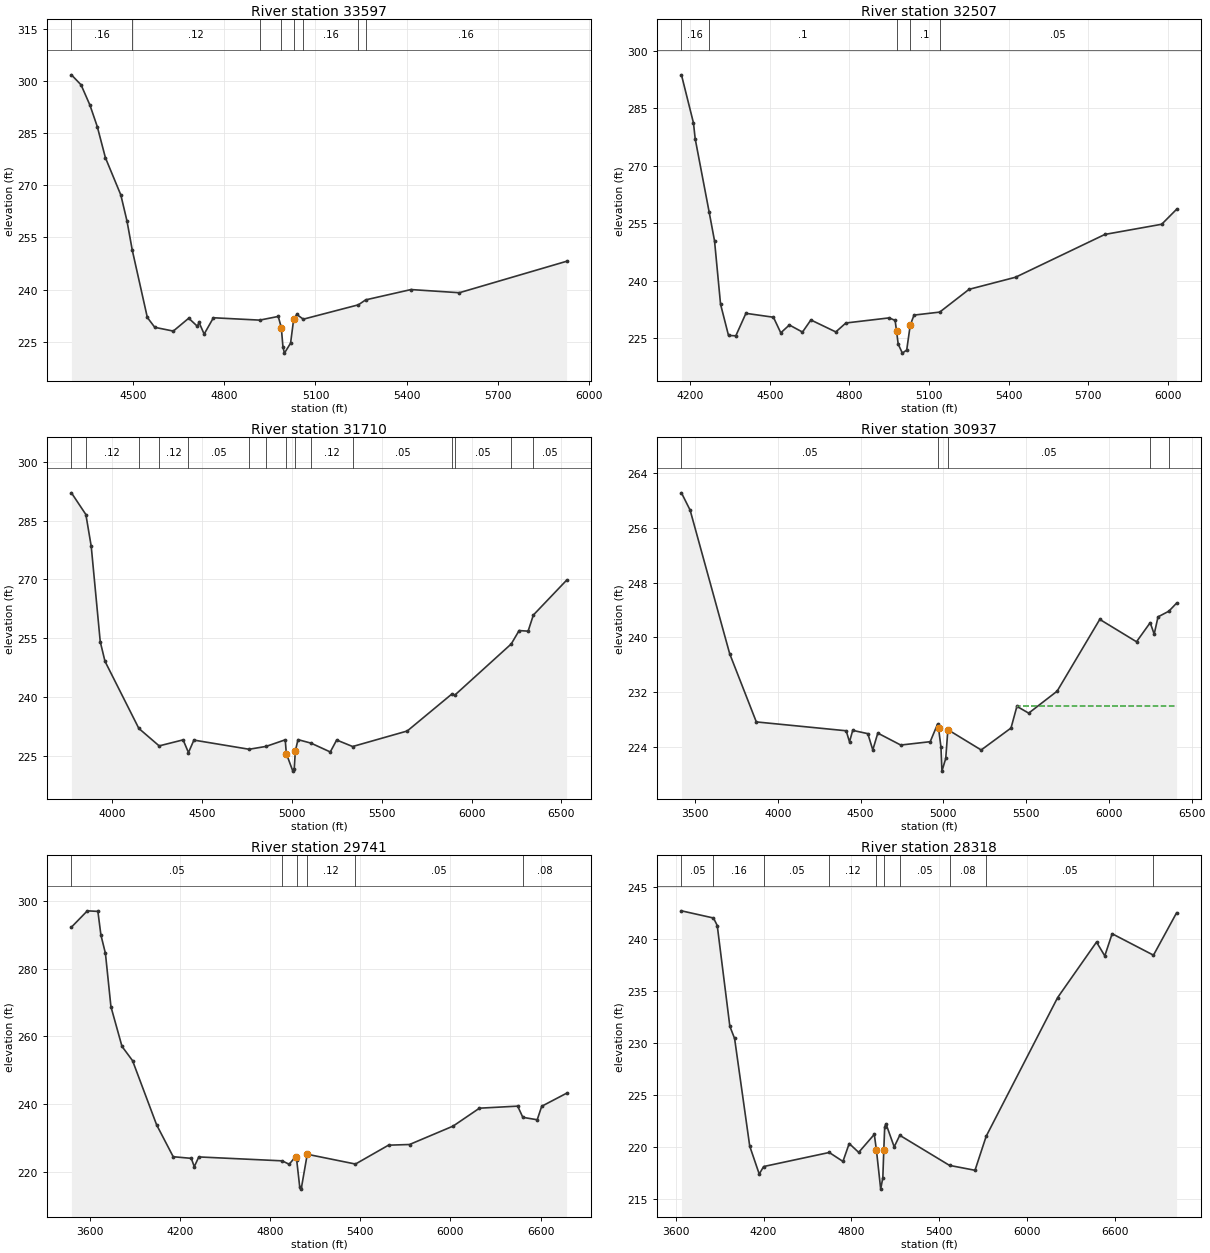
Type RM Length L Ch R = 1 ,33597   ,1090,1090,1090
BEGIN DESCRIPTION:
HOLLAND CREEK 27.0
END DESCRIPTION:
XS GIS Cut Line= 3
       3657342.1      10156641.6      3657511.51     10157570.75
      3657892.11     10158141.65
#Sta/Elev= 30
  4296.4  301.74  4328.2  298.85  4357.4  293.02  4381.5  286.86  4408.3  277.91
  4459.1  267.19  4479.4   259.7  4496.9  251.28  4546.4  231.96  4570.9  229.13
  4631.9  228.05  4682.7  231.75  4711.3  229.42  4716.4  230.59  4733.5  227.19
    4764  231.88  4916.5   231.2  4977.5  232.26  4987.6  229.07    4993  223.46
  4997.9  221.71  5018.1  224.58  5028.3  231.45  5038.5  232.83    5060  231.47
  5241.3   235.6  5265.5  237.03  5414.7  239.99  5573.9  239.08    5927  248.12
#Mann= 8 ,-1 , 0
  4296.4     .16       0  4496.9     .12       0  4916.5      .1       0
  4987.6     .05       0  5028.3      .1       0    5060     .16       0
  5241.3      .1       0  5265.5     .16       0
Bank Sta=4987.6,5028.3
XS Rating Curve= 0 ,0
Exp/Cntr=0.3,0.1

Type RM Length L Ch R = 1 ,32507   ,797,797,797
BEGIN DESCRIPTION:
HOLLAND CREEK 25.0
END DESCRIPTION:
XS GIS Cut Line= 3
       3657092.1     10156691.66      3656576.85     10157648.03
      3656516.28     10158427.64
#Sta/Elev= 30
  4165.9  293.68  4211.3  281.13  4217.8  276.99  4270.3  257.95  4290.8  250.36
  4313.5  233.85  4343.5  225.71  4371.1  225.62  4409.2  231.48    4513  230.46
  4540.7  226.39  4573.1  228.44  4622.6  226.59  4654.3  229.75  4748.3  226.63
  4786.4  228.96  4949.6  230.29  4972.1  229.64  4977.8  226.75  4983.7  223.46
  4999.5   221.1  5015.9  221.91  5029.2   228.4  5043.5  231.02  5140.4   231.8
  5251.2  237.74  5426.4  240.89  5763.8  252.06    5978  254.71  6034.2  258.62
#Mann= 5 ,-1 , 0
  4165.9     .16       0  4270.3      .1       0  4977.8     .05       0
  5029.2      .1       0  5140.4     .05       0
Bank Sta=4977.8,5029.2
XS Rating Curve= 0 ,0
Exp/Cntr=0.3,0.1

Type RM Length L Ch R = 1 ,31710   ,773,773,773
BEGIN DESCRIPTION:
HOLLAND CREEK 23.0
END DESCRIPTION:
XS GIS Cut Line= 3
      3657092.08     10156591.64      3656303.71     10156654.71
      3655142.12     10158241.62
#Sta/Elev= 30
  3771.4  292.07  3851.9  286.53  3881.7  278.42  3931.9  254.09  3958.2  249.09
  4146.8  231.95    4260  227.49  4393.4  229.03  4423.2  225.78  4453.5  228.97
  4761.1  226.63  4855.5  227.36  4962.1  229.04  4968.2  225.54  5004.4  221.05
  5012.2  221.63  5018.4  226.18  5033.1  229.09  5105.9  228.19    5213  225.94
  5248.5  228.99  5337.5  227.33  5641.5  231.29  5891.2  240.77  5906.5  240.45
  6220.8  253.51  6264.5  256.92  6314.7  256.77  6343.9  260.88  6528.9  269.77
#Mann= 15 ,-1 , 0
  3771.4     .16       0  3851.9     .12       0  4146.8     .05       0
    4260     .12       0  4423.2     .05       0  4761.1     .12       0
  4855.5     .05       0  4968.2    .035       0  5018.4     .05       0
  5105.9     .12       0  5337.5     .05       0  5891.2     .16       0
  5906.5     .05       0  6220.8     .08       0  6343.9     .05       0
Bank Sta=4968.2,5018.4
XS Rating Curve= 0 ,0
Exp/Cntr=0.3,0.1

Type RM Length L Ch R = 1 ,30937   ,1196,1196,1196
BEGIN DESCRIPTION:
HOLLAND CREEK 22.0
END DESCRIPTION:
XS GIS Cut Line= 3
      3656992.11     10156141.64      3655738.41     10156269.01
      3654724.51     10157671.81
#Sta/Elev= 30
  3418.1  261.07  3470.5  258.55  3709.6  237.62  3870.4  227.69  4413.2   226.4
  4433.3  224.78  4452.6  226.46  4543.9  225.98    4574  223.61  4604.2  226.06
  4742.9  224.32  4920.8  224.81  4964.9  227.36  4971.1   226.8  4985.8  224.02
  4991.7  220.52  5014.6  222.37  5027.5  226.56  5228.7   223.6  5408.9   226.8
  5444.5  229.96  5515.7  228.97  5687.4  232.17    5945  242.63    6167  239.37
  6249.7  242.15  6273.7  240.48    6297     243  6362.2  243.82  6409.1     245
#Mann= 5 ,-1 , 0
  3418.1     .05       0  4964.9    .035       0  5027.5     .05       0
  6249.7     .08       0  6362.2     .05       0
#XS Ineff= 2 , 0
                         5442.05          229.95
Permanent Ineff=
       F       F
Bank Sta=4971.1,5027.5
XS Rating Curve= 0 ,0
Exp/Cntr=0.3,0.1

Type RM Length L Ch R = 1 ,29741   ,1423,1423,1423
BEGIN DESCRIPTION:
HOLLAND CREEK 20.0
END DESCRIPTION:
XS GIS Cut Line= 3
      3654828.69     10154275.94      3654675.91     10156144.01
      3654627.32     10157567.17
#Sta/Elev= 30
  3475.1  292.39  3581.2  297.23  3651.4  297.06  3671.5  290.07  3701.6  284.63
  3738.3  268.83  3811.9  257.07  3882.2  252.85  4042.7  233.82  4153.1  224.38
  4273.5   223.9  4293.5  221.43  4323.6  224.32  4879.1  223.16  4925.6  222.14
  4968.8  224.44  4975.8  223.36  4995.9   215.4  5005.6  214.78    5046  225.11
  5367.1  222.21  5587.2   227.8  5727.3     228  6017.4  233.45  6193.1  238.76
  6447.7  239.37    6482  236.05  6577.8  235.33  6607.8  239.33  6773.4  243.19
#Mann= 6 ,-1 , 0
  3475.1     .05       0  4879.1     .12       0  4975.8     .07       0
    5046     .12       0  5367.1     .05       0    6482     .08       0
Bank Sta=4968.8,5046
XS Rating Curve= 0 ,0
Exp/Cntr=0.3,0.1

Type RM Length L Ch R = 1 ,28318   ,1456,1456,1456
BEGIN DESCRIPTION:
HOLLAND CREEK 19.0
END DESCRIPTION:
XS GIS Cut Line= 3
      3652790.72     10154712.46      3652755.56     10155073.87
      3654537.03     10157512.08
#Sta/Elev= 30
  3639.1  242.72    3858  242.03  3883.7  241.31  3969.8  231.63  4002.2  230.46
  4105.6  220.12  4170.5  217.44  4200.7  218.16  4648.9  219.51  4742.5  218.65
  4785.2  220.37  4850.1  219.52  4956.7  221.25  4971.3  219.73  5000.4  215.99
    5015  217.09  5021.5  219.73  5027.7  221.96  5036.2  222.27  5092.6  220.05
  5130.7  221.16  5470.5  218.27  5644.7   217.8  5721.1  221.07  6209.3  234.39
  6474.9  239.72  6531.3  238.39  6581.5  240.52  6863.9  238.46  7021.9  242.53
#Mann= 10 ,-1 , 0
  3639.1     .05       0    3858     .16       0  4200.7     .05       0
  4648.9     .12       0  4971.3     .05       0  5021.5     .12       0
  5130.7     .05       0  5470.5     .08       0  5721.1     .05       0
  6863.9     .08       0
Bank Sta=4971.3,5021.5
XS Rating Curve= 0 ,0
Exp/Cntr=0.3,0.1

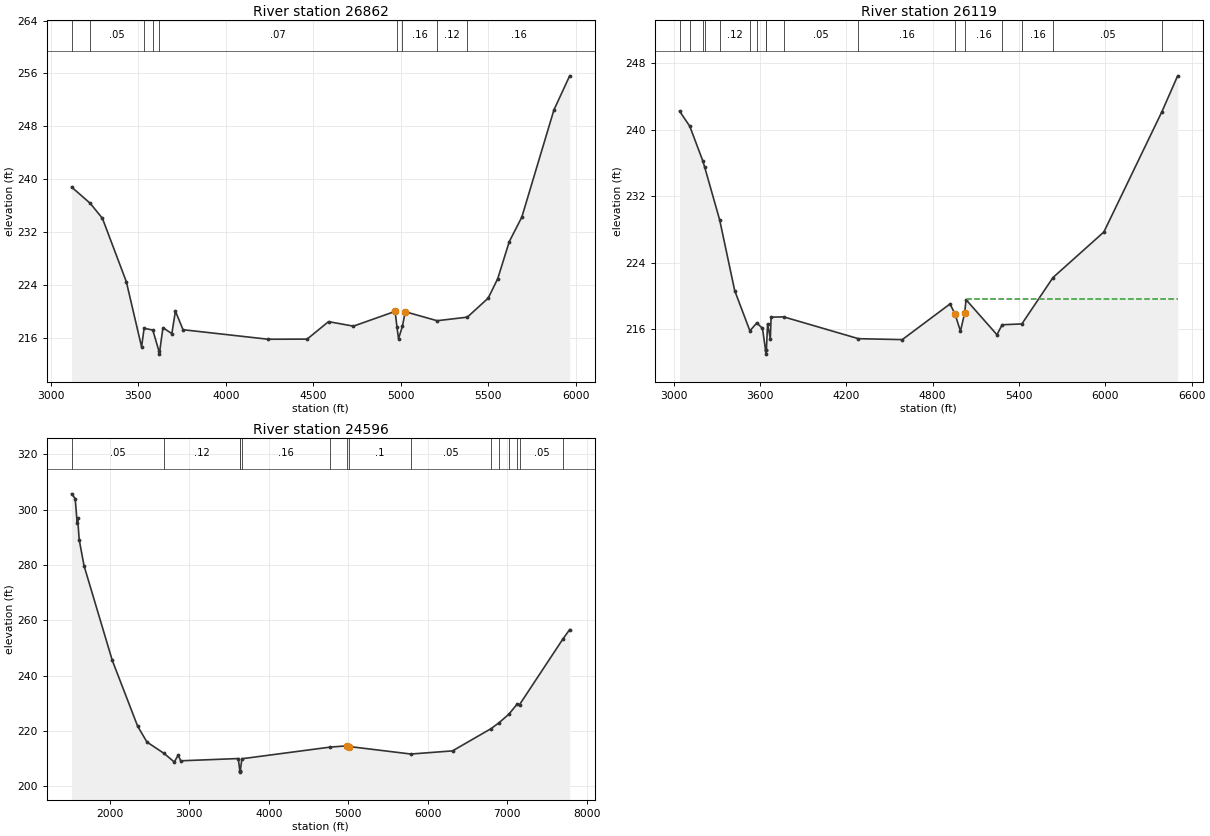
Type RM Length L Ch R = 1 ,26862   ,743,743,743
BEGIN DESCRIPTION:
HOLLAND CREEK 18.0
END DESCRIPTION:
XS GIS Cut Line= 3
      3652655.09     10154838.42      3652342.58     10156491.24
      3652675.52     10157607.96
#Sta/Elev= 30
  3118.9  238.83  3225.4  236.37  3295.2   234.1  3431.8  224.53  3519.1  214.66
  3533.5  217.48  3583.2  217.21  3617.9  214.07  3620.6  213.57  3641.2  217.57
  3692.1  216.67  3712.5  220.07  3756.1  217.26  4242.6  215.82  4465.6  215.84
  4587.7  218.48  4730.2   217.8  4968.4  220.03  4978.8  217.73  4987.9  215.89
  5010.1  217.77  5026.3  219.98  5208.4  218.62  5381.3  219.16  5500.6  222.04
  5554.9  224.97  5621.2  230.59  5692.7  234.28  5876.2  250.48  5966.3  255.64
#Mann= 9 ,-1 , 0
  3118.9     .16       0  3225.4     .05       0  3533.5     .16       0
  3583.2     .05       0  3617.9     .07       0  4978.8     .05       0
  5010.1     .16       0  5208.4     .12       0  5381.3     .16       0
Bank Sta=4968.4,5026.3
XS Rating Curve= 0 ,0
Exp/Cntr=0.3,0.1

Type RM Length L Ch R = 1 ,26119   ,1523,1523,1523
BEGIN DESCRIPTION:
HOLLAND CREEK 17.0
END DESCRIPTION:
XS GIS Cut Line= 3
      3652446.75     10154671.79      3651793.97     10156352.35
      3651043.98     10157831.49
#Sta/Elev= 30
  3041.6  242.25  3112.8  240.42  3202.7  236.27  3216.7  235.47  3320.5  229.13
  3424.8  220.62  3530.4  215.77  3578.5  216.72    3618  216.06  3639.2  213.46
    3642  212.96  3645.2  213.46  3653.3  216.63  3672.4  214.82  3677.8  217.42
  3765.4  217.45  4285.1  214.82  4589.4  214.71  4921.3  219.01  4955.8  217.79
  4993.7  215.73  5023.1  217.93  5032.6  219.52  5247.3   215.3  5283.2   216.5
  5420.4   216.6  5636.6  222.19  5990.2  227.68  6394.1   242.2  6502.9   246.5
#Mann= 17 ,-1 , 0
  3041.6     .05       0  3112.8     .16       0  3202.7     .12       0
  3216.7     .16       0  3320.5     .12       0  3530.4     .05       0
  3578.5     .16       0  3639.2     .07       0  3645.2     .16       0
  3765.4     .05       0  4285.1     .16       0  4955.8     .05       0
  5023.1     .16       0  5283.2     .12       0  5420.4     .16       0
  5636.6     .05       0  6394.1     .16       0
#XS Ineff= 2 , 0
                         5036.36          219.56
Permanent Ineff=
       F       F
Bank Sta=4955.8,5023.1
XS Rating Curve= 0 ,0
Exp/Cntr=0.3,0.1

Type RM Length L Ch R = 1 ,24596   ,1019,1019,1019
BEGIN DESCRIPTION:
HOLLAND CREEK 16.0
END DESCRIPTION:
XS GIS Cut Line= 3
      3651441.97     10153271.63      3650239.01     10156544.03
      3649510.81     10159227.69
#Sta/Elev= 30
  1517.3  305.74  1562.8  304.04    1588  295.16  1593.3     297  1613.1  289.21
  1674.1  279.76  2029.1  245.58  2348.3  221.79  2465.5  216.05  2681.2  211.93
  2809.2  208.84  2859.5  211.33    2890  209.26  3614.5  210.08  3634.5  205.67
  3637.3  205.17  3640.5  205.67    3660     210  4772.7  214.22  4982.8  214.67
  5008.8  214.43  5786.1  211.71  6310.7  212.85  6793.9  220.86  6894.7     223
  7019.4   226.1    7122   229.7  7154.4  229.59  7700.9  253.36  7784.5  256.68
#Mann= 15 ,-1 , 0
  1517.3     .05       0  2681.2     .12       0  3634.5     .07       0
  3640.5     .12       0    3660     .16       0  4772.7      .1       0
  4982.8     .05       0  5008.8      .1       0  5786.1     .05       0
  6793.9     .16       0  6894.7      .1       0  7019.4     .05       0
    7122      .1       0  7154.4     .05       0  7700.9     .08       0
#Block Obstruct= 2 , 0
         4966.93  213.22
Bank Sta=4982.8,5008.8
XS Rating Curve= 0 ,0
Exp/Cntr=0.3,0.1