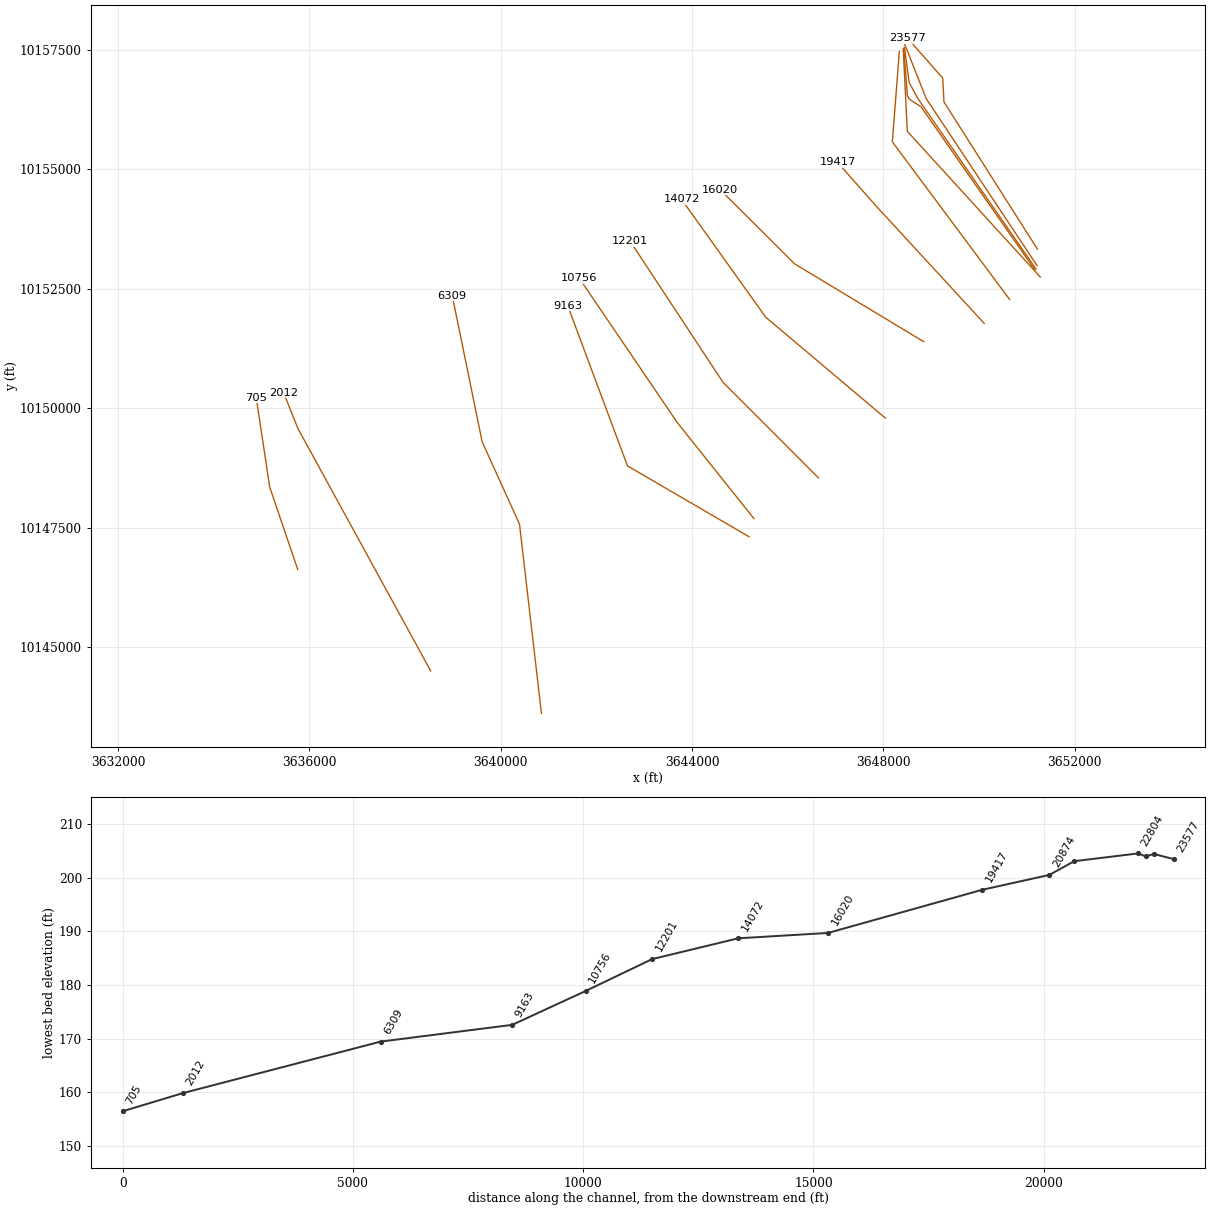
HEC-RAS study HOLLAND CREEK.prj: HOLLAND CREEK Base Level Engineering

--- HOLLAND CREEK.g01 (geometry) --- (continued)

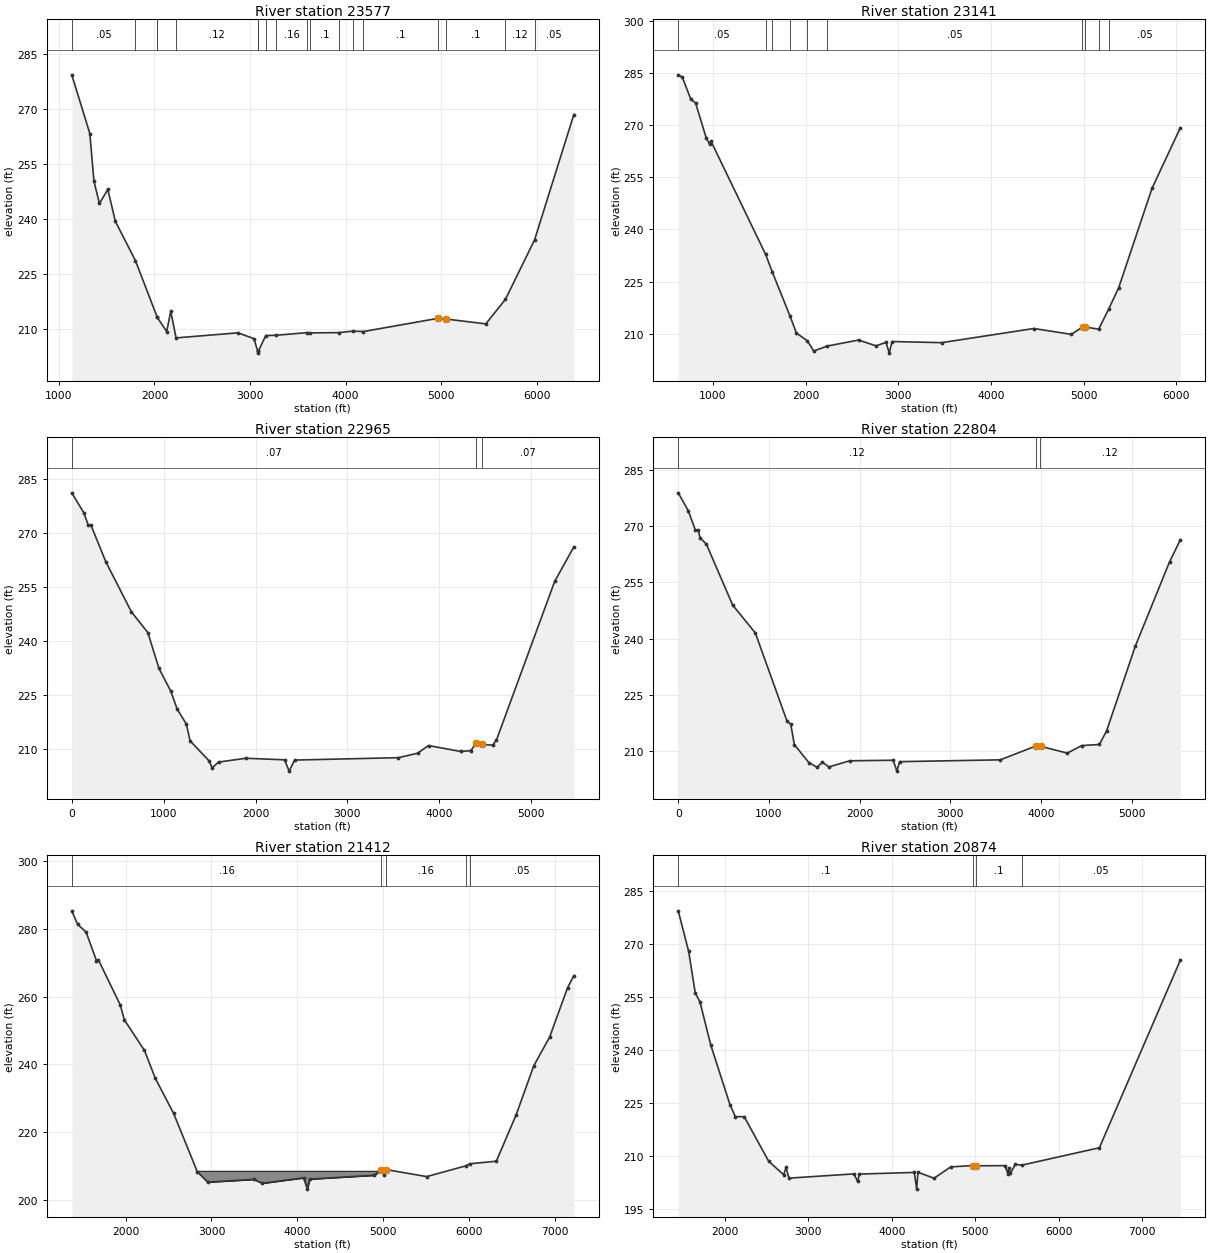
Type RM Length L Ch R = 1 ,23577   ,437,437,437
BEGIN DESCRIPTION:
Mapping XS a1d5a9ba
END DESCRIPTION:
XS GIS Cut Line= 4
      3651219.18     10153327.81      3649266.05     10156405.94
      3649240.01     10156905.94      3648507.56     10157737.09
#Sta/Elev= 30
  1134.5  279.42  1323.8  263.38  1366.2  250.42  1423.8   244.3  1511.9  248.12
  1590.7  239.42  1800.6  228.71  2028.4  213.27  2029.8  213.19  2127.8  209.35
  2170.1  214.86  2226.1  207.61  2874.1  208.99    3041   207.4  3080.4  203.95
  3083.1  203.45  3086.4  203.95  3164.6  208.26  3269.1  208.32    3600  209.05
  3631.7  208.98  3928.1  209.05  4073.4  209.45    4187  209.35  4965.9  212.94
  5046.1  212.77  5467.4  211.44  5673.2  218.16  5977.8  234.38  6388.5  268.59
#Mann= 18 ,-1 , 0
  1134.5     .05       0  1800.6     .16       0  2028.4     .05       0
  2029.8      .1       0  2226.1     .12       0  3080.4     .03       0
  3086.4     .12       0  3164.6      .1       0  3269.1     .16       0
    3600     .05       0  3631.7      .1       0  3928.1     .05       0
  4073.4      .1       0    4187      .1       0  4965.9     .05       0
  5046.1      .1       0  5673.2     .12       0  5977.8     .05       0
#Block Obstruct= 2 , 0
          4963.6  211.38
Bank Sta=4965.9,5046.1
XS Rating Curve= 0 ,0
Exp/Cntr=0.3,0.1

Type RM Length L Ch R = 1 ,23141   ,175,175,175
BEGIN DESCRIPTION:
Mapping XS 13bf9b7f
END DESCRIPTION:
XS GIS Cut Line= 3
      3651212.23     10152982.67      3648896.26     10156473.65
       3648443.7     10157618.06
#Sta/Elev= 30
   624.8  284.46   667.9  283.84   761.1   277.4   812.3  276.37   926.5  266.34
   962.6  264.52   977.7   265.4  1568.8  232.79  1640.5  227.74  1830.1  215.17
    1901  210.18  2019.8  207.93  2087.6  205.02  2232.6  206.45  2571.6  208.18
  2759.7  206.52  2867.7  207.51  2903.4  204.42  2932.5  207.76  3467.7  207.43
  4463.3   211.5  4868.7  209.82  4984.1  211.83  4994.8  211.83  5016.3  211.94
  5163.4  211.31  5271.6   217.1  5379.7  223.24  5739.3  251.81  6044.8  269.23
#Mann= 10 ,-1 , 0
   624.8     .05       0  1568.8     .16       0  1640.5      .1       0
  1830.1     .05       0  2019.8     .12       0  2232.6     .05       0
  4984.1    .035       0  5016.3     .05       0  5163.4     .12       0
  5271.6     .05       0
#Block Obstruct= 2 , 0
         4986.77   210.9
Bank Sta=4994.8,5016.3
XS Rating Curve= 0 ,0
Exp/Cntr=0.3,0.1

Type RM Length L Ch R = 1 ,22965   ,162,162,162
XS GIS Cut Line= 4
     3651191.286    10152909.519     3648719.064    10156478.963
     3648538.508    10156812.297     3648440.765    10157545.456
#Sta/Elev= 30
       0281.1543 129.767275.6806179.6774272.2304209.6236272.1452369.3368262.0966
648.8348248.1364828.5122242.3718948.2971232.48431078.064226.11861147.939221.1074
1247.759216.99151287.688212.36821497.311206.73151527.257204.83871597.132  206.47
1896.594 207.5242315.841207.09412365.752203.95662425.644207.02383553.619207.6847
3763.242208.91913883.027211.0547  4232.4 209.4084342.203209.63184401.994211.6566
4461.786211.36274581.369211.1596 4621.23212.5091 5256.27256.60175464.476266.1736
#Mann= 3 , 0 , 0
       0     .07       04401.994     .05       04461.786     .07       0
#Block Obstruct= 2 , 0
         4402.42  211.06
Bank Sta=4401.994,4461.786
XS Rating Curve= 0 ,0
Exp/Cntr=0.3,0.1

Type RM Length L Ch R = 1 ,22804   ,1391,1391,1391
XS GIS Cut Line= 5
     3651168.198    10152892.168      3648787.99    10156303.627
     3648548.407    10156459.877     3648501.532    10156532.793
     3648425.898     10157529.05
#Sta/Elev= 30
       0278.9933109.9931274.2339189.9881268.9394219.9863269.0562 239.985266.9855
309.9807265.2697599.9625248.9554 849.947 241.4941199.925217.85841239.923217.1032
 1279.92211.6059 1439.91206.81581529.905205.55471589.901206.91651659.896 205.641
1889.882207.28952369.852207.4382 2409.85204.52312439.848207.05473549.778207.5464
3939.754211.22413989.751 211.155 3999.75 211.1344288.614209.33944447.228211.3628
4642.011211.65964721.302215.28595038.467237.9848  5415.1260.50665534.037266.4312
#Mann= 3 ,-1 , 0
       0     .12       03939.754     .07       03989.751     .12       0
Bank Sta=3939.754,3999.75
XS Rating Curve= 0 ,0
Exp/Cntr=0.3,0.1

Type RM Length L Ch R = 1 ,21412   ,539,539,539
BEGIN DESCRIPTION:
Mapping XS 83e6bd51
END DESCRIPTION:
XS GIS Cut Line= 3
      3651279.91     10152743.13      3648500.43     10155791.36
      3648413.62     10157513.58
#Sta/Elev= 30
  1372.1  285.39  1440.1   281.4  1539.4  279.08  1659.7  270.67  1681.3  270.93
    1936  257.61  1985.3  253.12  2219.1  244.08  2346.1  235.82  2558.9  225.47
  2834.6  208.23  2954.8  205.14  3493.3  205.94    3592  204.79  4073.7  206.41
    4116  203.07  4144.4  206.03  4894.6  207.17  4979.7  208.69  5014.9  207.33
    5029  208.87  5507.6  206.78  5965.2  209.97  6009.3  210.57  6318.6  211.33
  6548.9     225  6754.7  239.55  6939.4  248.03  7148.6  262.65  7221.7  266.21
#Mann= 5 ,-1 , 0
  1372.1     .16       0  4979.7     .07       0    5029     .16       0
  5965.2     .07       0  6009.3     .05       0
#Block Obstruct= 2 , 0
       0 4971.91   208.5               0
Bank Sta=4979.7,5029
XS Rating Curve= 0 ,0
Exp/Cntr=0.3,0.1

Type RM Length L Ch R = 1 ,20874   ,1456,1456,1456
BEGIN DESCRIPTION:
HOLLAND CREEK 15.0
END DESCRIPTION:
XS GIS Cut Line= 3
      3650639.02     10152273.35      3648186.77     10155571.97
      3648333.69      10157467.5
#Sta/Elev= 30
  1443.4  279.25    1568  267.79  1647.3  255.99  1703.6  253.49    1833  241.26
  2062.4  224.44  2126.6  221.03  2233.5     221  2525.5  208.43  2704.9  204.58
  2734.1  206.63  2769.5  203.62  3547.6  204.82  3591.4  202.68  3612.2  204.77
  4269.8  205.24  4298.3  200.51  4313.1  205.28  4506.6  203.59    4706   206.8
  4978.5  207.19    5014  207.11  5356.1  207.16  5391.5  204.77  5399.9  206.54
  5420.7  204.94  5478.5  207.51  5558.2   207.3  6486.1  212.22  7454.9  265.27
#Mann= 4 ,-1 , 0
  1443.4      .1       0  4978.5     .05       0    5014      .1       0
  5558.2     .05       0
#Block Obstruct= 2 , 0
         4963.15  205.79
Bank Sta=4978.5,5014
XS Rating Curve= 0 ,0
Exp/Cntr=0.3,0.1

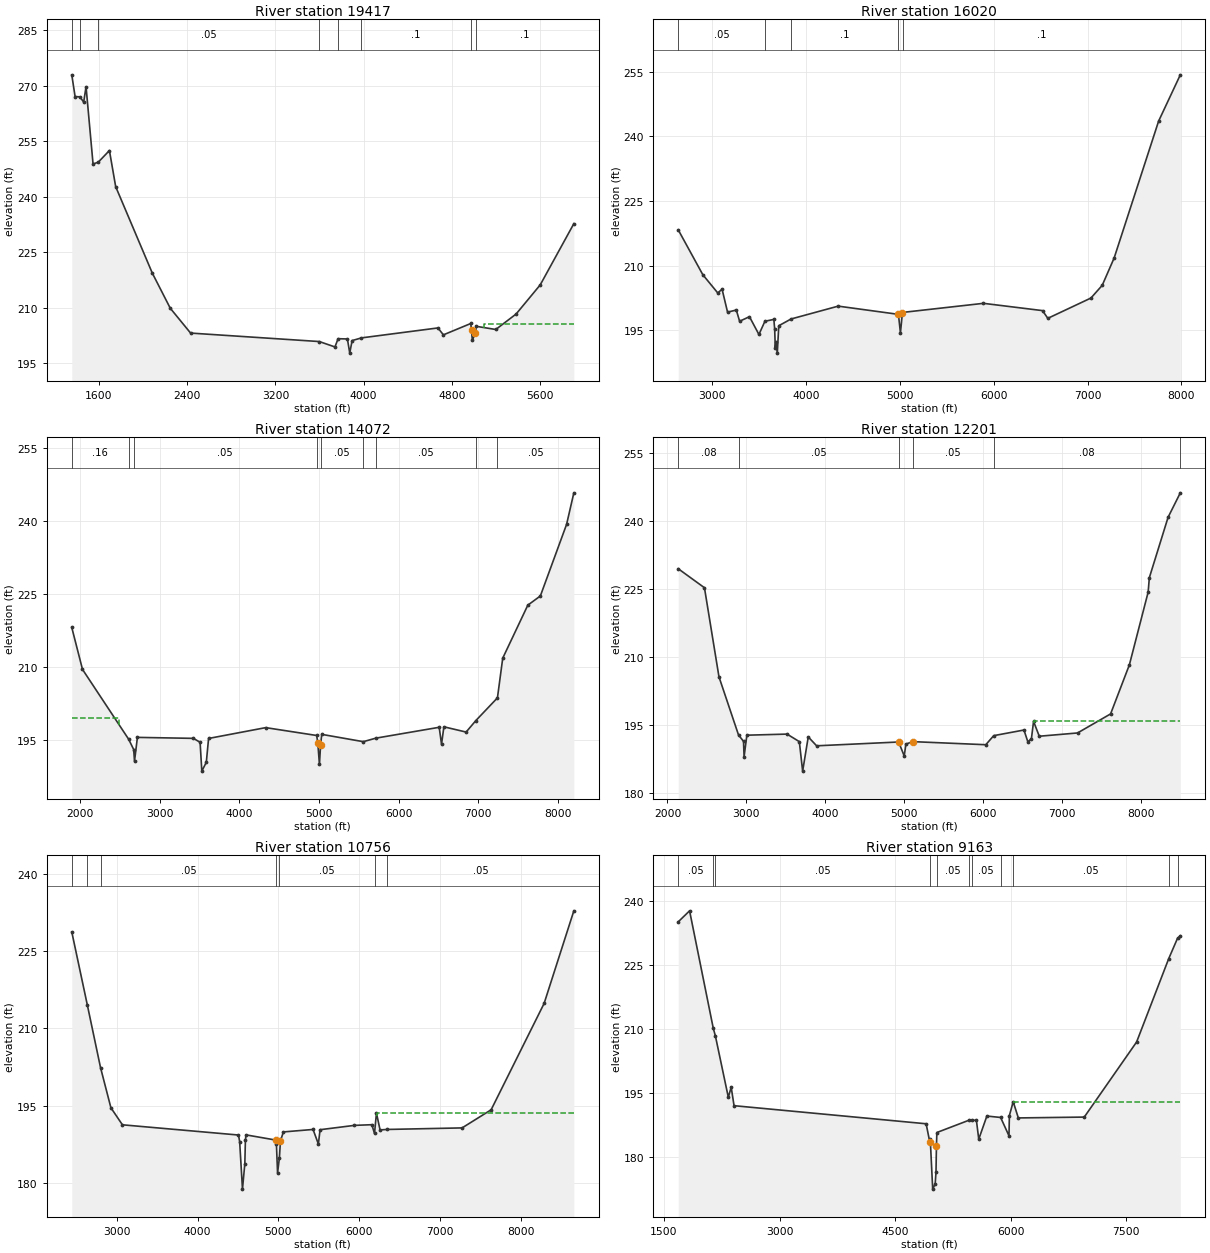
Type RM Length L Ch R = 1 ,19417   ,3351,3351,3351
BEGIN DESCRIPTION:
HOLLAND CREEK 12.0
END DESCRIPTION:
XS GIS Cut Line= 3
      3650107.36      10151774.2      3647850.39     10154226.48
      3647042.11     10155141.64
#Sta/Elev= 30
  1353.2  272.97  1383.4   267.1  1427.1  267.01  1461.1   265.6  1482.7  269.76
  1546.2  248.88  1593.1  249.34  1694.7  252.51  1751.5  242.74  2083.8  219.36
  2246.7  209.87  2430.9  203.16  3598.5  200.87  3740.3  199.41  3768.7  201.64
  3853.2  201.57  3874.5  197.74  3895.7  201.13  3980.8  201.86  4674.4  204.55
  4723.7  202.68  4972.2  205.75  4978.9  203.89  4986.4  201.18    5014  203.26
  5021.5  204.99  5198.9  204.13  5382.9   208.3  5602.1  216.19    5907  232.74
#Mann= 8 ,-1 , 0
  1353.2     .05       0  1427.1      .1       0  1593.1     .05       0
  3598.5     .12       0  3768.7     .07       0  3980.8      .1       0
  4972.2     .05       0  5021.5      .1       0
#XS Ineff= 2 , 0
                         5092.55          205.49
Permanent Ineff=
       F       F
#Block Obstruct= 2 , 0
          4965.7  201.23
Bank Sta=4978.9,5014
XS Rating Curve= 0 ,0
Exp/Cntr=0.3,0.1

Type RM Length L Ch R = 1 ,16020   ,1948,1948,1948
BEGIN DESCRIPTION:
HOLLAND CREEK 11.0
END DESCRIPTION:
XS GIS Cut Line= 3
      3648842.12     10151391.64      3646143.13     10153019.91
      3644585.71     10154572.33
#Sta/Elev= 30
  2636.8  218.31  2898.9  207.89  3058.1  203.66    3104  204.53  3162.4  199.21
  3255.8  199.69    3291  197.09  3395.8  198.15  3496.7  194.02  3560.8  197.09
  3655.9  197.52  3664.6  195.29  3671.4  190.87  3677.3  192.19  3692.6  189.69
  3708.3  196.05  3839.7  197.62  4341.9   200.6  4983.7  198.69    5005  194.38
  5026.4  199.11  5032.2  199.15  5889.8  201.25  6519.2  199.56  6575.8  197.77
  7035.4  202.48  7155.6  205.43  7282.9  211.79  7756.6  243.55  7987.9   254.3
#Mann= 5 ,-1 , 0
  2636.8     .05       0  3560.8     .07       0  3839.7      .1       0
  4983.7     .05       0  5032.2      .1       0
#XS Ineff= 2 , 0
                         5937.25          200.89
Permanent Ineff=
       F       F
Bank Sta=4983.7,5026.4
XS Rating Curve= 0 ,0
Exp/Cntr=0.3,0.1

Type RM Length L Ch R = 1 ,14072   ,1871,1871,1871
BEGIN DESCRIPTION:
HOLLAND CREEK 10.0
END DESCRIPTION:
XS GIS Cut Line= 3
      3648042.12     10149791.63       3645539.2     10151904.43
      3643781.71     10154367.07
#Sta/Elev= 30
  1898.2  218.15  2032.8  209.55  2611.4  195.25  2675.2  193.12  2685.5  190.72
  2721.9  195.61    3424  195.41  3508.6  194.61  3530.4  188.69  3586.6   190.5
  3615.2  195.39  4332.3  197.61  4971.3     196  4985.6  194.54  5006.4  190.05
  5020.7  194.05    5035  196.23  5556.6  194.73  5713.9  195.45  6509.3  197.68
  6538.6   194.2  6568.1  197.78  6847.1   196.7    6970  199.07  7240.2  203.71
  7306.8  211.86  7621.4  222.72  7778.8  224.61  8108.2   239.3  8199.1  245.76
#Mann= 9 ,-1 , 0
  1898.2     .16       0  2611.4     .12       0  2675.2     .05       0
  4971.3    .035       0  5020.7     .05       0  5556.6     .12       0
  5713.9     .05       0    6970      .1       0  7240.2     .05       0
#XS Ineff= 2 , 0
         2491.32  199.67
Permanent Ineff=
       F       F
Bank Sta=4985.6,5020.7
XS Rating Curve= 0 ,0
Exp/Cntr=0.3,0.1

Type RM Length L Ch R = 1 ,12201   ,1445,1445,1445
BEGIN DESCRIPTION:
HOLLAND CREEK 9.0
END DESCRIPTION:
XS GIS Cut Line= 3
       3646642.1     10148541.65      3644644.56     10150544.61
      3642703.06     10153496.96
#Sta/Elev= 30
  2136.7  229.41    2469  225.22  2652.9  205.59  2900.4  192.79    2964  191.37
  2971.1  187.97  3006.4  192.73  3515.5  192.97  3671.1  191.31  3713.3  184.81
  3784.2  192.35  3890.3  190.39  4929.8  191.23  5000.5  188.15  5021.8  190.77
    5109  191.31  6033.9  190.63  6134.8  192.63  6517.8  193.87  6567.1  191.26
  6612.3  191.96  6639.4  195.77  6711.7   192.5  7196.7  193.22  7615.5  197.42
  7853.5  208.23  8091.5  224.26  8106.5  227.44  8344.5  240.77    8499  246.14
#Mann= 6 ,-1 , 0
  2136.7     .08       0  2900.4     .05       0  4929.8    .035       0
    5109     .05       0  6134.8     .08       0    8499     .05       0
#XS Ineff= 2 , 0
                         6645.45          195.86
Permanent Ineff=
       F       F
Bank Sta=4929.8,5109
XS Rating Curve= 0 ,0
Exp/Cntr=0.3,0.1

Type RM Length L Ch R = 1 ,10756   ,1593,1593,1593
BEGIN DESCRIPTION:
HOLLAND CREEK 6.0
END DESCRIPTION:
XS GIS Cut Line= 3
      3645292.12     10147691.63      3643694.56     10149694.61
      3641643.82     10152716.03
#Sta/Elev= 30
  2442.5  228.69  2636.3  214.44  2798.4   202.4  2926.9  194.62  3069.3  191.32
  4505.8  189.34  4520.2  188.06  4555.2  178.86  4584.3   183.8  4591.4  188.29
  4598.7  189.37  4968.6  188.36  4975.2  187.62  4989.4  181.99  5012.4  184.96
  5025.1  188.18  5061.4  189.94  5428.7  190.42  5494.5   187.6  5515.5  190.37
  5940.7  191.21  6156.3  191.34  6189.2  189.64  6213.2   193.6  6257.9  190.33
  6346.6  190.42  7273.1  190.72  7632.5  194.23  8288.2  214.83  8656.2  232.77
#Mann= 7 ,-1 , 0
  2442.5     .05       0  2636.3     .16       0  2798.4     .05       0
  4975.2    .035       0  5012.4     .05       0  6189.2     .08       0
  6346.6     .05       0
#XS Ineff= 2 , 0
                         6219.89          193.57
Permanent Ineff=
       F       F
Bank Sta=4968.6,5025.1
XS Rating Curve= 0 ,0
Exp/Cntr=0.3,0.1

Type RM Length L Ch R = 1 ,9163    ,2854,2854,2854
BEGIN DESCRIPTION:
HOLLAND CREEK 5.0
END DESCRIPTION:
XS GIS Cut Line= 3
      3645191.83     10147310.96      3642650.74     10148792.45
      3641400.73     10152143.16
#Sta/Elev= 30
  1685.3  235.21  1832.6  237.79  2140.2  210.25    2167  208.51  2335.5  194.08
  2372.7  196.44  2409.9  192.11  4903.4  187.87  4951.6  183.53  4956.9  184.26
  4988.5  172.55  5020.8  173.77  5031.4  176.52  5037.2  182.61  5042.6  185.82
    5465  188.74  5496.3  188.74  5556.2  188.65  5586.5  184.26  5691.8  189.68
  5870.4  189.35  5978.9  185.05  5984.2   189.8  6033.7  193.04  6100.2  189.24
  6956.2  189.44  7635.7  207.04  8052.1  226.56  8166.5  231.34    8203  231.94
#Mann= 11 ,-1 , 0
  1685.3     .05       0  2140.2     .16       0    2167     .05       0
  4956.9    .035       0  5042.6     .05       0    5465     .16       0
  5496.3     .05       0  5870.4     .08       0  6033.7     .05       0
  8052.1     .08       0  8166.5     .05       0
#XS Ineff= 2 , 0
                         6031.82          193.04
Permanent Ineff=
       F       F
Bank Sta=4951.6,5037.2
XS Rating Curve= 0 ,0
Exp/Cntr=0.3,0.1

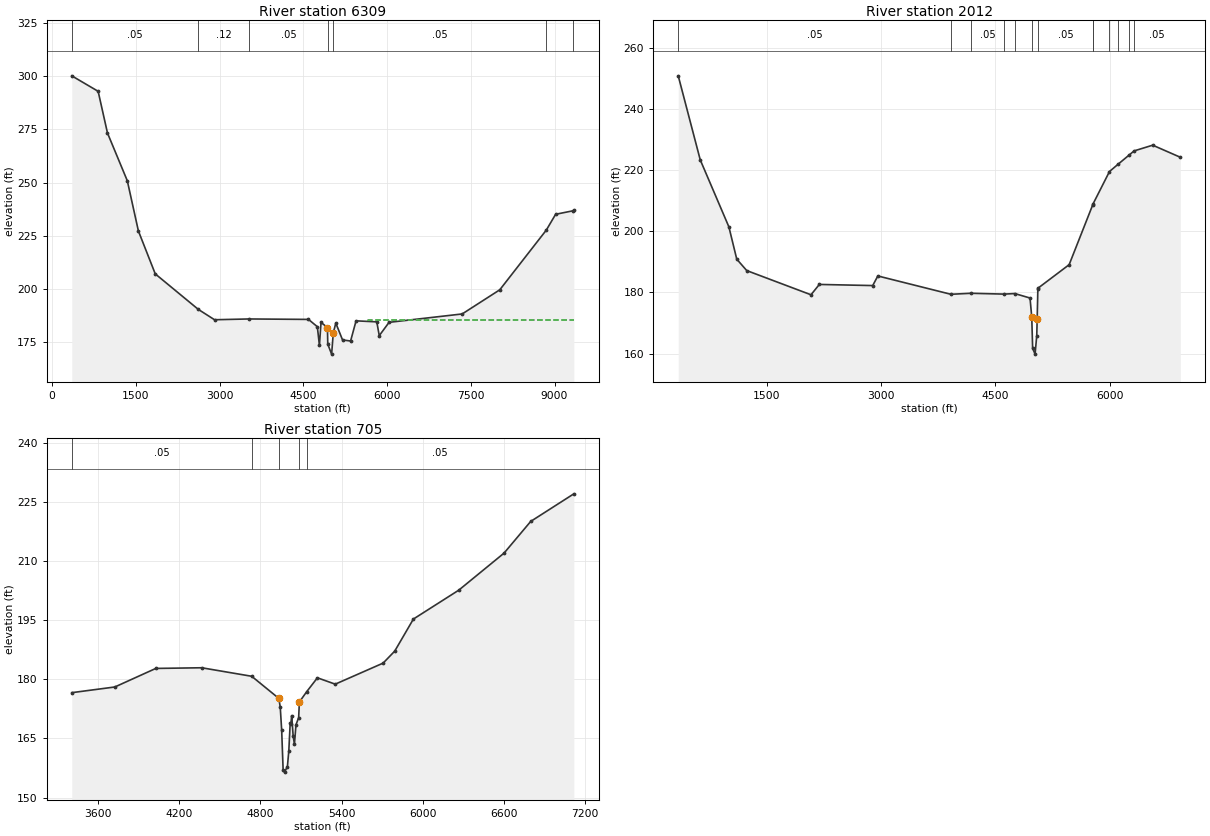
Type RM Length L Ch R = 1 ,6309    ,4297,4297,4297
BEGIN DESCRIPTION:
HOLLAND CREEK 4.0
END DESCRIPTION:
XS GIS Cut Line= 4
      3640851.26     10143615.95      3640392.92     10147574.33
      3639612.55     10149295.92      3638987.56     10152351.43
#Sta/Elev= 30
     352  300.09   824.3  292.82   991.8  273.22  1346.9  250.82  1545.6  227.24
  1847.6   207.1  2619.1  190.43  2909.5  185.57  3524.7  185.94  4592.5  185.73
  4751.1   182.3  4788.2  173.52    4817  184.32  4932.2  181.91  4937.7  174.11
  5006.7  169.43  5036.6  179.37  5081.8     184  5202.7  176.08  5346.7  175.59
  5444.6  185.06  5816.1  184.58    5860   178.1  6035.7  184.35  7345.4  188.29
  8019.1  199.63  8852.7  227.67  9019.4  235.08  9327.6  236.71  9345.8  236.91
#Mann= 7 ,-1 , 0
     352     .05       0  2619.1     .12       0  3524.7     .05       0
  4937.7    .035       0  5036.6     .05       0  8852.7      .1       0
  9327.6     .05       0
#XS Ineff= 2 , 0
                         5653.41          185.43
Permanent Ineff=
       F       F
Bank Sta=4932.2,5036.6
XS Rating Curve= 0 ,0
Exp/Cntr=0.3,0.1

Type RM Length L Ch R = 1 ,2012    ,1307,1307,1307
BEGIN DESCRIPTION:
HOLLAND CREEK 3.0
END DESCRIPTION:
XS GIS Cut Line= 3
      3638536.18     10144504.22      3635762.24      10149572.2
      3635462.26     10150322.16
#Sta/Elev= 30
   340.4  250.79   629.1  223.31  1004.7  201.42    1108  190.86  1238.9  187.13
  2081.7  179.22    2191   182.6  2891.1  182.23  2958.3  185.37  3916.5  179.38
  4178.3  179.71  4615.5  179.44  4754.4  179.62  4954.4  178.16  4977.2  171.92
  4988.7  161.73  5020.7  159.82  5042.7  165.87  5048.4  171.26    5057  180.99
  5064.5  181.48  5467.6  189.06    5775   208.5  5781.6  208.94  5996.3   219.5
  6110.7  221.92  6250.7  224.82  6319.6  226.25  6563.4  228.12  6925.6  224.17
#Mann= 13 ,-1 , 0
   340.4     .05       0  3916.5      .1       0  4178.3     .05       0
  4615.5     .12       0  4754.4     .05       0  4977.2    .035       0
  5064.5     .05       0    5775     .08       0  5781.6     .05       0
  5996.3     .08       0  6110.7     .05       0  6250.7     .08       0
  6319.6     .05       0
#XS Ineff= 2 , 0
         2961.57  185.34
Permanent Ineff=
       F       F
Bank Sta=4977.2,5048.4
XS Rating Curve= 0 ,0
Exp/Cntr=0.3,0.1

Type RM Length L Ch R = 1 ,705     ,0,0,0
BEGIN DESCRIPTION:
HOLLAND CREEK 1.0
END DESCRIPTION:
XS GIS Cut Line= 3
      3635758.39     10146622.28      3635170.46     10148351.39
      3634890.33     10150216.03
#Sta/Elev= 30
  3405.3   176.6  3723.4  178.04  4026.5  182.75  4365.8  182.92  4735.5  180.76
  4936.4  175.14  4946.7   172.9  4957.2  167.05  4967.8  157.08  4978.2  156.44
  4999.5  157.84  5010.1  161.92    5020  168.82  5025.3  168.76  5031.2  170.78
  5041.8  165.73  5051.4  163.51  5062.9  168.45  5082.7  170.27    5088  174.23
  5141.3  176.81  5221.3  180.37  5353.2  178.76  5707.2   184.1  5792.9  187.14
    5931  195.28  6266.1   202.6  6601.3  212.01  6798.3  220.05  7117.2  227.05
#Mann= 5 ,-1 , 0
  3405.3     .05       0  4735.5     .12       0  4936.4     .07       0
    5088     .12       0  5141.3     .05       0
Bank Sta=4936.4,5088
XS Rating Curve= 0 ,0
Exp/Cntr=0.3,0.1
Stream Node=HOLLAND CREEK   ,Reach-1         , 0 , 0 ,Upstream end
Stream Node=HOLLAND CREEK   ,Reach-1         , 0 , 1 ,Downstream end

Chan Stop Cuts=-1
Use User Specified Reach Order=0
Composite Channel Slope=5