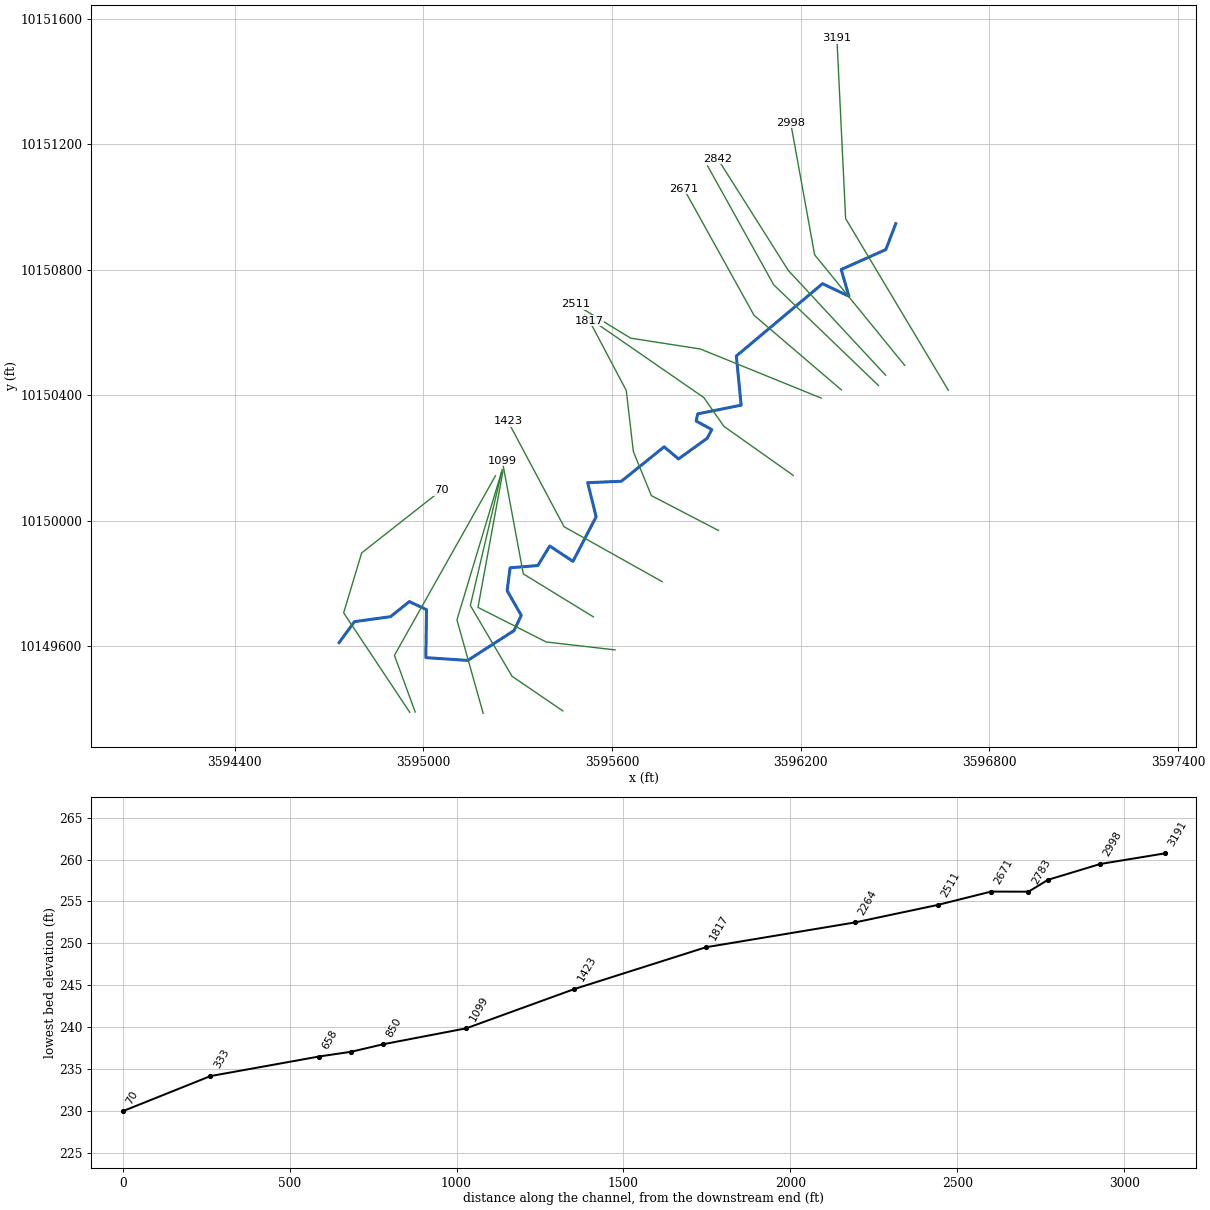
--- HUTTON MILL BRANCH TRIB 1.prj (project) ---

Proj Title=HUTTON MILL BRANCH TRIB 1 Base Level Engineering
Current Plan=p01
Default Exp/Contr=0.3,0.1
English Units
Geom File=g01
Flow File=f01
Plan File=p01
Y Axis Title=Elevation
X Axis Title(PF)=Main Channel Distance
X Axis Title(XS)=Station
BEGIN DESCRIPTION:
HUTTON MILL BRANCH TRIB 1
END DESCRIPTION:
DSS Export Rating Curves= 0
DSS Export Rating Curve Sorted= 0
DSS Export Volume Flow Curves= 0
DXF OffsetX= 0
DXF OffsetY= 0
DXF ScaleX= 1
DXF ScaleY= 10

--- HUTTON MILL BRANCH TRIB 1.p01 (plan) ---

Plan Title=Multiple Run
Short Identifier=Multiple
Geom File=g01
Flow File=f01
Subcritical Flow
K Sum by GR= 0
Std Step Tol= 0.01
Critical Tol= 0.01
Num of Std Step Trials= 20
Max Error Tol= 0.3
Flow Tol Ratio= 0.001
Split Flow NTrial= 30
Split Flow Tol= 0.02
Split Flow Ratio= 0.02
Log Output Level= 0
Friction Slope Method= 1
Unsteady Friction Slope Method= 2
Unsteady Bridges Friction Slope Method= 1
Parabolic Critical Depth
Global Vel Dist=  1 , 1 , 1
Global Log Level= 0
CheckData=True
Encroach Param= -1, 0, 0, 0
BEGIN DESCRIPTION:
Multiple Run
END DESCRIPTION:

--- HUTTON MILL BRANCH TRIB 1.f01 (steady flow) ---

Flow Title=Multiple
Number of Profiles=7
Profile Names=10-year,25-year,50-year,1pct_min,100-year,1pct_plu,500-year
River Rch & RM= HUTTON MILL BRAN,Reach-1,3191
     203     256     297     254     343     464     456
Boundary for River Rch & Prof#=HUTTON MILL BRAN,Reach-1,1
Up Type=0
Dn Type=3
Dn Slope=0.005
Boundary for River Rch & Prof#=HUTTON MILL BRAN,Reach-1,2
Up Type=0
Dn Type=3
Dn Slope=0.005
Boundary for River Rch & Prof#=HUTTON MILL BRAN,Reach-1,3
Up Type=0
Dn Type=3
Dn Slope=0.005
Boundary for River Rch & Prof#=HUTTON MILL BRAN,Reach-1,4
Up Type=0
Dn Type=3
Dn Slope=0.005
Boundary for River Rch & Prof#=HUTTON MILL BRAN,Reach-1,5
Up Type=0
Dn Type=3
Dn Slope=0.005
Boundary for River Rch & Prof#=HUTTON MILL BRAN,Reach-1,6
Up Type=0
Dn Type=3
Dn Slope=0.005
Boundary for River Rch & Prof#=HUTTON MILL BRAN,Reach-1,7
Up Type=0
Dn Type=3
Dn Slope=0.005

--- HUTTON MILL BRANCH TRIB 1.g01 (geometry) ---

Geom Title=Existing Conditions
Program Version=4.10

River Reach=HUTTON MILL BRAN,Reach-1
Reach XY= 30
      3596502.11     10150946.64       3596470.6     10150864.02
       3596328.6     10150800.47      3596353.13     10150715.44
      3596269.19     10150755.23       3595995.3     10150524.94
      3596010.48     10150368.27      3595872.35     10150340.45
      3595867.59     10150317.52      3595917.25     10150290.52
      3595902.61      10150262.8      3595811.25     10150196.81
      3595765.65     10150235.54      3595629.79     10150125.78
      3595522.38     10150121.17       3595549.4     10150012.59
      3595475.71     10149870.59      3595401.93     10149919.61
      3595364.18     10149857.34      3595275.78       10149850.
      3595266.34     10149777.31      3595311.38     10149698.46
      3595288.33     10149649.92      3595141.13     10149554.96
      3595007.89     10149563.78      3595010.05     10149716.59
      3594955.46     10149742.41      3594895.56     10149694.35
      3594780.91     10149678.49      3594732.11     10149611.64

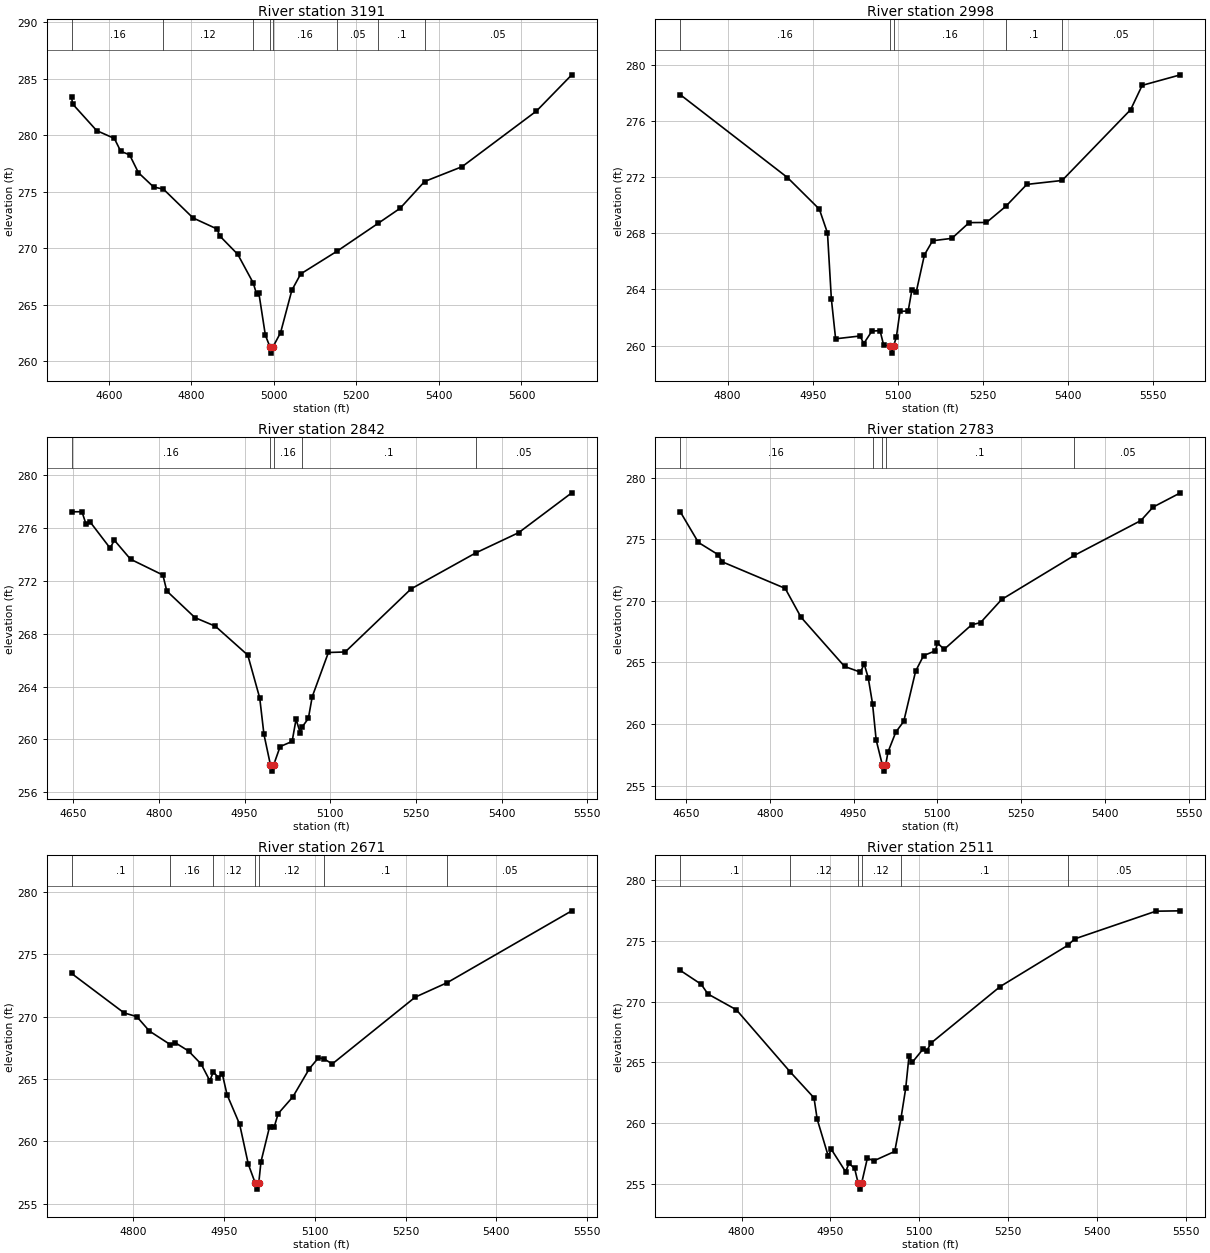
Type RM Length L Ch R = 1 ,3191    ,193,193,193
BEGIN DESCRIPTION:
HUTTON MILL BRANCH TRIB 1 31.0
END DESCRIPTION:
XS GIS Cut Line= 3
       3596669.1     10150415.88      3596342.72     10150962.74
      3596314.96     10151537.02
#Sta/Elev= 30
    4510  283.39  4512.4  282.76  4570.8   280.4  4613.6  279.71  4629.2  278.57
  4650.6  278.26    4672  276.68  4708.9  275.41  4732.5  275.23  4804.3  272.68
  4862.7   271.7  4868.5  271.11  4912.7  269.46  4950.3  266.92  4958.1  265.96
  4963.9  266.01  4979.5  262.32  4991.2  261.23  4993.9  260.73  4997.2  261.23
  5016.4  262.54  5043.7  266.29  5065.1  267.73    5154  269.76  5252.2  272.19
  5305.9  273.53  5365.3   275.9  5456.1  277.21  5636.3  282.13  5721.8  285.33
#Mann= 8 ,-1 , 0
    4510     .16       0  4732.5     .12       0  4950.3     .16       0
  4991.2     .07       0  4997.2     .16       0    5154     .05       0
  5252.2      .1       0  5365.3     .05       0
Bank Sta=4991.2,4997.2
XS Rating Curve= 0 ,0
Exp/Cntr=0.3,0.1

Type RM Length L Ch R = 1 ,2998    ,156,156,156
BEGIN DESCRIPTION:
Mapping XS 7441ce7e
END DESCRIPTION:
XS GIS Cut Line= 3
      3596530.59     10150494.95      3596244.11      10150847.4
      3596167.96     10151267.97
#Sta/Elev= 30
  4716.5  277.87  4905.5  271.97  4961.7  269.72  4976.1  268.02  4982.9  263.34
  4990.4  260.49  5033.5  260.69    5040  260.15  5054.4  261.04  5068.7  261.07
  5075.2  260.02  5086.5  259.97  5089.3  259.47  5092.5  259.97  5097.5  260.62
  5103.9  262.44  5118.3  262.47  5124.7  263.93  5132.6  263.84    5147  266.47
  5161.4  267.47  5195.3  267.64  5225.8  268.76  5256.3  268.77  5290.4  269.92
  5327.4  271.48  5389.6  271.76  5510.4   276.8  5530.7  278.53  5598.1  279.28
#Mann= 5 ,-1 , 0
  4716.5     .16       0  5086.5     .07       0  5092.5     .16       0
  5290.4      .1       0  5389.6     .05       0
Bank Sta=5086.5,5092.5
XS Rating Curve= 0 ,0
Exp/Cntr=0.3,0.1

Type RM Length L Ch R = 1 ,2842    ,59,59,59
BEGIN DESCRIPTION:
Mapping XS 90ea1f15
END DESCRIPTION:
XS GIS Cut Line= 3
      3596469.83      10150463.7      3596160.78     10150797.05
      3595936.08     10151153.11
#Sta/Elev= 30
  4647.1  277.24  4665.3  277.25  4672.1  276.35  4679.5  276.48  4714.6  274.49
    4722  275.09  4750.3  273.65    4807  272.45  4813.8  271.24  4863.2  269.22
  4898.9  268.57  4955.6  266.38  4976.5  263.13  4983.9  260.37  4995.1  258.09
  4997.8  257.59  5001.1  258.09  5012.2  259.45  5033.2  259.84  5040.1  261.52
  5047.4  260.49  5050.3  260.91  5061.6  261.58  5068.4  263.23  5096.7  266.58
  5126.1  266.62  5241.4   271.4  5354.8  274.13  5429.7  275.66  5522.7  278.68
#Mann= 5 ,-1 , 0
  4647.1     .16       0  4995.1     .07       0  5001.1     .16       0
  5050.3      .1       0  5354.8     .05       0
Bank Sta=4995.1,5001.1
XS Rating Curve= 0 ,0
Exp/Cntr=0.3,0.1

Type RM Length L Ch R = 1 ,2783    ,112,112,112
BEGIN DESCRIPTION:
Mapping XS 75903f1e
END DESCRIPTION:
XS GIS Cut Line= 3
      3596447.23     10150430.74       3596113.9     10150751.92
      3595903.85     10151130.35
#Sta/Elev= 30
  4639.5  277.24  4672.1  274.74  4707.4  273.75  4714.6  273.17  4827.5  271.01
  4855.8  268.67  4933.8  264.67  4962.1  264.21    4969  264.86  4976.2  263.75
  4983.9  261.65  4990.4   258.7  5001.5  256.67  5004.3  256.17  5007.5  256.67
  5011.5  257.71  5025.6  259.34  5039.8  260.21  5061.1  264.29  5075.3  265.55
  5096.4  265.94  5100.2  266.58  5112.1  266.06  5161.3  268.05  5177.3  268.23
  5215.1  270.11  5345.4  273.69  5464.5  276.52  5486.2  277.61  5535.2  278.77
#Mann= 5 ,-1 , 0
  4639.5     .16       0  4983.9      .1       0  5001.5     .07       0
  5007.5      .1       0  5345.4     .05       0
Bank Sta=5001.5,5007.5
XS Rating Curve= 0 ,0
Exp/Cntr=0.3,0.1

Type RM Length L Ch R = 1 ,2671    ,160,160,160
BEGIN DESCRIPTION:
Mapping XS 23c8a5ab
END DESCRIPTION:
XS GIS Cut Line= 3
       3596329.2     10150416.83       3596051.4     10150654.69
      3595828.17      10151057.9
#Sta/Elev= 30
    4698  273.48  4784.9  270.31  4805.7  270.02  4826.6  268.86  4861.5  267.76
  4869.4  267.92  4891.3  267.26  4912.2  266.21  4926.5  264.87  4932.2  265.58
  4940.7  265.13  4947.3  265.38    4955  263.75  4975.8  261.38  4990.1  258.18
  5001.4  256.68  5004.1  256.18  5007.4  256.68    5011  258.37  5025.2  261.18
  5032.9  261.17  5039.5  262.24  5063.7  263.58    5091  265.84    5106  266.71
  5115.2  266.63  5128.8  266.22    5266  271.58  5318.8  272.74  5524.6   278.5
#Mann= 7 ,-1 , 0
    4698      .1       0  4861.5     .16       0  4932.2     .12       0
  5001.4     .07       0  5007.4     .12       0  5115.2      .1       0
  5318.8     .05       0
Bank Sta=5001.4,5007.4
XS Rating Curve= 0 ,0
Exp/Cntr=0.3,0.1

Type RM Length L Ch R = 1 ,2511    ,247,247,247
BEGIN DESCRIPTION:
Mapping XS 334ef6ba
END DESCRIPTION:
XS GIS Cut Line= 4
      3596264.91     10150390.82      3595881.26     10150547.05
      3595659.04     10150581.78       3595483.7     10150689.41
#Sta/Elev= 30
  4696.4  272.56  4731.8  271.42  4743.2  270.62  4791.3  269.32  4881.8  264.24
  4922.4  262.09  4927.8  260.33  4946.4  257.32  4951.8  257.85  4975.9  256.01
  4981.3   256.7    4991   256.3  4996.9  255.09  4999.7  254.59  5002.9  255.09
  5012.6  257.14  5023.3  256.91  5058.8  257.69  5069.5  260.47  5077.3  262.87
  5082.9  265.53  5088.3     265  5106.9  266.11  5112.7  265.93  5119.9  266.58
  5236.9  271.23  5350.9  274.61  5362.6  275.14  5499.9  277.42  5541.3  277.45
#Mann= 6 ,-1 , 0
  4696.4      .1       0  4881.8     .12       0  4996.9     .07       0
  5002.9     .12       0  5069.5      .1       0  5350.9     .05       0
Bank Sta=4996.9,5002.9
XS Rating Curve= 0 ,0
Exp/Cntr=0.3,0.1

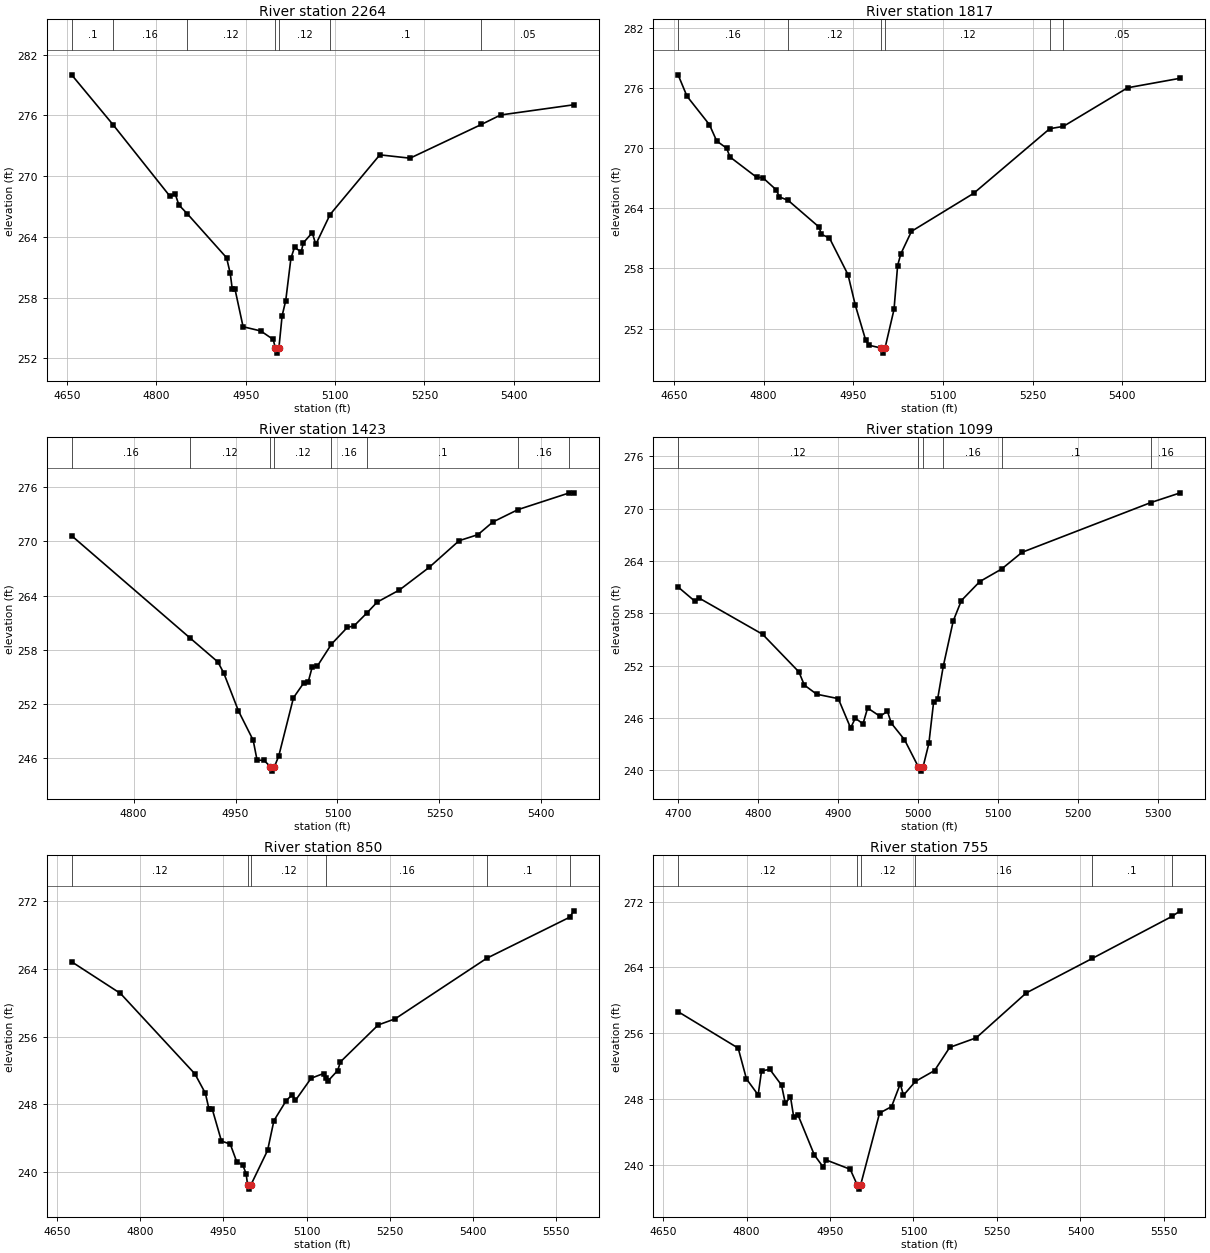
Type RM Length L Ch R = 1 ,2264    ,447,447,447
BEGIN DESCRIPTION:
Mapping XS 3156962e
END DESCRIPTION:
XS GIS Cut Line= 4
      3596176.39     10150144.29      3595955.92     10150300.53
      3595891.68     10150392.54      3595513.24     10150654.67
#Sta/Elev= 30
    4658  280.02  4727.6  275.08  4823.2     268  4831.9  268.22    4838  267.15
    4852  266.29    4918  261.94  4924.1   260.4  4927.5  258.87    4932  258.87
  4945.7  255.12  4975.4   254.7  4996.3  253.86  4999.8  253.01  5002.5  252.51
  5005.8  253.01  5011.2   256.2  5017.3  257.71    5026  261.89  5032.1  262.98
  5043.2   262.5  5046.8  263.41  5061.7  264.41  5067.8  263.26  5091.7  266.21
  5175.2  272.11  5225.9  271.78  5345.5  275.11  5377.9  276.05  5500.8  277.06
#Mann= 7 ,-1 , 0
    4658      .1       0  4727.6     .16       0    4852     .12       0
  4999.8     .07       0  5005.8     .12       0  5091.7      .1       0
  5345.5     .05       0
Bank Sta=4999.8,5005.8
XS Rating Curve= 0 ,0
Exp/Cntr=0.3,0.1

Type RM Length L Ch R = 1 ,1817    ,394,394,394
BEGIN DESCRIPTION:
Mapping XS 097923fe
END DESCRIPTION:
XS GIS Cut Line= 5
      3595938.55     10149968.93      3595725.01     10150080.04
      3595667.72     10150220.67      3595645.15     10150415.11
      3595527.74     10150637.85
#Sta/Elev= 30
    4657  277.29  4671.8  275.16  4709.4  272.32  4721.6  270.69  4738.1  269.98
  4743.8   269.1  4788.3  267.08  4798.8  267.03  4820.9  265.84  4826.5  265.12
    4841  264.78  4892.9  262.11  4896.5   261.4  4910.2  261.02  4941.2  257.37
  4953.4  254.33  4970.7  250.86  4976.1  250.34  4997.1  250.05  4999.9  249.55
  5003.1  250.05  5018.2  253.91  5024.2  258.28  5029.6  259.45  5047.4  261.69
  5151.2  265.47  5278.7  271.92  5301.4  272.15    5409     276  5497.1  276.95
#Mann= 6 ,-1 , 0
    4657     .16       0    4841     .12       0  4997.1     .07       0
  5003.1     .12       0  5278.7      .1       0  5301.4     .05       0
Bank Sta=4997.1,5003.1
XS Rating Curve= 0 ,0
Exp/Cntr=0.3,0.1

Type RM Length L Ch R = 1 ,1423    ,324,324,324
BEGIN DESCRIPTION:
Mapping XS 3b6563a7
END DESCRIPTION:
XS GIS Cut Line= 3
       3595759.7     10149805.75      3595447.24     10149981.08
      3595268.76     10150317.25
#Sta/Elev= 30
  4708.9  270.63  4882.6  259.34    4924  256.66  4932.6  255.45  4954.3  251.24
    4976  247.99  4981.7  245.79  4991.9  245.76  5001.3  245.07    5004  244.57
  5007.3  245.07  5013.6  246.24  5035.3   252.7  5050.1   254.3    5057  254.46
  5062.7  256.05  5070.5  256.21  5091.2  258.63  5114.5  260.48  5124.4  260.65
  5143.6   262.1  5158.4  263.28  5191.1  264.62    5235  267.13    5279  270.08
  5306.7  270.75  5328.6  272.15  5365.6  273.52  5441.4  275.38  5447.8  275.35
#Mann= 8 ,-1 , 0
  4708.9     .16       0  4882.6     .12       0  5001.3     .07       0
  5007.3     .12       0  5091.2     .16       0  5143.6      .1       0
  5365.6     .16       0  5441.4     .05       0
Bank Sta=5001.3,5007.3
XS Rating Curve= 0 ,0
Exp/Cntr=0.3,0.1

Type RM Length L Ch R = 1 ,1099    ,249,249,249
BEGIN DESCRIPTION:
Mapping XS d93d1318
END DESCRIPTION:
XS GIS Cut Line= 3
      3595540.86     10149693.53      3595317.78     10149830.68
      3595250.93     10150190.96
#Sta/Elev= 30
  4699.6     261  4720.2   259.4  4726.1  259.72  4805.3  255.58  4850.7  251.27
  4857.5  249.76  4872.9  248.71    4900   248.2  4915.4  244.84  4921.3  245.96
  4930.9  245.31  4936.7  247.13  4952.1  246.18  4961.5  246.74  4966.3  245.39
  4982.8   243.5  5000.1  240.39  5002.9  239.89  5006.1  240.39  5013.3  243.06
  5019.2  247.76  5024.3  248.17  5031.3   251.9  5043.8  257.11    5054  259.45
  5077.1  261.63  5104.3  263.06  5129.9  264.98  5290.9  270.68  5327.9   271.8
#Mann= 6 ,-1 , 0
  4699.6     .12       0  5000.1     .07       0  5006.1     .12       0
  5031.3     .16       0  5104.3      .1       0  5290.9     .16       0
Bank Sta=5000.1,5006.1
XS Rating Curve= 0 ,0
Exp/Cntr=0.3,0.1

Type RM Length L Ch R = 1 ,850     ,95,95,95
BEGIN DESCRIPTION:
Mapping XS 15b5ae16
END DESCRIPTION:
XS GIS Cut Line= 4
      3595609.49     10149588.48       3595390.7     10149613.66
      3595173.68     10149723.91      3595253.18     10150158.55
#Sta/Elev= 30
  4676.5  264.85  4764.5  261.11  4898.7  251.61  4917.6  249.32  4924.3   247.4
  4929.9  247.47  4946.6  243.67  4962.5  243.31  4974.4  241.18  4984.9  240.87
  4991.1  239.81  4993.7  238.49  4996.4  237.99  4999.7  238.49  5029.8  242.57
  5041.2  246.08  5063.4  248.45  5074.5  249.16  5080.1  248.48  5108.3  251.09
  5130.7  251.65  5135.1  251.11  5138.2  250.73  5156.1     252  5161.2  253.03
  5229.3  257.39  5259.8  258.11  5425.1  265.27  5574.4  270.11    5582  270.87
#Mann= 6 ,-1 , 0
  4676.5     .12       0  4993.7     .07       0  4999.7     .12       0
  5135.1     .16       0  5425.1      .1       0  5574.4     .16       0
Bank Sta=4993.7,4999.7
XS Rating Curve= 0 ,0
Exp/Cntr=0.3,0.1

Type RM Length L Ch R = 1 ,755     ,97,97,97
BEGIN DESCRIPTION:
Mapping XS f19260ef
END DESCRIPTION:
XS GIS Cut Line= 4
      3595443.67     10149394.03      3595282.19     10149504.29
      3595149.38     10149729.98      3595250.94     10150163.14
#Sta/Elev= 30
  4677.1  258.63    4785  254.21  4799.9  250.47  4820.9  248.53    4827  251.45
  4841.9  251.63  4862.9  249.72  4869.7   247.5    4879   248.3  4884.8  245.84
  4892.8  246.05  4921.9  241.24  4937.6  239.79  4943.4  240.63  4986.3  239.51
    4999   237.6  5001.7   237.1    5005   237.6  5039.1  246.33  5060.6  247.11
  5076.2  249.87    5082  248.49  5103.5  250.17  5137.9  251.49  5165.1   254.3
  5212.7  255.46  5302.7  260.91  5421.4   265.1  5564.3  270.19  5579.4  270.87
#Mann= 6 ,-1 , 0
  4677.1     .12       0    4999     .07       0    5005     .12       0
  5103.5     .16       0  5421.4      .1       0  5564.3     .16       0
Bank Sta=4999,5005
XS Rating Curve= 0 ,0
Exp/Cntr=0.3,0.1

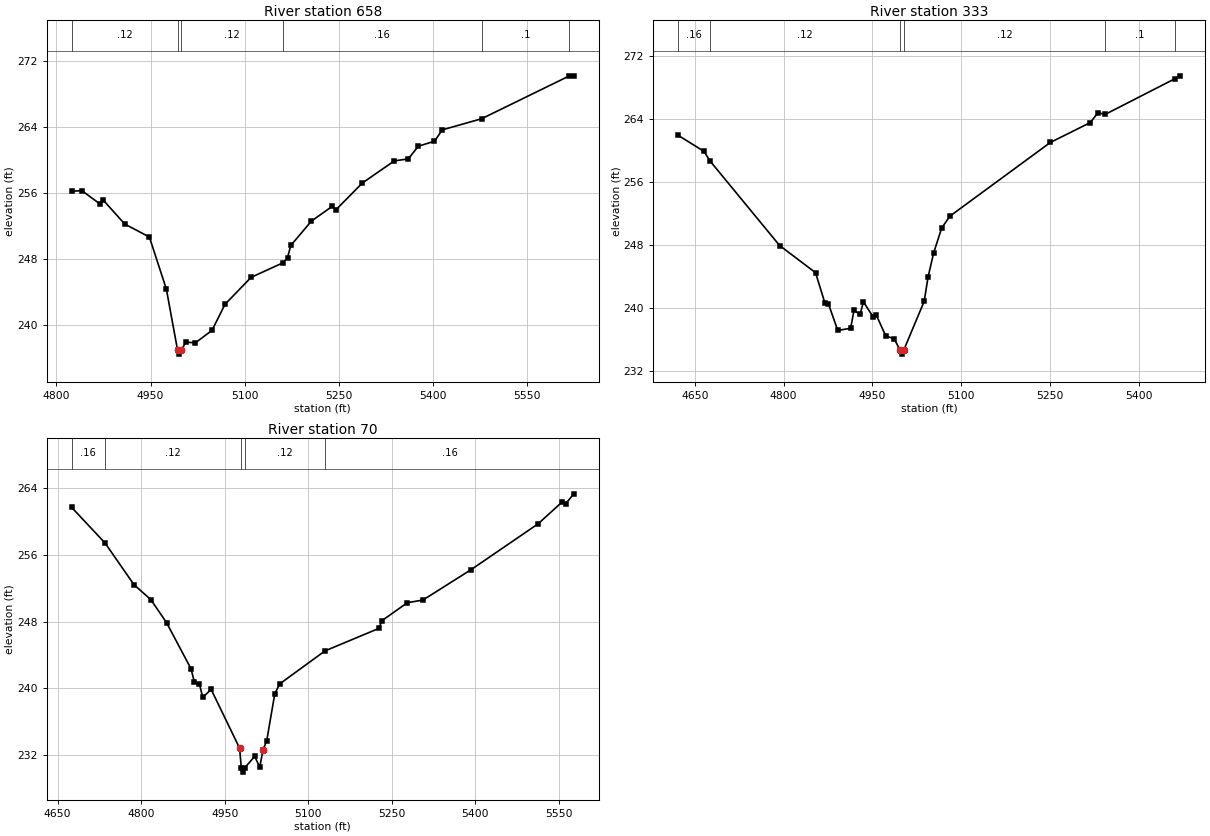
Type RM Length L Ch R = 1 ,658     ,325,325,325
BEGIN DESCRIPTION:
Mapping XS fecd2c89
END DESCRIPTION:
XS GIS Cut Line= 3
      3595190.18      10149386.2      3595106.84     10149683.98
      3595248.33     10150154.45
#Sta/Elev= 30
  4824.2  256.22  4840.5   256.3  4869.5  254.68  4874.7  255.14  4908.8  252.26
  4948.1  250.69  4975.2  244.38    4993  237.03  4995.7  236.53    4999  237.03
  5006.4  237.97  5021.5   237.9  5047.9   239.4  5068.7  242.56  5110.2  245.81
  5161.2  247.58  5168.3  248.19  5173.5  249.67  5206.5  252.62  5239.6   254.4
  5245.8  254.01  5287.6  257.22  5338.6   259.9  5360.7  260.13  5376.9  261.67
  5402.5  262.27  5415.1  263.65  5477.7  264.99  5617.7  270.18  5624.7  270.11
#Mann= 6 ,-1 , 0
  4824.2     .12       0    4993     .07       0    4999     .12       0
  5161.2     .16       0  5477.7      .1       0  5617.7     .16       0
Bank Sta=4993,4999
XS Rating Curve= 0 ,0
Exp/Cntr=0.3,0.1

Type RM Length L Ch R = 1 ,333     ,263,263,263
BEGIN DESCRIPTION:
Mapping XS fdf1689a
END DESCRIPTION:
XS GIS Cut Line= 3
      3594974.04     10149390.54      3594908.06     10149571.13
      3595229.23     10150143.17
#Sta/Elev= 30
  4621.9  261.97  4665.7  259.93  4675.5  258.74  4793.4  247.98    4854  244.54
  4869.9  240.68  4875.7   240.6  4891.6  237.21  4913.3  237.48    4919  239.75
  4929.2  239.25    4935  240.83  4950.9  238.97  4956.7  239.15  4972.6  236.52
  4986.8  236.14    4997   234.7  4999.8   234.2    5003   234.7  5037.6  240.91
  5044.1  243.99  5053.6  247.06  5067.1   250.2    5081  251.71  5250.6  261.06
  5318.2  263.59  5330.8  264.81  5343.7  264.64  5460.5  269.13  5470.2  269.52
#Mann= 6 ,-1 , 0
  4621.9     .16       0  4675.5     .12       0    4997     .07       0
    5003     .12       0  5343.7      .1       0  5460.5     .16       0
Bank Sta=4997,5003
XS Rating Curve= 0 ,0
Exp/Cntr=0.3,0.1

Type RM Length L Ch R = 1 ,70      ,0,0,0
BEGIN DESCRIPTION:
HUTTON MILL BRANCH TRIB 1 1.0
END DESCRIPTION:
XS GIS Cut Line= 4
      3594956.65     10149389.73       3594746.6     10149706.54
      3594803.89     10149897.52      3595056.75     10150096.87
#Sta/Elev= 30
  4675.3  261.63  4735.2  257.38  4787.3  252.39  4817.4  250.62  4845.6  247.87
  4889.6  242.35  4895.6  240.76  4904.7  240.53  4910.6  238.94  4925.7  239.89
  4976.8  232.87  4979.8  230.51  4982.6  230.01  4985.8  230.51  5003.9  231.89
  5012.9  230.61  5018.9  232.66  5025.5  233.77    5040  239.39    5049  240.56
  5130.1  244.49  5226.9  247.18  5232.1  248.09    5278  250.25  5305.8  250.56
  5392.5   254.2  5512.7  259.67    5556  262.29  5562.4  262.09  5576.8  263.25
#Mann= 5 ,-1 , 0
  4675.3     .16       0  4735.2     .12       0  4979.8     .07       0
  4985.8     .12       0  5130.1     .16       0
Bank Sta=4976.8,5018.9
XS Rating Curve= 0 ,0
Exp/Cntr=0.3,0.1

Chan Stop Cuts=-1
Use User Specified Reach Order=0
Composite Channel Slope=5