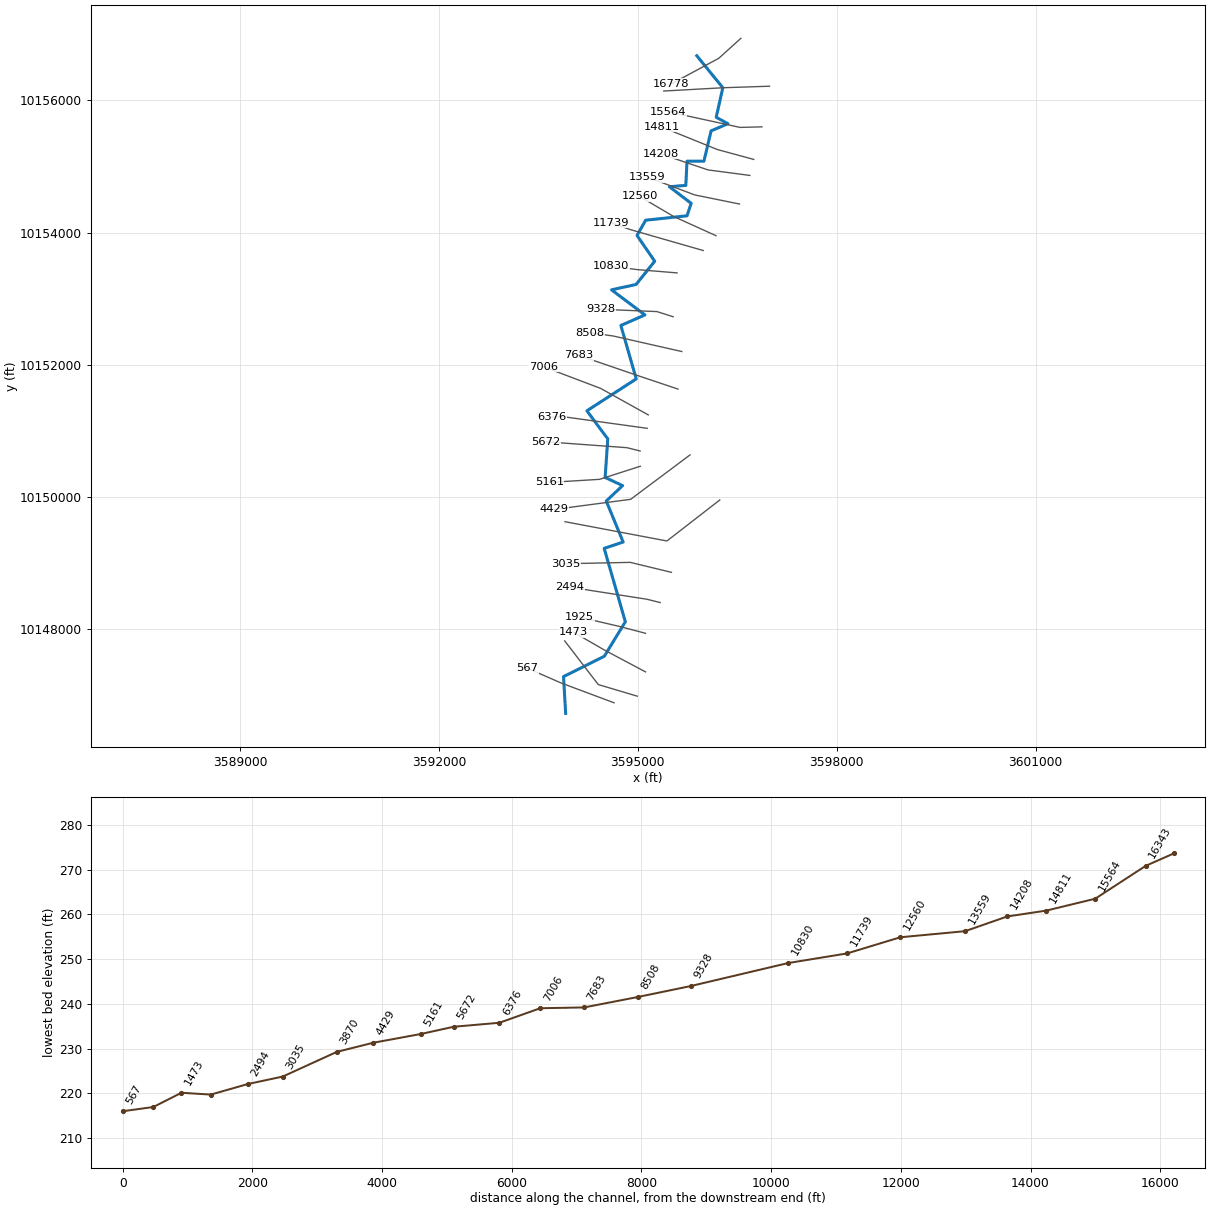
--- HUTTON MILL BRANCH.prj (project) ---

Proj Title=HUTTON MILL BRANCH Base Level Engineering
Current Plan=p01
Default Exp/Contr=0.3,0.1
English Units
Geom File=g01
Flow File=f01
Plan File=p01
Y Axis Title=Elevation
X Axis Title(PF)=Main Channel Distance
X Axis Title(XS)=Station
BEGIN DESCRIPTION:
HUTTON MILL BRANCH
END DESCRIPTION:
DSS Export Rating Curves= 0
DSS Export Rating Curve Sorted= 0
DSS Export Volume Flow Curves= 0
DXF OffsetX= 0
DXF OffsetY= 0
DXF ScaleX= 1
DXF ScaleY= 10

--- HUTTON MILL BRANCH.p01 (plan) ---

Plan Title=Multiple Run
Short Identifier=Multiple
Geom File=g01
Flow File=f01
Subcritical Flow
K Sum by GR= 0
Std Step Tol= 0.01
Critical Tol= 0.01
Num of Std Step Trials= 20
Max Error Tol= 0.3
Flow Tol Ratio= 0.001
Split Flow NTrial= 30
Split Flow Tol= 0.02
Split Flow Ratio= 0.02
Log Output Level= 0
Friction Slope Method= 1
Unsteady Friction Slope Method= 2
Unsteady Bridges Friction Slope Method= 1
Parabolic Critical Depth
Global Vel Dist=  1 , 1 , 1
Global Log Level= 0
CheckData=True
Encroach Param= -1, 0, 0, 0
BEGIN DESCRIPTION:
Multiple Run
END DESCRIPTION:

--- HUTTON MILL BRANCH.f01 (steady flow) ---

Flow Title=Multiple
Program Version=4.10
Number of Profiles= 7
Profile Names=10-year,25-year,50-year,1pct_min,100-year,1pct_plu,500-year
River Rch & RM=HUTTON MILL BRAN,Reach-1         ,16778
     616     832    1008     895    1211    1638    1751
River Rch & RM=HUTTON MILL BRAN,Reach-1         ,13559
     826    1128    1377    1231    1665    2251    2437
River Rch & RM=HUTTON MILL BRAN,Reach-1         ,3870
     945    1299    1591    1426    1929    2609    2841
Boundary for River Rch & Prof#=HUTTON MILL BRAN,Reach-1         , 1
Up Type= 0
Dn Type= 3
Dn Slope=0.005
Boundary for River Rch & Prof#=HUTTON MILL BRAN,Reach-1         , 2
Up Type= 0
Dn Type= 3
Dn Slope=0.005
Boundary for River Rch & Prof#=HUTTON MILL BRAN,Reach-1         , 3
Up Type= 0
Dn Type= 3
Dn Slope=0.005
Boundary for River Rch & Prof#=HUTTON MILL BRAN,Reach-1         , 4
Up Type= 0
Dn Type= 3
Dn Slope=0.005
Boundary for River Rch & Prof#=HUTTON MILL BRAN,Reach-1         , 5
Up Type= 0
Dn Type= 3
Dn Slope=0.005
Boundary for River Rch & Prof#=HUTTON MILL BRAN,Reach-1         , 6
Up Type= 0
Dn Type= 3
Dn Slope=0.005
Boundary for River Rch & Prof#=HUTTON MILL BRAN,Reach-1         , 7
Up Type= 0
Dn Type= 3
Dn Slope=0.005
DSS Import GetInterval= 0
DSS Import GetPeak= 0
DSS Import FillOption= 0

--- HUTTON MILL BRANCH.g01 (geometry) ---

Geom Title=Existing Conditions
Program Version=4.10

River Reach=HUTTON MILL BRAN,Reach-1
Reach XY= 30
      3595889.96      10156675.1      3596282.11     10156191.64
      3596182.49       10155745.      3596360.24     10155647.41
      3596105.52      10155539.6      3595997.05     10155080.08
      3595742.11     10155081.64      3595724.22     10154715.23
      3595477.19     10154694.55      3595805.36     10154443.01
      3595742.47     10154255.16      3595119.02     10154188.53
      3594988.34     10153957.82        3595255.     10153568.21
      3594974.42     10153216.99      3594603.75     10153135.58
       3595107.6     10152756.38      3594744.46     10152596.59
      3594976.95     10151788.95      3594232.38     10151306.68
      3594547.49     10150881.36      3594507.28       10150299.
      3594770.43     10150175.61      3594524.37     10149941.93
      3594779.06     10149322.91      3594493.05       10149227.
      3594812.17     10148117.18      3594495.46     10147595.29
      3593879.99     10147287.99      3593912.11     10146731.64

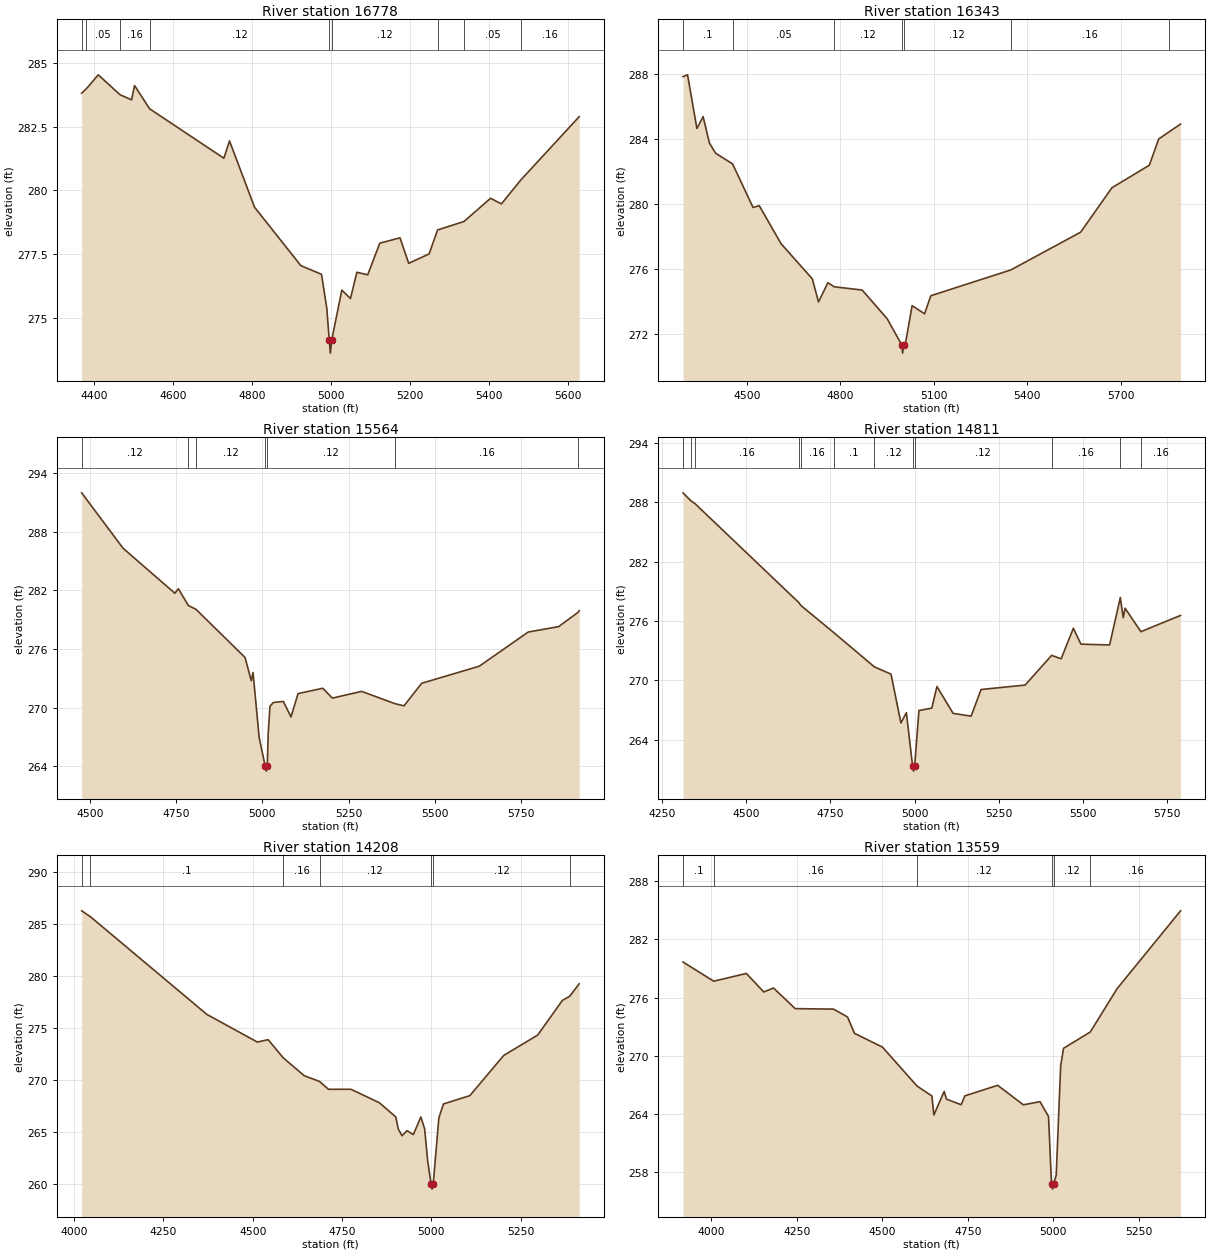
Type RM Length L Ch R = 1 ,16778   ,435,435,435
BEGIN DESCRIPTION:
HUTTON MILL BRANCH 31.0
END DESCRIPTION:
XS GIS Cut Line= 3
      3596554.37     10156938.42      3596221.07     10156636.36
      3595507.52     10156250.94
#Sta/Elev= 30
  4368.6  283.81  4380.8  283.99  4410.7  284.53  4465.8  283.75  4495.1  283.55
  4502.6  284.11  4540.7   283.2    4729  281.26  4743.2  281.94  4806.7  279.34
  4924.1  277.05  4976.4  276.71  4989.8  275.38  4996.1  274.12  4998.8  273.62
  5002.1  274.12  5027.9  276.09  5049.8  275.76    5066  276.79  5093.5  276.69
  5124.1  277.93  5175.4  278.14  5197.3  277.14  5249.1  277.51  5270.6  278.45
  5337.4  278.78  5404.8  279.69  5432.3  279.47  5481.6  280.41  5629.4  282.89
#Mann= 9 ,-1 , 0
  4368.6     .12       0  4380.8     .05       0  4465.8     .16       0
  4540.7     .12       0  4996.1     .07       0  5002.1     .12       0
  5270.6     .16       0  5337.4     .05       0  5481.6     .16       0
Bank Sta=4996.1,5002.1
XS Rating Curve= 0 ,0
Exp/Cntr=0.3,0.1

Type RM Length L Ch R = 1 ,16343   ,779,779,779
BEGIN DESCRIPTION:
HUTTON MILL BRANCH 30.0
END DESCRIPTION:
XS GIS Cut Line= 3
      3596986.68     10156214.49      3596292.11     10156191.64
      3595392.15     10156141.64
#Sta/Elev= 30
    4295  287.85  4309.6  287.96  4339.6  284.66  4359.6  285.39  4379.6  283.77
  4399.6  283.14  4454.1  282.48  4519.7   279.8  4539.7  279.91  4609.7  277.57
  4709.8  275.41  4729.8  273.99  4759.8  275.17  4780.5  274.92  4869.9  274.72
  4949.9  272.96    4997  271.34  4999.7  270.84    5003  271.34    5010  271.56
    5030  273.76  5070.1  273.26  5090.1  274.37  5347.1  275.96  5570.8  278.28
    5671  281.01  5791.2   282.4  5821.2  284.01  5852.9  284.43  5891.3  284.93
#Mann= 7 ,-1 , 0
    4295      .1       0  4454.1     .05       0  4780.5     .12       0
    4997     .07       0    5003     .12       0  5347.1     .16       0
  5852.9      .1       0
Bank Sta=4997,5003
XS Rating Curve= 0 ,0
Exp/Cntr=0.3,0.1

Type RM Length L Ch R = 1 ,15564   ,753,753,753
BEGIN DESCRIPTION:
HUTTON MILL BRANCH 29.0
END DESCRIPTION:
XS GIS Cut Line= 3
      3596872.09      10155599.9      3596542.11     10155591.64
      3595456.31     10155828.88
#Sta/Elev= 30
  4476.3     292  4596.3  286.32  4746.4  281.71  4756.4  282.18  4785.4  280.46
  4807.7  280.06  4949.7  275.13  4967.7  272.75  4972.8   273.6  4990.6  266.92
  5008.1  263.99  5010.9  263.49  5014.1  263.99  5016.7  267.29  5021.8  270.13
  5031.6  270.52  5060.6  270.63  5082.8  269.04  5103.2  271.43  5174.9  271.98
  5202.5  270.97  5287.5  271.66  5384.1   270.4  5410.3  270.18  5461.5  272.49
  5628.3  274.24  5770.2  277.74    5858  278.29  5915.1  279.77  5917.8  279.93
#Mann= 7 ,-1 , 0
  4476.3     .12       0  4785.4     .16       0  4807.7     .12       0
  5008.1     .07       0  5014.1     .12       0  5384.1     .16       0
  5915.1      .1       0
Bank Sta=5008.1,5014.1
XS Rating Curve= 0 ,0
Exp/Cntr=0.3,0.1

Type RM Length L Ch R = 1 ,14811   ,603,603,603
BEGIN DESCRIPTION:
HUTTON MILL BRANCH 28.0
END DESCRIPTION:
XS GIS Cut Line= 3
      3596749.42     10155107.26       3596199.4     10155257.27
      3595356.76     10155599.79
#Sta/Elev= 30
  4311.5  288.94    4335  288.13  4346.8  287.86  4657.1  277.82  4661.6  277.58
  4760.5  274.81  4880.6  271.37  4930.2  270.63  4959.6   265.7  4975.8  266.74
  4994.4  261.34  4997.2  260.84  5000.4  261.34  5013.2  266.96  5051.4   267.2
  5066.7  269.38  5114.9  266.67  5168.4  266.39  5197.9  269.08    5329  269.53
  5407.9  272.53  5436.1  272.18  5472.4  275.26    5495  273.66  5580.3  273.58
  5612.1  278.37  5620.8  276.33  5626.2  277.29  5673.3  274.92  5791.2  276.56
#Mann= 12 ,-1 , 0
  4311.5     .12       0    4335      .1       0  4346.8     .16       0
  4657.1      .1       0  4661.6     .16       0  4760.5      .1       0
  4880.6     .12       0  4994.4     .07       0  5000.4     .12       0
  5407.9     .16       0  5612.1     .12       0  5673.3     .16       0
Bank Sta=4994.4,5000.4
XS Rating Curve= 0 ,0
Exp/Cntr=0.3,0.1

Type RM Length L Ch R = 1 ,14208   ,649,649,649
BEGIN DESCRIPTION:
HUTTON MILL BRANCH 27.0
END DESCRIPTION:
XS GIS Cut Line= 3
      3596689.82     10154865.53      3596059.61     10154948.86
      3595342.06     10155191.66
#Sta/Elev= 30
    4021  286.23  4045.7  285.66  4371.7  276.29    4513  273.64  4543.2  273.87
  4585.6  272.12  4644.4  270.41  4687.2  269.86  4712.1  269.11    4775  269.11
  4854.6  267.82  4900.8  266.45  4907.4  265.32    4918  264.65  4932.2  265.14
  4949.7  264.76  4970.8  266.45  4981.3  265.33  4989.8  262.27  4999.4  260.03
  5002.2  259.53  5005.4  260.03  5021.2  266.36  5034.1   267.7    5108   268.5
    5203  272.36    5298  274.31    5367  277.63  5387.7  278.04  5414.2  279.23
#Mann= 7 ,-1 , 0
    4021     .12       0  4045.7      .1       0  4585.6     .16       0
  4687.2     .12       0  4999.4     .07       0  5005.4     .12       0
  5387.7     .16       0
Bank Sta=4999.4,5005.4
XS Rating Curve= 0 ,0
Exp/Cntr=0.3,0.1

Type RM Length L Ch R = 1 ,13559   ,999,999,999
BEGIN DESCRIPTION:
HUTTON MILL BRANCH 25.0
END DESCRIPTION:
XS GIS Cut Line= 3
      3596533.53     10154433.24      3595858.56     10154570.76
       3595142.1     10154841.65
#Sta/Elev= 30
  3917.4  279.67  4007.4  277.69  4102.6  278.49  4153.6  276.58    4182  276.99
  4245.4  274.86  4357.7  274.81  4398.5     274  4418.9  272.31  4500.6  270.89
  4601.8  266.87  4645.2  265.85  4650.9  263.89    4681  266.32    4688  265.52
  4730.7  264.95  4741.4  265.86  4837.6  266.95  4912.5  264.94  4961.4  265.26
  4986.2  263.73    4995  256.74  4997.8  256.24    5001  256.74  5008.7  257.68
  5021.7  268.97  5030.1  270.77  5108.3  272.45  5186.7  276.92  5372.2  284.95
#Mann= 6 ,-1 , 0
  3917.4      .1       0  4007.4     .16       0  4601.8     .12       0
    4995     .07       0    5001     .12       0  5108.3     .16       0
Bank Sta=4995,5001
XS Rating Curve= 0 ,0
Exp/Cntr=0.3,0.1

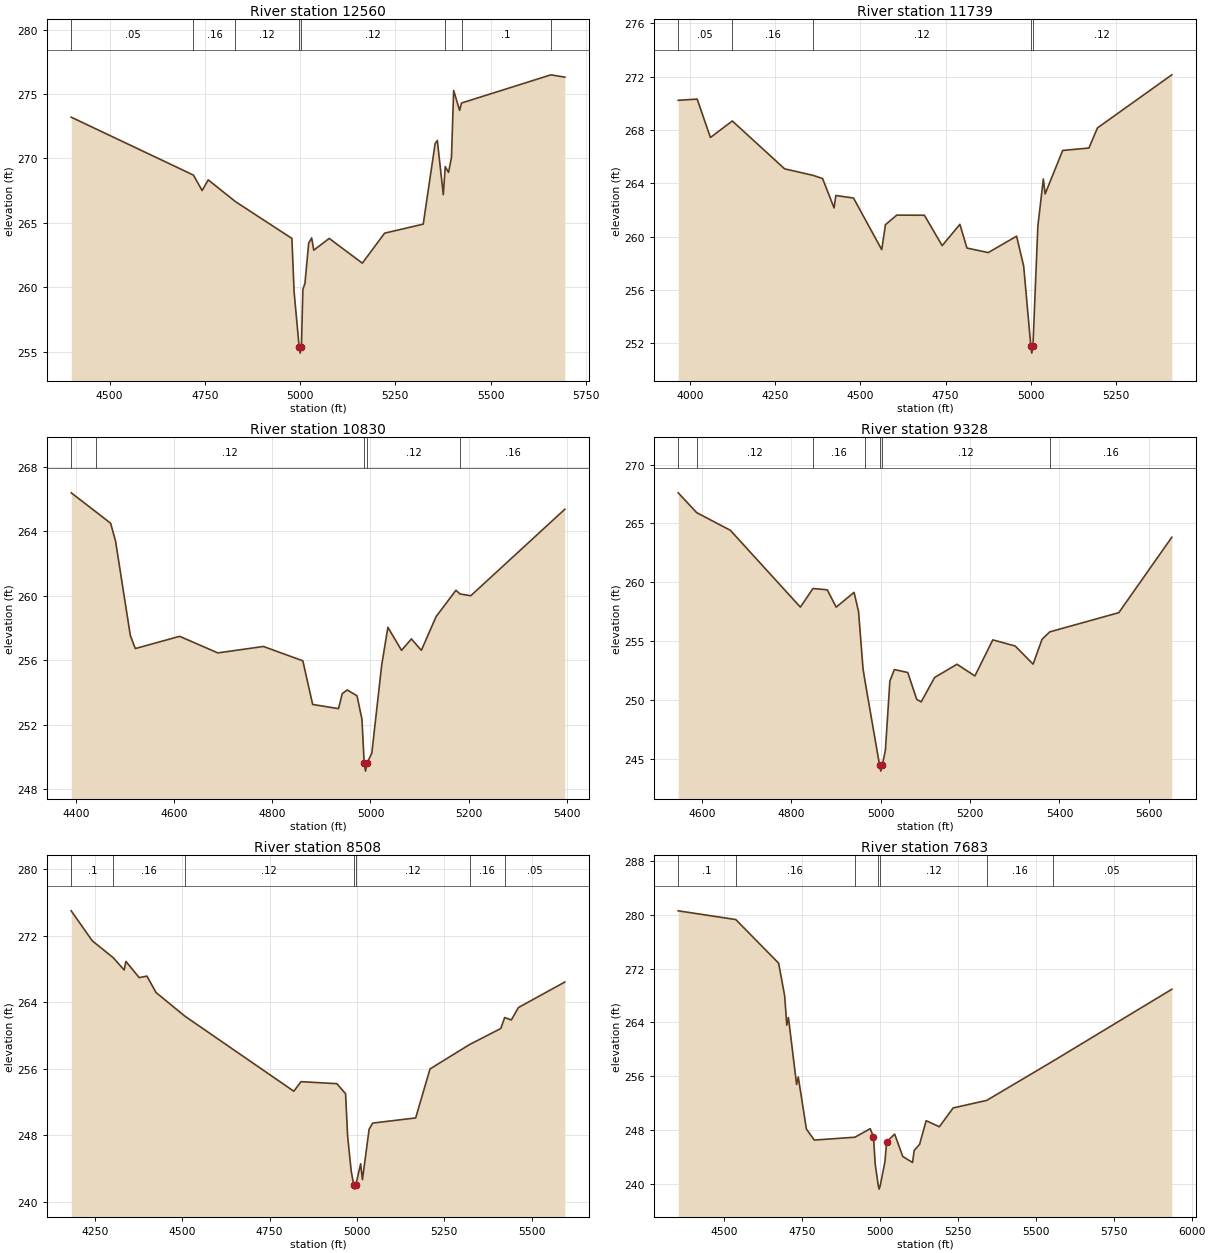
Type RM Length L Ch R = 1 ,12560   ,821,821,821
BEGIN DESCRIPTION:
HUTTON MILL BRANCH 24.0
END DESCRIPTION:
XS GIS Cut Line= 3
      3596179.44     10153954.05      3595538.78     10154245.74
      3595029.35     10154547.24
#Sta/Elev= 30
  4399.2  273.21  4720.1  268.71  4742.9  267.51  4758.9  268.34  4830.4  266.65
  4978.6  263.79  4984.4  259.63  4997.6  255.38  5000.3  254.88  5003.6  255.38
  5007.4  259.82  5012.9  260.31  5022.6  263.42  5030.5  263.83    5036  262.88
  5076.6  263.79  5163.5  261.87    5222   264.2  5323.4   264.9  5354.6  271.15
  5360.4   271.4  5376.1  267.19  5381.2  269.37  5389.8  268.92  5397.5  270.07
  5403.3  275.28  5418.9  273.74  5423.9  274.31  5658.7   276.5  5695.1  276.32
#Mann= 8 ,-1 , 0
  4399.2     .05       0  4720.1     .16       0  4830.4     .12       0
  4997.6     .07       0  5003.6     .12       0  5381.2     .16       0
  5423.9      .1       0  5658.7     .16       0
Bank Sta=4997.6,5003.6
XS Rating Curve= 0 ,0
Exp/Cntr=0.3,0.1

Type RM Length L Ch R = 1 ,11739   ,909,909,909
BEGIN DESCRIPTION:
HUTTON MILL BRANCH 23.0
END DESCRIPTION:
XS GIS Cut Line= 3
      3595986.67     10153730.12      3594882.53     10154047.82
      3594601.24       10154152.
#Sta/Elev= 30
  3965.2  270.23  4020.9  270.32  4059.8  267.44    4124  268.68  4277.5  265.09
  4361.2   264.6    4389  264.36  4422.7  262.16  4427.9  263.09  4479.8   262.9
  4562.6  259.03  4573.5   260.9  4606.7  261.62  4687.9  261.61    4740  259.33
    4792  260.93  4812.8  259.15  4875.3  258.81  4958.5  260.04  4979.3  257.79
  5000.4  251.77  5003.1  251.27  5006.4  251.77  5020.9  260.79    5037  264.33
  5042.3  263.21  5093.8  266.47  5170.8  266.65  5195.9  268.16  5414.1  272.14
#Mann= 5 ,-1 , 0
  3965.2     .05       0    4124     .16       0  4361.2     .12       0
  5000.4     .07       0  5006.4     .12       0
Bank Sta=5000.4,5006.4
XS Rating Curve= 0 ,0
Exp/Cntr=0.3,0.1

Type RM Length L Ch R = 1 ,10830   ,1502,1502,1502
BEGIN DESCRIPTION:
HUTTON MILL BRANCH 21.0
END DESCRIPTION:
XS GIS Cut Line= 3
      3595592.14     10153391.64      3594992.11     10153441.64
      3594592.13     10153491.64
#Sta/Elev= 30
  4390.6   266.4  4441.3  265.21  4470.9  264.51  4480.9   263.4    4511  257.54
  4521.1  256.73  4611.4  257.49  4689.2  256.46    4782  256.86  4862.3  255.97
  4882.3  253.26    4935     253  4942.5  253.93  4952.6  254.16  4972.6   253.8
  4982.7  252.34  4987.2  249.62    4990  249.12  4993.2  249.62  5002.8  250.24
  5022.9  255.71  5035.5  258.05  5063.3  256.62  5083.4  257.33  5103.6  256.62
  5133.8  258.72  5174.1  260.35  5182.4  260.12  5204.3  260.01  5395.8  265.38
#Mann= 5 ,-1 , 0
  4390.6     .05       0  4441.3     .12       0  4987.2     .07       0
  4993.2     .12       0  5182.4     .16       0
Bank Sta=4987.2,4993.2
XS Rating Curve= 0 ,0
Exp/Cntr=0.3,0.1

Type RM Length L Ch R = 1 ,9328    ,820,820,820
BEGIN DESCRIPTION:
HUTTON MILL BRANCH 19.0
END DESCRIPTION:
XS GIS Cut Line= 3
      3595533.14     10152728.81      3595288.34     10152806.94
      3594442.12     10152841.64
#Sta/Elev= 30
  4547.3   267.6  4588.6  265.92  4663.9  264.42  4820.5   257.9  4848.7  259.48
  4880.6  259.37  4900.6   257.9  4940.6  259.15  4950.6  257.53  4960.6  252.68
  4964.7   251.7  4997.7  244.48  5000.4  243.98  5003.7  244.48  5010.7  245.77
  5020.7  251.63  5030.7   252.6  5060.7  252.35  5080.7  250.07  5090.7  249.86
  5120.8  251.93  5170.8  253.05  5210.8  252.06  5250.9  255.12  5300.9   254.6
    5341  253.06    5361  255.17  5378.3   255.8  5532.7  257.43  5651.2  263.83
#Mann= 7 ,-1 , 0
  4547.3     .16       0  4588.6     .12       0  4848.7     .16       0
  4964.7     .12       0  4997.7     .07       0  5003.7     .12       0
  5378.3     .16       0
Bank Sta=4997.7,5003.7
XS Rating Curve= 0 ,0
Exp/Cntr=0.3,0.1

Type RM Length L Ch R = 1 ,8508    ,825,825,825
BEGIN DESCRIPTION:
HUTTON MILL BRANCH 18.0
END DESCRIPTION:
XS GIS Cut Line= 3
      3595663.39     10152202.76      3594630.65     10152437.48
      3594280.68     10152487.47
#Sta/Elev= 30
  4182.4  274.98  4242.6  271.38    4303  269.33  4333.9  267.87    4339   268.9
  4376.9  266.95  4399.1  267.13  4425.1  265.16  4507.2  262.33  4819.5  253.29
    4840  254.44  4942.6   254.2  4967.6  252.99  4973.4  247.91  4983.6  243.72
  4990.9  242.02  4993.6  241.52  4996.9  242.02  5010.7  244.57  5015.8  242.66
  5034.9  248.71  5045.1  249.46  5168.2  250.08  5209.2  255.97  5322.7  258.91
  5411.7  260.83  5422.9  262.15    5442  261.86  5462.2  263.35    5595  266.42
#Mann= 7 ,-1 , 0
  4182.4      .1       0    4303     .16       0  4507.2     .12       0
  4990.9     .07       0  4996.9     .12       0  5322.7     .16       0
  5422.9     .05       0
Bank Sta=4990.9,4996.9
XS Rating Curve= 0 ,0
Exp/Cntr=0.3,0.1

Type RM Length L Ch R = 1 ,7683    ,677,677,677
BEGIN DESCRIPTION:
HUTTON MILL BRANCH 16.0
END DESCRIPTION:
XS GIS Cut Line= 3
      3595606.01     10151635.07      3594992.11     10151841.64
      3594106.55     10152145.31
#Sta/Elev= 30
  4352.4   280.6  4537.2   279.3  4674.6  272.81  4694.1  267.93  4700.8  263.59
  4706.1  264.73  4732.3  254.77  4737.6  255.88  4763.8  248.13  4789.1   246.5
  4919.4  246.92  4968.5  248.19    4979  246.99  4984.4  242.98  4994.5   239.7
  4997.2   239.2  5000.5   239.7  5015.8  243.29  5021.3  246.24    5047  247.38
    5073  244.06  5104.3  243.16  5109.6  244.96    5127  245.87  5148.1  249.38
  5190.4  248.48  5234.7  251.28  5342.3   252.4  5553.8  258.21  5936.3  268.93
#Mann= 7 ,-1 , 0
  4352.4      .1       0  4537.2     .16       0  4919.4     .12       0
  4994.5     .07       0  5000.5     .12       0  5342.3     .16       0
  5553.8     .05       0
Bank Sta=4979,5021.3
XS Rating Curve= 0 ,0
Exp/Cntr=0.3,0.1

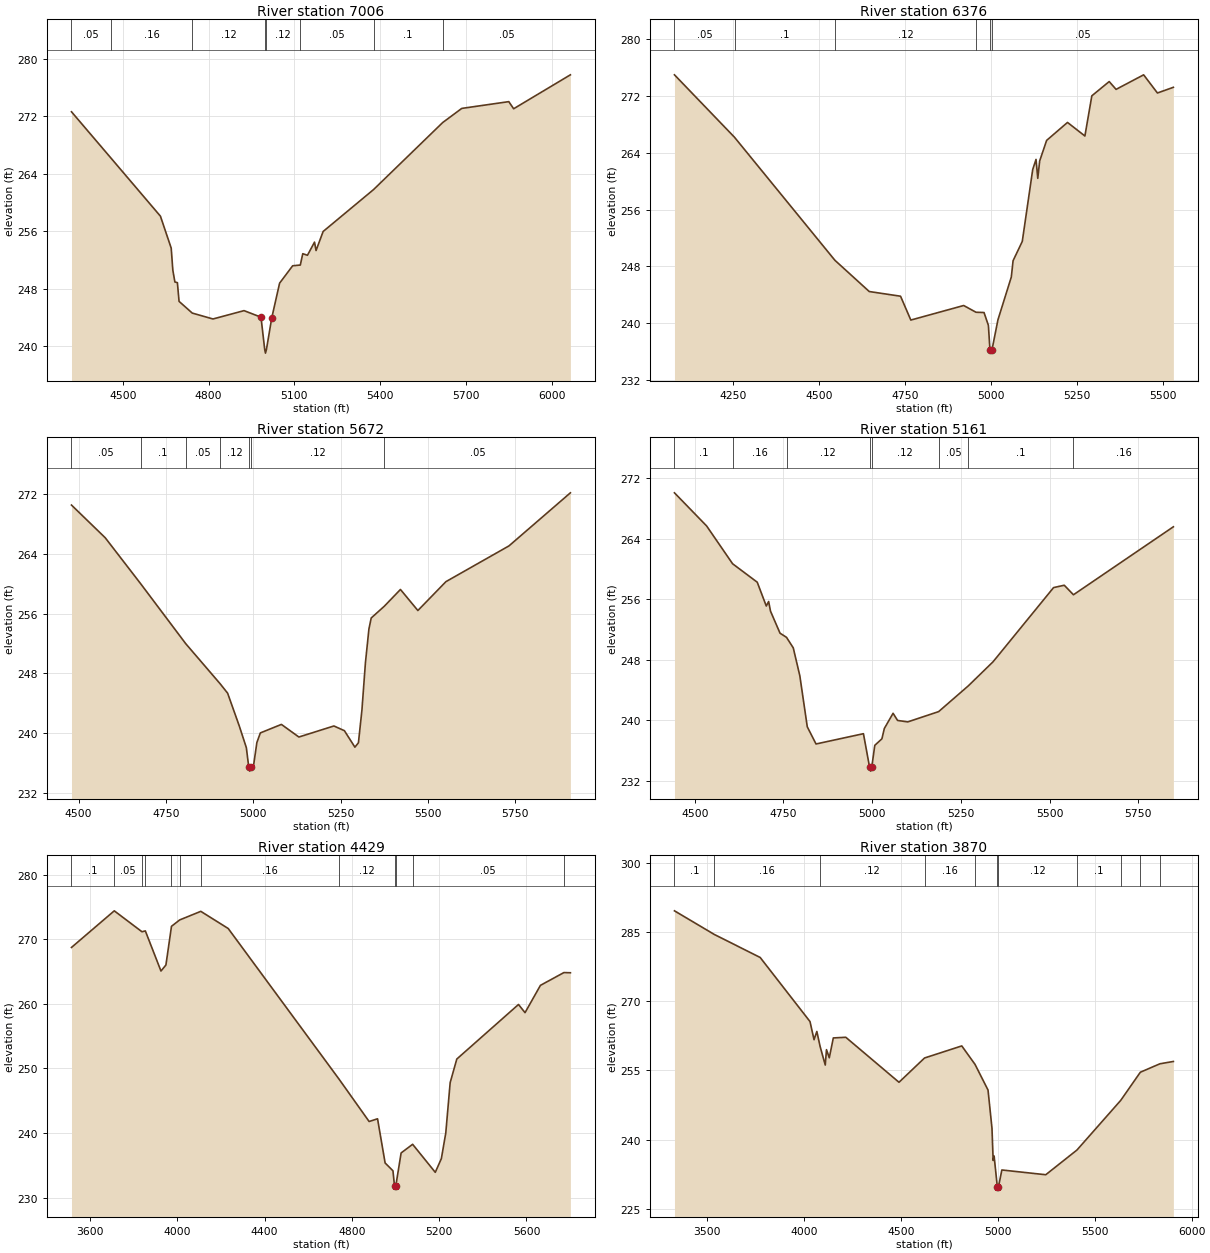
Type RM Length L Ch R = 1 ,7006    ,630,630,630
BEGIN DESCRIPTION:
HUTTON MILL BRANCH 15.0
END DESCRIPTION:
XS GIS Cut Line= 3
       3595158.1     10151244.46      3594439.38     10151645.48
       3593576.5     10151973.62
#Sta/Elev= 30
  4319.9  272.59  4458.1  266.15  4631.2  258.07  4668.9  253.63  4674.7  250.54
  4681.8  248.92  4690.6  248.82  4696.4  246.22  4742.6  244.59  4815.2  243.77
  4923.8  244.93  4983.2  244.02  4996.2  239.52  4998.9  239.02  5002.2  239.52
  5020.9  243.93  5048.3  248.75    5094  251.17  5120.8  251.27  5129.4  252.85
  5145.8  252.63  5170.5  254.46  5175.9  253.29  5200.7  255.94  5377.2  261.77
  5619.1  271.09  5685.9  273.06  5850.5     274  5867.5  273.01  6066.1  277.73
#Mann= 8 ,-1 , 0
  4319.9     .05       0  4458.1     .16       0  4742.6     .12       0
  4996.2     .07       0  5002.2     .12       0  5120.8     .05       0
  5377.2      .1       0  5619.1     .05       0
Bank Sta=4983.2,5020.9
XS Rating Curve= 0 ,0
Exp/Cntr=0.3,0.1

Type RM Length L Ch R = 1 ,6376    ,704,704,704
BEGIN DESCRIPTION:
HUTTON MILL BRANCH 13.0
END DESCRIPTION:
XS GIS Cut Line= 3
      3595142.13     10151041.64      3593904.61     10151213.52
      3593705.81     10151213.52
#Sta/Elev= 30
  4080.9  274.99  4255.2  266.19  4546.5  248.86  4646.3  244.45  4737.2  243.79
    4767  240.43  4920.4  242.48  4956.2  241.53  4979.5  241.49  4992.1  239.69
  4996.7  236.27  4999.4  235.77  5002.7  236.27  5019.9  240.47  5058.7   246.5
  5063.8  248.79  5090.5  251.51  5120.8  261.64  5130.4  263.07  5135.5   260.4
    5141  262.85  5161.2  265.75  5221.8  268.28  5272.3  266.37  5292.4  272.03
  5342.8  274.04  5362.8  272.94  5442.8  274.99  5482.8  272.43  5529.1  273.23
#Mann= 6 ,-1 , 0
  4080.9     .05       0  4255.2      .1       0  4546.5     .12       0
  4956.2     .05       0  4996.7     .03       0  5002.7     .05       0
Bank Sta=4996.7,5002.7
XS Rating Curve= 0 ,0
Exp/Cntr=0.3,0.1

Type RM Length L Ch R = 1 ,5672    ,511,511,511
BEGIN DESCRIPTION:
HUTTON MILL BRANCH 12.0
END DESCRIPTION:
XS GIS Cut Line= 3
      3595035.86     10150698.93      3594835.86     10150748.93
      3593616.77     10150838.16
#Sta/Elev= 30
  4479.4  270.53    4576  266.15  4677.5  259.99  4806.3  251.97  4905.5  246.56
  4926.5  245.32    4960  240.91  4980.1  238.02  4987.1  235.38  4989.9  234.88
  4993.1  235.38  5000.1  235.43  5010.2  238.71  5020.2     240  5080.4  241.14
  5130.5  239.45  5230.8  240.93  5260.8   240.3  5290.9  238.09    5301  238.68
    5311  243.05    5321  249.38    5331  253.91  5337.6   255.4    5375  256.97
  5421.3  259.22  5471.2   256.4  5551.6  260.27  5732.1  265.06  5907.9  272.17
#Mann= 7 ,-1 , 0
  4479.4     .05       0  4677.5      .1       0  4806.3     .05       0
  4905.5     .12       0  4987.1     .07       0  4993.1     .12       0
    5375     .05       0
Bank Sta=4987.1,4993.1
XS Rating Curve= 0 ,0
Exp/Cntr=0.3,0.1

Type RM Length L Ch R = 1 ,5161    ,732,732,732
BEGIN DESCRIPTION:
HUTTON MILL BRANCH 11.0
END DESCRIPTION:
XS GIS Cut Line= 3
      3595038.33     10150468.39      3594423.76     10150270.48
      3593665.25     10150223.72
#Sta/Elev= 30
  4442.9  270.05  4533.5  265.67  4606.7  260.67  4676.1  258.23  4701.6  255.08
  4708.2  255.68  4713.5   254.4  4740.3  251.49  4758.6  250.94  4777.6  249.55
  4796.1  245.86  4817.1  239.11  4841.7  236.84  4975.3   238.2  4992.7  233.75
  4995.5  233.25  4998.7  233.75  5007.3  236.66  5027.3  237.52  5034.2  238.89
  5058.8   240.9  5071.5  239.95  5100.2  239.76  5187.2  241.12  5271.1  244.54
  5340.7  247.72    5511  257.52  5541.1  257.83    5567  256.57  5848.5  265.56
#Mann= 8 ,-1 , 0
  4442.9      .1       0  4606.7     .16       0  4758.6     .12       0
  4992.7     .07       0  4998.7     .12       0  5187.2     .05       0
  5271.1      .1       0    5567     .16       0
Bank Sta=4992.7,4998.7
XS Rating Curve= 0 ,0
Exp/Cntr=0.3,0.1

Type RM Length L Ch R = 1 ,4429    ,559,559,559
BEGIN DESCRIPTION:
HUTTON MILL BRANCH 10.0
END DESCRIPTION:
XS GIS Cut Line= 3
      3595788.37     10150640.29      3594892.51     10149968.39
        3593736.     10149814.72
#Sta/Elev= 30
  3514.7  268.72  3710.8  274.39  3837.7  271.15  3853.2  271.28  3924.8  265.07
  3947.5     266    3973  271.99  4010.6  272.98  4107.3  274.31  4233.1  271.65
    4742  248.28  4878.8  241.77  4917.4  242.19  4952.1  235.35    4988  234.14
  4995.1   231.8  4997.8   231.3  5001.1   231.8  5025.4   236.9  5078.2  238.24
    5182   233.9  5209.9  236.03  5230.1     240  5250.2  247.79  5280.6  251.44
  5563.4  259.89  5593.3  258.62  5663.9  262.85  5771.5  264.83  5801.2   264.8
#Mann= 12 ,-1 , 0
  3514.7      .1       0  3710.8     .05       0  3837.7     .12       0
  3853.2      .1       0    3973     .05       0  4010.6      .1       0
  4107.3     .16       0    4742     .12       0  4995.1     .07       0
  5001.1     .12       0  5078.2     .05       0  5771.5      .1       0
Bank Sta=4995.1,5001.1
XS Rating Curve= 0 ,0
Exp/Cntr=0.3,0.1

Type RM Length L Ch R = 1 ,3870    ,835,835,835
BEGIN DESCRIPTION:
HUTTON MILL BRANCH 8.0
END DESCRIPTION:
XS GIS Cut Line= 3
      3596236.22     10149957.95      3595439.38     10149338.19
      3593902.91     10149629.86
#Sta/Elev= 30
  3332.3  289.59  3538.2  284.46  3774.4  279.48  4031.4  265.59  4052.2  261.66
  4066.7  263.44  4083.6  260.18  4110.1  256.16  4116.4   259.5  4130.9  257.74
  4151.7  262.04    4216  262.18  4490.5  252.43  4622.1  257.69  4814.2  260.31
  4882.6  256.31  4949.7  250.74  4970.1  242.45  4976.1  235.48  4981.1  236.45
  4997.6  229.77  5000.4  229.27  5003.6  229.77    5021  233.42  5247.5  232.39
  5408.5  237.75  5634.2  248.51  5735.4  254.61  5836.6  256.44  5905.7  256.94
#Mann= 11 ,-1 , 0
  3332.3      .1       0  3538.2     .16       0  4083.6     .12       0
  4622.1     .16       0  4882.6     .12       0  4997.6     .07       0
  5003.6     .12       0  5408.5      .1       0  5634.2     .05       0
  5735.4      .1       0  5836.6     .16       0
Bank Sta=4997.6,5003.6
XS Rating Curve= 0 ,0
Exp/Cntr=0.3,0.1

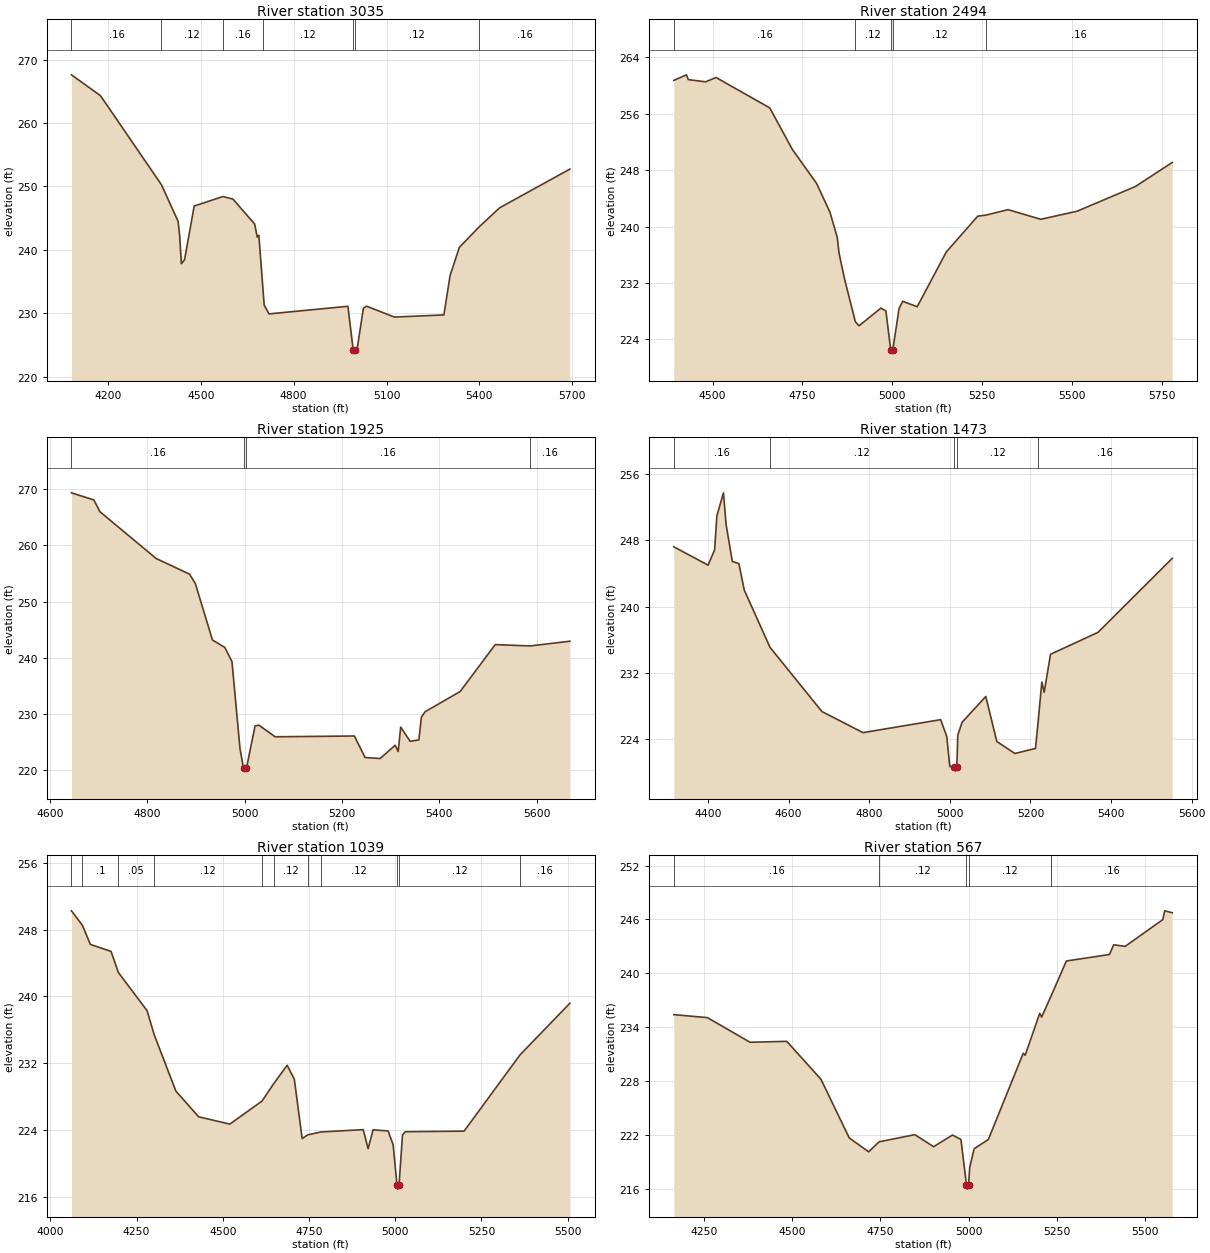
Type RM Length L Ch R = 1 ,3035    ,541,541,541
BEGIN DESCRIPTION:
HUTTON MILL BRANCH 6.0
END DESCRIPTION:
XS GIS Cut Line= 3
      3595507.13     10148864.22      3594886.73     10149014.88
      3593915.18     10148994.47
#Sta/Elev= 30
  4082.2  267.59    4176   264.3    4373  250.27  4426.6  244.52  4431.8  242.19
  4437.3  237.84  4447.5  238.45  4478.7  246.92  4571.6  248.42    4604  248.01
  4673.9  244.09  4682.4  242.03  4687.6  242.31  4701.2  233.59  4704.8  231.31
  4720.4  229.93  4975.3  231.13  4992.3  224.25  4995.1  223.75  4998.3  224.25
  5005.3  224.48  5025.3  230.82  5035.3  231.15  5125.3  229.43  5285.4  229.77
  5305.4  235.99  5335.4  240.42  5399.9  243.67  5465.4  246.64  5692.4  252.74
#Mann= 7 ,-1 , 0
  4082.2     .16       0    4373     .12       0  4571.6     .16       0
  4701.2     .12       0  4992.3     .07       0  4998.3     .12       0
  5399.9     .16       0
Bank Sta=4992.3,4998.3
XS Rating Curve= 0 ,0
Exp/Cntr=0.3,0.1

Type RM Length L Ch R = 1 ,2494    ,569,569,569
BEGIN DESCRIPTION:
HUTTON MILL BRANCH 5.0
END DESCRIPTION:
XS GIS Cut Line= 3
      3595337.95     10148407.26      3595137.94     10148457.27
      3593970.66     10148640.26
#Sta/Elev= 30
  4391.8  260.69    4427  261.48  4432.2   260.8  4480.3  260.49  4509.5   261.1
    4659   256.8  4721.7  250.93  4789.4   246.1  4826.6  242.02  4846.8  238.48
    4852  236.19    4867  232.61  4897.2  226.52  4907.5  225.94  4968.3  228.44
  4982.4  228.05  4995.6  222.57  4998.4  222.07  5001.6  222.57  5018.9  228.36
    5029  229.41  5069.5  228.64  5150.5   236.4    5238  241.46  5262.3  241.63
  5322.5  242.39  5413.6  241.02  5514.9  242.17  5676.8  245.66  5779.5  249.07
#Mann= 5 ,-1 , 0
  4391.8     .16       0  4897.2     .12       0  4995.6     .07       0
  5001.6     .12       0  5262.3     .16       0
Bank Sta=4995.6,5001.6
XS Rating Curve= 0 ,0
Exp/Cntr=0.3,0.1

Type RM Length L Ch R = 1 ,1925    ,452,452,452
BEGIN DESCRIPTION:
HUTTON MILL BRANCH 4.0
END DESCRIPTION:
XS GIS Cut Line= 3
      3595116.51     10147942.34      3594742.11     10148041.64
      3594122.76     10148186.89
#Sta/Elev= 30
  4644.4   269.4  4690.3  268.13    4703  266.02  4818.4  257.67  4886.9  254.88
  4898.8   253.2  4933.9  243.13  4959.3   241.8    4974  239.26  4990.4   223.8
  4997.7  220.22  5000.5  219.72  5003.7  220.22  5021.4  227.79  5029.2  227.93
  5062.6  225.85  5225.3  225.99  5247.4  222.15  5278.3  221.97  5309.1  224.34
  5315.3  223.22  5320.5  227.58  5339.9  225.04  5357.8  225.29  5362.9  229.34
  5370.7  230.33  5442.6  233.93  5514.5   242.3  5586.5  242.07  5667.9  242.91
#Mann= 4 ,-1 , 0
  4644.4     .16       0  4997.7     .07       0  5003.7     .16       0
  5586.5     .16       0
Bank Sta=4997.7,5003.7
XS Rating Curve= 0 ,0
Exp/Cntr=0.3,0.1

Type RM Length L Ch R = 1 ,1473    ,434,434,434
BEGIN DESCRIPTION:
HUTTON MILL BRANCH 3.0
END DESCRIPTION:
XS GIS Cut Line= 3
      3595116.45     10147359.03      3594492.11     10147691.64
      3594034.32     10147957.29
#Sta/Elev= 30
  4315.1  247.24  4400.1  245.02  4416.4  246.86    4422  250.98  4438.3  253.76
  4444.7  249.98  4460.3  245.47  4476.6  245.21    4490     242  4553.8  235.09
  4682.6  227.33  4784.6  224.78  4977.2  226.35  4992.4  224.31  4999.9  220.69
  5011.4  220.63  5014.1  220.13  5017.4  220.63  5019.7  224.47  5030.4  226.03
  5089.2  229.15  5116.5  223.72  5161.3  222.26  5212.5  222.87  5219.2  226.16
  5228.3  230.89  5234.1  229.65  5249.8  234.25  5367.4  236.89  5551.8  245.84
#Mann= 5 ,-1 , 0
  4315.1     .16       0  4553.8     .12       0  5011.4     .07       0
  5017.4     .12       0  5219.2     .16       0
Bank Sta=5011.4,5017.4
XS Rating Curve= 0 ,0
Exp/Cntr=0.3,0.1

Type RM Length L Ch R = 1 ,1039    ,472,472,472
BEGIN DESCRIPTION:
HUTTON MILL BRANCH 2.0
END DESCRIPTION:
XS GIS Cut Line= 3
      3594992.13     10146991.64      3594404.26      10147167.2
      3593898.17     10147827.17
#Sta/Elev= 30
  4061.2  250.25  4092.8  248.53  4116.1  246.23    4176  245.39  4197.1  242.88
  4280.4   238.3  4301.3   235.4  4363.9  228.68  4429.9   225.6  4520.4  224.72
  4613.9  227.49  4647.4  229.55  4686.6  231.77  4707.4  230.09  4730.1  222.99
  4745.9  223.43  4784.1  223.78  4907.2  224.06  4921.3  221.78  4935.8  224.04
  4979.4   223.9  4993.9  222.25    5005  217.44  5007.7  216.94    5011  217.44
    5021  223.42  5029.2  223.81  5199.6  223.88  5361.8  233.01  5506.4  239.19
#Mann= 11 ,-1 , 0
  4061.2     .16       0  4092.8      .1       0  4197.1     .05       0
  4301.3     .12       0  4613.9     .16       0  4647.4     .12       0
  4745.9     .16       0  4784.1     .12       0    5005     .07       0
    5011     .12       0  5361.8     .16       0
Bank Sta=5005,5011
XS Rating Curve= 0 ,0
Exp/Cntr=0.3,0.1

Type RM Length L Ch R = 1 ,567     ,0,0,0
BEGIN DESCRIPTION:
HUTTON MILL BRANCH 1.0
END DESCRIPTION:
XS GIS Cut Line= 3
      3594642.07     10146891.65      3593842.11     10147191.64
      3593329.99     10147416.32
#Sta/Elev= 30
  4163.8  235.41    4259  235.08    4380  232.34  4484.2  232.44  4581.2  228.22
  4661.3   221.7  4716.5  220.15  4745.8  221.26  4847.3  222.06  4900.7  220.72
  4954.1  222.02  4978.1  221.53  4993.8   216.5  4996.6     216  4999.8   216.5
    5003  218.39  5015.5  220.49  5055.9  221.52  5154.9  231.12  5160.3  230.89
  5201.6  235.56  5207.1  235.14  5234.4  237.54  5277.2  241.38  5399.4   242.1
  5411.3  243.18    5444  243.01  5550.6  245.98    5556  246.96  5577.4  246.75
#Mann= 5 ,-1 , 0
  4163.8     .16       0  4745.8     .12       0  4993.8     .07       0
  4999.8     .12       0  5234.4     .16       0
Bank Sta=4993.8,4999.8
XS Rating Curve= 0 ,0
Exp/Cntr=0.3,0.1

Chan Stop Cuts=-1
Use User Specified Reach Order=0
Composite Channel Slope=5