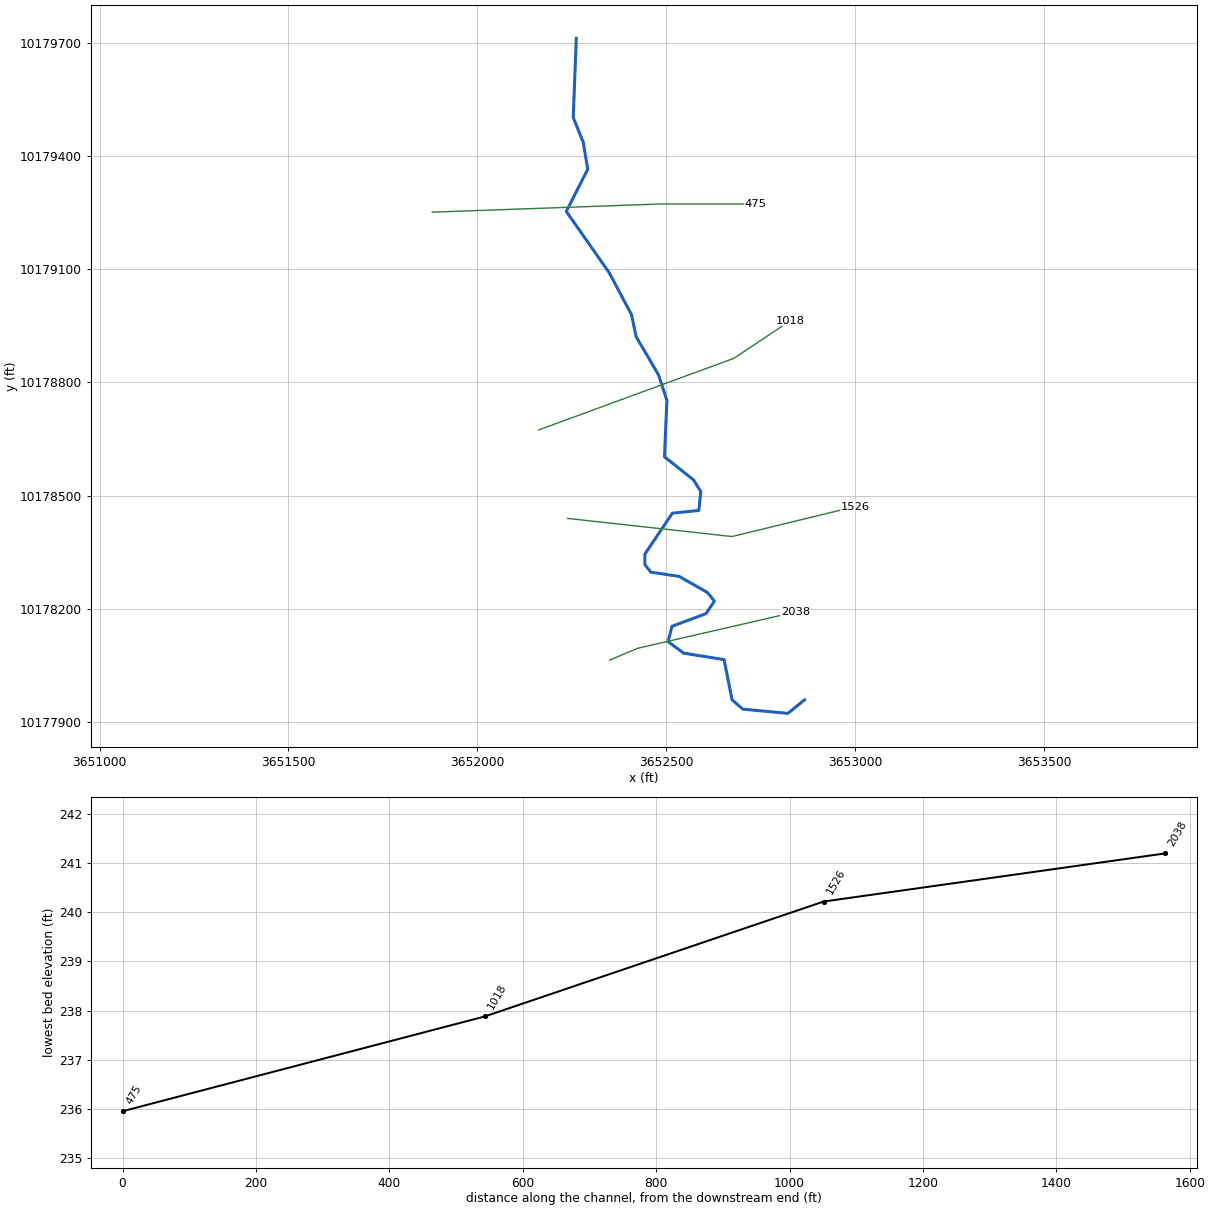
--- JACK BRANCH.prj (project) ---

Proj Title=JACK BRANCH Base Level Engineering
Current Plan=p01
Default Exp/Contr=0.3,0.1
English Units
Geom File=g01
Flow File=f01
Plan File=p01
Y Axis Title=Elevation
X Axis Title(PF)=Main Channel Distance
X Axis Title(XS)=Station
BEGIN DESCRIPTION:
JACK BRANCH
END DESCRIPTION:
DSS Export Rating Curves= 0
DSS Export Rating Curve Sorted= 0
DSS Export Volume Flow Curves= 0
DXF OffsetX= 0
DXF OffsetY= 0
DXF ScaleX= 1
DXF ScaleY= 10

--- JACK BRANCH.p01 (plan) ---

Plan Title=Multiple Run
Short Identifier=Multiple
Geom File=g01
Flow File=f01
Subcritical Flow
K Sum by GR= 0
Std Step Tol= 0.01
Critical Tol= 0.01
Num of Std Step Trials= 20
Max Error Tol= 0.3
Flow Tol Ratio= 0.001
Split Flow NTrial= 30
Split Flow Tol= 0.02
Split Flow Ratio= 0.02
Log Output Level= 0
Friction Slope Method= 1
Unsteady Friction Slope Method= 2
Unsteady Bridges Friction Slope Method= 1
Parabolic Critical Depth
Global Vel Dist=  1 , 1 , 1
Global Log Level= 0
CheckData=True
Encroach Param= -1, 0, 0, 0
BEGIN DESCRIPTION:
Multiple Run
END DESCRIPTION:

--- JACK BRANCH.f01 (steady flow) ---

Flow Title=Multiple
Number of Profiles=7
Profile Names=10-year,25-year,50-year,1pct_min,100-year,1pct_plu,500-year
River Rch & RM= JACK BRANCH,Reach-1,2038
     705     959    1168    1044    1412    1909    2064
Boundary for River Rch & Prof#=JACK BRANCH,Reach-1,1
Up Type=0
Dn Type=3
Dn Slope=0.005
Boundary for River Rch & Prof#=JACK BRANCH,Reach-1,2
Up Type=0
Dn Type=3
Dn Slope=0.005
Boundary for River Rch & Prof#=JACK BRANCH,Reach-1,3
Up Type=0
Dn Type=3
Dn Slope=0.005
Boundary for River Rch & Prof#=JACK BRANCH,Reach-1,4
Up Type=0
Dn Type=3
Dn Slope=0.005
Boundary for River Rch & Prof#=JACK BRANCH,Reach-1,5
Up Type=0
Dn Type=3
Dn Slope=0.005
Boundary for River Rch & Prof#=JACK BRANCH,Reach-1,6
Up Type=0
Dn Type=3
Dn Slope=0.005
Boundary for River Rch & Prof#=JACK BRANCH,Reach-1,7
Up Type=0
Dn Type=3
Dn Slope=0.005

--- JACK BRANCH.g01 (geometry) ---

Geom Title=Existing Conditions
Program Version=4.10

River Reach=JACK BRANCH     ,Reach-1
Reach XY= 30
      3652866.38      10177958.9       3652822.1     10177923.13
      3652703.03     10177934.38      3652674.58     10177958.74
      3652653.26     10178065.56      3652546.09     10178082.74
      3652505.04     10178113.27      3652515.36     10178153.78
      3652605.37      10178187.5      3652627.75     10178220.51
      3652609.22     10178243.47      3652534.47     10178286.03
       3652459.2     10178297.31      3652443.55     10178317.26
       3652443.7     10178345.24      3652516.45     10178453.54
      3652586.37     10178460.78      3652591.63     10178510.82
      3652572.56     10178541.59      3652495.51     10178602.97
      3652501.96     10178752.66      3652479.47     10178820.54
      3652420.56       10178921.        3652408.     10178979.94
      3652349.36     10179090.51      3652235.63     10179253.05
      3652292.34     10179364.75      3652280.53     10179435.96
      3652253.99     10179502.06      3652262.11     10179711.64

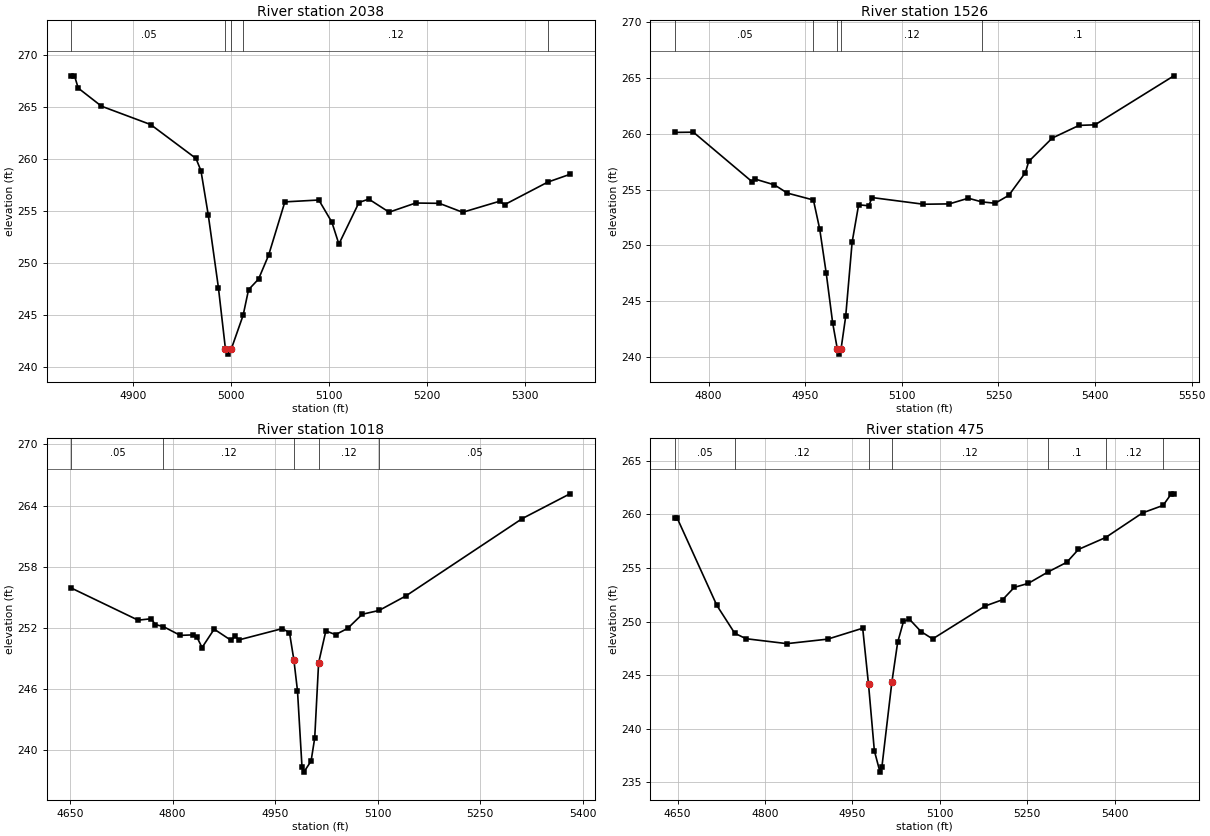
Type RM Length L Ch R = 1 ,2038    ,512,512,512
BEGIN DESCRIPTION:
JACK BRANCH 4.0
END DESCRIPTION:
XS GIS Cut Line= 3
      3652350.14      10178064.2      3652424.71     10178095.65
      3652842.08     10178191.64
#Sta/Elev= 30
  4836.9  267.98    4840  267.98  4843.8   266.8  4867.5  265.06  4917.8  263.29
  4964.1  260.03  4969.2  258.84  4976.7  254.56    4987  247.61  4994.2   241.7
    4997   241.2  5000.2   241.7  5012.3  244.95  5017.8   247.4    5028  248.42
  5038.3  250.72  5054.9  255.85  5089.6  256.03  5102.9   253.9  5110.1  251.79
  5130.6  255.79  5140.6  256.12  5161.4  254.86  5188.5  255.74  5212.7  255.71
  5236.5  254.85  5274.2  255.91  5279.3  255.58  5323.4  257.75  5346.1   258.5
#Mann= 5 ,-1 , 0
  4836.9     .05       0  4994.2     .03       0  5000.2     .05       0
  5012.3     .12       0  5323.4      .1       0
Bank Sta=4994.2,5000.2
XS Rating Curve= 0 ,0
Exp/Cntr=0.3,0.1

Type RM Length L Ch R = 1 ,1526    ,508,508,508
BEGIN DESCRIPTION:
JACK BRANCH 3.0
END DESCRIPTION:
XS GIS Cut Line= 3
      3652239.35     10178439.69      3652674.36     10178391.64
      3653001.15     10178471.24
#Sta/Elev= 30
  4748.4  260.13  4776.3  260.15  4867.1  255.72  4872.1  255.94  4902.1  255.42
  4922.2  254.68  4962.7  254.06  4972.5  251.44  4982.6  247.48  4992.6  243.02
  4999.7  240.72  5002.4  240.22  5005.7  240.72  5012.8   243.6  5022.8  250.27
  5032.9  253.63  5048.7  253.54  5053.7  254.28  5133.5  253.68  5173.7  253.71
  5203.2  254.22  5224.1  253.89  5244.9  253.77  5266.1  254.48  5291.8  256.51
    5297  257.52  5333.5  259.62  5375.2  260.76  5399.9  260.81  5522.4  265.21
#Mann= 5 ,-1 , 0
  4748.4     .05       0  4962.7     .12       0  4999.7     .07       0
  5005.7     .12       0  5224.1      .1       0
Bank Sta=4999.7,5005.7
XS Rating Curve= 0 ,0
Exp/Cntr=0.3,0.1

Type RM Length L Ch R = 1 ,1018    ,543,543,543
BEGIN DESCRIPTION:
JACK BRANCH 2.0
END DESCRIPTION:
XS GIS Cut Line= 3
      3652162.68     10178674.09      3652679.18     10178863.77
      3652828.18      10178963.1
#Sta/Elev= 30
  4652.1  255.91  4749.6  252.77  4768.7  252.91  4774.8  252.34  4786.6  252.14
  4811.3  251.28  4830.4  251.33  4835.7   251.1  4843.2  250.09  4860.9  251.89
  4885.9  250.78  4891.4  251.21  4896.7  250.83  4960.4  251.94  4971.1  251.55
  4977.5  248.88  4982.8  245.85  4989.4  238.38  4992.1  237.88  5002.7  238.97
    5008  241.22  5013.7  248.59  5024.3  251.72  5038.5  251.35  5056.3  251.97
  5077.6  253.35  5102.1  253.72  5141.5  255.15  5311.8  262.73  5381.4  265.15
#Mann= 5 ,-1 , 0
  4652.1     .05       0  4786.6     .12       0  4977.5     .07       0
  5013.7     .12       0  5102.1     .05       0
Bank Sta=4977.5,5013.7
XS Rating Curve= 0 ,0
Exp/Cntr=0.3,0.1

Type RM Length L Ch R = 1 ,475     ,0,0,0
BEGIN DESCRIPTION:
JACK BRANCH 1.0
END DESCRIPTION:
XS GIS Cut Line= 3
      3651880.94     10179251.12      3652485.95     10179272.78
      3652735.95     10179272.78
#Sta/Elev= 30
  4646.1  259.65  4649.2  259.65  4717.3   251.5  4747.9  248.91  4767.3   248.4
  4837.4  247.94  4907.4  248.36  4967.5  249.38  4977.5  244.14  4987.5  237.95
  4997.2  235.95  5000.5  236.45  5017.5  244.32  5027.5  248.06  5037.5  250.01
  5047.5  250.23  5067.5  249.07  5087.5  248.38  5177.6  251.45  5207.6  252.04
  5227.6  253.19  5251.5  253.56  5285.6  254.63  5317.7  255.53  5337.7  256.73
  5384.3  257.84  5447.7  260.14    5483  260.84  5497.1  261.92  5501.5  261.92
#Mann= 7 ,-1 , 0
  4646.1     .05       0  4747.9     .12       0  4977.5     .05       0
  5017.5     .12       0  5285.6      .1       0  5384.3     .12       0
    5483     .05       0
Bank Sta=4977.5,5017.5
XS Rating Curve= 0 ,0
Exp/Cntr=0.3,0.1

Chan Stop Cuts=-1
Use User Specified Reach Order=0
Composite Channel Slope=5