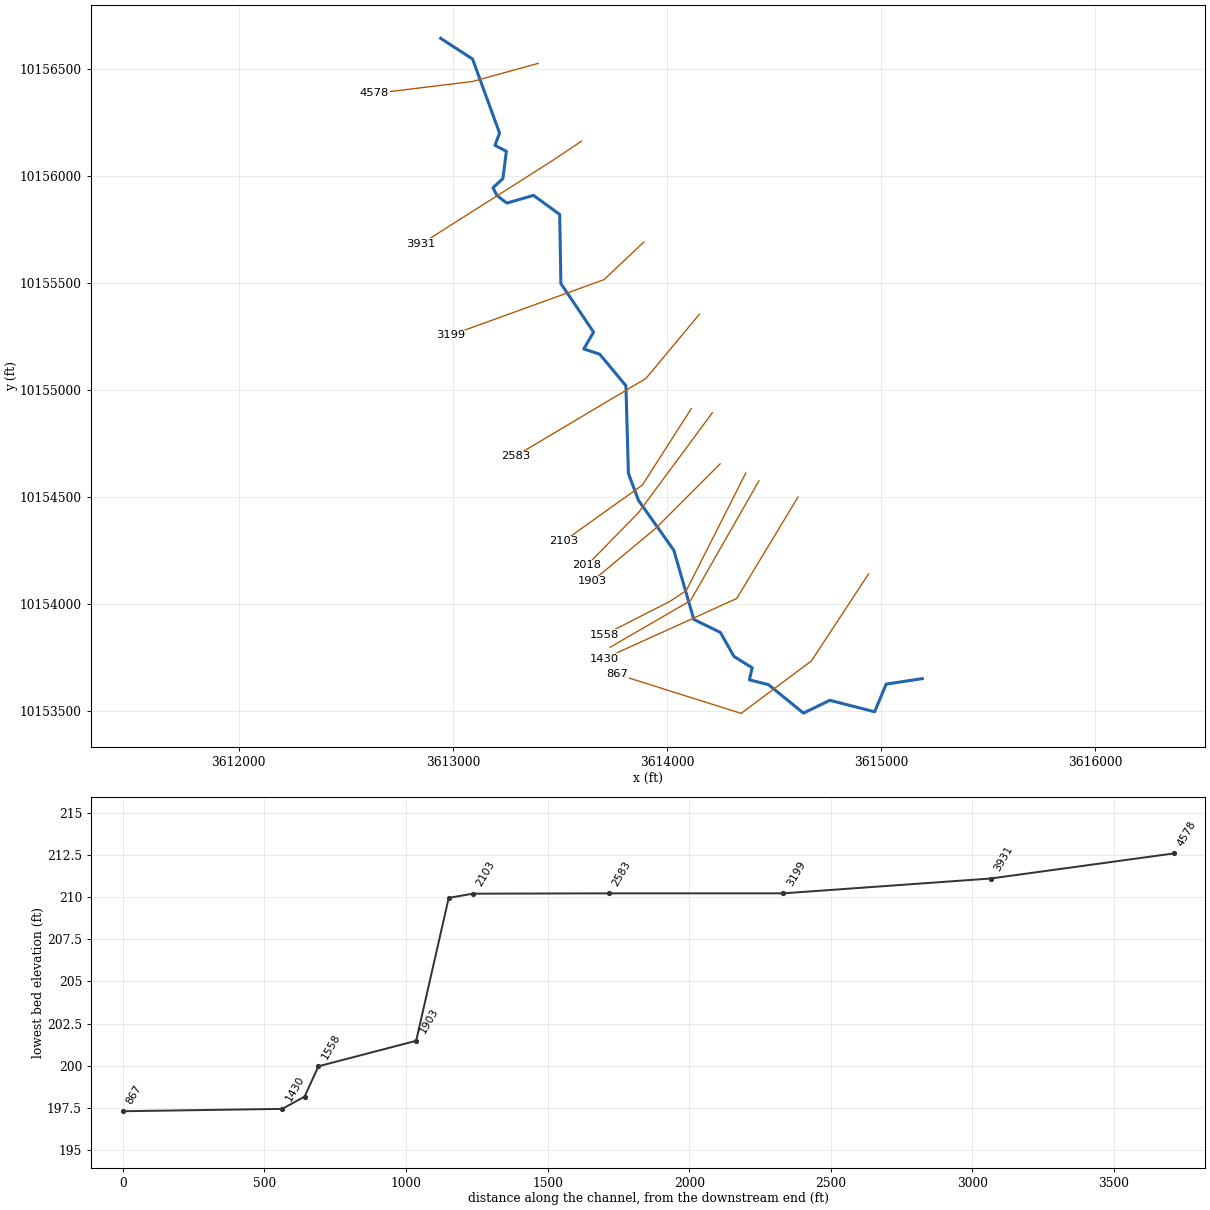
--- JONES CREEK TRIB 1.prj (project) ---

Proj Title=JONES CREEK TRIB 1 Base Level Engineering
Current Plan=p01
Default Exp/Contr=0.3,0.1
English Units
Geom File=g01
Flow File=f01
Plan File=p01
Y Axis Title=Elevation
X Axis Title(PF)=Main Channel Distance
X Axis Title(XS)=Station
BEGIN DESCRIPTION:
JONES CREEK TRIB 1
END DESCRIPTION:
DSS Export Rating Curves= 0
DSS Export Rating Curve Sorted= 0
DSS Export Volume Flow Curves= 0
DXF OffsetX= 0
DXF OffsetY= 0
DXF ScaleX= 1
DXF ScaleY= 10

--- JONES CREEK TRIB 1.p01 (plan) ---

Plan Title=Multiple Run
Short Identifier=Multiple
Geom File=g01
Flow File=f01
Subcritical Flow
K Sum by GR= 0
Std Step Tol= 0.01
Critical Tol= 0.01
Num of Std Step Trials= 20
Max Error Tol= 0.3
Flow Tol Ratio= 0.001
Split Flow NTrial= 30
Split Flow Tol= 0.02
Split Flow Ratio= 0.02
Log Output Level= 0
Friction Slope Method= 1
Unsteady Friction Slope Method= 2
Unsteady Bridges Friction Slope Method= 1
Parabolic Critical Depth
Global Vel Dist=  1 , 1 , 1
Global Log Level= 0
CheckData=True
Encroach Param= -1, 0, 0, 0
BEGIN DESCRIPTION:
Multiple Run
END DESCRIPTION:

--- JONES CREEK TRIB 1.f01 (steady flow) ---

Flow Title=Multiple
Number of Profiles=7
Profile Names=10-year,25-year,50-year,1pct_min,100-year,1pct_plu,500-year
River Rch & RM= JONES CREEK TRIB,Reach-1,4578
     391     513     609     531     719     972    1001
Boundary for River Rch & Prof#=JONES CREEK TRIB,Reach-1,1
Up Type=0
Dn Type=3
Dn Slope=0.005
Boundary for River Rch & Prof#=JONES CREEK TRIB,Reach-1,2
Up Type=0
Dn Type=3
Dn Slope=0.005
Boundary for River Rch & Prof#=JONES CREEK TRIB,Reach-1,3
Up Type=0
Dn Type=3
Dn Slope=0.005
Boundary for River Rch & Prof#=JONES CREEK TRIB,Reach-1,4
Up Type=0
Dn Type=3
Dn Slope=0.005
Boundary for River Rch & Prof#=JONES CREEK TRIB,Reach-1,5
Up Type=0
Dn Type=3
Dn Slope=0.005
Boundary for River Rch & Prof#=JONES CREEK TRIB,Reach-1,6
Up Type=0
Dn Type=3
Dn Slope=0.005
Boundary for River Rch & Prof#=JONES CREEK TRIB,Reach-1,7
Up Type=0
Dn Type=3
Dn Slope=0.005

--- JONES CREEK TRIB 1.g01 (geometry) ---

Geom Title=Existing Conditions
Program Version=4.10

River Reach=JONES CREEK TRIB,Reach-1
Reach XY= 30
       3612942.8     10156643.08      3613091.84     10156546.34
      3613217.95     10156200.11      3613196.25     10156143.14
      3613249.71     10156115.62      3613233.42     10155988.21
      3613187.22     10155944.78      3613205.87     10155908.57
      3613251.86     10155873.49      3613376.59     10155909.57
      3613498.86      10155820.3      3613504.38     10155497.58
      3613657.16     10155270.52      3613611.24      10155191.9
      3613685.73     10155167.62      3613808.17     10155020.01
      3613819.85     10154610.72      3613866.72     10154484.85
      3614032.01      10154251.6       3614125.4     10153928.43
      3614249.54     10153867.66       3614312.9     10153755.68
      3614397.97     10153702.73      3614384.95     10153646.31
      3614474.36     10153623.74      3614637.56     10153490.93
      3614760.82     10153550.82      3614970.02       10153497.
      3615023.84     10153626.34      3615192.56       10153652.

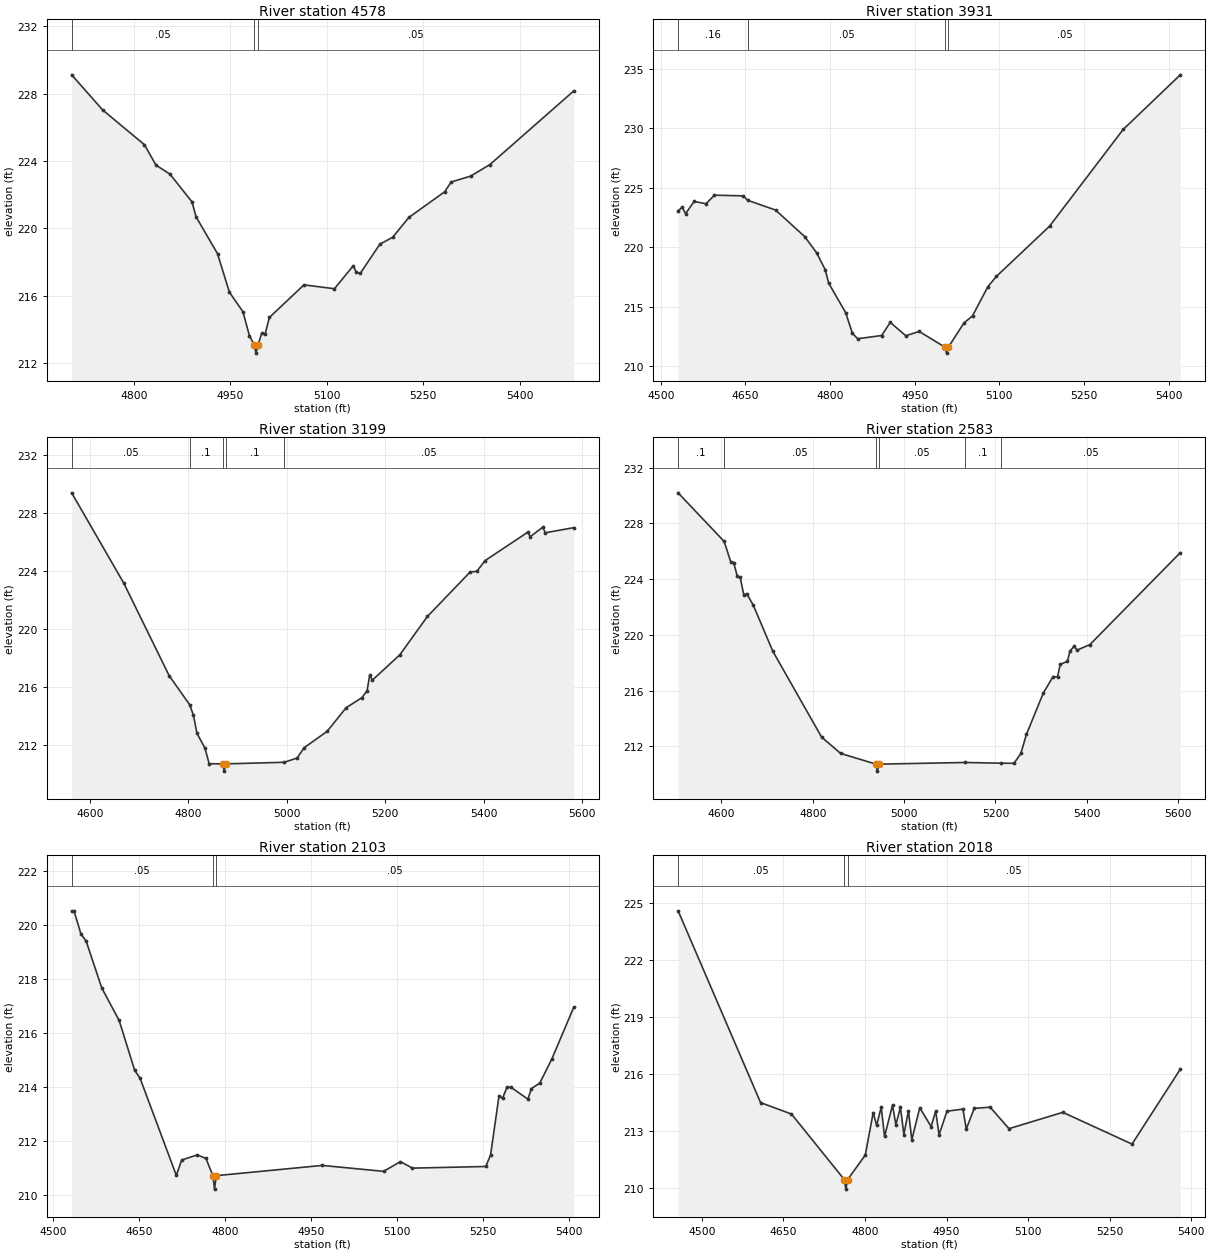
Type RM Length L Ch R = 1 ,4578    ,647,647,647
BEGIN DESCRIPTION:
JONES CREEK TRIB 1 9.0
END DESCRIPTION:
XS GIS Cut Line= 3
      3613398.44     10156526.16      3613092.11     10156441.64
       3612632.8     10156385.53
#Sta/Elev= 30
  4703.5  229.11  4751.6  227.03  4816.7  224.96  4834.6  223.75  4856.3  223.22
  4890.6  221.57  4896.8  220.69  4930.2   218.5  4948.7  216.21  4969.7  215.06
  4979.8  213.63  4987.2   213.1  4989.9   212.6  4993.2   213.1  4998.9  213.77
  5004.1  213.73  5010.9  214.72  5064.6  216.65  5111.9  216.42  5141.1  217.78
  5146.1  217.39  5152.2  217.34  5182.5  219.06  5202.6  219.48  5227.6  220.65
  5283.2  222.17  5293.3  222.75  5323.5   223.1  5353.7  223.79    5484  228.16
#Mann= 3 ,-1 , 0
  4703.5     .05       0  4987.2     .03       0  4993.2     .05       0
Bank Sta=4987.2,4993.2
XS Rating Curve= 0 ,0
Exp/Cntr=0.3,0.1

Type RM Length L Ch R = 1 ,3931    ,732,732,732
BEGIN DESCRIPTION:
JONES CREEK TRIB 1 8.0
END DESCRIPTION:
XS GIS Cut Line= 3
      3613600.47      10156162.5      3613450.44     10156062.48
      3612851.57     10155682.42
#Sta/Elev= 30
  4530.8  223.07  4538.1  223.36  4544.1  222.83  4559.1  223.85  4580.2  223.66
  4595.2  224.38  4646.3  224.32    4654  223.95  4703.4  223.13    4755   220.9
  4776.1  219.54  4791.4  218.12  4797.3  217.01  4827.6  214.51  4839.7  212.76
    4849  212.32  4891.3  212.59  4906.6  213.69  4934.2  212.57  4957.9  212.93
  5003.5  211.61  5006.3  211.11  5009.5  211.61  5037.1  213.64  5052.3  214.24
  5079.4  216.68  5094.7  217.56  5188.7  221.77  5319.2   229.9  5420.4  234.49
#Mann= 4 ,-1 , 0
  4530.8     .16       0    4654     .05       0  5003.5     .03       0
  5009.5     .05       0
Bank Sta=5003.5,5009.5
XS Rating Curve= 0 ,0
Exp/Cntr=0.3,0.1

Type RM Length L Ch R = 1 ,3199    ,616,616,616
BEGIN DESCRIPTION:
JONES CREEK TRIB 1 6.0
END DESCRIPTION:
XS GIS Cut Line= 3
       3613892.1     10155691.64      3613705.71     10155515.74
      3612987.01     10155255.34
#Sta/Elev= 30
  4562.7  229.41  4668.9  223.17  4760.7  216.82  4802.5  214.81  4810.2  214.09
  4817.4  212.83  4833.5  211.83  4842.2  210.74  4869.9  210.73  4872.6  210.23
  4875.9  210.73  4994.7  210.84  5020.7  211.13  5035.5  211.85    5082  212.97
  5120.6   214.6  5152.5  215.29  5163.2  215.77  5168.5  216.85  5173.9   216.5
  5229.8  218.25  5285.8  220.89  5372.3  223.94  5386.5  224.01    5403  224.74
  5489.5  226.69  5494.9  226.39  5520.2  227.04  5525.5  226.66  5583.4  227.01
#Mann= 5 ,-1 , 0
  4562.7     .05       0  4802.5      .1       0  4869.9     .03       0
  4875.9      .1       0  4994.7     .05       0
Bank Sta=4869.9,4875.9
XS Rating Curve= 0 ,0
Exp/Cntr=0.3,0.1

Type RM Length L Ch R = 1 ,2583    ,480,480,480
BEGIN DESCRIPTION:
JONES CREEK TRIB 1 5.0
END DESCRIPTION:
XS GIS Cut Line= 3
      3614151.49     10155354.15      3613901.48     10155054.14
      3613292.08     10154691.63
#Sta/Elev= 30
  4505.1  230.19    4606   226.7  4620.2  225.25  4626.7  225.19  4634.5  224.23
    4641  224.13  4648.8  222.88  4655.3  222.95  4669.6  222.14  4712.6  218.82
  4819.3  212.67    4861   211.5  4938.4  210.73  4941.2  210.23  4944.4  210.73
    5133  210.85  5212.7   210.8  5240.5  210.79  5255.6   211.5  5267.7  212.86
  5304.7  215.83  5326.1  217.01  5335.9  216.99  5341.7  217.89  5357.3   218.1
  5363.2  218.83    5372  219.19  5378.8  218.91  5406.9  219.31  5604.7   225.9
#Mann= 6 ,-1 , 0
  4505.1      .1       0    4606     .05       0  4938.4    .033       0
  4944.4     .05       0    5133      .1       0  5212.7     .05       0
Bank Sta=4938.4,4944.4
XS Rating Curve= 0 ,0
Exp/Cntr=0.3,0.1

Type RM Length L Ch R = 1 ,2103    ,85,85,85
BEGIN DESCRIPTION:
Mapping XS da4c3d75
END DESCRIPTION:
XS GIS Cut Line= 3
      3614113.65      10154913.6      3613885.17     10154556.39
      3613517.07     10154293.45
#Sta/Elev= 30
  4532.2  220.54  4536.3  220.54  4548.3  219.69  4557.6  219.41  4584.7  217.68
  4615.1  216.47  4642.2  214.62  4651.5  214.33  4714.9  210.72  4724.2  211.29
  4751.3  211.48  4766.5  211.35  4778.7  210.71  4781.5  210.21  4784.7  210.71
  4969.6  211.09  5076.5  210.87    5106  211.23  5126.9  210.99  5254.9  211.05
  5263.3  211.48    5278  213.67  5284.2  213.58  5291.8  213.99  5298.9  213.99
  5328.4  213.55  5334.6  213.94  5349.3  214.15  5370.2  215.04  5408.6  216.97
#Mann= 3 ,-1 , 0
  4532.2     .05       0  4778.7    .033       0  4784.7     .05       0
Bank Sta=4778.7,4784.7
XS Rating Curve= 0 ,0
Exp/Cntr=0.3,0.1

Type RM Length L Ch R = 1 ,2018    ,115,115,115
BEGIN DESCRIPTION:
Mapping XS 2f740d4e
END DESCRIPTION:
XS GIS Cut Line= 3
      3614211.56     10154893.66      3613867.04     10154427.65
      3613626.48     10154181.66
#Sta/Elev= 30
  4456.4   224.6  4608.1  214.51  4664.9  213.91  4762.1  210.46  4764.9  209.96
  4768.1  210.46  4800.6  211.75  4815.2  213.99  4821.5  213.31  4829.9  214.27
  4836.1  212.73  4850.7  214.38  4856.9  213.34  4865.3  214.27  4871.6  212.83
    4880  214.08  4886.2  212.56  4900.8  214.24  4921.7  213.25  4930.1  214.07
  4936.3  212.82  4950.9  214.06  4980.2  214.17  4986.4  213.12    5001  214.21
  5030.3  214.27  5064.9  213.14  5163.9     214  5291.2  212.33    5380  216.27
#Mann= 3 ,-1 , 0
  4456.4     .05       0  4762.1    .033       0  4768.1     .05       0
Bank Sta=4762.1,4768.1
XS Rating Curve= 0 ,0
Exp/Cntr=0.3,0.1

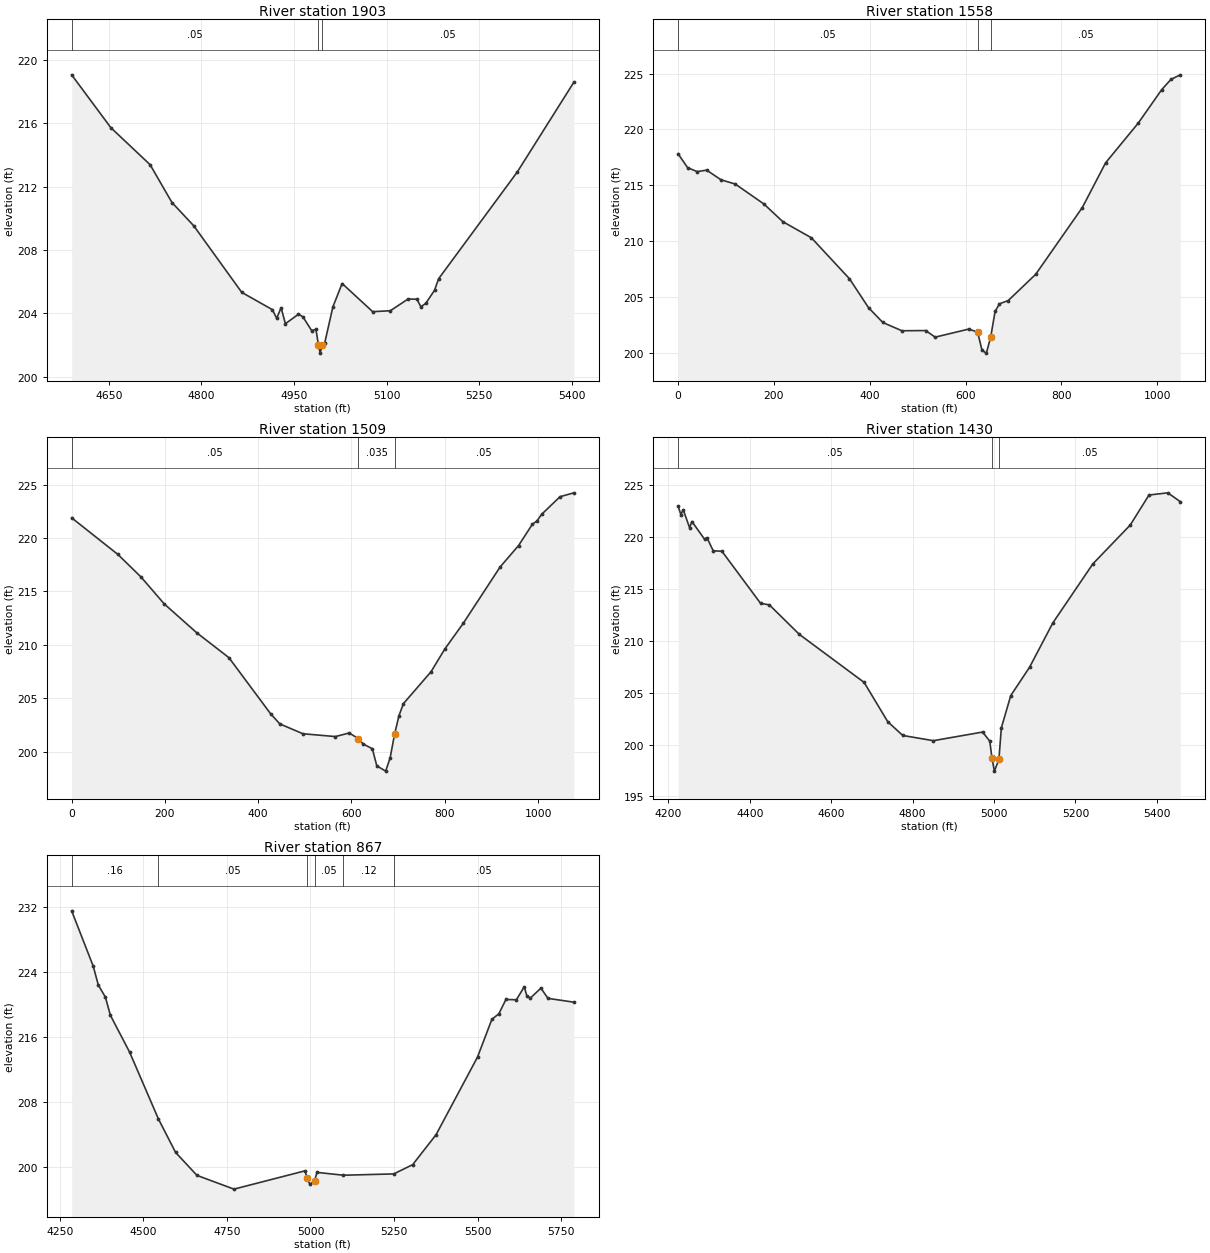
Type RM Length L Ch R = 1 ,1903    ,345,345,345
BEGIN DESCRIPTION:
JONES CREEK TRIB 1 3.0
END DESCRIPTION:
XS GIS Cut Line= 3
      3614248.35     10154655.17      3613948.36     10154355.18
      3613649.25     10154105.93
#Sta/Elev= 30
  4589.9  219.07  4653.4  215.73    4717  213.39  4752.4     211  4787.7  209.53
  4865.5  205.32    4915  204.23  4922.1  203.68  4929.2  204.35  4936.2  203.34
  4957.4  203.94  4964.5  203.78  4978.6  202.91  4985.7  202.98  4989.8  201.98
  4992.5  201.48  4995.8  201.98  4999.9  202.12  5013.1   204.4  5028.1  205.88
  5077.6   204.1  5106.2  204.16  5134.9   204.9  5149.2  204.89  5155.7  204.41
  5163.5  204.62  5177.8  205.45  5184.4  206.18  5311.9  212.93  5403.5   218.6
#Mann= 3 ,-1 , 0
  4589.9     .05       0  4989.8     .03       0  4995.8     .05       0
Bank Sta=4989.8,4995.8
XS Rating Curve= 0 ,0
Exp/Cntr=0.3,0.1

Type RM Length L Ch R = 1 ,1558    ,49,49,49
XS GIS Cut Line= 4
     3614367.947      10154612.2     3614090.169    10154063.155
     3614014.214    10154013.242     3613706.054    10153855.906
#Sta/Elev= 30
       0217.8125 19.8738216.570539.74759216.222659.62139216.353389.43209215.4893
119.2428215.1086178.8642213.3295218.6118211.7389278.2332 210.294357.7284206.6256
 397.476204.0357427.2867202.7113467.0342201.9713516.7188201.9881536.5925201.3977
606.1508202.1154625.2036201.8577634.3196200.2169643.4355199.9675652.5514201.4267
661.6674203.7049670.7833204.3849689.0151204.6744  746.22207.0156843.6525212.9993
892.3687217.0119960.5715220.57021009.288223.55231028.774  224.481048.261224.8878
#Mann= 3 , 0 , 0
       0     .05       0625.2036    .035       0652.5514     .05       0
Bank Sta=625.2036,652.5514
XS Rating Curve= 0 ,0
Exp/Cntr=0.3,0.1

Type RM Length L Ch R = 1 ,1509    ,79,79,79
XS GIS Cut Line= 4
     3614429.687    10154576.094     3614110.677      10154017.5
     3614071.614    10153994.063     3613734.374     10153798.75
#Sta/Elev= 30
       0221.892999.19798218.4623 148.797216.3479 198.396213.8351267.8345211.1404
337.2731208.7926426.5513203.5414446.3909202.5894495.9899201.6673565.4285201.4041
595.1879201.7408615.0275201.2061624.9472200.7118644.7868200.2634654.2935198.6651
673.3068198.1669682.8134199.3909692.3201201.6095701.8267  203.36711.3334204.4875
770.5967207.4784800.2285  209.61839.7374212.0168918.7552217.2901958.2642219.2956
987.8959221.2911997.7731221.6028 1007.65222.21711047.159223.87071076.791224.2337
#Mann= 3 , 0 , 0
       0     .05       0615.0275    .035       0692.3201     .05       0
Bank Sta=615.0275,692.3201
XS Rating Curve= 0 ,0
Exp/Cntr=0.3,0.1

Type RM Length L Ch R = 1 ,1430    ,563,563,563
BEGIN DESCRIPTION:
JONES CREEK TRIB 1 2.0
END DESCRIPTION:
XS GIS Cut Line= 3
      3614611.96     10154500.12      3614325.51     10154026.16
      3613706.37     10153745.21
#Sta/Elev= 30
  4223.9  222.94  4230.6  222.13  4236.5  222.59    4252  220.87  4257.8  221.46
  4288.8  219.76  4294.7   219.9  4310.2  218.64  4331.5   218.6  4426.6  213.58
    4448  213.44  4521.7   210.6  4680.8  205.98    4739  202.19  4775.9  200.87
    4851  200.37  4971.9   201.2  4989.5  200.33    4995  198.69  5000.8  197.44
    5012  198.57    5018  201.61  5041.1  204.71  5087.3  207.44  5144.4   211.7
  5242.7  217.38  5334.6  221.12  5380.7  224.01  5426.9  224.22  5457.6  223.37
#Mann= 3 , 0 , 0
  4223.9     .05       0    4995    .035       0    5012     .05       0
Bank Sta=4995,5012
XS Rating Curve= 0 ,0
Exp/Cntr=0.3,0.1

Type RM Length L Ch R = 1 ,867     ,0,0,0
BEGIN DESCRIPTION:
JONES CREEK TRIB 1 1.0
END DESCRIPTION:
XS GIS Cut Line= 4
      3614942.08      10154141.6      3614674.46     10153734.49
      3614346.34      10153489.7      3613768.17     10153672.01
#Sta/Elev= 30
  4285.4  231.51  4350.1  224.69  4365.2  222.38  4386.3  220.91  4401.4  218.66
  4458.6  214.16  4545.1  205.92  4596.5  201.81  4660.4  198.99  4771.1   197.3
  4983.9  199.55  4990.1  198.63  4998.5  197.87  5012.6  198.33  5019.3  199.36
  5098.6  199.01  5249.3  199.17  5305.9  200.31  5375.9  203.99    5500  213.54
  5542.9  218.17  5563.9  218.86  5584.9  220.61  5616.3  220.58  5639.9  222.18
  5647.8  221.02  5658.2  220.79  5689.7  222.01  5710.7  220.75  5788.2  220.28
#Mann= 6 ,-1 , 0
  4285.4     .16       0  4545.1     .05       0  4990.1     .07       0
  5012.6     .05       0  5098.6     .12       0  5249.3     .05       0
Bank Sta=4990.1,5012.6
XS Rating Curve= 0 ,0
Exp/Cntr=0.3,0.1

Chan Stop Cuts=-1
Use User Specified Reach Order=0
Composite Channel Slope=5