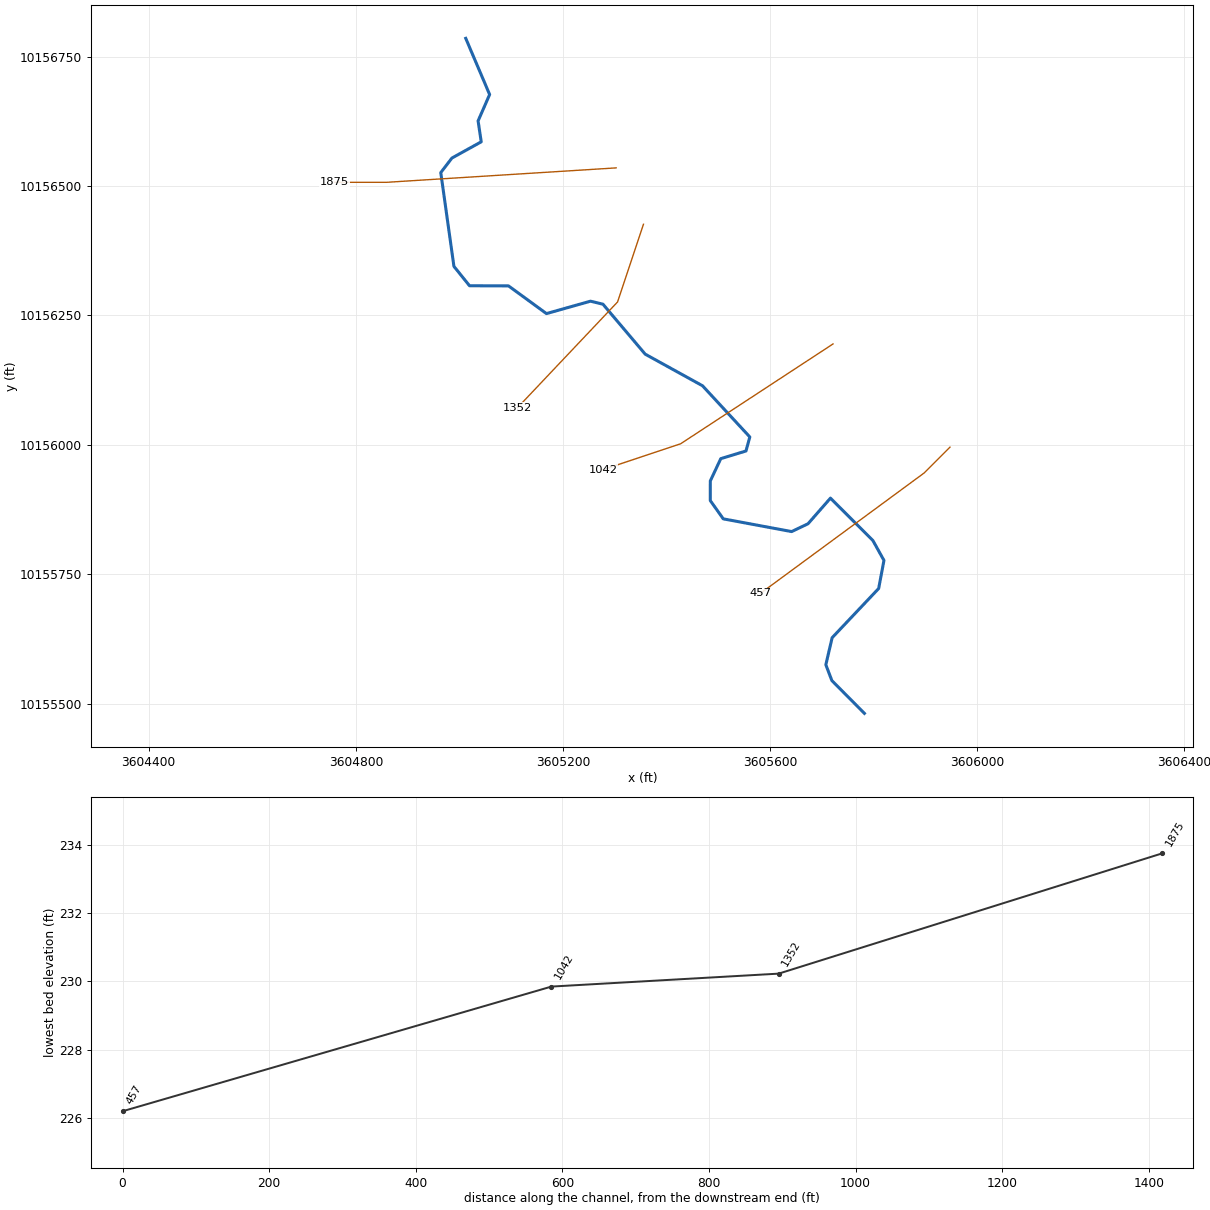
--- JONES CREEK TRIB 7.prj (project) ---

Proj Title=JONES CREEK TRIB 7 Base Level Engineering
Current Plan=p01
Default Exp/Contr=0.3,0.1
English Units
Geom File=g01
Flow File=f01
Plan File=p01
Y Axis Title=Elevation
X Axis Title(PF)=Main Channel Distance
X Axis Title(XS)=Station
BEGIN DESCRIPTION:
JONES CREEK TRIB 7
END DESCRIPTION:
DSS Export Rating Curves= 0
DSS Export Rating Curve Sorted= 0
DSS Export Volume Flow Curves= 0
DXF OffsetX= 0
DXF OffsetY= 0
DXF ScaleX= 1
DXF ScaleY= 10

--- JONES CREEK TRIB 7.p01 (plan) ---

Plan Title=Multiple Run
Short Identifier=Multiple
Geom File=g01
Flow File=f01
Subcritical Flow
K Sum by GR= 0
Std Step Tol= 0.01
Critical Tol= 0.01
Num of Std Step Trials= 20
Max Error Tol= 0.3
Flow Tol Ratio= 0.001
Split Flow NTrial= 30
Split Flow Tol= 0.02
Split Flow Ratio= 0.02
Log Output Level= 0
Friction Slope Method= 1
Unsteady Friction Slope Method= 2
Unsteady Bridges Friction Slope Method= 1
Parabolic Critical Depth
Global Vel Dist=  1 , 1 , 1
Global Log Level= 0
CheckData=True
Encroach Param= -1, 0, 0, 0
BEGIN DESCRIPTION:
Multiple Run
END DESCRIPTION:

--- JONES CREEK TRIB 7.f01 (steady flow) ---

Flow Title=Multiple
Number of Profiles=7
Profile Names=10-year,25-year,50-year,1pct_min,100-year,1pct_plu,500-year
River Rch & RM= JONES CREEK TRIB,Reach-1,1875
     282     363     426     367     497     672     676
Boundary for River Rch & Prof#=JONES CREEK TRIB,Reach-1,1
Up Type=0
Dn Type=3
Dn Slope=0.005
Boundary for River Rch & Prof#=JONES CREEK TRIB,Reach-1,2
Up Type=0
Dn Type=3
Dn Slope=0.005
Boundary for River Rch & Prof#=JONES CREEK TRIB,Reach-1,3
Up Type=0
Dn Type=3
Dn Slope=0.005
Boundary for River Rch & Prof#=JONES CREEK TRIB,Reach-1,4
Up Type=0
Dn Type=3
Dn Slope=0.005
Boundary for River Rch & Prof#=JONES CREEK TRIB,Reach-1,5
Up Type=0
Dn Type=3
Dn Slope=0.005
Boundary for River Rch & Prof#=JONES CREEK TRIB,Reach-1,6
Up Type=0
Dn Type=3
Dn Slope=0.005
Boundary for River Rch & Prof#=JONES CREEK TRIB,Reach-1,7
Up Type=0
Dn Type=3
Dn Slope=0.005

--- JONES CREEK TRIB 7.g01 (geometry) ---

Geom Title=Existing Conditions
Program Version=4.10

River Reach=JONES CREEK TRIB,Reach-1
Reach XY= 30
      3605012.22     10156785.21      3605058.36     10156676.68
      3605036.08     10156625.72      3605042.15     10156585.35
      3604985.56     10156554.04      3604964.03     10156525.97
      3604989.41     10156344.85      3605019.55     10156307.43
      3605094.83     10156307.13      3605168.13     10156253.65
      3605253.14     10156277.62      3605277.19     10156271.81
      3605358.78     10156175.33      3605469.43      10156114.3
      3605560.81     10156015.42      3605553.41     10155988.34
      3605504.71     10155973.52      3605484.51     10155930.46
      3605484.44     10155892.65       3605509.5     10155857.28
      3605641.58      10155832.7      3605673.23     10155847.83
      3605716.53      10155897.3       3605798.4     10155815.57
      3605819.84     10155777.06      3605809.63      10155722.8
      3605719.79     10155627.76       3605707.6     10155575.45
      3605719.29     10155544.92      3605782.11     10155481.64

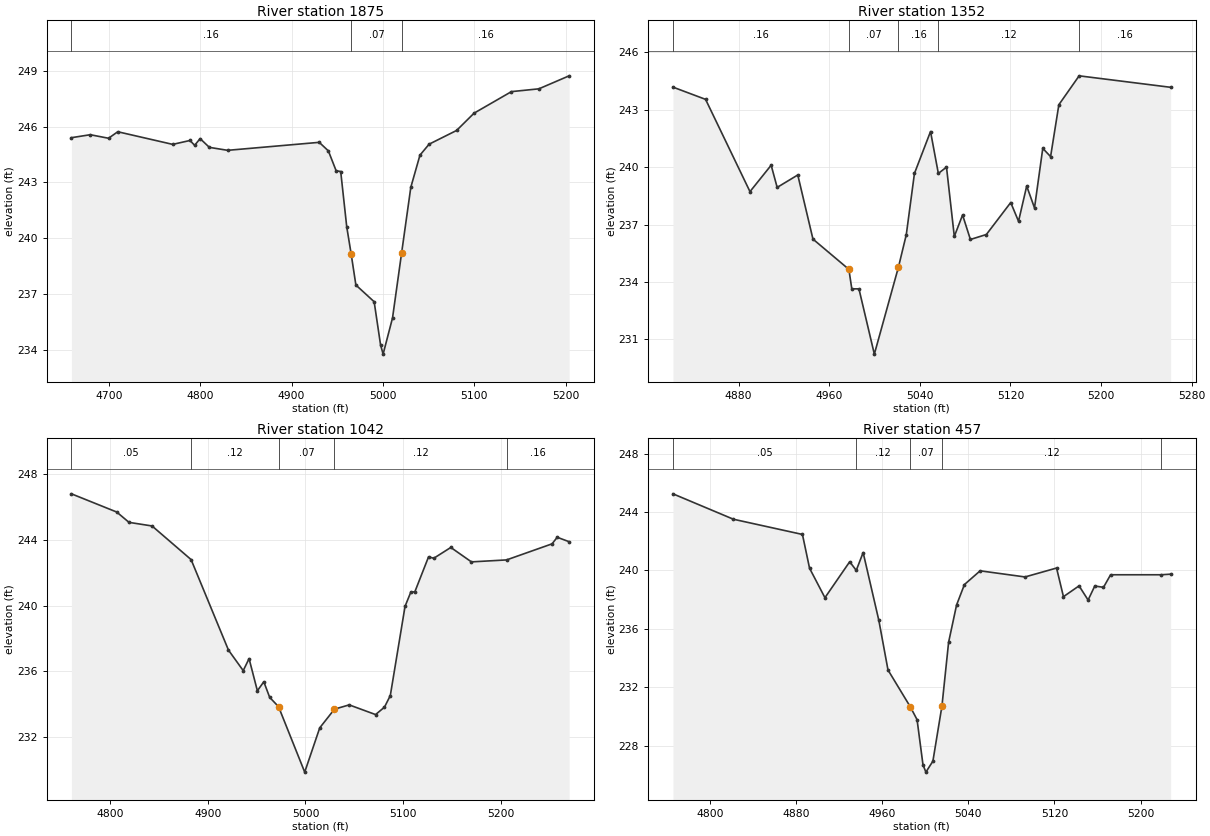
Type RM Length L Ch R = 1 ,1875    ,523,523,523
BEGIN DESCRIPTION:
JONES CREEK TRIB 7 4.0
END DESCRIPTION:
XS GIS Cut Line= 3
      3605302.67     10156535.03      3604859.06     10156507.15
      3604759.05     10156507.15
#Sta/Elev= 30
  4659.1  245.41  4679.7  245.57  4699.7  245.38  4709.8  245.73  4769.9  245.05
  4788.8  245.26  4793.9     245  4799.9  245.36    4810  244.89    4830  244.73
  4930.2  245.16  4940.2   244.7  4948.7  243.63  4953.7  243.59  4960.3  240.61
 4965.11  239.16  4970.3  237.48  4990.3  236.58  4997.3  234.26  5000.1  233.76
  5010.4  235.71  5020.4  239.23  5030.4  242.74  5040.4  244.47  5050.4  245.06
  5080.5   245.8  5099.6  246.73  5140.5  247.89  5170.5  248.04  5203.6  248.74
#Mann= 3 , 0 , 0
  4659.1     .16       0 4965.11     .07       0  5020.4     .16       0
Bank Sta=4965.11,5020.4
XS Rating Curve= 0 ,0
Exp/Cntr=0.3,0.1

Type RM Length L Ch R = 1 ,1352    ,310,310,310
BEGIN DESCRIPTION:
JONES CREEK TRIB 7 3.0
END DESCRIPTION:
XS GIS Cut Line= 3
      3605355.45     10156426.17      3605305.44     10156276.14
      3605112.13     10156071.86
#Sta/Elev= 30
    4822  244.18  4850.8  243.54    4890  238.72  4908.7   240.1    4914  238.94
  4932.2  239.59  4945.6  236.24  4977.3  234.66  4979.9  233.64  4986.2  233.64
  4999.8  230.23  5021.1  234.78    5028  236.47  5035.2  239.67  5049.4  241.86
  5056.3  239.67  5063.5     240  5070.4  236.38  5077.7   237.5  5084.6  236.22
  5098.7  236.48  5120.2  238.15  5127.1  237.17  5134.3  239.01  5141.2  237.87
  5148.5  240.98  5155.4  240.55  5162.7  243.26  5180.6  244.77  5261.4  244.17
#Mann= 5 ,-1 , 0
    4822     .16       0  4977.3     .07       0  5021.1     .16       0
  5056.3     .12       0  5180.6     .16       0
Bank Sta=4977.3,5021.1
XS Rating Curve= 0 ,0
Exp/Cntr=0.3,0.1

Type RM Length L Ch R = 1 ,1042    ,585,585,585
BEGIN DESCRIPTION:
JONES CREEK TRIB 7 2.0
END DESCRIPTION:
XS GIS Cut Line= 3
      3605721.44       10156195.      3605427.13     10156002.22
      3605277.17     10155952.23
#Sta/Elev= 30
  4760.2  246.82  4806.6  245.71  4819.2  245.08  4842.8  244.86  4882.8  242.81
  4921.1  237.29  4936.2  236.04  4942.2  236.77  4950.7  234.81  4957.3  235.36
  4963.3  234.41  4972.4  233.84  4999.2  229.85  5014.6  232.55  5029.7  233.69
  5044.8  233.95  5071.8  233.36  5080.9  233.81  5086.9  234.52    5102  239.96
    5108  240.84    5112  240.84  5126.1  242.98  5131.4  242.89  5148.9  243.55
    5170  242.67    5206  242.79  5252.6  243.77  5257.9  244.17  5270.1   243.9
#Mann= 5 ,-1 , 0
  4760.2     .05       0  4882.8     .12       0  4972.4     .07       0
  5029.7     .12       0    5206     .16       0
Bank Sta=4972.4,5029.7
XS Rating Curve= 0 ,0
Exp/Cntr=0.3,0.1

Type RM Length L Ch R = 1 ,457     ,0,0,0
BEGIN DESCRIPTION:
JONES CREEK TRIB 7 1.0
END DESCRIPTION:
XS GIS Cut Line= 3
       3605947.4     10155995.82      3605897.42     10155945.85
      3605581.86     10155713.76
#Sta/Elev= 30
  4765.6  245.24  4821.8   243.5  4885.9  242.46  4892.5  240.15  4906.8  238.13
  4929.8  240.59  4935.9     240  4942.3  241.22  4956.9  236.57  4965.4  233.18
  4986.2  230.65  4992.4  229.78  4997.9  226.69  5000.6  226.19  5007.1  226.94
  5015.5  230.71  5021.7  235.08  5029.1  237.63  5036.4  239.03    5051  239.97
  5092.7  239.55    5122  240.16  5128.4   238.2  5142.9  238.94  5151.3  237.97
  5157.5  238.93  5165.6  238.84  5172.2   239.7  5219.2   239.7    5228  239.74
#Mann= 5 ,-1 , 0
  4765.6     .05       0  4935.9     .12       0  4986.2     .07       0
  5015.5     .12       0  5219.2     .16       0
Bank Sta=4986.2,5015.5
XS Rating Curve= 0 ,0
Exp/Cntr=0.3,0.1

Chan Stop Cuts=-1
Use User Specified Reach Order=0
Composite Channel Slope=5