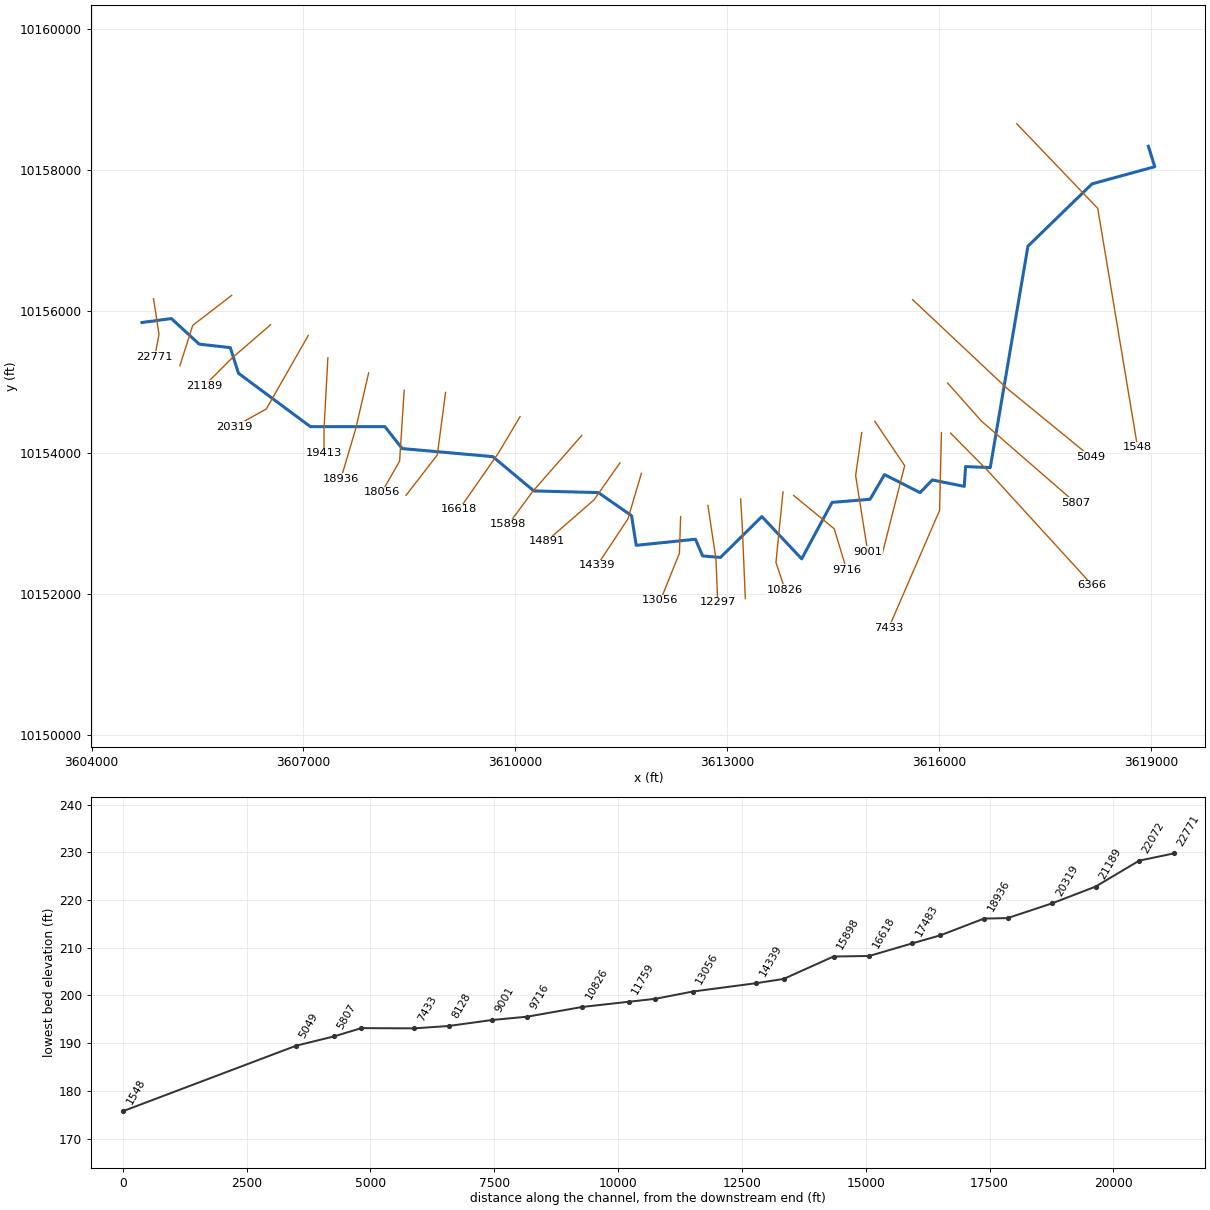
--- JONES CREEK.prj (project) ---

Proj Title=JONES CREEK Base Level Engineering
Current Plan=p01
Default Exp/Contr=0.3,0.1
English Units
Geom File=g01
Flow File=f01
Plan File=p01
Y Axis Title=Elevation
X Axis Title(PF)=Main Channel Distance
X Axis Title(XS)=Station
BEGIN DESCRIPTION:
JONES CREEK
END DESCRIPTION:
DSS Export Rating Curves= 0
DSS Export Rating Curve Sorted= 0
DSS Export Volume Flow Curves= 0
DXF OffsetX= 0
DXF OffsetY= 0
DXF ScaleX= 1
DXF ScaleY= 10

--- JONES CREEK.p01 (plan) ---

Plan Title=Multiple Run
Short Identifier=Multiple
Geom File=g01
Flow File=f01
Subcritical Flow
K Sum by GR= 0
Std Step Tol= 0.01
Critical Tol= 0.01
Num of Std Step Trials= 20
Max Error Tol= 0.3
Flow Tol Ratio= 0.001
Split Flow NTrial= 30
Split Flow Tol= 0.02
Split Flow Ratio= 0.02
Log Output Level= 0
Friction Slope Method= 1
Unsteady Friction Slope Method= 2
Unsteady Bridges Friction Slope Method= 1
Parabolic Critical Depth
Global Vel Dist=  1 , 1 , 1
Global Log Level= 0
CheckData=True
Encroach Param= -1, 0, 0, 0
BEGIN DESCRIPTION:
Multiple Run
END DESCRIPTION:

--- JONES CREEK.f01 (steady flow) ---

Flow Title=Multiple
Program Version=4.10
Number of Profiles= 7
Profile Names=10-year,25-year,50-year,1pct_min,100-year,1pct_plu,500-year
River Rch & RM=JONES CREEK,Reach-1         ,22771
     438     580     695     612     827    1119    1172
River Rch & RM=JONES CREEK,Reach-1         ,22072
     653     885    1076     959    1297    1754    1886
River Rch & RM=JONES CREEK,Reach-1         ,21189
     653     885    1076     959    1297    1754    1886
River Rch & RM=JONES CREEK,Reach-1         ,19413
    1369    1911    2367    2142    2897    3917    4349
River Rch & RM=JONES CREEK,Reach-1         ,14891
    1445    2015    2493    2253    3047    4121    4563
River Rch & RM=JONES CREEK,Reach-1         ,9001
    1754    2462    3059    2773    3751    5072    5655
River Rch & RM=JONES CREEK,Reach-1         ,8128
    1754    2462    3059    2773    3751    5072    5655
Boundary for River Rch & Prof#=JONES CREEK,Reach-1         , 1
Up Type= 0
Dn Type= 3
Dn Slope=0.005
Boundary for River Rch & Prof#=JONES CREEK,Reach-1         , 2
Up Type= 0
Dn Type= 3
Dn Slope=0.005
Boundary for River Rch & Prof#=JONES CREEK,Reach-1         , 3
Up Type= 0
Dn Type= 3
Dn Slope=0.005
Boundary for River Rch & Prof#=JONES CREEK,Reach-1         , 4
Up Type= 0
Dn Type= 3
Dn Slope=0.005
Boundary for River Rch & Prof#=JONES CREEK,Reach-1         , 5
Up Type= 0
Dn Type= 3
Dn Slope=0.005
Boundary for River Rch & Prof#=JONES CREEK,Reach-1         , 6
Up Type= 0
Dn Type= 3
Dn Slope=0.005
Boundary for River Rch & Prof#=JONES CREEK,Reach-1         , 7
Up Type= 0
Dn Type= 3
Dn Slope=0.005
DSS Import GetInterval= 0
DSS Import GetPeak= 0
DSS Import FillOption= 0

--- JONES CREEK.g01 (geometry) ---

Geom Title=Existing Conditions
Program Version=4.10

River Reach=JONES CREEK     ,Reach-1
Reach XY= 30
      3604713.07     10155842.03      3605130.19     10155898.34
       3605524.2     10155535.46       3605964.6     10155486.22
      3606080.24     10155122.85      3607099.29     10154366.22
      3608153.73     10154366.66      3608399.01     10154055.75
      3609682.11     10153941.64      3610263.41     10153455.66
      3611177.26     10153432.11      3611647.06     10153104.52
      3611713.33     10152684.63      3612552.16     10152770.69
      3612653.38     10152534.24      3612906.45     10152512.89
      3613492.38     10153092.02      3614056.31     10152493.18
      3614487.43     10153293.43      3615024.83     10153336.98
      3615229.71     10153686.54      3615733.12     10153431.52
      3615906.82     10153611.21      3616359.01     10153519.78
      3616377.47     10153800.55      3616727.06     10153786.52
      3617260.84     10156924.23      3618169.23     10157807.25
      3619057.09     10158050.16      3618966.06      10158339.9

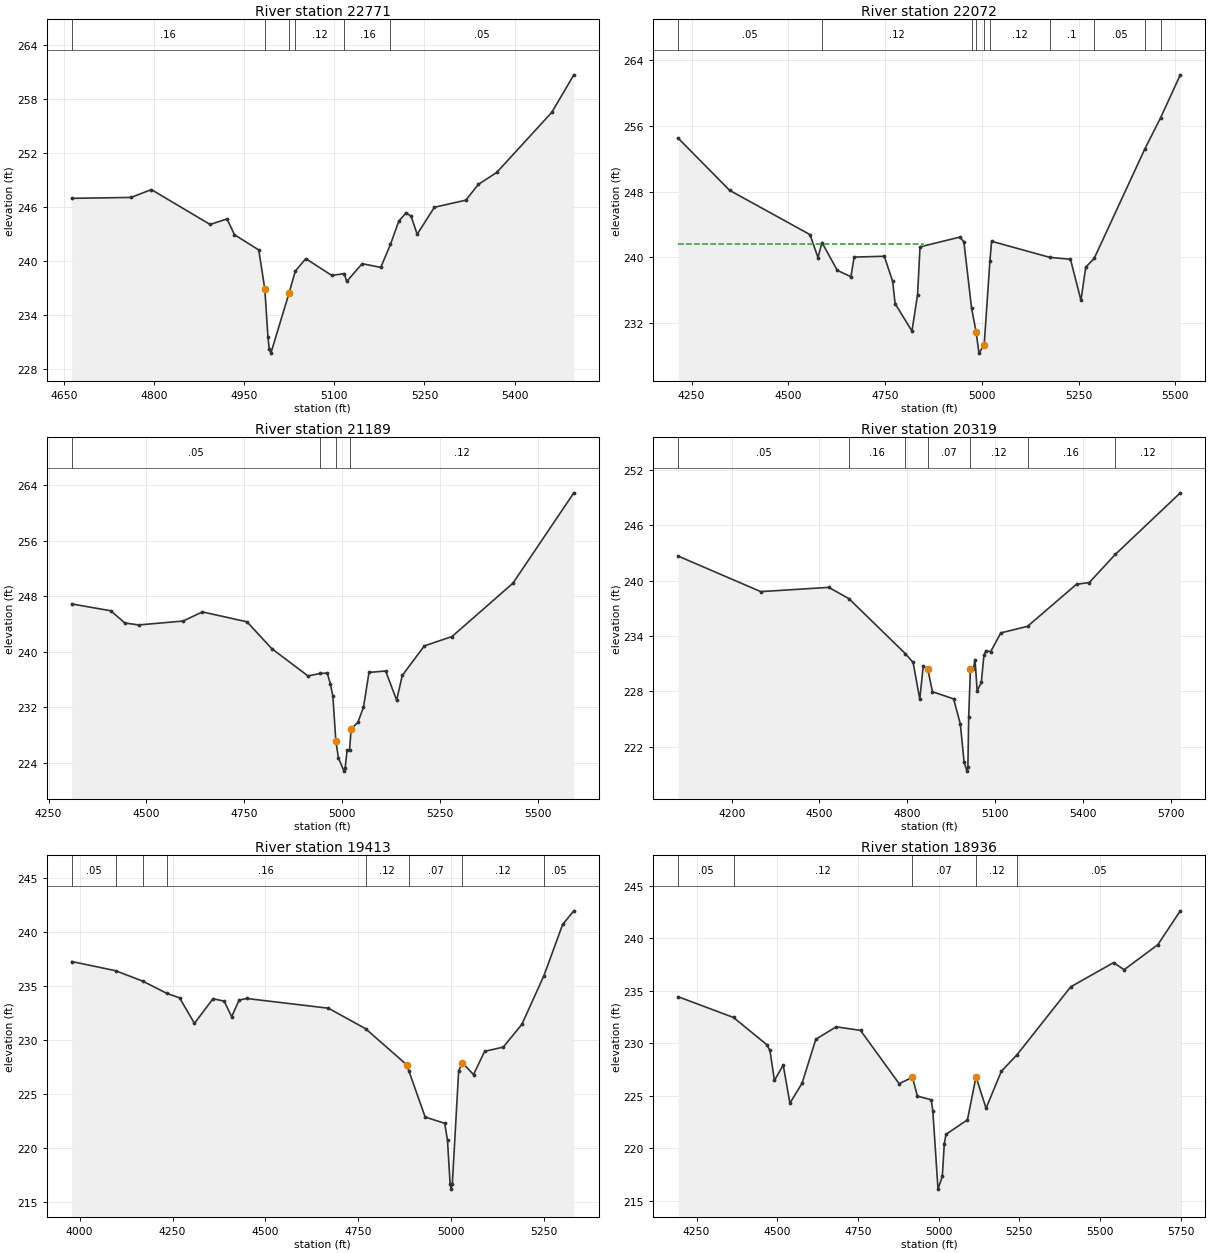
Type RM Length L Ch R = 1 ,22771   ,699,699,699
BEGIN DESCRIPTION:
JONES CREEK 41.0
END DESCRIPTION:
XS GIS Cut Line= 3
      3604877.03     10156179.27      3604955.15     10155675.77
      3604894.58     10155355.58
#Sta/Elev= 30
  4663.1  246.94  4761.9  247.04  4795.7  247.91  4893.5  244.04  4921.6  244.66
  4933.9  242.91  4974.4  241.21  4984.5  236.84  4989.6  231.61  4991.7  230.27
  4994.5  229.77    5025  236.48  5035.1  238.87  5052.6  240.25  5095.8  238.39
  5116.7  238.59  5120.6  237.72  5146.4  239.69  5177.3  239.28  5193.5  241.84
  5207.4  244.43  5219.3  245.31  5227.7  244.98  5237.9  242.95  5266.5  245.95
  5318.9  246.74  5339.7  248.49  5370.2  249.81  5461.8  256.48  5498.5  260.64
#Mann= 6 ,-1 , 0
  4663.1     .16       0  4984.5     .07       0    5025     .16       0
  5035.1     .12       0  5116.7     .16       0  5193.5     .05       0
Bank Sta=4984.5,5025
XS Rating Curve= 0 ,0
Exp/Cntr=0.3,0.1

Type RM Length L Ch R = 1 ,22072   ,883,883,883
BEGIN DESCRIPTION:
JONES CREEK 40.0
END DESCRIPTION:
XS GIS Cut Line= 3
      3605983.78     10156226.97      3605432.59     10155801.64
      3605250.31     10155228.76
#Sta/Elev= 30
  4215.2  254.52  4348.3  248.14  4555.8  242.74  4576.6  239.93  4586.8  241.77
  4626.4  238.37  4661.7  237.59  4669.9  239.99  4747.8  240.09  4769.5  237.03
  4775.8  234.31  4819.3  230.95  4833.8  235.39  4840.2  241.24  4942.9  242.43
  4953.4  241.86  4973.3  233.77  4984.9  230.89  4992.5  228.26  5005.9  229.28
  5020.7   239.5    5025  241.92  5175.1  239.96  5228.9  239.72  5255.9  234.71
  5268.2  238.75  5290.3  239.85    5421   253.2  5461.9  257.03  5512.6  262.25
#Mann= 10 ,-1 , 0
  4215.2     .05       0  4586.8     .12       0  4973.3     .16       0
  4984.9     .07       0  5005.9     .16       0  5020.7     .12       0
  5175.1      .1       0  5290.3     .05       0    5421      .1       0
  5461.9     .05       0
#XS Ineff= 2 , 0
          4847.5  241.57
Permanent Ineff=
       F       F
Bank Sta=4984.9,5005.9
XS Rating Curve= 0 ,0
Exp/Cntr=0.3,0.1

Type RM Length L Ch R = 1 ,21189   ,870,870,870
BEGIN DESCRIPTION:
JONES CREEK 39.0
END DESCRIPTION:
XS GIS Cut Line= 3
        3606535.     10155810.31      3605992.11     10155341.64
       3605592.1     10154941.63
#Sta/Elev= 30
    4309  246.92  4409.2  245.93  4444.9  244.17  4480.4  243.89  4593.5  244.45
  4643.1  245.77  4756.9  244.34  4820.5  240.46  4912.7  236.54  4944.6   236.9
    4962  236.95  4969.7  235.44  4976.3  233.64    4984  227.09  4990.6   224.7
  5004.6  222.81  5007.8  223.31  5012.5  225.79  5019.1  225.92  5022.9  228.89
  5040.3  229.85  5054.5  232.03  5068.6  237.04  5111.1  237.25  5139.3  233.04
  5153.5   236.6    5210  240.87  5280.8  242.22  5436.3  249.91  5591.9  262.94
#Mann= 4 ,-1 , 0
    4309     .05       0  4944.6     .12       0    4984     .07       0
  5019.1     .12       0
Bank Sta=4984,5022.9
XS Rating Curve= 0 ,0
Exp/Cntr=0.3,0.1

Type RM Length L Ch R = 1 ,20319   ,906,906,906
BEGIN DESCRIPTION:
JONES CREEK 37.0
END DESCRIPTION:
XS GIS Cut Line= 3
      3607068.86      10155658.4      3606474.25     10154616.74
      3606024.31     10154365.82
#Sta/Elev= 30
  4017.3  242.67  4299.5  238.81  4531.7  239.27  4600.3  238.05  4793.4  232.07
  4819.6  231.12  4842.4  227.14  4854.1  230.71  4869.7  230.42  4885.6  227.95
  4957.8  227.17  4980.8  224.46  4993.6  220.35  5003.4  219.33  5006.7  219.83
  5009.4  225.24  5015.3  230.39  5025.3   230.4    5031  231.42  5038.4  228.03
  5052.6  228.98  5061.4  231.91  5068.5  232.41  5084.3  232.28    5119  234.33
  5210.2  235.04  5377.5  239.61  5420.9  239.79  5509.7  242.84  5731.9  249.53
#Mann= 7 ,-1 , 0
  4017.3     .05       0  4600.3     .16       0  4793.4     .12       0
  4869.7     .07       0  5015.3     .12       0  5210.2     .16       0
  5509.7     .12       0
Bank Sta=4869.7,5015.3
XS Rating Curve= 0 ,0
Exp/Cntr=0.3,0.1

Type RM Length L Ch R = 1 ,19413   ,477,477,477
BEGIN DESCRIPTION:
JONES CREEK 35.0
END DESCRIPTION:
XS GIS Cut Line= 3
      3607346.65     10155341.62      3607292.11     10154341.64
      3607292.11      10153991.6
#Sta/Elev= 30
  3978.5  237.27  4096.6  236.42  4169.5  235.46  4234.9  234.32  4268.9  233.91
    4309  231.55    4359  233.83  4389.1   233.6  4409.1  232.16  4429.1   233.7
  4449.2  233.85  4669.5  232.95  4769.6  231.05  4879.8  227.73  4886.5   227.1
  4929.9  222.88  4982.5   222.3    4990  220.72    4997  216.71  4999.7  216.21
    5003  216.71    5020  227.15    5030   227.9    5060  226.81    5090  228.96
    5140  229.35    5190  231.45  5249.6  235.97    5300  240.71    5330  241.96
#Mann= 8 ,-1 , 0
  3978.5     .05       0  4096.6     .16       0  4169.5     .05       0
  4234.9     .16       0  4769.6     .12       0  4886.5     .07       0
    5030     .12       0  5249.6     .05       0
Bank Sta=4879.8,5030
XS Rating Curve= 0 ,0
Exp/Cntr=0.3,0.1

Type RM Length L Ch R = 1 ,18936   ,880,880,880
BEGIN DESCRIPTION:
JONES CREEK 34.0
END DESCRIPTION:
XS GIS Cut Line= 3
       3607923.9     10155128.88      3607742.11     10154341.64
      3607529.51     10153624.76
#Sta/Elev= 30
  4192.9  234.44  4364.5  232.46  4467.2  229.88  4477.4  229.32  4491.3  226.46
  4518.5  227.93  4539.2   224.3  4576.8  226.19  4619.5  230.39  4682.7  231.57
    4758  231.23  4877.7  226.15  4918.7  226.77  4934.2  224.97  4976.9  224.62
    4982  223.56    4998  216.11  5011.3  217.33  5017.5  220.45  5022.7  221.33
  5089.2  222.71  5115.6   226.8  5146.9  223.82  5194.1  227.33  5242.7  228.91
  5409.1  235.38    5542  237.69  5574.5  237.01  5678.8  239.39  5748.6  242.62
#Mann= 5 ,-1 , 0
  4192.9     .05       0  4364.5     .12       0  4918.7     .07       0
  5115.6     .12       0  5242.7     .05       0
Bank Sta=4918.7,5115.6
XS Rating Curve= 0 ,0
Exp/Cntr=0.3,0.1

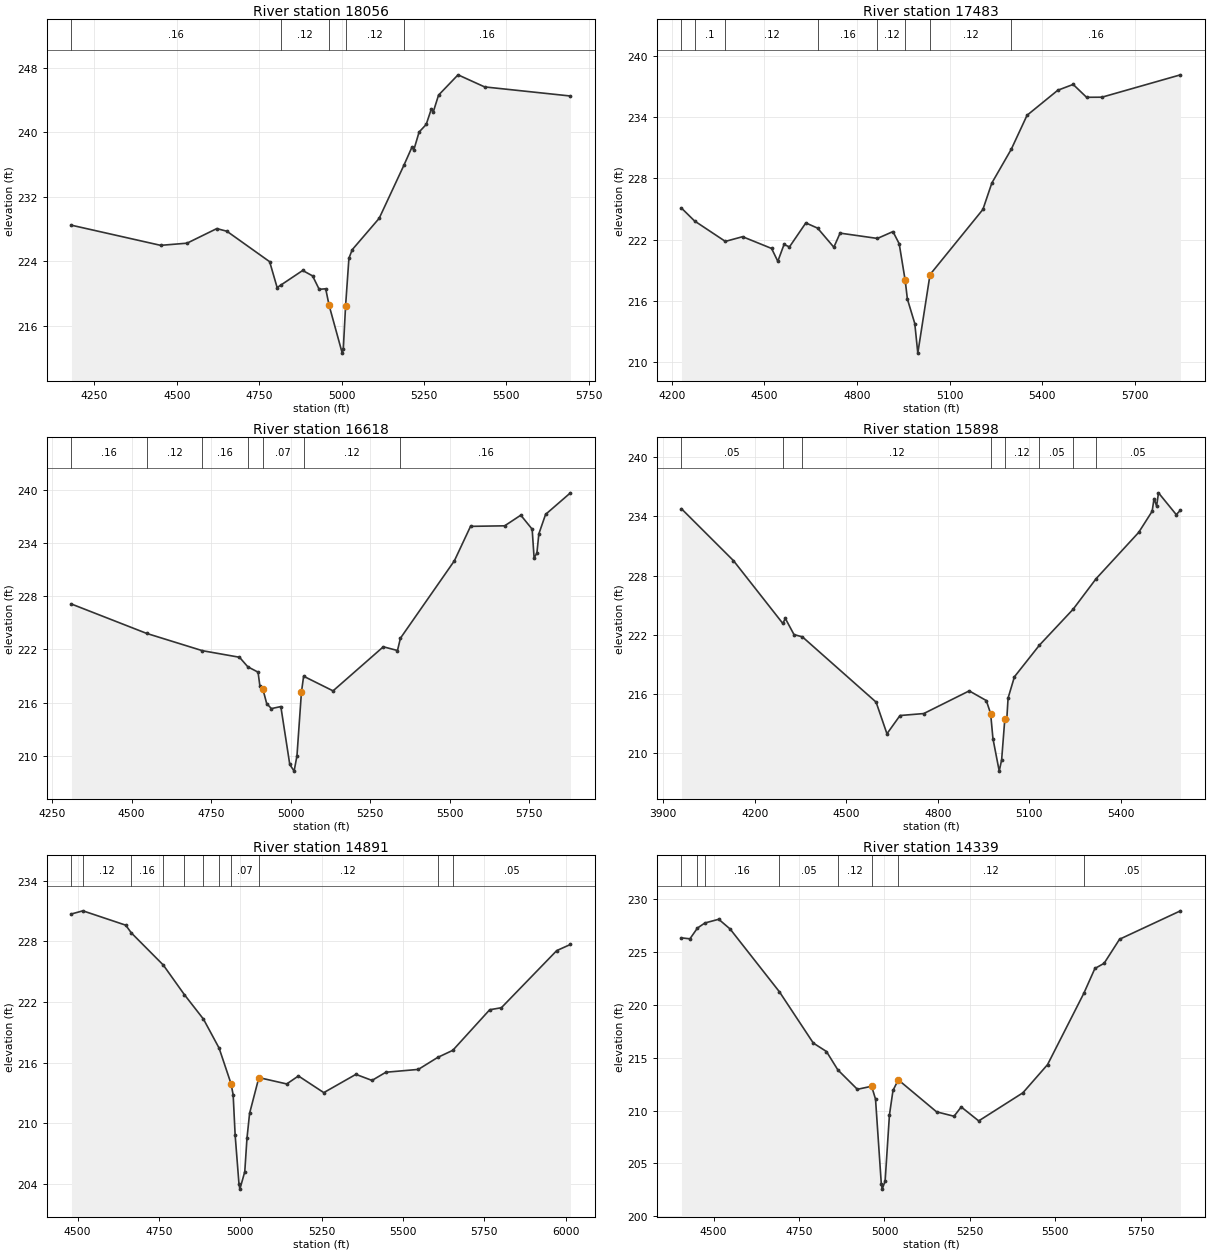
Type RM Length L Ch R = 1 ,18056   ,573,573,573
BEGIN DESCRIPTION:
JONES CREEK 32.0
END DESCRIPTION:
XS GIS Cut Line= 3
      3608427.38     10154881.53      3608362.27      10153878.9
      3608110.65     10153436.38
#Sta/Elev= 30
  4180.8  228.48  4451.3  225.98  4531.4  226.25  4621.6  228.06  4652.3  227.73
    4782  223.95  4804.7  220.74    4816  221.05  4882.2  222.86  4912.2  222.19
  4932.3  220.52    4952  220.59  4962.3  218.54  5002.2   212.6  5005.4   213.1
  5012.4  218.49  5022.5  224.38  5032.5  225.44  5114.3  229.34  5189.7  235.96
  5213.7  238.17  5219.4  237.83  5235.3  240.04  5256.9  240.99  5272.8  242.94
  5278.5  242.56  5294.4  244.63  5353.5  247.15  5434.2  245.65  5694.6  244.52
#Mann= 5 ,-1 , 0
  4180.8     .16       0    4816     .12       0  4962.3     .07       0
  5012.4     .12       0  5189.7     .16       0
Bank Sta=4962.3,5012.4
XS Rating Curve= 0 ,0
Exp/Cntr=0.3,0.1

Type RM Length L Ch R = 1 ,17483   ,865,865,865
BEGIN DESCRIPTION:
JONES CREEK 31.0
END DESCRIPTION:
XS GIS Cut Line= 3
      3609013.32     10154851.17      3608896.13      10153965.7
      3608453.43      10153392.8
#Sta/Elev= 30
  4231.1   225.1  4273.5  223.84  4373.2  221.84  4429.1   222.3  4523.1  221.15
  4543.3  219.89  4563.5  221.54    4581   221.3  4634.1  223.65  4672.2  223.14
  4724.9  221.27  4745.1  222.65  4866.1  222.13  4916.5   222.8  4936.7  221.61
    4956  218.04  4956.9  217.83  4963.2   216.2  4987.2   213.8    4997   210.9
  5036.6  218.59    5208  224.97    5237  227.56  5299.9  230.86  5351.1  234.19
  5450.7  236.64  5500.5  237.21    5544  235.95  5593.8  235.96  5848.3  238.15
#Mann= 8 ,-1 , 0
  4231.1     .16       0  4273.5      .1       0  4373.2     .12       0
  4672.2     .16       0  4866.1     .12       0  4956.9     .07       0
  5036.6     .12       0  5299.9     .16       0
Bank Sta=4956,5036.6
XS Rating Curve= 0 ,0
Exp/Cntr=0.3,0.1

Type RM Length L Ch R = 1 ,16618   ,720,720,720
BEGIN DESCRIPTION:
JONES CREEK 29.0
END DESCRIPTION:
XS GIS Cut Line= 3
      3610067.98     10154508.21      3609764.18     10153996.08
      3609208.62     10153197.47
#Sta/Elev= 30
    4311  227.11  4547.1   223.8  4722.4  221.85    4839  221.11  4865.3  220.03
  4897.4  219.43  4903.3  217.83  4912.2  217.57  4924.5  215.89  4939.3  215.32
    4969  215.55  4997.1  209.02  5010.7  208.27  5019.7     210  5033.7  217.16
  5040.6  218.97  5133.1  217.32  5291.1  222.29  5335.6  221.87  5344.9  223.26
  5514.5  231.99  5565.2  235.87  5672.5  235.93  5723.2  237.13  5758.9  235.55
    5765  232.31  5773.8  232.85  5779.9  235.02  5801.1  237.22  5879.3  239.65
#Mann= 7 ,-1 , 0
    4311     .16       0  4547.1     .12       0  4722.4     .16       0
  4865.3     .12       0  4912.2     .07       0  5040.6     .12       0
  5344.9     .16       0
Bank Sta=4912.2,5033.7
XS Rating Curve= 0 ,0
Exp/Cntr=0.3,0.1

Type RM Length L Ch R = 1 ,15898   ,1007,1007,1007
BEGIN DESCRIPTION:
JONES CREEK 27.0
END DESCRIPTION:
XS GIS Cut Line= 3
      3610942.13     10154241.67      3610242.11     10153441.64
       3609903.1      10152980.5
#Sta/Elev= 30
  3959.8  234.77  4130.2  229.51  4291.9  223.14  4300.1  223.65  4328.6  222.01
  4356.1  221.78  4597.6  215.16  4633.2  211.95    4676   213.8  4753.8     214
  4902.8   216.3  4958.8  215.32    4973     214  4980.6  211.46  5001.2  208.16
  5009.1  209.31  5019.5  213.44    5026  213.44  5030.2  215.57    5051  217.73
    5133  220.94  5243.6  224.59  5318.7  227.68  5458.4  232.38  5502.4  234.52
  5508.6   235.8    5517  235.05  5523.2  236.39  5581.4  234.18  5595.2  234.63
#Mann= 8 ,-1 , 0
  3959.8     .05       0  4291.9     .16       0  4356.1     .12       0
    4973     .07       0  5019.5     .12       0    5133     .05       0
  5243.6     .16       0  5318.7     .05       0
Bank Sta=4973,5019.5
XS Rating Curve= 0 ,0
Exp/Cntr=0.3,0.1

Type RM Length L Ch R = 1 ,14891   ,552,552,552
BEGIN DESCRIPTION:
JONES CREEK 25.0
END DESCRIPTION:
XS GIS Cut Line= 3
      3611482.92     10153852.83      3611114.01     10153327.68
      3610442.14     10152741.67
#Sta/Elev= 30
  4481.4  230.72  4516.4  231.03    4648  229.61  4665.4  228.84  4763.5  225.66
    4828  222.74    4887   220.3    4935  217.43  4971.7   213.9  4978.2   212.8
  4984.3  208.81  4996.1  203.96  4998.9  203.46  5013.9  205.19  5020.6  208.48
  5028.7  210.97  5057.2  214.51  5142.8  213.88  5178.8  214.67  5256.7  213.02
  5355.4  214.83  5404.8  214.23  5447.5  215.04  5547.2  215.32  5606.8  216.51
  5653.1  217.21  5766.5  221.23  5802.4  221.43  5972.5  227.09  6014.7   227.7
#Mann= 11 ,-1 , 0
  4481.4     .16       0  4516.4     .12       0  4665.4     .16       0
  4763.5      .1       0    4828     .05       0    4887      .1       0
    4935     .12       0  4971.7     .07       0  5057.2     .12       0
  5606.8     .16       0  5653.1     .05       0
Bank Sta=4971.7,5057.2
XS Rating Curve= 0 ,0
Exp/Cntr=0.3,0.1

Type RM Length L Ch R = 1 ,14339   ,1283,1283,1283
BEGIN DESCRIPTION:
JONES CREEK 23.0
END DESCRIPTION:
XS GIS Cut Line= 3
      3611786.76     10153705.33      3611595.78     10153058.58
      3611161.77     10152403.22
#Sta/Elev= 30
  4405.9  226.36  4430.6  226.27  4452.6  227.29  4474.5  227.77  4514.9  228.12
  4548.2   227.2  4692.6  221.25  4791.7   216.4  4830.2   215.6  4863.5  213.86
  4920.7  212.02  4962.4  212.31  4973.8  211.09  4990.7  203.07  4993.4  202.57
  5001.9  203.34  5014.5  209.59  5024.9  211.91  5040.4  212.92  5152.4  209.89
  5203.6  209.47  5224.6  210.35  5275.8  209.03  5405.1  211.69  5477.3  214.36
  5583.6  221.12  5615.8  223.46  5642.8  223.95    5688  226.23  5866.3  228.92
#Mann= 8 ,-1 , 0
  4405.9     .05       0  4452.6      .1       0  4474.5     .16       0
  4692.6     .05       0  4863.5     .12       0  4962.4     .07       0
  5040.4     .12       0  5583.6     .05       0
Bank Sta=4962.4,5040.4
XS Rating Curve= 0 ,0
Exp/Cntr=0.3,0.1

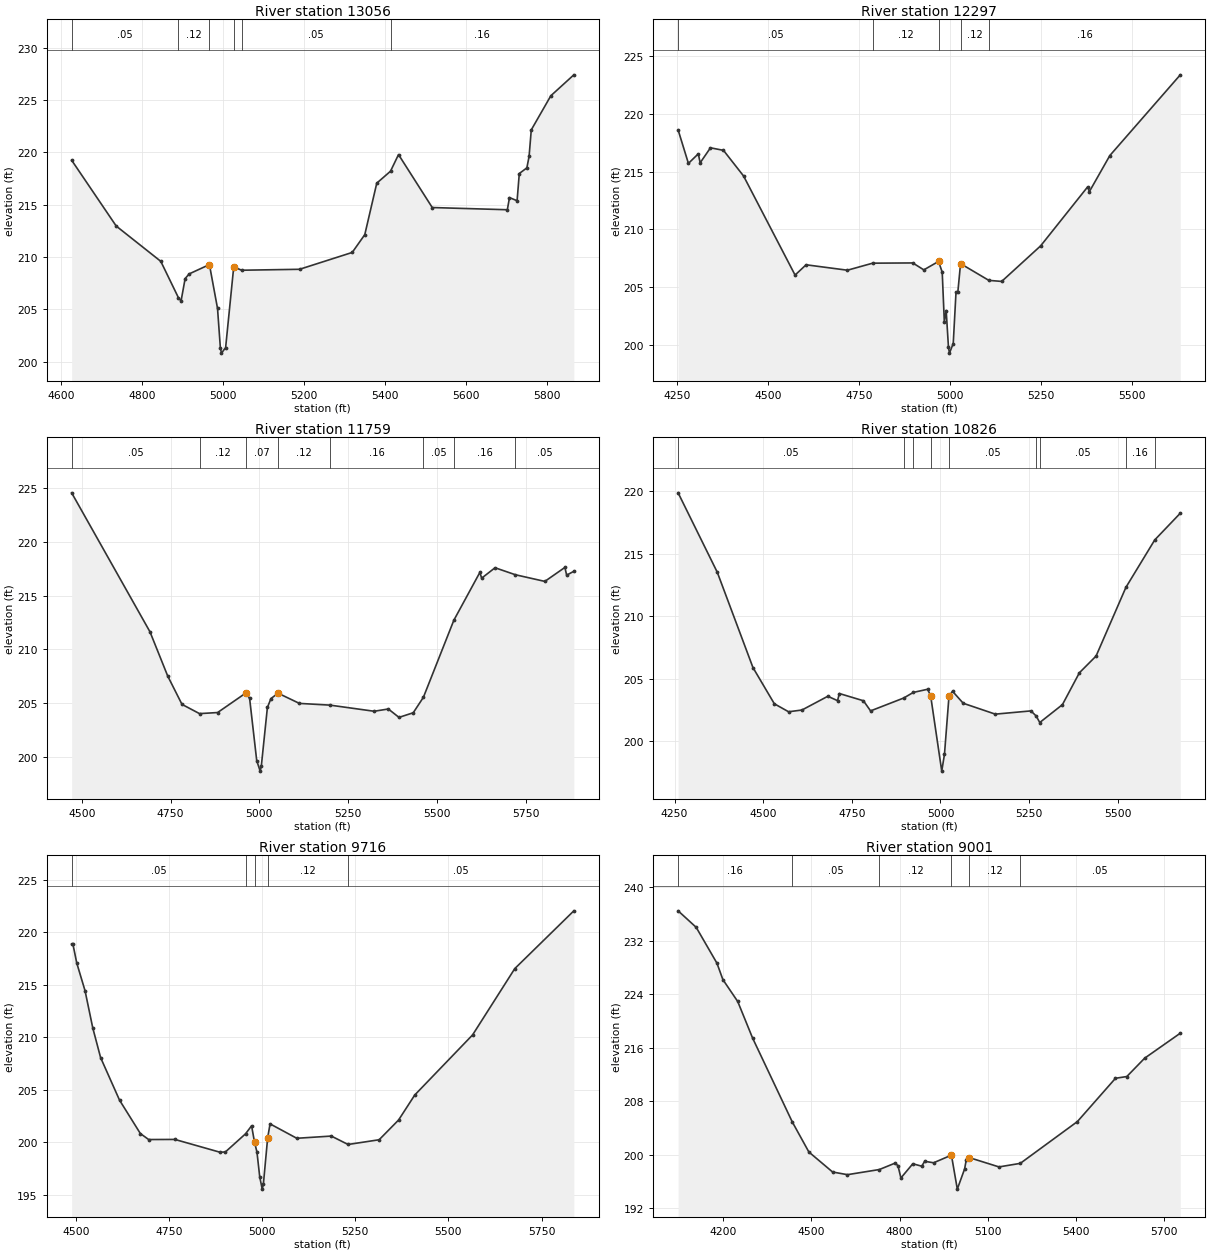
Type RM Length L Ch R = 1 ,13056   ,759,759,759
BEGIN DESCRIPTION:
JONES CREEK 21.0
END DESCRIPTION:
XS GIS Cut Line= 3
      3612342.11     10153091.66      3612324.95     10152572.47
      3612055.85     10151904.07
#Sta/Elev= 30
  4626.7  219.25  4736.8  212.96  4846.8  209.59  4890.4  206.11  4896.9  205.81
  4906.9  207.94  4916.9  208.39  4966.9  209.28  4986.9  205.09  4993.9  201.32
  4996.7  200.82  5006.9  201.35  5026.9  209.06  5046.4  208.74  5189.4  208.83
  5319.5  210.44  5350.5  212.14  5380.1  217.06    5414   218.2  5433.8  219.79
  5517.1  214.73  5702.5  214.52  5707.8  215.68  5726.6  215.38    5732  217.98
  5750.7  218.52  5756.2  219.61  5761.6  222.15  5809.9  225.41  5866.7  227.41
#Mann= 6 ,-1 , 0
  4626.7     .05       0  4890.4     .12       0  4966.9     .07       0
  5026.9     .12       0  5046.4     .05       0    5414     .16       0
Bank Sta=4966.9,5026.9
XS Rating Curve= 0 ,0
Exp/Cntr=0.3,0.1

Type RM Length L Ch R = 1 ,12297   ,538,538,538
BEGIN DESCRIPTION:
JONES CREEK 19.0
END DESCRIPTION:
XS GIS Cut Line= 3
      3612728.59      10153249.6      3612842.11     10152491.64
      3612867.48     10151878.08
#Sta/Elev= 30
  4253.3  218.62  4281.6  215.72  4308.8  216.55  4313.9  215.77  4342.2  217.07
    4378  216.85  4433.2  214.63  4574.8  206.05  4605.1  206.94  4718.7  206.47
  4788.1  207.08  4898.4   207.1  4928.7   206.5  4969.2  207.23  4979.3   206.3
  4985.1     202  4990.2  202.98  4996.5  199.79  4999.2  199.29  5009.6  200.12
  5017.2  204.56  5022.2  204.56  5029.7  207.04  5107.5  205.59  5142.8   205.5
  5249.9  208.58  5378.9  213.68  5383.9  213.28  5440.1   216.4  5633.8  223.39
#Mann= 5 ,-1 , 0
  4253.3     .05       0  4788.1     .12       0  4969.2     .07       0
  5029.7     .12       0  5107.5     .16       0
Bank Sta=4969.2,5029.7
XS Rating Curve= 0 ,0
Exp/Cntr=0.3,0.1

Type RM Length L Ch R = 1 ,11759   ,933,933,933
BEGIN DESCRIPTION:
JONES CREEK 18.0
END DESCRIPTION:
XS GIS Cut Line= 3
      3613192.11     10153341.61       3613214.7      10152963.1
      3613258.11      10151930.1
#Sta/Elev= 30
  4471.6  224.56    4692  211.63    4742  207.51  4782.1  204.88  4831.4  204.02
  4882.3  204.12  4962.3  205.95  4972.4  205.43  4992.4  199.64  5002.1  198.67
  5005.4  199.17  5022.4  204.59  5032.4  205.42  5052.4  205.92  5112.5  204.97
  5198.6  204.81  5322.7  204.24  5362.7  204.45  5392.7  203.67  5432.8   204.1
  5461.4  205.54  5547.1  212.71  5620.3  217.16  5625.3  216.62    5663  217.59
  5720.2  216.94  5803.1  216.32  5859.5  217.62  5864.5   216.9  5884.7  217.26
#Mann= 8 ,-1 , 0
  4471.6     .05       0  4831.4     .12       0  4962.3     .07       0
  5052.4     .12       0  5198.6     .16       0  5461.4     .05       0
  5547.1     .16       0  5720.2     .05       0
Bank Sta=4962.3,5052.4
XS Rating Curve= 0 ,0
Exp/Cntr=0.3,0.1

Type RM Length L Ch R = 1 ,10826   ,1110,1110,1110
BEGIN DESCRIPTION:
JONES CREEK 17.0
END DESCRIPTION:
XS GIS Cut Line= 3
       3613792.1     10153441.63      3613692.13     10152442.27
      3613822.34     10152051.64
#Sta/Elev= 30
  4260.2  219.86  4370.7   213.5  4471.2  205.88  4531.5  202.98  4571.7  202.34
  4609.4  202.48  4682.3  203.58  4709.8  203.23  4714.9   203.8  4782.8  203.22
  4802.9  202.41  4896.3  203.44  4923.5  203.89  4963.7  204.14  4972.2  203.64
  5003.6  197.59  5011.3  198.94    5024  203.58    5034  203.98  5064.2  203.02
  5154.6  202.15  5255.1  202.41  5269.9     202    5280  201.48  5343.9  202.91
  5391.7  205.46  5438.8   206.8    5523   212.3  5604.2  216.09  5676.3  218.23
#Mann= 9 ,-1 , 0
  4260.2     .05       0  4896.3     .12       0  4923.5     .05       0
  4972.2    .035       0    5024     .05       0  5269.9     .16       0
    5280     .05       0    5523     .16       0  5604.2     .05       0
Bank Sta=4972.2,5024
XS Rating Curve= 0 ,0
Exp/Cntr=0.3,0.1

Type RM Length L Ch R = 1 ,9716    ,715,715,715
BEGIN DESCRIPTION:
JONES CREEK 14.0
END DESCRIPTION:
XS GIS Cut Line= 3
      3613942.08     10153391.66      3614516.79      10152919.7
       3614692.1     10152341.66
#Sta/Elev= 30
    4489  218.89  4492.3  218.89  4502.7  217.07  4524.9  214.44  4545.7  210.89
  4566.7  208.07  4617.5  204.02  4673.4  200.84  4695.7  200.27    4766  200.28
  4887.3  199.06  4901.6  199.09  4955.8  200.82  4971.9  201.58  4979.8  200.01
  4986.3  199.08  4993.7  196.73  5000.4  195.55  5003.6  196.05    5015  200.43
  5021.5  201.76  5093.2  200.39  5185.8   200.6  5230.8   199.8  5314.2  200.25
  5366.4  202.13  5409.8  204.51    5565  210.23  5678.2  216.54  5836.7  222.04
#Mann= 5 ,-1 , 0
    4489     .05       0  4955.8     .12       0  4979.8     .07       0
    5015     .12       0  5230.8     .05       0
Bank Sta=4979.8,5015
XS Rating Curve= 0 ,0
Exp/Cntr=0.3,0.1

Type RM Length L Ch R = 1 ,9001    ,873,873,873
BEGIN DESCRIPTION:
JONES CREEK 13.0
END DESCRIPTION:
XS GIS Cut Line= 3
      3614907.42     10154282.58      3614820.61      10153674.9
      3614992.11     10152591.64
#Sta/Elev= 30
  4045.7  236.45  4107.3  233.98    4178  228.62  4198.2  226.17  4248.7   222.9
  4299.2  217.45  4434.5   204.9  4491.1   200.4  4571.9  197.41  4622.4  197.01
  4731.3  197.78  4784.3  198.73  4794.5  198.37  4804.6  196.52  4845.1  198.64
  4875.5  198.28  4885.6  199.01    4916  198.79  4976.7  199.93  4996.7  194.85
  5021.6  197.87  5027.3  199.25  5037.5  199.56  5138.7  198.17  5211.2   198.7
  5405.8  204.95  5535.5  211.42  5574.1  211.68  5634.8  214.42  5756.3  218.16
#Mann= 6 ,-1 , 0
  4045.7     .16       0  4434.5     .05       0  4731.3     .12       0
  4976.7     .07       0  5037.5     .12       0  5211.2     .05       0
Bank Sta=4976.7,5037.5
XS Rating Curve= 0 ,0
Exp/Cntr=0.3,0.1

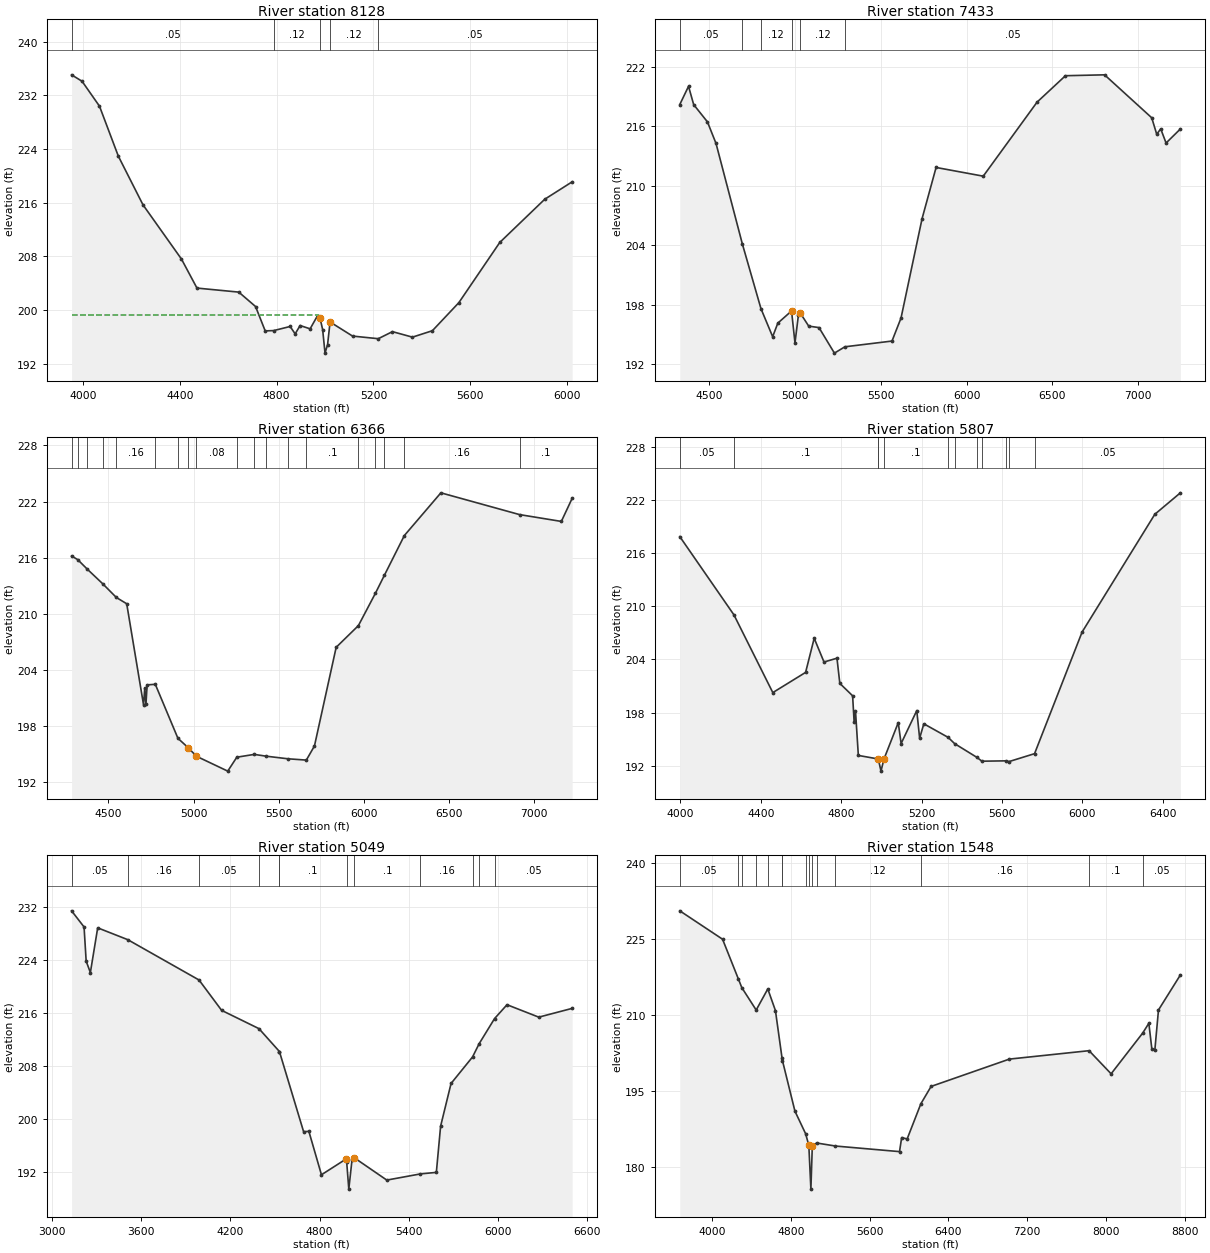
Type RM Length L Ch R = 1 ,8128    ,695,695,695
BEGIN DESCRIPTION:
JONES CREEK 11.0
END DESCRIPTION:
XS GIS Cut Line= 3
      3615092.13      10154441.6      3615515.05     10153813.79
       3615192.1     10152541.62
#Sta/Elev= 30
  3952.3  235.06  3995.7   234.1  4067.7  230.39  4145.7  222.94  4247.6  215.69
  4406.5  207.62  4470.7  203.29  4643.5  202.69    4713  200.54  4752.8  196.91
  4788.2  196.96  4855.9  197.57  4876.6  196.47  4897.2  197.71  4938.5  197.22
  4969.4   199.2  4979.7  198.79  4990.3  197.11  5000.1   193.6  5010.7  194.88
    5021  198.24  5113.9  196.14  5220.2  195.75  5278.9   196.8  5361.5  195.98
    5444  196.94  5553.4  201.12  5722.6  210.09  5908.3  216.52  6021.8  219.12
#Mann= 5 ,-1 , 0
  3952.3     .05       0  4788.2     .12       0  4979.7     .07       0
    5021     .12       0  5220.2     .05       0
#XS Ineff= 2 , 0
         4969.41  199.21
Permanent Ineff=
       F       F
Bank Sta=4979.7,5021
XS Rating Curve= 0 ,0
Exp/Cntr=0.3,0.1

Type RM Length L Ch R = 1 ,7433    ,1067,1067,1067
BEGIN DESCRIPTION:
JONES CREEK 10.0
END DESCRIPTION:
XS GIS Cut Line= 3
      3616035.88     10154282.54      3616009.84     10153180.11
      3615290.06     10151515.07
#Sta/Elev= 30
  4328.8  218.22  4379.7  220.06  4409.7  218.21  4489.7  216.47  4539.8  214.29
  4693.3  204.13  4801.8  197.59  4869.9  194.76  4899.9  196.13  4979.9  197.36
  4999.9  194.13  5019.9  196.94  5029.9  197.17  5079.9  195.83  5139.9  195.68
  5229.7   193.1  5290.8  193.74  5565.2  194.32  5617.7  196.64  5740.6   206.7
  5822.1  211.86  6096.8  210.98  6410.4  218.46  6575.9  221.13  6803.7  221.22
  7078.5  216.88  7107.6  215.22  7130.9  215.76  7162.1  214.33  7245.5  215.75
#Mann= 6 ,-1 , 0
  4328.8     .05       0  4693.3     .16       0  4801.8     .12       0
  4979.9     .07       0  5029.9     .12       0  5290.8     .05       0
Bank Sta=4979.9,5029.9
XS Rating Curve= 0 ,0
Exp/Cntr=0.3,0.1

Type RM Length L Ch R = 1 ,6366    ,559,559,559
BEGIN DESCRIPTION:
JONES CREEK 8.0
END DESCRIPTION:
XS GIS Cut Line= 3
      3616166.09     10154273.86      3616692.11     10153741.64
      3618171.28     10152121.11
#Sta/Elev= 30
  4283.1  216.17  4319.4  215.78  4376.1  214.75  4465.6  213.21  4546.4  211.73
  4607.2  211.06  4706.2  200.24  4713.2  202.04  4720.3  200.32  4727.3  202.38
  4775.3  202.44  4908.3  196.66  4967.8  195.67  5017.3  194.74  5201.1  193.15
  5254.4  194.64  5357.1  194.94  5426.5  194.75    5555  194.47    5663  194.33
  5710.7  195.84  5838.4   206.4    5969  208.72    6069  212.18  6121.9  214.11
  6239.2  218.36  6453.9  222.93  6916.4   220.6  7161.9  219.87  7225.5  222.34
#Mann= 19 ,-1 , 0
  4283.1     .05       0  4319.4     .08       0  4376.1     .05       0
  4465.6      .1       0  4546.4     .16       0  4775.3     .08       0
  4908.3     .08       0  4967.8     .07       0  5017.3     .08       0
  5254.4     .12       0  5357.1     .08       0  5426.5     .12       0
    5555     .12       0    5663      .1       0    5969      .1       0
    6069     .16       0  6121.9      .1       0  6239.2     .16       0
  6916.4      .1       0
Bank Sta=4967.8,5017.3
XS Rating Curve= 0 ,0
Exp/Cntr=0.3,0.1

Type RM Length L Ch R = 1 ,5807    ,758,758,758
BEGIN DESCRIPTION:
JONES CREEK 7.0
END DESCRIPTION:
XS GIS Cut Line= 3
      3616122.69     10154985.67      3616600.12     10154447.47
      3617935.59     10153285.44
#Sta/Elev= 30
  3997.4  217.86  4266.7  209.03    4460  200.26  4623.1  202.54  4665.8  206.39
  4714.6  203.71  4779.1  204.14  4793.3   201.3  4856.9   199.9  4864.6   196.9
  4871.2   198.2  4885.4  193.17  4984.6  192.77  4998.1   191.4  5012.6  192.75
  5083.9  196.87  5098.1  194.51    5176  198.23  5190.2  195.11  5211.1  196.74
  5331.9  195.21  5364.4   194.5  5475.2  192.95  5499.9  192.52  5618.5  192.56
  5635.3  192.48  5761.8  193.37  5998.2  207.09    6360  220.38  6487.1   222.8
#Mann= 12 ,-1 , 0
  3997.4     .05       0  4266.7      .1       0  4984.6     .11       0
  4984.6     .05       0  5012.6      .1       0  5331.9     .05       0
  5364.4     .12       0  5475.2     .05       0  5499.9     .12       0
  5618.5     .05       0  5635.3     .12       0  5761.8     .05       0
Bank Sta=4984.6,5012.6
XS Rating Curve= 0 ,0
Exp/Cntr=0.3,0.1

Type RM Length L Ch R = 1 ,5049    ,3501,3501,3501
BEGIN DESCRIPTION:
JONES CREEK 5.0
END DESCRIPTION:
XS GIS Cut Line= 3
      3615627.91     10156166.21      3616956.02     10154916.22
      3618153.16     10153935.96
#Sta/Elev= 30
  3130.2  231.35  3214.3  228.92  3228.5  223.78  3256.8  222.06  3306.1  228.79
  3508.6  227.01  3988.6  220.94  4140.8  216.37  4392.2  213.62  4529.9  210.18
  4530.3  210.15  4692.7  198.12  4728.3  198.16  4812.9  191.63  4975.2  193.95
  4983.1   193.5  4997.2  189.47  5018.3  193.78  5032.6  194.21    5253  190.83
  5479.7  191.76  5586.7  191.99  5615.4  198.94  5685.8  205.37  5830.5  209.36
  5875.1  211.36  5978.6  215.13  6062.6  217.22  6276.5  215.35  6501.3  216.67
#Mann= 12 ,-1 , 0
  3130.2     .05       0  3508.6     .16       0  3988.6     .05       0
  4392.2     .12       0  4529.9     .05       0  4530.3      .1       0
  4983.1     .05       0  5032.6      .1       0  5479.7     .16       0
  5830.5     .05       0  5875.1     .16       0  5978.6     .05       0
Bank Sta=4975.2,5032.6
XS Rating Curve= 0 ,0
Exp/Cntr=0.3,0.1

Type RM Length L Ch R = 1 ,1548    ,0,0,0
BEGIN DESCRIPTION:
JONES CREEK 1.0
END DESCRIPTION:
XS GIS Cut Line= 3
      3617103.62     10158657.51      3618249.43     10157459.63
      3618813.45     10154075.45
#Sta/Elev= 30
  3669.3  230.63  4103.9  225.03  4265.9  217.13  4299.6  215.48  4445.8  211.06
  4563.7  215.22  4641.4  210.96    4708  201.66  4712.6   201.1  4839.5  191.12
    4948  186.67  4980.8  184.38  5001.9  175.73  5016.3  184.26  5060.6  184.83
  5251.9  184.23  5902.8  183.13  5924.6   185.9  5980.4  185.63  6119.8  192.57
  6223.7  195.99  7019.5  201.38  7829.7  203.04  8053.6  198.48  8374.8  206.52
  8437.2  208.45  8467.7  203.39  8498.1  203.14  8535.1  211.07  8757.8  217.98
#Mann= 15 ,-1 , 0
  3669.3     .05       0  4265.9      .1       0  4299.6     .05       0
  4445.8      .1       0  4563.7     .05       0    4708     .16       0
  4712.6     .05       0    4948      .1       0  4980.8     .05       0
  5016.3      .1       0  5060.6     .07       0  5251.9     .12       0
  6119.8     .16       0  7829.7      .1       0  8374.8     .05       0
Bank Sta=4980.8,5016.3
XS Rating Curve= 0 ,0
Exp/Cntr=0.3,0.1

Chan Stop Cuts=-1
Use User Specified Reach Order=0
Composite Channel Slope=5