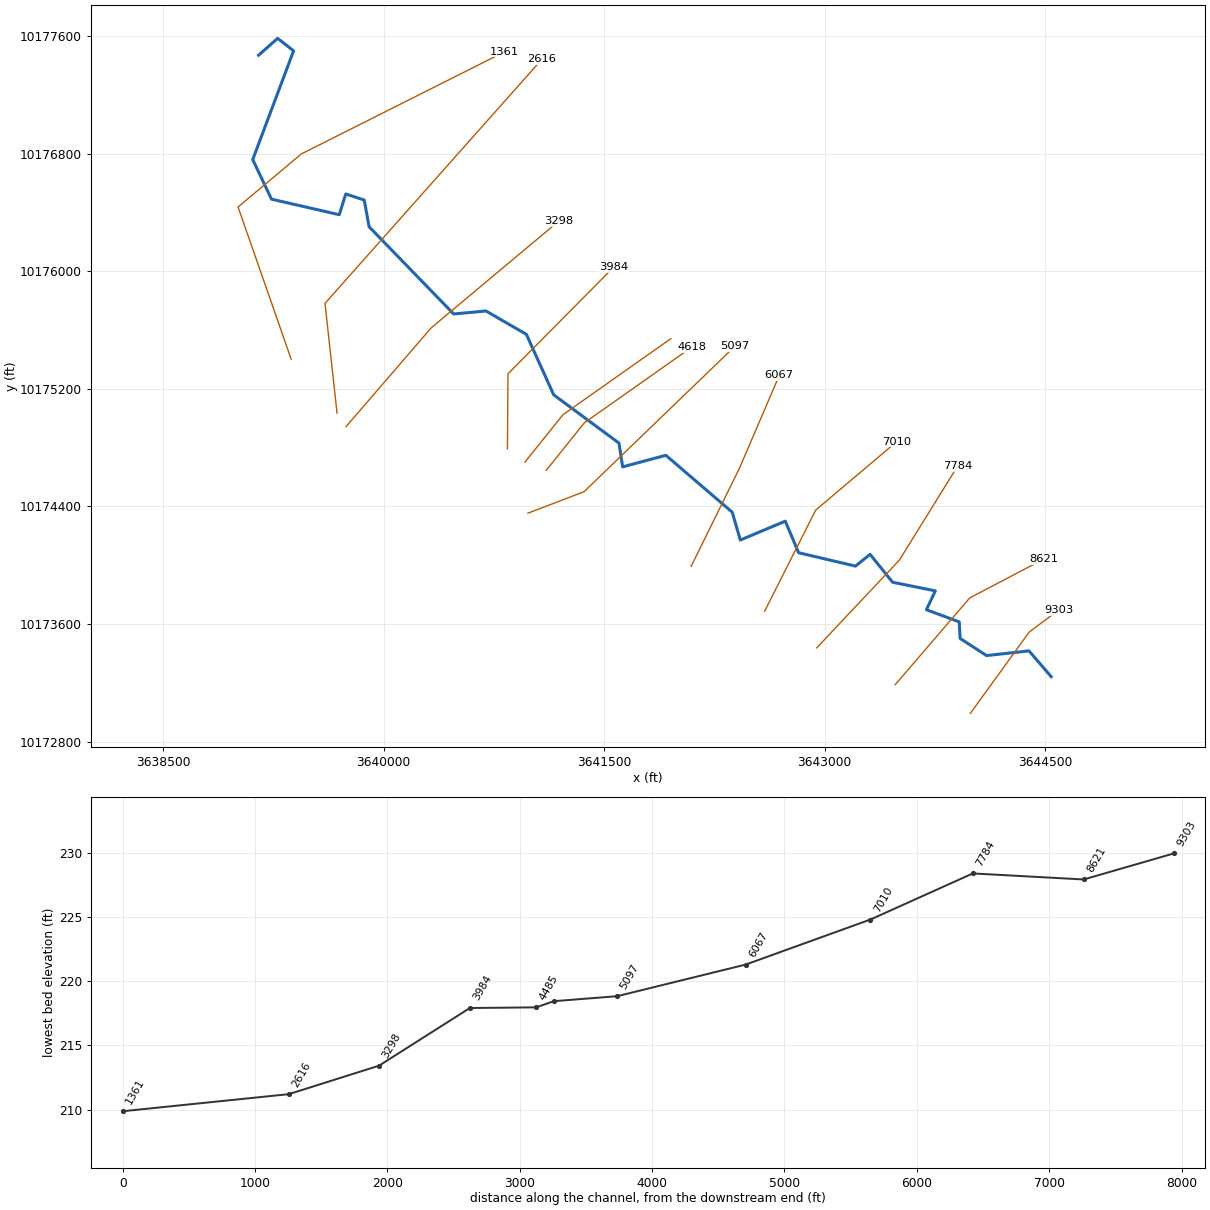
--- LITTLE FLOCK CREEK.prj (project) ---

Proj Title=LITTLE FLOCK CREEK Base Level Engineering
Current Plan=p01
Default Exp/Contr=0.3,0.1
English Units
Geom File=g01
Flow File=f01
Plan File=p01
Y Axis Title=Elevation
X Axis Title(PF)=Main Channel Distance
X Axis Title(XS)=Station
BEGIN DESCRIPTION:
LITTLE FLOCK CREEK
END DESCRIPTION:
DSS Export Rating Curves= 0
DSS Export Rating Curve Sorted= 0
DSS Export Volume Flow Curves= 0
DXF OffsetX= 0
DXF OffsetY= 0
DXF ScaleX= 1
DXF ScaleY= 10

--- LITTLE FLOCK CREEK.p01 (plan) ---

Plan Title=Multiple Run
Short Identifier=Multiple
Geom File=g01
Flow File=f01
Subcritical Flow
K Sum by GR= 0
Std Step Tol= 0.01
Critical Tol= 0.01
Num of Std Step Trials= 20
Max Error Tol= 0.3
Flow Tol Ratio= 0.001
Split Flow NTrial= 30
Split Flow Tol= 0.02
Split Flow Ratio= 0.02
Log Output Level= 0
Friction Slope Method= 1
Unsteady Friction Slope Method= 2
Unsteady Bridges Friction Slope Method= 1
Parabolic Critical Depth
Global Vel Dist=  1 , 1 , 1
Global Log Level= 0
CheckData=True
Encroach Param= -1, 0, 0, 0
BEGIN DESCRIPTION:
Multiple Run
END DESCRIPTION:

--- LITTLE FLOCK CREEK.f01 (steady flow) ---

Flow Title=Multiple
Program Version=4.10
Number of Profiles= 7
Profile Names=10-year,25-year,50-year,1pct_min,100-year,1pct_plu,500-year
River Rch & RM=LITTLE FLOCK CRE,Reach-1         ,9303
     882    1219    1500    1353    1830    2475    2729
River Rch & RM=LITTLE FLOCK CRE,Reach-1         ,5097
    1054    1466    1814    1643    2222    3006    3341
River Rch & RM=LITTLE FLOCK CRE,Reach-1         ,4618
    1054    1466    1814    1643    2222    3006    3341
River Rch & RM=LITTLE FLOCK CRE,Reach-1         ,3298
    1178    1645    2040    1851    2503    3386    3777
River Rch & RM=LITTLE FLOCK CRE,Reach-1         ,1361
    1178    1645    2040    1851    2503    3386    3777
Boundary for River Rch & Prof#=LITTLE FLOCK CRE,Reach-1         , 1
Up Type= 0
Dn Type= 3
Dn Slope=0.005
Boundary for River Rch & Prof#=LITTLE FLOCK CRE,Reach-1         , 2
Up Type= 0
Dn Type= 3
Dn Slope=0.005
Boundary for River Rch & Prof#=LITTLE FLOCK CRE,Reach-1         , 3
Up Type= 0
Dn Type= 3
Dn Slope=0.005
Boundary for River Rch & Prof#=LITTLE FLOCK CRE,Reach-1         , 4
Up Type= 0
Dn Type= 3
Dn Slope=0.005
Boundary for River Rch & Prof#=LITTLE FLOCK CRE,Reach-1         , 5
Up Type= 0
Dn Type= 3
Dn Slope=0.005
Boundary for River Rch & Prof#=LITTLE FLOCK CRE,Reach-1         , 6
Up Type= 0
Dn Type= 3
Dn Slope=0.005
Boundary for River Rch & Prof#=LITTLE FLOCK CRE,Reach-1         , 7
Up Type= 0
Dn Type= 3
Dn Slope=0.005
DSS Import GetInterval= 0
DSS Import GetPeak= 0
DSS Import FillOption= 0

--- LITTLE FLOCK CREEK.g01 (geometry) ---

Geom Title=Existing Conditions
Program Version=4.10

River Reach=LITTLE FLOCK CRE,Reach-1
Reach XY= 30
      3644542.11     10173241.64      3644390.79     10173416.97
      3644102.59     10173384.86      3643922.47     10173501.61
      3643916.39     10173614.02      3643693.18     10173697.06
      3643753.85     10173825.27      3643463.06     10173883.98
       3643309.7     10174073.93      3643210.55     10173993.81
      3642823.49     10174084.82      3642732.76     10174299.57
      3642426.95     10174171.23      3642371.72     10174360.58
      3641920.07     10174747.86      3641626.16     10174668.99
      3641601.11     10174830.78       3641157.1     10175158.95
      3640971.11     10175570.68      3640696.23     10175729.71
      3640476.35     10175709.35      3639900.74     10176302.93
      3639867.56     10176484.88      3639742.04     10176526.02
      3639697.77     10176384.88      3639236.61     10176490.66
      3639108.98     10176760.02      3639386.96     10177499.95
      3639278.45     10177585.02      3639149.25     10177470.46

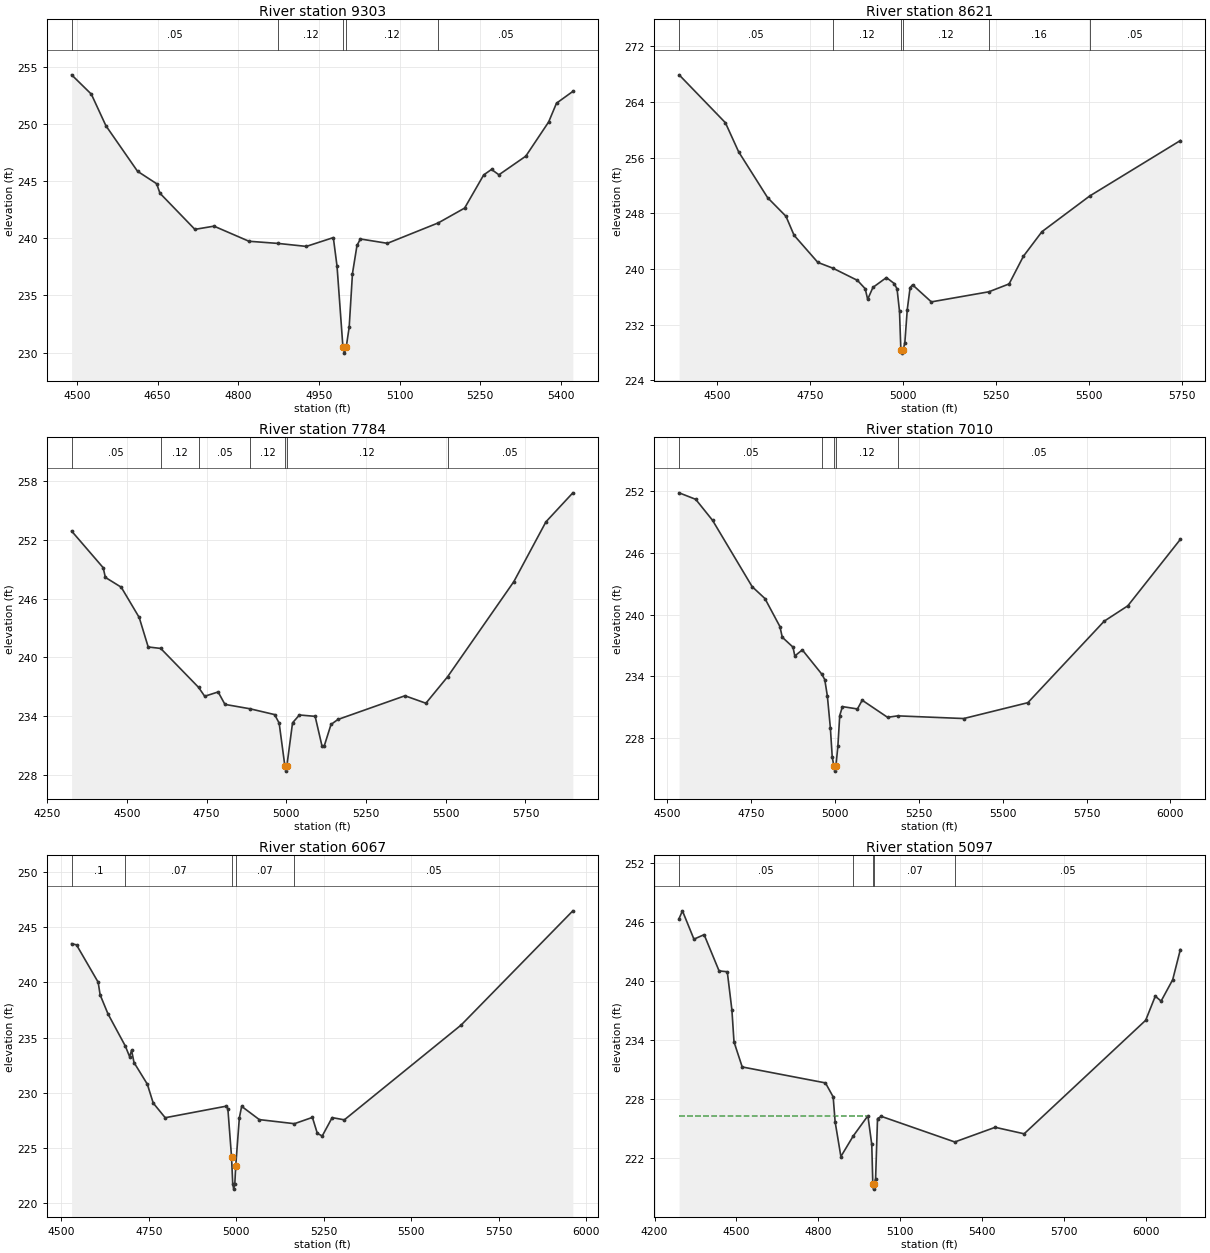
Type RM Length L Ch R = 1 ,9303    ,682,682,682
BEGIN DESCRIPTION:
LITTLE FLOCK CREEK 13.0
END DESCRIPTION:
XS GIS Cut Line= 3
      3643992.11     10172991.65      3644392.11     10173544.42
       3644592.1     10173694.41
#Sta/Elev= 30
    4490  254.28  4526.7  252.59  4553.8  249.83  4612.6  245.85  4648.2  244.76
  4654.3  243.93  4719.3  240.77  4754.9  241.05  4819.9  239.73  4874.2  239.54
  4926.6  239.28  4976.8  240.05  4983.7  237.55  4994.7  230.45  4997.5  229.95
  5000.7  230.45  5006.3  232.22  5012.4  236.91  5020.8  239.36  5027.1  239.93
  5077.4  239.55  5172.2  241.34    5221  242.63  5256.5  245.53    5271  246.01
  5284.8  245.54  5334.8  247.17  5377.3  250.16  5391.9   251.8  5422.3  252.83
#Mann= 5 ,-1 , 0
    4490     .05       0  4874.2     .12       0  4994.7     .07       0
  5000.7     .12       0  5172.2     .05       0
Bank Sta=4994.7,5000.7
XS Rating Curve= 0 ,0
Exp/Cntr=0.3,0.1

Type RM Length L Ch R = 1 ,8621    ,837,837,837
BEGIN DESCRIPTION:
LITTLE FLOCK CREEK 11.0
END DESCRIPTION:
XS GIS Cut Line= 3
      3643481.29     10173187.28      3643988.26     10173777.59
      3644492.13     10174041.66
#Sta/Elev= 30
  4397.5  267.89  4521.9  261.01  4557.4  256.84  4635.3  250.25  4684.7  247.57
  4706.4  244.85  4770.3  240.95  4810.8  240.12  4876.7  238.37  4897.6  237.17
  4904.2  235.65  4918.4  237.36  4954.6  238.77  4975.5  237.92  4983.2  237.14
  4989.8  233.91  4993.4  228.42  4996.2  227.92  4999.4  228.42    5004  229.34
  5010.6  234.17  5018.3  237.34  5024.9  237.73  5075.3  235.28  5229.9  236.73
  5284.3  237.86  5322.7  241.83  5372.5  245.36  5500.7  250.48  5744.5  258.45
#Mann= 6 ,-1 , 0
  4397.5     .05       0  4810.8     .12       0  4993.4     .07       0
  4999.4     .12       0  5229.9     .16       0  5500.7     .05       0
Bank Sta=4993.4,4999.4
XS Rating Curve= 0 ,0
Exp/Cntr=0.3,0.1

Type RM Length L Ch R = 1 ,7784    ,774,774,774
BEGIN DESCRIPTION:
LITTLE FLOCK CREEK 10.0
END DESCRIPTION:
XS GIS Cut Line= 3
      3642946.63     10173437.34       3643509.1     10174034.53
      3643904.91     10174673.38
#Sta/Elev= 30
  4326.6  252.89  4425.6  249.15  4432.5  248.16  4482.2  247.16  4538.6  244.07
  4566.8  241.06  4606.1  240.91  4724.7  236.94    4744  236.03  4786.1  236.47
  4807.5   235.2  4886.4  234.75  4963.3  234.16  4977.5  233.29  4995.5  228.89
  4998.2  228.39  5001.5  228.89  5019.5  233.32    5041  234.12  5090.3  233.98
  5111.8  230.96  5118.6  230.93  5140.1  233.15  5161.7  233.66    5372  236.08
  5437.7  235.32  5505.5  238.01  5713.5  247.73  5814.1  253.83  5898.5  256.79
#Mann= 7 ,-1 , 0
  4326.6     .05       0  4606.1     .12       0  4724.7     .05       0
  4886.4     .12       0  4995.5     .07       0  5001.5     .12       0
  5505.5     .05       0
Bank Sta=4995.5,5001.5
XS Rating Curve= 0 ,0
Exp/Cntr=0.3,0.1

Type RM Length L Ch R = 1 ,7010    ,943,943,943
BEGIN DESCRIPTION:
LITTLE FLOCK CREEK 9.0
END DESCRIPTION:
XS GIS Cut Line= 3
      3642592.42     10173687.29      3642939.65     10174374.81
       3643492.1     10174841.64
#Sta/Elev= 30
  4536.1  251.84  4585.5  251.21  4635.7  249.17  4753.8  242.72  4791.8  241.57
  4836.4  238.85  4843.5  237.81  4875.3  236.85  4880.9  235.99  4903.2  236.58
  4961.1  234.23  4970.1  233.69  4977.9  232.08  4986.8  228.99  4992.4  226.15
  4997.3   225.3    5000   224.8  5003.3   225.3  5009.1   227.2  5014.7   230.2
  5022.7  231.07  5067.5  230.84  5081.6  231.69  5157.1  230.03  5187.6  230.17
  5384.1  229.91  5575.2  231.45  5802.7  239.37    5873  240.86  6029.6  247.32
#Mann= 5 ,-1 , 0
  4536.1     .05       0  4961.1     .12       0  4997.3     .07       0
  5003.3     .12       0  5187.6     .05       0
Bank Sta=4997.3,5003.3
XS Rating Curve= 0 ,0
Exp/Cntr=0.3,0.1

Type RM Length L Ch R = 1 ,6067    ,970,970,970
BEGIN DESCRIPTION:
LITTLE FLOCK CREEK 8.0
END DESCRIPTION:
XS GIS Cut Line= 3
      3642092.09     10173991.62      3642422.27     10174662.55
      3642692.11     10175291.65
#Sta/Elev= 30
  4529.5   243.5  4543.5  243.39  4605.4  240.01    4611  238.87  4633.4  237.15
  4683.1  234.23  4695.3  233.27  4700.8  233.85  4707.9  232.74  4745.8  230.79
  4762.7  229.08    4797  227.75  4970.5  228.79    4976  228.57  4986.5  224.22
  4989.9  221.79  4992.7  221.29  4995.9  221.79  4998.5  223.39  5008.8  227.73
  5015.4  228.78  5065.9  227.58  5166.2  227.21  5217.6  227.78  5231.7  226.33
  5245.7   226.1    5274  227.76  5308.9  227.56  5642.7  236.14  5961.8  246.47
#Mann= 5 ,-1 , 0
  4529.5      .1       0  4683.1     .07       0  4986.5    .035       0
  4998.5     .07       0  5166.2     .05       0
Bank Sta=4986.5,4998.5
XS Rating Curve= 0 ,0
Exp/Cntr=0.3,0.1

Type RM Length L Ch R = 1 ,5097    ,479,479,479
BEGIN DESCRIPTION:
LITTLE FLOCK CREEK 7.0
END DESCRIPTION:
XS GIS Cut Line= 3
      3640981.31     10174353.97      3641363.26     10174499.81
      3642392.09     10175491.63
#Sta/Elev= 30
  4289.8  246.32    4302   247.1  4344.2  244.22  4381.5  244.68  4436.3     241
  4466.4  240.91  4483.3  237.05  4491.1  233.78  4521.2  231.24  4826.4  229.62
  4854.7   228.2  4861.9  225.66    4883  222.14  4928.1  224.22    4982  226.28
  4996.2  223.37  5000.1  219.33  5002.9  218.83  5006.1  219.33  5010.3  219.89
  5017.3     226  5031.4  226.22  5300.6  223.62  5448.7  225.11  5554.9  224.45
  6000.5  235.98  6035.8  238.43  6057.1  237.93  6099.6   240.1  6127.7  243.17
#Mann= 5 ,-1 , 0
  4289.8     .05       0  4928.1     .07       0  5000.1    .035       0
  5006.1     .07       0  5300.6     .05       0
#XS Ineff= 2 , 0
         4982.24  226.27
Permanent Ineff=
       F       F
Bank Sta=5000.1,5006.1
XS Rating Curve= 0 ,0
Exp/Cntr=0.3,0.1

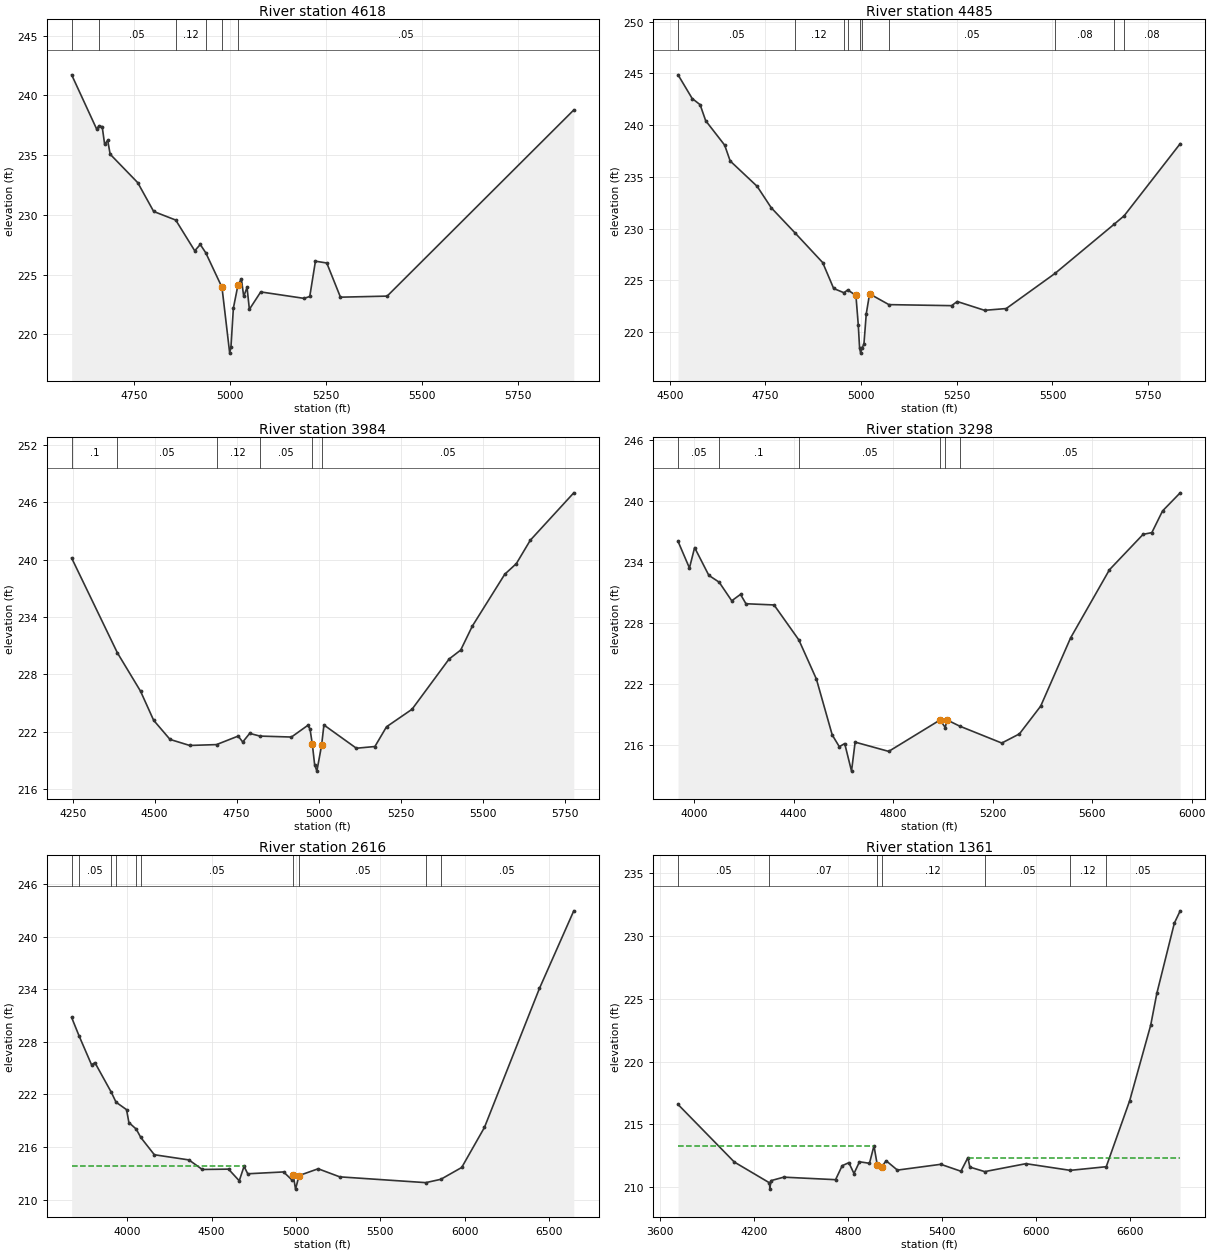
Type RM Length L Ch R = 1 ,4618    ,133,133,133
BEGIN DESCRIPTION:
LITTLE FLOCK CREEK 6.0
END DESCRIPTION:
XS GIS Cut Line= 3
      3641106.33     10174645.66      3641365.42     10174968.43
      3642098.28     10175485.15
#Sta/Elev= 30
  4586.1  241.72  4651.4  237.18  4656.8  237.43  4665.8  237.39  4672.2  235.91
  4680.2  236.24  4686.6  235.08  4758.6   232.7  4800.2  230.29  4857.8  229.57
  4907.4     227  4921.8  227.53  4936.2  226.83  4978.5  223.94  4998.6  218.44
  5001.9  218.94  5008.2   222.2  5020.4  224.16  5029.1  224.65  5035.2  223.18
  5043.9  223.94    5050   222.1  5079.6  223.56  5192.8  223.02  5207.6  223.18
  5222.4  226.13    5252  225.98  5287.7  223.12  5409.6  223.21  5896.7  238.78
#Mann= 6 ,-1 , 0
  4586.1     .08       0  4656.8     .05       0  4857.8     .12       0
  4936.2     .05       0  4978.5    .035       0  5020.4     .05       0
Bank Sta=4978.5,5020.4
XS Rating Curve= 0 ,0
Exp/Cntr=0.3,0.1

Type RM Length L Ch R = 1 ,4485    ,501,501,501
BEGIN DESCRIPTION:
LITTLE FLOCK CREEK 5.0
END DESCRIPTION:
XS GIS Cut Line= 3
      3640961.16     10174701.36      3641220.25     10175024.13
      3641954.17      10175541.6
#Sta/Elev= 30
  4521.7  244.87  4558.6  242.58  4579.4  241.98  4593.8  240.44  4643.5  238.07
  4657.9  236.54  4728.3  234.09  4765.1  232.02  4826.7  229.61  4899.5  226.72
  4928.3  224.21  4955.1   223.8    4965  224.07  4986.4  223.54  4992.5  220.72
    4996  218.46  4998.8  217.96    5002  218.46  5007.3  218.81  5013.4  221.75
  5022.1  223.69  5072.6  222.65  5236.3  222.55  5251.1  222.95  5322.5   222.1
  5379.1  222.27  5506.7  225.67  5660.3   230.4  5687.2  231.24  5833.6  238.21
#Mann= 10 ,-1 , 0
  4521.7     .05       0  4826.7     .12       0  4955.1     .05       0
    4965     .12       0    4996     .07       0    5002     .12       0
  5072.6     .05       0  5506.7     .08       0  5660.3     .05       0
  5687.2     .08       0
Bank Sta=4986.4,5022.1
XS Rating Curve= 0 ,0
Exp/Cntr=0.3,0.1

Type RM Length L Ch R = 1 ,3984    ,686,686,686
BEGIN DESCRIPTION:
LITTLE FLOCK CREEK 4.0
END DESCRIPTION:
XS GIS Cut Line= 3
      3640842.11     10174791.69      3640845.86      10175302.4
      3641564.17      10176027.1
#Sta/Elev= 30
  4246.9  240.16  4386.4  230.26  4456.9  226.26  4496.9  223.22  4546.9  221.22
  4606.9  220.59  4688.6  220.68  4754.7  221.57  4768.6  220.95  4789.8  221.85
  4821.1  221.57  4917.1  221.47  4966.6  222.68  4973.6  222.33  4980.7  220.75
  4987.8  218.59  4994.6  217.91    5009  220.59  5016.1  222.73  5115.1   220.3
  5171.6  220.48    5207  222.54  5284.8  224.37  5397.9  229.62  5433.2  230.55
  5468.6  233.05  5567.6  238.47  5602.9  239.58  5645.4  242.02    5778  246.97
#Mann= 6 ,-1 , 0
  4246.9      .1       0  4386.4     .05       0  4688.6     .12       0
  4821.1     .05       0  4980.7    .035       0    5009     .05       0
Bank Sta=4980.7,5009
XS Rating Curve= 0 ,0
Exp/Cntr=0.3,0.1

Type RM Length L Ch R = 1 ,3298    ,682,682,682
BEGIN DESCRIPTION:
LITTLE FLOCK CREEK 3.0
END DESCRIPTION:
XS GIS Cut Line= 3
      3639745.22     10174944.27      3640323.64     10175615.36
      3641192.11     10176341.65
#Sta/Elev= 30
  3935.9     236  3981.7  233.38  4002.5  235.39  4059.6  232.66  4101.1  231.99
  4151.7  230.16  4186.9  230.79  4208.8  229.87  4321.8  229.75  4421.5  226.31
  4491.9  222.47  4555.5  216.98    4584  215.82  4605.7  216.13  4633.1  213.42
  4647.6  216.27  4782.6  215.36  4989.1  218.45  5009.9   217.7  5016.4  218.46
  5067.1  217.85    5237  216.18  5307.9  217.08  5393.4  219.81  5513.5  226.51
  5669.7  233.21    5805  236.69  5840.1  236.86  5883.1  238.99    5954  240.77
#Mann= 6 ,-1 , 0
  3935.9     .05       0  4101.1      .1       0  4421.5     .05       0
  4989.1    .035       0  5009.9     .05       0  5067.1     .05       0
#Block Obstruct= 2 , 0
         4977.14  217.68 5030.22          217.69
Bank Sta=4989.1,5016.4
XS Rating Curve= 0 ,0
Exp/Cntr=0.3,0.1

Type RM Length L Ch R = 1 ,2616    ,1255,1255,1255
BEGIN DESCRIPTION:
LITTLE FLOCK CREEK 2.0
END DESCRIPTION:
XS GIS Cut Line= 3
       3639682.7     10175034.56      3639600.76     10175781.69
      3641077.81     10177443.43
#Sta/Elev= 30
  3671.1  230.77  3714.9  228.68  3788.9  225.38    3809  225.62  3906.1  222.24
  3934.1  221.11  3996.4  220.26  4010.2  218.79  4053.5  218.05  4080.8  217.09
  4161.1  215.12  4365.9  214.53    4445  213.44  4600.5  213.48  4664.1  212.15
  4692.5   213.8  4714.3  212.95  4926.7  213.16    4976  212.25  4983.5  212.83
  4997.5   211.2  5018.7  212.75  5131.7  213.52  5259.5   212.6  5769.1  211.94
  5858.3  212.32    5982  213.67  6116.6  218.23  6442.7  234.09    6646  242.93
#Mann= 10 ,-1 , 0
  3671.1      .1       0  3714.9     .05       0  3906.1      .1       0
  3934.1     .05       0  4053.5     .16       0  4080.8     .05       0
  4983.5    .035       0  5018.7     .05       0  5769.1     .12       0
  5858.3     .05       0
#XS Ineff= 2 , 0
         4691.01   213.8
Permanent Ineff=
       F       F
Bank Sta=4983.5,5018.7
XS Rating Curve= 0 ,0
Exp/Cntr=0.3,0.1

Type RM Length L Ch R = 1 ,1361    ,0,0,0
BEGIN DESCRIPTION:
LITTLE FLOCK CREEK 1.0
END DESCRIPTION:
XS GIS Cut Line= 4
      3639370.22     10175402.55       3639009.1     10176437.31
      3639439.65     10176798.42      3640821.58     10177492.86
#Sta/Elev= 30
  3714.7  216.59  4073.8  212.02  4298.2  210.37  4300.9  209.87  4306.9  210.54
  4389.1  210.82  4719.9  210.62  4762.3  211.73  4804.7  211.97  4837.5  211.11
  4872.6  212.04  4936.3  211.92    4965  213.31  4985.8  211.81  5014.4  211.65
    5043  212.12  5114.6  211.38  5391.5  211.84  5519.9  211.29  5564.5  212.37
  5576.8  211.62  5671.9  211.26  5934.9  211.89  6217.8  211.36  6447.4  211.65
  6597.2   216.9  6731.2  222.89  6770.2  225.41  6881.9  230.98  6919.2  231.96
#Mann= 7 ,-1 , 0
  3714.7     .05       0  4298.2     .07       0  4985.8     .05       0
  5014.4     .12       0  5671.9     .05       0  6217.8     .12       0
  6447.4     .05       0
#XS Ineff= 2 , 0
         4965.37  213.32 5565.11          212.37
Permanent Ineff=
       F       F
Bank Sta=4985.8,5014.4
XS Rating Curve= 0 ,0
Exp/Cntr=0.3,0.1

Chan Stop Cuts=-1
Use User Specified Reach Order=0
Composite Channel Slope=5