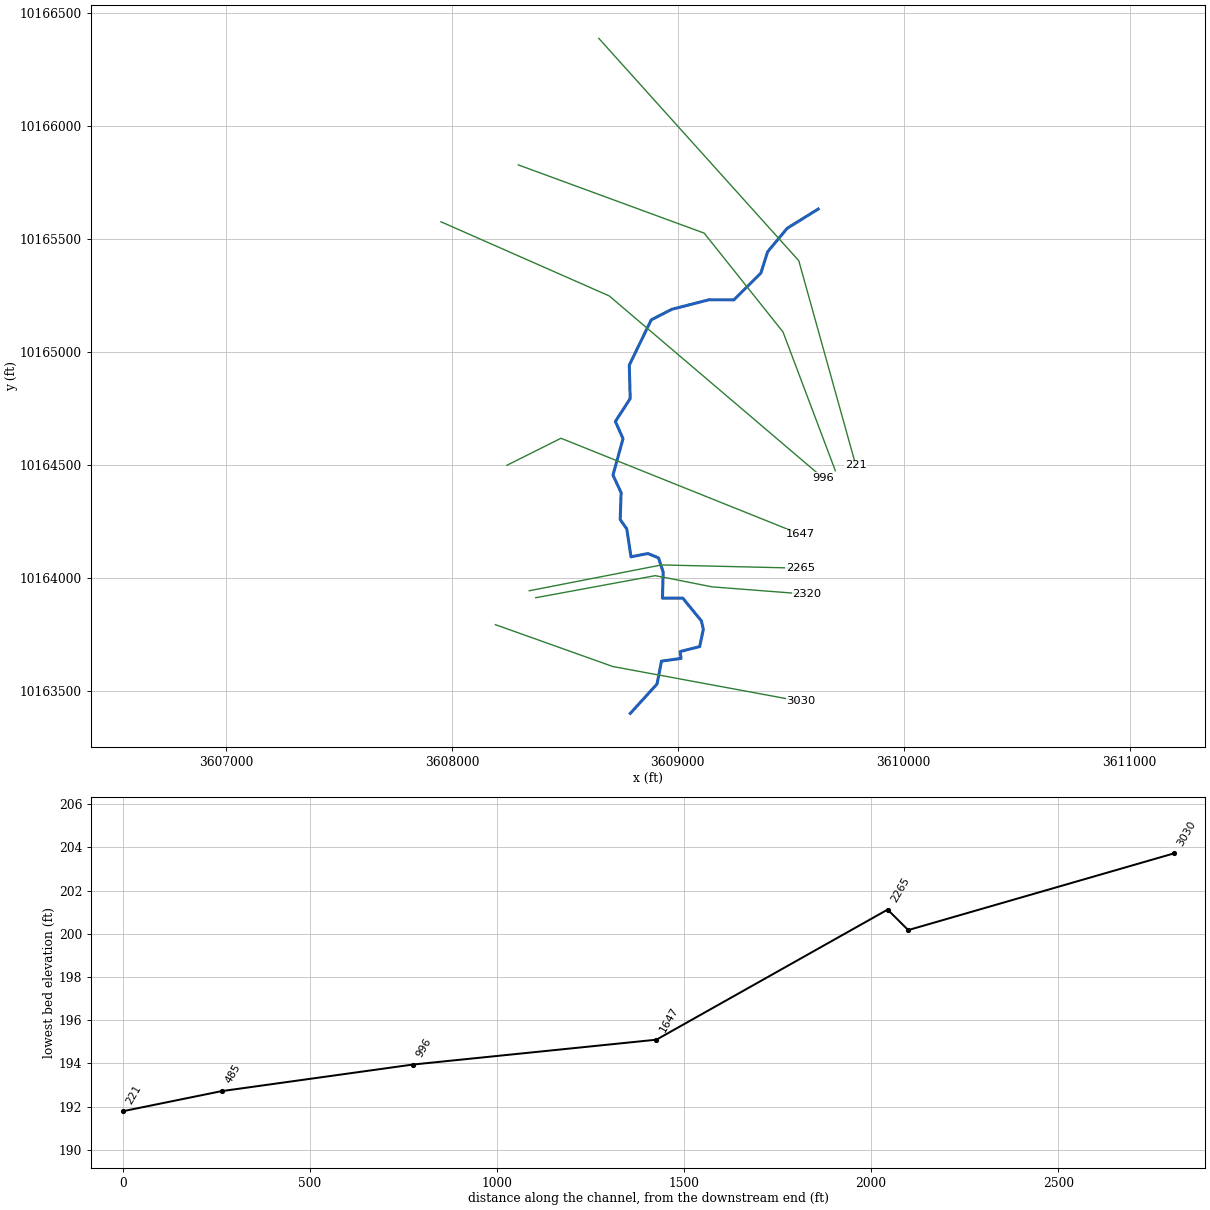
--- MILLICAN CREEK TRIB 2.prj (project) ---

Proj Title=MILLICAN CREEK TRIB 2 Base Level Engineering
Current Plan=p01
Default Exp/Contr=0.3,0.1
English Units
Geom File=g01
Flow File=f01
Plan File=p01
Y Axis Title=Elevation
X Axis Title(PF)=Main Channel Distance
X Axis Title(XS)=Station
BEGIN DESCRIPTION:
MILLICAN CREEK TRIB 2
END DESCRIPTION:
DSS Export Rating Curves= 0
DSS Export Rating Curve Sorted= 0
DSS Export Volume Flow Curves= 0
DXF OffsetX= 0
DXF OffsetY= 0
DXF ScaleX= 1
DXF ScaleY= 10

--- MILLICAN CREEK TRIB 2.p01 (plan) ---

Plan Title=Multiple Run
Short Identifier=Multiple
Geom File=g01
Flow File=f01
Subcritical Flow
K Sum by GR= 0
Std Step Tol= 0.01
Critical Tol= 0.01
Num of Std Step Trials= 20
Max Error Tol= 0.3
Flow Tol Ratio= 0.001
Split Flow NTrial= 30
Split Flow Tol= 0.02
Split Flow Ratio= 0.02
Log Output Level= 0
Friction Slope Method= 1
Unsteady Friction Slope Method= 2
Unsteady Bridges Friction Slope Method= 1
Parabolic Critical Depth
Global Vel Dist=  1 , 1 , 1
Global Log Level= 0
CheckData=True
Encroach Param= -1, 0, 0, 0
BEGIN DESCRIPTION:
Multiple Run
END DESCRIPTION:

--- MILLICAN CREEK TRIB 2.f01 (steady flow) ---

Flow Title=Multiple
Number of Profiles=7
Profile Names=10-year,25-year,50-year,1pct_min,100-year,1pct_plu,500-year
River Rch & RM= MILLICAN CREEK T,Reach-1,3030
     840    1156    1419    1276    1726    2334    2556
Boundary for River Rch & Prof#=MILLICAN CREEK T,Reach-1,1
Up Type=0
Dn Type=3
Dn Slope=0.005
Boundary for River Rch & Prof#=MILLICAN CREEK T,Reach-1,2
Up Type=0
Dn Type=3
Dn Slope=0.005
Boundary for River Rch & Prof#=MILLICAN CREEK T,Reach-1,3
Up Type=0
Dn Type=3
Dn Slope=0.005
Boundary for River Rch & Prof#=MILLICAN CREEK T,Reach-1,4
Up Type=0
Dn Type=3
Dn Slope=0.005
Boundary for River Rch & Prof#=MILLICAN CREEK T,Reach-1,5
Up Type=0
Dn Type=3
Dn Slope=0.005
Boundary for River Rch & Prof#=MILLICAN CREEK T,Reach-1,6
Up Type=0
Dn Type=3
Dn Slope=0.005
Boundary for River Rch & Prof#=MILLICAN CREEK T,Reach-1,7
Up Type=0
Dn Type=3
Dn Slope=0.005

--- MILLICAN CREEK TRIB 2.g01 (geometry) ---

Geom Title=Existing Conditions
Program Version=4.10

River Reach=MILLICAN CREEK T,Reach-1
Reach XY= 30
      3608789.64     10163398.83      3608907.87     10163529.04
      3608927.47     10163630.16      3609014.27      10163642.1
      3609009.93     10163672.48       3609096.8     10163694.45
      3609112.75     10163771.74      3609104.21     10163808.11
      3609021.87     10163909.02      3608931.81     10163909.02
      3608935.06     10164024.04      3608914.45     10164086.97
      3608867.79     10164106.51      3608792.58     10164091.84
      3608773.98     10164214.73      3608744.74     10164257.32
      3608748.78     10164376.02      3608712.73     10164453.65
      3608757.28     10164614.83      3608723.49      10164691.2
      3608789.03     10164792.56      3608784.97     10164940.35
      3608882.12     10165141.01      3608973.66     10165187.87
      3609137.97      10165229.9      3609248.47     10165229.64
      3609367.67     10165348.36       3609397.3     10165442.23
      3609484.11     10165546.39      3609621.34     10165631.53

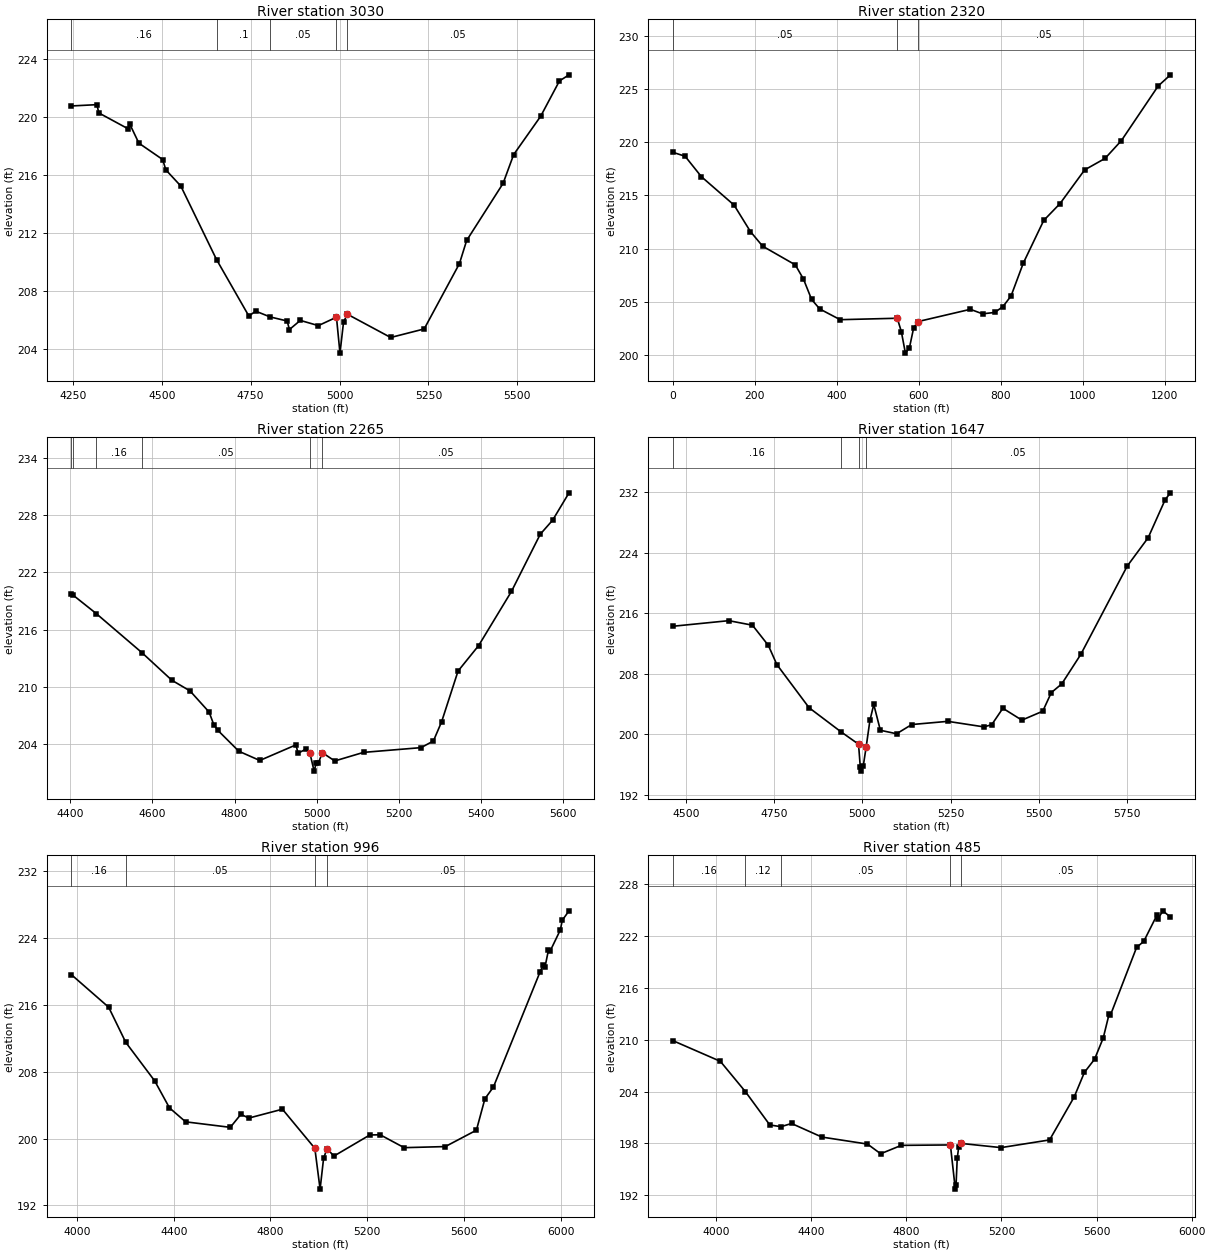
Type RM Length L Ch R = 1 ,3030    ,710,710,710
BEGIN DESCRIPTION:
MILLICAN CREEK TRIB 2 7.0
END DESCRIPTION:
XS GIS Cut Line= 3
       3608192.1     10163791.64       3608711.7     10163606.34
      3609545.19     10163452.07
#Sta/Elev= 30
  4246.1  220.79  4317.8  220.88  4323.1  220.31  4404.9  219.22  4410.3  219.53
  4435.8  218.22  4502.7  217.09  4511.5  216.38  4553.7  215.26  4654.2  210.18
  4745.1  206.28  4764.1  206.62  4804.9  206.22  4852.6  205.94  4859.2  205.35
  4889.7  205.98  4940.5  205.62  4991.4   206.2  5001.3  203.72  5011.3  205.86
  5021.9  206.41  5143.9   204.8  5238.1  205.39  5337.2   209.9  5357.5   211.5
  5459.9  215.44  5489.7  217.43  5565.7  220.08  5618.5  222.52  5645.4  222.94
#Mann= 5 ,-1 , 0
  4246.1     .16       0  4654.2      .1       0  4804.9     .05       0
  4991.4    .035       0  5021.9     .05       0
Bank Sta=4991.4,5021.9
XS Rating Curve= 0 ,0
Exp/Cntr=0.3,0.1

Type RM Length L Ch R = 1 ,2320    ,55,55,55
XS GIS Cut Line= 5
     3608370.927    10163910.815     3608899.573    10164008.471
      3608954.26    10163998.054     3609150.875    10163958.992
     3609571.448     10163926.44
#Sta/Elev= 30
       0219.061829.86612218.690869.68761216.7668149.3306214.0971189.1521211.6116
219.0182210.2319298.6612208.4756318.5719 207.141338.4827205.2205358.3934 204.324
408.1703203.3175547.4935203.4531557.3969202.1905567.3003200.1717577.2037200.6911
587.1071202.4922597.0105203.1309725.7546204.2932755.4648203.8674 785.175203.9991
805.0491204.5434824.9904 205.545854.9024208.6401904.7557 212.656944.6384214.2441
1004.462217.40451054.316218.48661094.198220.16421183.935225.30131213.847226.3492
#Mann= 3 ,-1 , 0
       0     .05       0547.4935    .035       0597.0105     .05       0
Bank Sta=547.4935,597.0105
XS Rating Curve= 0 ,0
Exp/Cntr=0.3,0.1

Type RM Length L Ch R = 1 ,2265    ,618,618,618
BEGIN DESCRIPTION:
MILLICAN CREEK TRIB 2 5.0
END DESCRIPTION:
XS GIS Cut Line= 3
      3608342.15     10163941.65      3608927.77     10164055.98
      3609542.12     10164041.64
#Sta/Elev= 30
  4402.8  219.69  4406.2  219.64  4463.2  217.68  4574.7  213.56  4647.3  210.67
  4691.5  209.55  4737.9  207.33  4749.2  206.02  4759.4   205.4  4810.3  203.21
  4861.3  202.24  4949.3  203.88  4954.4     203  4973.3  203.43  4983.5  202.98
  4993.5  201.12  4999.1  202.02  5004.1  202.02  5013.8  203.05  5043.8  202.19
  5113.8  203.09  5253.9  203.59  5283.9  204.29  5303.9  206.31  5343.9  211.64
  5393.9  214.31  5473.9  220.01    5544  226.02    5574  227.49    5614  230.37
#Mann= 6 ,-1 , 0
  4402.8     .16       0  4406.2      .1       0  4463.2     .16       0
  4574.7     .05       0  4983.5    .035       0  5013.8     .05       0
Bank Sta=4983.5,5013.8
XS Rating Curve= 0 ,0
Exp/Cntr=0.3,0.1

Type RM Length L Ch R = 1 ,1647    ,651,651,651
BEGIN DESCRIPTION:
MILLICAN CREEK TRIB 2 3.0
END DESCRIPTION:
XS GIS Cut Line= 3
      3608242.96     10164496.98      3608482.53     10164616.76
      3609542.09     10164191.65
#Sta/Elev= 30
  4463.4  214.25  4621.9  214.99  4688.9  214.39  4733.9  211.72  4758.1  209.18
  4849.3  203.48    4939  200.32  4989.4  198.66  4994.4   195.6  4997.2   195.1
  5002.8   195.8  5010.9  198.27  5021.6   201.8  5032.5  203.91  5051.2   200.5
  5097.1  200.04  5140.2  201.26  5242.2  201.68  5344.4  200.95  5366.5  201.23
  5398.2  203.41    5452  201.84  5511.2  203.02  5535.4  205.48    5565  206.63
  5618.8  210.52  5750.5  222.21  5809.7  225.95  5858.1     231  5872.9  231.89
#Mann= 4 ,-1 , 0
  4463.4     .16       0    4939     .05       0  4989.4    .035       0
  5010.9     .05       0
Bank Sta=4989.4,5010.9
XS Rating Curve= 0 ,0
Exp/Cntr=0.3,0.1

Type RM Length L Ch R = 1 ,996     ,511,511,511
BEGIN DESCRIPTION:
MILLICAN CREEK TRIB 2 2.0
END DESCRIPTION:
XS GIS Cut Line= 3
      3607951.27      10165575.1      3608696.08     10165246.97
      3609642.12     10164441.63
#Sta/Elev= 30
  3977.4   219.6  4131.3  215.71  4201.9  211.51  4321.7  206.89  4382.6  203.67
  4449.3     202    4634  201.34  4677.7   202.9  4710.5  202.45  4849.3  203.51
  4983.3  198.83    5005  193.95  5019.5  197.64  5033.8   198.8  5061.9   197.9
  5210.6  200.43  5253.4  200.45  5352.3  198.91  5522.5  199.04    5651     201
  5686.1  204.76  5721.2  206.16  5913.4  219.89  5927.7  220.81  5934.3   220.5
  5948.6  222.54  5955.1  222.39    5998  224.97  6005.7  226.11  6033.7  227.24
#Mann= 4 ,-1 , 0
  3977.4     .16       0  4201.9     .05       0  4983.3    .035       0
  5033.8     .05       0
Bank Sta=4983.3,5033.8
XS Rating Curve= 0 ,0
Exp/Cntr=0.3,0.1

Type RM Length L Ch R = 1 ,485     ,264,264,264
BEGIN DESCRIPTION:
Mapping XS 70680104
END DESCRIPTION:
XS GIS Cut Line= 4
      3608293.67     10165826.94      3609116.55     10165524.86
      3609465.51     10165087.36       3609697.2       10164473.
#Sta/Elev= 30
    3818  209.89  4017.7   207.5  4123.2  203.99  4225.8  200.14  4272.7  199.94
  4317.3  200.31  4444.8  198.74  4636.6  197.93    4692  196.81  4778.7  197.78
  4985.3  197.83  5005.9  192.72  5009.1  193.22  5014.1  196.29  5020.5  197.64
  5028.6  198.01  5198.3  197.52  5402.5  198.41  5506.1  203.39  5548.9  206.22
  5591.6  207.74  5628.1   210.2  5652.9  212.97  5658.3  212.83  5768.4  220.67
  5798.6  221.37  5853.7  224.39    5859  223.97  5878.5   224.9  5910.8  224.18
#Mann= 5 ,-1 , 0
    3818     .16       0  4123.2     .12       0  4272.7     .05       0
  4985.3    .035       0  5028.6     .05       0
Bank Sta=4985.3,5028.6
XS Rating Curve= 0 ,0
Exp/Cntr=0.3,0.1

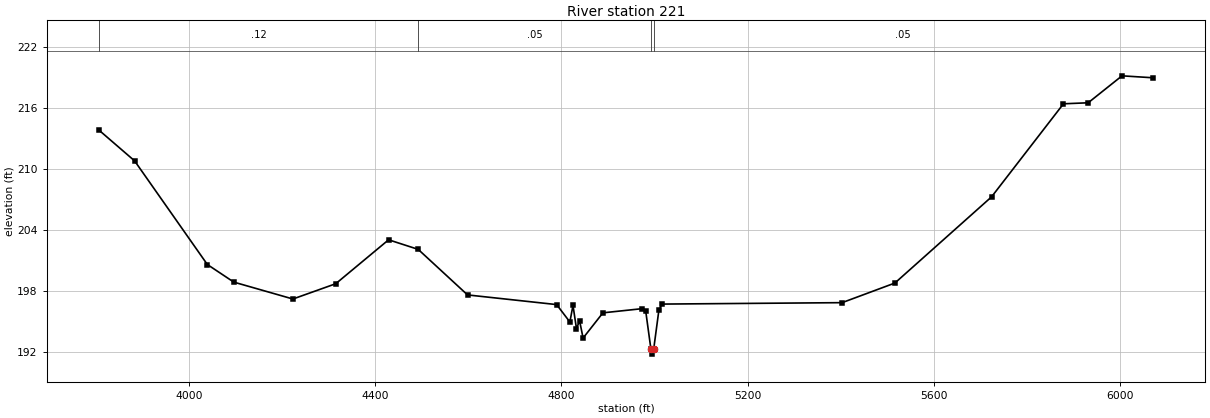
Type RM Length L Ch R = 1 ,221     ,0,0,0
BEGIN DESCRIPTION:
MILLICAN CREEK TRIB 2 1.0
END DESCRIPTION:
XS GIS Cut Line= 3
      3608649.91     10166387.24       3609535.3      10165402.9
      3609787.52     10164498.04
#Sta/Elev= 30
  3807.2  213.79  3883.2  210.79  4039.5   200.6  4096.3  198.87  4223.3  197.21
  4315.3  198.71  4428.9  203.03  4492.4  202.09  4598.5  197.61  4789.9  196.66
  4818.3  194.95    4825  196.58  4832.5   194.3  4839.2  195.07  4846.7  193.37
  4889.3  195.85  4973.8  196.26  4981.2  196.04  4992.4  192.29  4995.2  191.79
  4998.4  192.29  5009.6  196.13  5016.4  196.71  5403.1  196.85  5516.6  198.78
  5724.2  207.25  5878.7   216.4  5931.8   216.5  6004.5  219.15  6070.5  218.96
#Mann= 4 ,-1 , 0
  3807.2     .12       0  4492.4     .05       0  4992.4     .03       0
  4998.4     .05       0
Bank Sta=4992.4,4998.4
XS Rating Curve= 0 ,0
Exp/Cntr=0.3,0.1

Chan Stop Cuts=-1
Use User Specified Reach Order=0
Composite Channel Slope=5