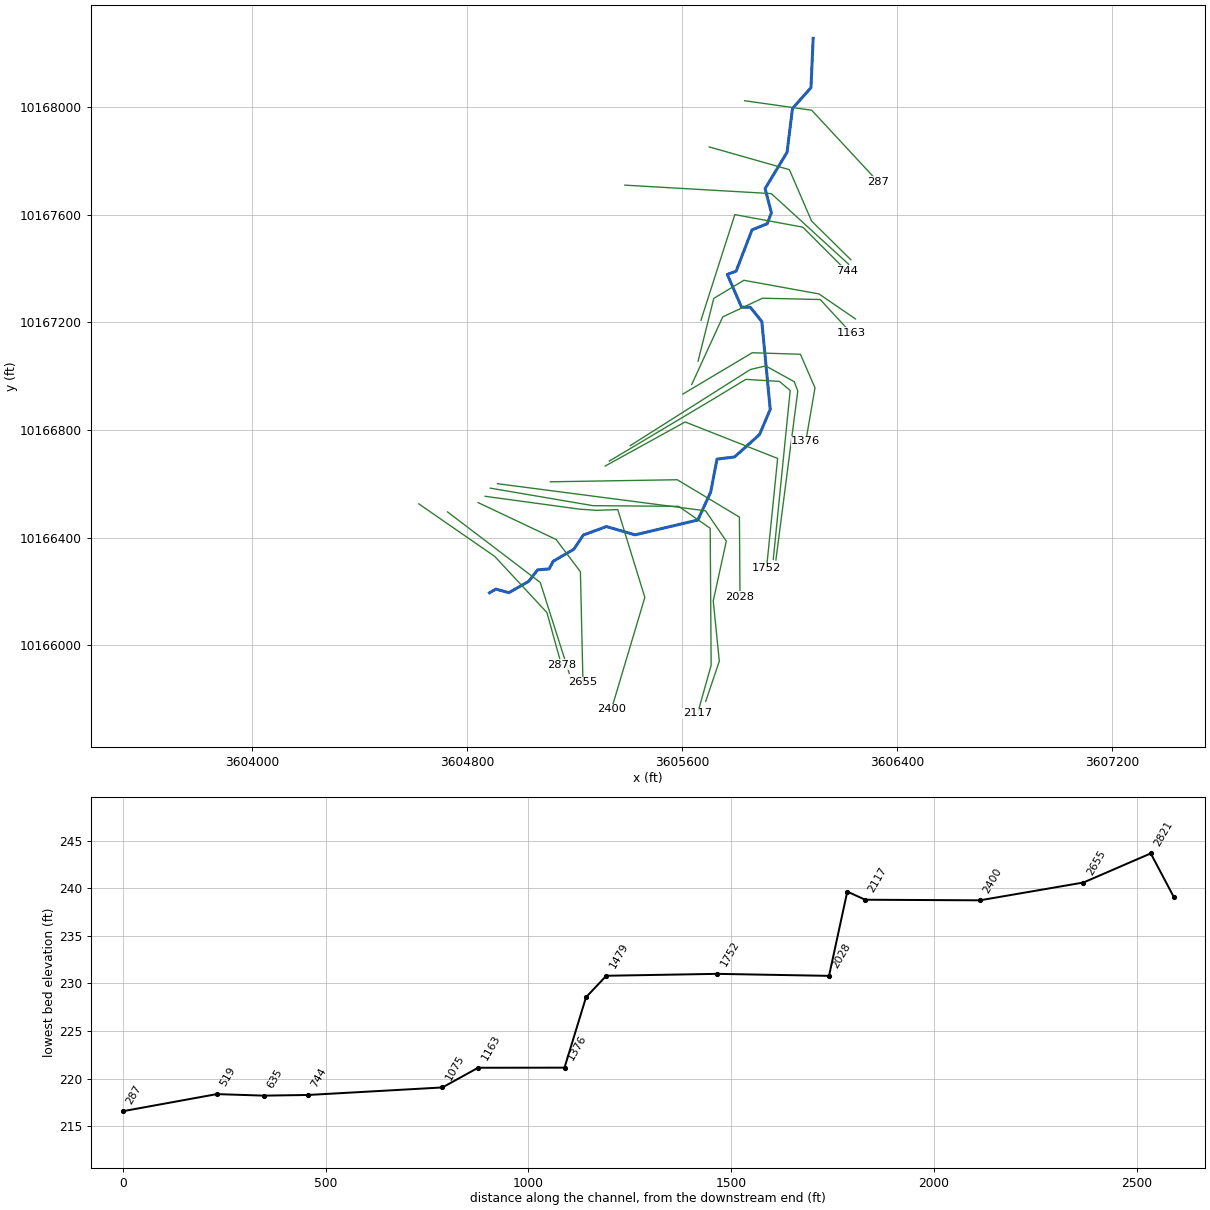
--- MILLICAN CREEK TRIBUTARY 4.prj (project) ---

Proj Title=MILLICAN CREEK TRIBUTARY 4 Base Level Engineering
Current Plan=p01
Default Exp/Contr=0.3,0.1
English Units
Geom File=g01
Flow File=f01
Plan File=p01
Y Axis Title=Elevation
X Axis Title(PF)=Main Channel Distance
X Axis Title(XS)=Station
BEGIN DESCRIPTION:
MILLICAN CREEK TRIBUTARY 4
END DESCRIPTION:
DSS Export Rating Curves= 0
DSS Export Rating Curve Sorted= 0
DSS Export Volume Flow Curves= 0
DXF OffsetX= 0
DXF OffsetY= 0
DXF ScaleX= 1
DXF ScaleY= 10

--- MILLICAN CREEK TRIBUTARY 4.p01 (plan) ---

Plan Title=Multiple Run
Short Identifier=Multiple
Geom File=g01
Flow File=f01
Subcritical Flow
K Sum by GR= 0
Std Step Tol= 0.01
Critical Tol= 0.01
Num of Std Step Trials= 20
Max Error Tol= 0.3
Flow Tol Ratio= 0.001
Split Flow NTrial= 30
Split Flow Tol= 0.02
Split Flow Ratio= 0.02
Log Output Level= 0
Friction Slope Method= 1
Unsteady Friction Slope Method= 2
Unsteady Bridges Friction Slope Method= 1
Parabolic Critical Depth
Global Vel Dist=  1 , 1 , 1
Global Log Level= 0
CheckData=True
Encroach Param= -1, 0, 0, 0
BEGIN DESCRIPTION:
Multiple Run
END DESCRIPTION:

--- MILLICAN CREEK TRIBUTARY 4.f01 (steady flow) ---

Flow Title=Multiple
Number of Profiles=7
Profile Names=10-year,25-year,50-year,1pct_min,100-year,1pct_plu,500-year
River Rch & RM= MILLICAN CREEK T,Reach-1,2878
      97     116     129     106     143     194     177
Boundary for River Rch & Prof#=MILLICAN CREEK T,Reach-1,1
Up Type=0
Dn Type=3
Dn Slope=0.005
Boundary for River Rch & Prof#=MILLICAN CREEK T,Reach-1,2
Up Type=0
Dn Type=3
Dn Slope=0.005
Boundary for River Rch & Prof#=MILLICAN CREEK T,Reach-1,3
Up Type=0
Dn Type=3
Dn Slope=0.005
Boundary for River Rch & Prof#=MILLICAN CREEK T,Reach-1,4
Up Type=0
Dn Type=3
Dn Slope=0.005
Boundary for River Rch & Prof#=MILLICAN CREEK T,Reach-1,5
Up Type=0
Dn Type=3
Dn Slope=0.005
Boundary for River Rch & Prof#=MILLICAN CREEK T,Reach-1,6
Up Type=0
Dn Type=3
Dn Slope=0.005
Boundary for River Rch & Prof#=MILLICAN CREEK T,Reach-1,7
Up Type=0
Dn Type=3
Dn Slope=0.005

--- MILLICAN CREEK TRIBUTARY 4.g01 (geometry) ---

Geom Title=Existing Conditions
Program Version=4.10

River Reach=MILLICAN CREEK T,Reach-1
Reach XY= 30
      3604883.86     10166194.76      3604907.43     10166208.51
      3604955.86     10166195.19      3605029.72     10166237.57
      3605062.41     10166279.95       3605105.4     10166283.58
      3605120.53     10166312.03      3605197.15     10166356.47
      3605232.54     10166409.51       3605318.5     10166440.99
      3605425.02     10166410.26      3605658.48     10166465.37
      3605706.22     10166569.54      3605729.66     10166691.94
      3605794.76     10166699.75      3605887.64     10166783.08
      3605927.57     10166876.83      3605896.32     10167203.22
      3605853.79     10167256.17       3605820.8     10167257.04
      3605767.85     10167378.57      3605800.84     10167390.72
      3605859.87     10167544.37      3605916.29     10167566.94
      3605931.91     10167607.73      3605908.48     10167698.01
      3605990.07     10167832.56      3606010.35     10167995.75
       3606079.1      10168073.1      3606087.18     10168256.44

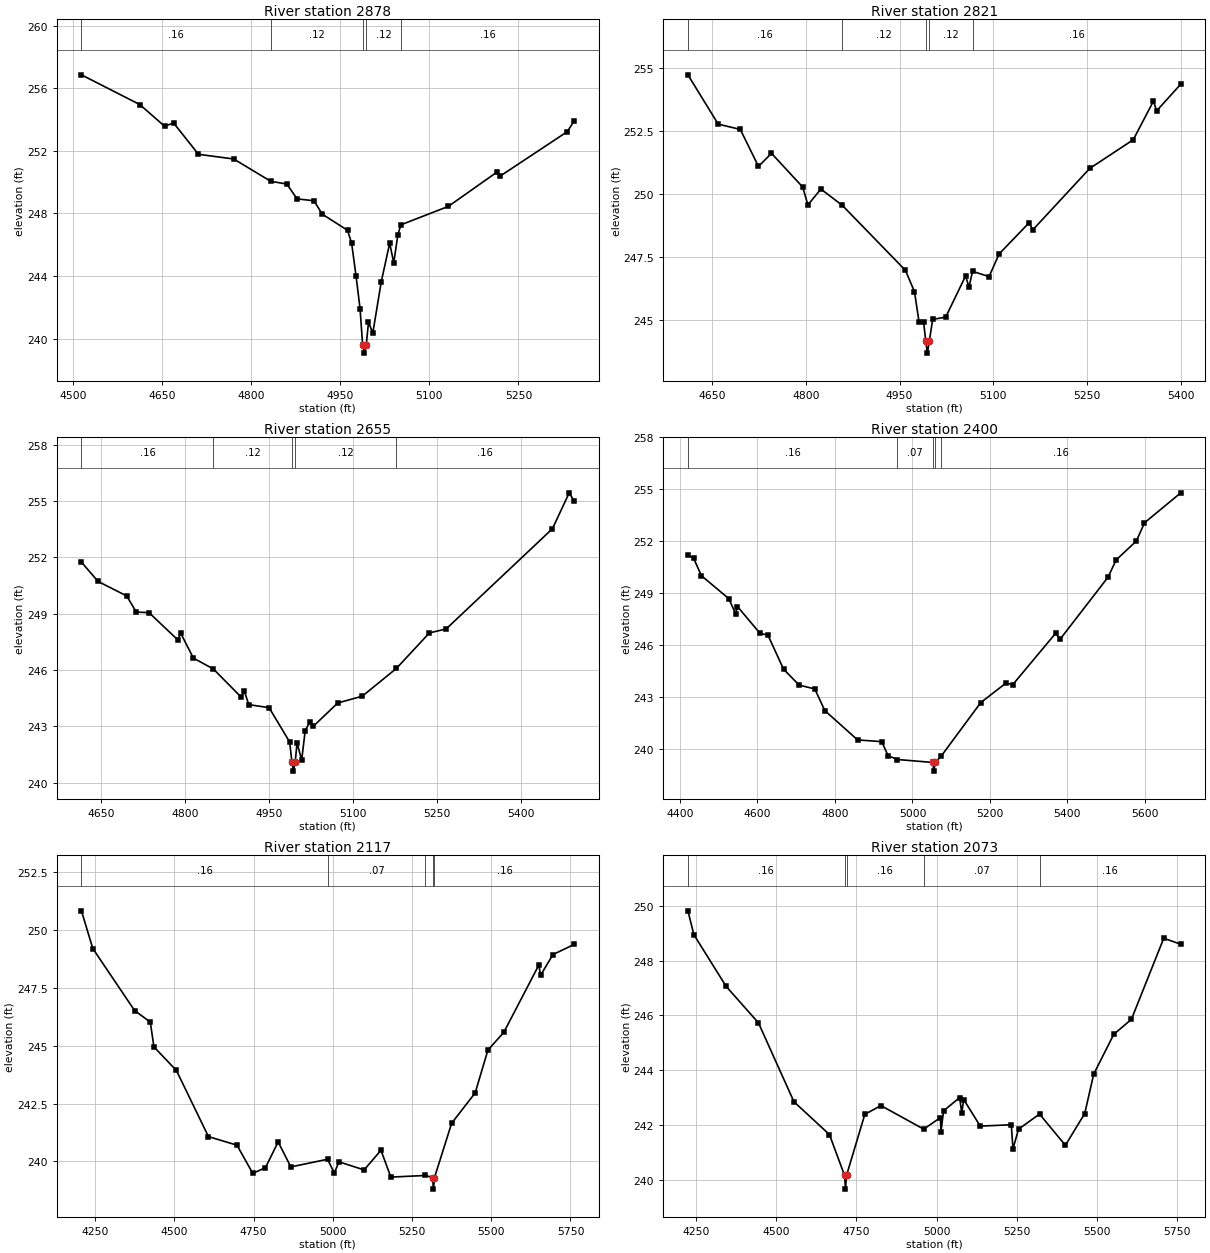
Type RM Length L Ch R = 1 ,2878    ,57,57,57
BEGIN DESCRIPTION:
MILLICAN CREEK TRIB 4 43.0
END DESCRIPTION:
XS GIS Cut Line= 4
      3604620.68     10166525.52      3604902.95     10166330.22
      3605097.22     10166121.37      3605150.86     10165927.65
#Sta/Elev= 30
  4514.5  256.86  4612.7  254.96  4654.6  253.57  4669.5  253.79  4711.4  251.78
  4770.8  251.48  4833.3  250.05  4860.2  249.88  4877.4  248.93  4905.8  248.81
  4919.9  247.95  4962.4  246.92  4969.3  246.08  4976.6  244.02  4983.4  241.92
  4987.8  239.57  4990.5  239.07  4993.8  239.57  4997.6  241.04  5004.9  240.36
  5019.1  243.63  5033.3   246.1  5040.1  244.84    5047  246.62    5052  247.27
    5132  248.45  5213.8  250.64    5219  250.38  5332.3  253.23    5344  253.93
#Mann= 5 ,-1 , 0
  4514.5     .16       0  4833.3     .12       0  4987.8     .07       0
  4993.8     .12       0    5052     .16       0
Bank Sta=4987.8,4993.8
XS Rating Curve= 0 ,0
Exp/Cntr=0.3,0.1

Type RM Length L Ch R = 1 ,2821    ,166,166,166
BEGIN DESCRIPTION:
Mapping XS c6e7b0b8
END DESCRIPTION:
XS GIS Cut Line= 3
      3604727.77      10166495.4      3605072.42     10166233.22
      3605180.35     10165894.75
#Sta/Elev= 30
  4611.4  254.73  4659.9  252.77  4695.2  252.56  4724.3  251.09  4745.1  251.61
    4795  250.27  4803.3  249.56  4824.1  250.19  4858.5  249.54  4959.3  246.96
  4973.8  246.11  4981.2  244.89  4988.4   244.9  4991.7  244.17  4994.4  243.67
  4997.7  244.17  5002.9  245.01  5023.7   245.1  5055.6  246.74  5060.9  246.29
  5066.7  246.92  5093.1  246.71  5109.1  247.61  5157.5  248.86  5162.7  248.56
  5254.1  251.01  5323.7  252.15  5355.9  253.68  5361.2   253.3  5399.7  254.36
#Mann= 5 ,-1 , 0
  4611.4     .16       0  4858.5     .12       0  4991.7     .07       0
  4997.7     .12       0  5066.7     .16       0
Bank Sta=4991.7,4997.7
XS Rating Curve= 0 ,0
Exp/Cntr=0.3,0.1

Type RM Length L Ch R = 1 ,2655    ,255,255,255
BEGIN DESCRIPTION:
Mapping XS ba8f3f2d
END DESCRIPTION:
XS GIS Cut Line= 4
      3604841.55     10166530.07      3605131.45     10166392.94
      3605221.72     10166273.15      3605231.27     10165862.55
#Sta/Elev= 30
  4614.5  251.74  4644.3  250.71  4695.4  249.94  4712.6  249.08  4735.4  249.05
  4786.4  247.61  4792.1  247.95  4814.7  246.63  4850.4  246.05  4900.2  244.55
  4905.7  244.88  4913.8  244.15  4950.1  243.99  4986.9  242.16  4990.8  241.11
  4993.6  240.61  4996.8  241.11  5000.1  242.11  5008.4   241.2  5014.6  242.76
  5022.9  243.23  5029.2     243  5072.9  244.24  5116.7   244.6  5177.8  246.08
  5236.7  247.97  5266.7  248.18  5456.8  253.52  5486.8  255.43  5495.9  254.97
#Mann= 5 ,-1 , 0
  4614.5     .16       0  4850.4     .12       0  4990.8     .07       0
  4996.8     .12       0  5177.8     .16       0
Bank Sta=4990.8,4996.8
XS Rating Curve= 0 ,0
Exp/Cntr=0.3,0.1

Type RM Length L Ch R = 1 ,2400    ,283,283,283
BEGIN DESCRIPTION:
Mapping XS eeb822b4
END DESCRIPTION:
XS GIS Cut Line= 6
      3604867.55     10166553.53      3605218.25     10166505.79
      3605281.62     10166501.45      3605360.61     10166504.05
      3605461.31     10166177.66      3605337.17     10165761.85
#Sta/Elev= 30
  4420.5   251.2  4435.2  251.02  4455.4  250.01    4526  248.69  4543.4  247.83
  4548.5  248.23  4606.8  246.68  4626.9  246.59  4667.3  244.62  4707.7   243.7
    4748  243.48  4773.9  242.23  4858.4  240.54  4920.9  240.44  4937.1  239.63
  4961.3  239.41  5052.6  239.24  5055.3  238.74  5058.6  239.24    5074   239.6
  5176.2  242.69  5241.5  243.82  5258.6  243.72  5369.2  246.68  5381.5  246.36
  5504.9  249.93  5525.7  250.92  5577.9  252.01  5598.8  253.06  5692.5  254.79
#Mann= 5 ,-1 , 0
  4420.5     .16       0  4961.3     .07       0  5052.6     .07       0
  5058.6     .07       0    5074     .16       0
Bank Sta=5052.6,5058.6
XS Rating Curve= 0 ,0
Exp/Cntr=0.3,0.1

Type RM Length L Ch R = 1 ,2117    ,44,44,44
BEGIN DESCRIPTION:
Mapping XS 411072ef
END DESCRIPTION:
XS GIS Cut Line= 6
      3604886.69      10166583.9      3605267.73     10166518.81
      3605587.18      10166516.2      3605704.36     10166434.61
      3605707.84     10165925.06      3605657.53      10165746.4
#Sta/Elev= 30
  4206.6  250.83  4242.5   249.2  4374.4  246.52    4424  246.02  4435.3  244.95
  4506.3  243.93  4607.5  241.07  4697.5   240.7  4747.5  239.48  4787.5  239.73
  4827.5  240.84  4867.5  239.76  4983.3  240.09  5004.7   239.5  5019.5  239.98
  5098.7  239.63    5152  240.48  5183.1  239.32  5292.3  239.39  5314.9   239.3
  5317.6   238.8  5320.9   239.3  5375.1  241.65  5449.3  242.96  5489.5  244.81
  5539.8  245.58  5650.4  248.49  5655.6  248.04  5694.8  248.94  5762.2  249.38
#Mann= 5 ,-1 , 0
  4206.6     .16       0  4983.3     .07       0  5292.3     .16       0
  5314.9     .07       0  5320.9     .16       0
Bank Sta=5314.9,5320.9
XS Rating Curve= 0 ,0
Exp/Cntr=0.3,0.1

Type RM Length L Ch R = 1 ,2073    ,45,45,45
BEGIN DESCRIPTION:
Mapping XS 5b18f2d6
END DESCRIPTION:
XS GIS Cut Line= 6
      3604913.57      10166600.4        3605687.     10166499.71
      3605764.26     10166386.86      3605715.65     10166164.64
      3605738.22     10165940.68      3605687.87     10165791.39
#Sta/Elev= 30
  4225.2  249.82  4243.8  248.95  4344.4  247.06    4445  245.73  4555.6  242.85
  4666.2  241.65  4713.3  240.16  4716.1  239.66  4719.3  240.16  4776.4  242.39
  4826.5  242.71  4959.9  241.85  5011.7  242.27  5013.7  241.76  5021.8  242.52
  5071.8     243  5078.3  242.45  5084.6  242.93    5136  241.96  5232.7  242.01
  5237.9  241.13  5255.3  241.85  5320.7   242.4  5401.2  241.26  5461.5  242.42
  5489.5  243.86  5551.9  245.31    5607  245.86  5707.7  248.82  5760.7   248.6
#Mann= 5 ,-1 , 0
  4225.2     .16       0  4713.3     .07       0  4719.3     .16       0
  4959.9     .07       0  5320.7     .16       0
Bank Sta=4713.3,4719.3
XS Rating Curve= 0 ,0
Exp/Cntr=0.3,0.1

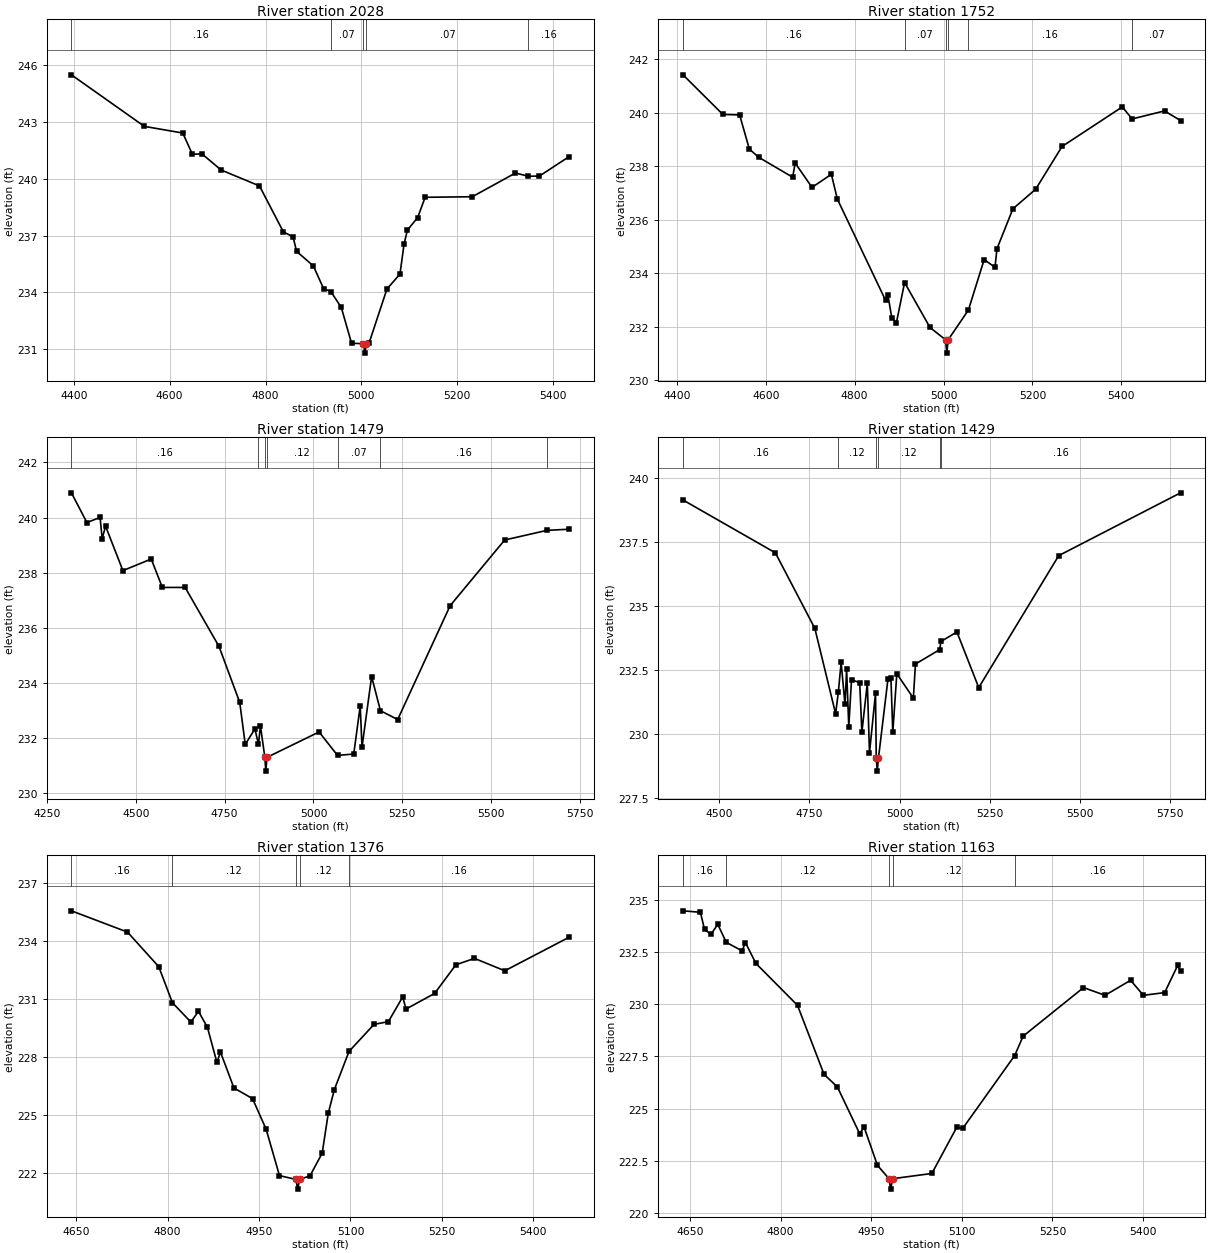
Type RM Length L Ch R = 1 ,2028    ,276,276,276
BEGIN DESCRIPTION:
Mapping XS 036b89f0
END DESCRIPTION:
XS GIS Cut Line= 4
      3605109.89     10166607.52      3605581.87     10166615.12
      3605812.99     10166476.23      3605815.16     10166180.02
#Sta/Elev= 30
  4395.1  245.48  4547.3  242.76  4627.4  242.41  4647.4  241.29  4667.4  241.31
  4707.4  240.46  4787.4  239.62  4837.4  237.19  4857.4  236.94  4864.8  236.17
  4899.8   235.4  4921.2   234.2  4936.2  234.05  4958.1  233.21  4979.5  231.32
  5004.4   231.3  5007.2   230.8  5010.4   231.3  5016.4  231.36  5053.3  234.18
  5080.5  234.97  5089.1  236.56    5096  237.29  5117.4  237.95    5133  239.02
  5231.4  239.05  5321.4   240.3  5348.6  240.13  5371.4  240.14    5433  241.16
#Mann= 5 ,-1 , 0
  4395.1     .16       0  4936.2     .07       0  5004.4     .07       0
  5010.4     .07       0  5348.6     .16       0
Bank Sta=5004.4,5010.4
XS Rating Curve= 0 ,0
Exp/Cntr=0.3,0.1

Type RM Length L Ch R = 1 ,1752    ,273,273,273
BEGIN DESCRIPTION:
Mapping XS c969d11d
END DESCRIPTION:
XS GIS Cut Line= 4
      3605313.83      10166666.1      3605611.16     10166829.96
      3605955.13     10166694.33      3605913.92     10166286.54
#Sta/Elev= 30
    4414  241.42  4503.5  239.94  4541.4  239.92  4563.2  238.64  4584.9  238.33
  4660.6  237.59  4666.3  238.12  4704.2  237.21  4747.7   237.7  4761.2  236.77
  4869.5  232.99  4874.9  233.18  4883.5  232.34  4893.9  232.14  4912.4  233.65
  4969.5  231.97  5004.5  231.51  5007.3  231.01  5010.5  231.51  5055.9  232.62
  5091.4  234.51  5115.8  234.22  5120.1  234.91  5156.1  236.41  5207.2  237.14
  5266.6  238.74  5402.1  240.22  5424.2  239.77  5497.1  240.07  5533.1  239.71
#Mann= 6 ,-1 , 0
    4414     .16       0  4912.4     .07       0  5004.5     .07       0
  5010.5     .07       0  5055.9     .16       0  5424.2     .07       0
Bank Sta=5004.5,5010.5
XS Rating Curve= 0 ,0
Exp/Cntr=0.3,0.1

Type RM Length L Ch R = 1 ,1479    ,50,50,50
BEGIN DESCRIPTION:
Mapping XS fe896031
END DESCRIPTION:
XS GIS Cut Line= 6
      3605329.09     10166684.59      3605724.01     10166920.02
      3605836.86     10166988.38      3605961.64     10166980.79
      3606001.79     10166947.15      3605938.85      10166318.9
#Sta/Elev= 30
  4318.7   240.9  4362.4  239.82  4399.4  240.01  4405.2  239.24  4414.9  239.69
  4463.6  238.08  4543.4   238.5  4574.6  237.47  4638.8  237.47  4734.2  235.33
  4792.5   233.3    4808  231.78  4835.2  232.34  4845.3  231.78  4850.7  232.46
  4863.2  231.31  4865.9  230.81  4869.2  231.31  5015.9  232.23  5067.8  231.38
  5113.4  231.43  5131.6  233.17  5136.7  231.68  5163.7  234.24  5188.6     233
  5237.1  232.68  5384.8  236.81  5538.3  239.19  5657.6  239.54  5719.2  239.58
#Mann= 7 ,-1 , 0
  4318.7     .16       0  4845.3     .12       0  4863.2     .07       0
  4869.2     .12       0  5067.8     .07       0  5188.6     .16       0
  5657.6     .07       0
Bank Sta=4863.2,4869.2
XS Rating Curve= 0 ,0
Exp/Cntr=0.3,0.1

Type RM Length L Ch R = 1 ,1429    ,53,53,53
BEGIN DESCRIPTION:
Mapping XS dbb373c4
END DESCRIPTION:
XS GIS Cut Line= 6
       3605407.2     10166742.09      3605854.22     10167025.27
      3605910.64     10167038.29      3606016.98      10166979.7
        3606030.     10166944.98      3605948.63     10166316.77
#Sta/Elev= 30
  4399.7  239.13  4655.7  237.07  4765.2  234.12  4822.8  230.79  4830.5  231.65
  4838.1  232.79  4848.8  231.15  4853.3  232.52  4859.3  230.28  4866.9  232.12
  4889.6     232  4895.6  230.07  4910.7  231.98  4916.7  229.26  4933.4  231.59
  4935.5  229.05  4938.3  228.55  4941.5  229.05  4967.8  232.13  4976.2  232.17
  4981.3  230.06  4992.5  232.35  5038.3   231.4  5044.2  232.73  5111.2  233.29
  5114.9  233.61  5159.1  233.98  5219.6  231.81  5441.4  236.96  5779.1  239.41
#Mann= 6 ,-1 , 0
  4399.7     .16       0  4830.5     .12       0  4935.5     .07       0
  4941.5     .12       0  5111.2     .07       0  5114.9     .16       0
Bank Sta=4935.5,4941.5
XS Rating Curve= 0 ,0
Exp/Cntr=0.3,0.1

Type RM Length L Ch R = 1 ,1376    ,213,213,213
BEGIN DESCRIPTION:
Mapping XS e108e132
END DESCRIPTION:
XS GIS Cut Line= 5
      3605603.03     10166933.86      3605860.69     10167087.34
      3606039.85     10167081.78      3606094.02     10166956.78
      3606059.99     10166758.87
#Sta/Elev= 30
  4642.2  235.54  4734.2  234.44  4785.5  232.65  4807.9  230.79  4838.1  229.79
  4850.6  230.34  4865.3  229.52  4880.9   227.7  4886.7  228.24  4908.8  226.38
  4939.3  225.83  4961.6  224.25  4983.5  221.85  5010.6  221.65  5013.3  221.15
  5016.6  221.65  5033.6  221.84  5053.6  223.01  5063.6  225.08  5073.6   226.3
  5097.6  228.27  5138.7  229.67  5162.2  229.81  5185.7  231.09  5191.1  230.46
  5238.1  231.27  5272.9  232.75  5303.4  233.08  5353.2  232.44  5458.4  234.17
#Mann= 5 ,-1 , 0
  4642.2     .16       0  4807.9     .12       0  5010.6     .07       0
  5016.6     .12       0  5097.6     .16       0
Bank Sta=5010.6,5016.6
XS Rating Curve= 0 ,0
Exp/Cntr=0.3,0.1

Type RM Length L Ch R = 1 ,1163    ,88,88,88
BEGIN DESCRIPTION:
Mapping XS 6f67743b
END DESCRIPTION:
XS GIS Cut Line= 5
      3605635.68     10166969.27      3605750.96     10167220.67
      3605898.88     10167290.12      3606113.46     10167285.26
      3606228.26     10167160.84
#Sta/Elev= 30
  4638.3  234.48  4667.1  234.41  4673.9  233.59  4684.6  233.36  4695.9  233.83
  4709.9  232.97  4736.1  232.56  4741.6  232.96    4759  231.96  4827.9  229.95
  4871.9  226.64  4893.9  226.04  4930.8   223.8  4938.2  224.11  4960.3  222.28
  4979.4  221.64  4982.2  221.14  4985.4  221.64  5050.4  221.89  5091.5   224.1
  5101.5  224.05  5187.5  227.54  5201.5  228.47  5301.5   230.8  5337.2  230.43
  5379.5  231.15  5400.7  230.43  5435.9  230.56  5457.4  231.86  5462.2  231.58
#Mann= 5 ,-1 , 0
  4638.3     .16       0  4709.9     .12       0  4979.4     .07       0
  4985.4     .12       0  5187.5     .16       0
Bank Sta=4979.4,4985.4
XS Rating Curve= 0 ,0
Exp/Cntr=0.3,0.1

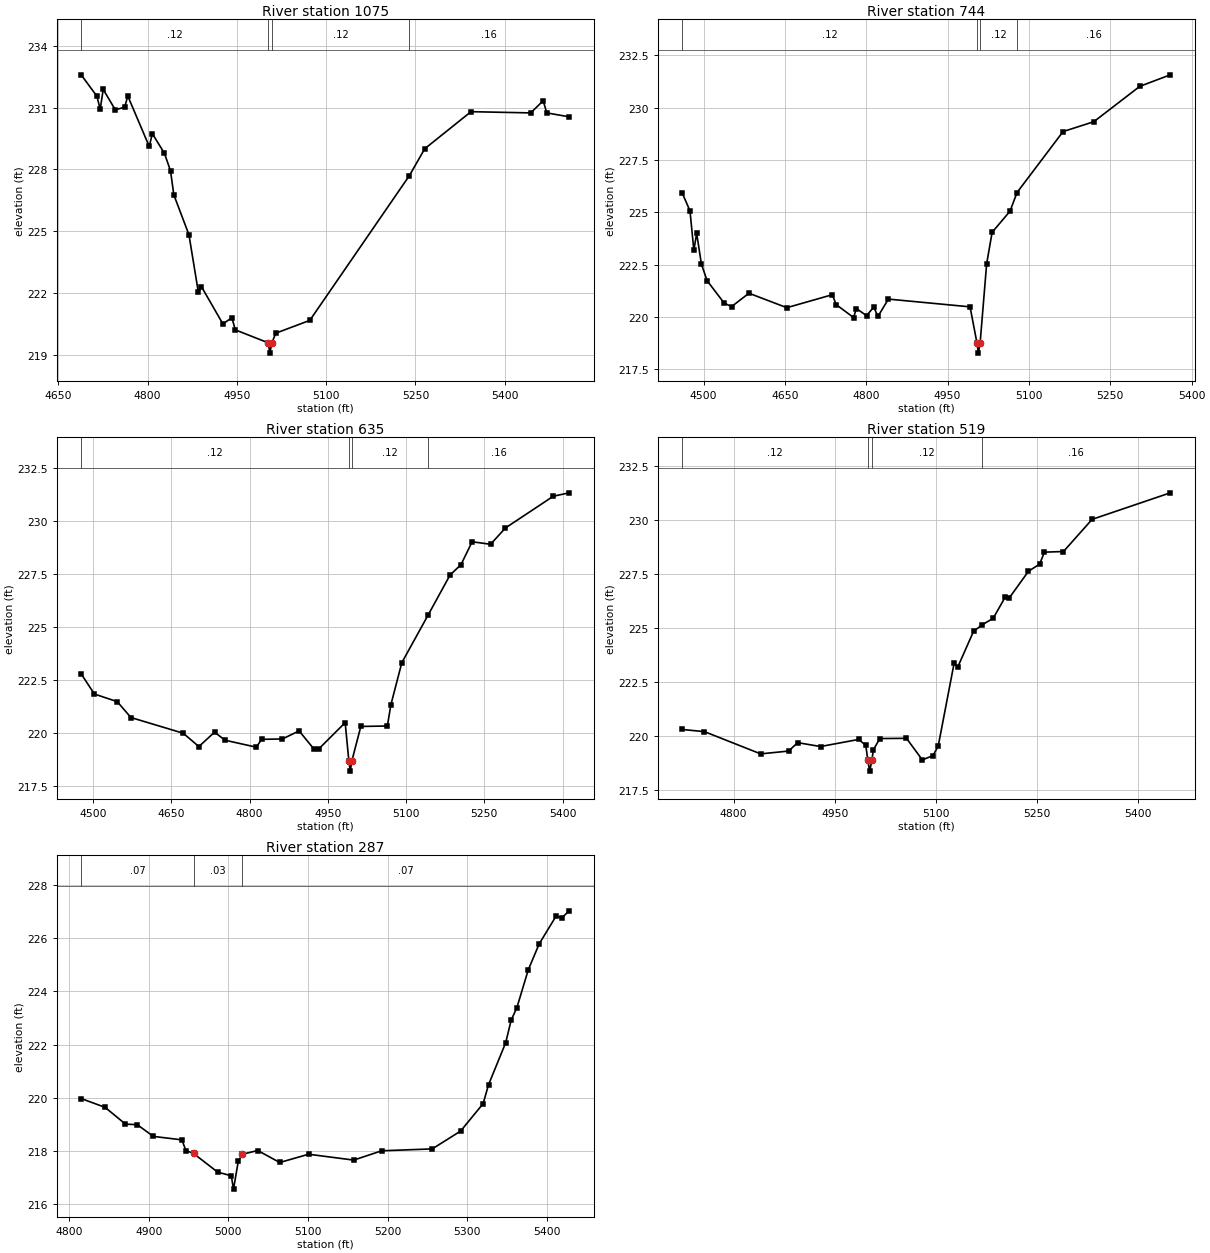
Type RM Length L Ch R = 1 ,1075    ,331,331,331
BEGIN DESCRIPTION:
Mapping XS 47f9cf46
END DESCRIPTION:
XS GIS Cut Line= 5
      3605659.29     10167056.05      3605717.63     10167289.42
      3605829.44     10167356.78       3606108.6     10167306.09
      3606244.71     10167213.03
#Sta/Elev= 30
  4688.6  232.59    4715  231.55  4720.5  230.92  4725.6  231.88  4745.9  230.89
  4761.7  231.02  4766.9  231.56  4802.9  229.11  4808.1  229.73  4828.4  228.78
  4838.7  227.92  4844.2  226.76  4869.6  224.82  4885.4  222.03  4890.6   222.3
  4926.6  220.49  4941.7  220.79  4947.5   220.2  5002.8  219.57  5005.5  219.07
  5008.8  219.57  5015.5  220.04  5072.6  220.66  5239.8  227.69  5265.7     229
  5343.4   230.8  5443.6  230.74  5464.6  231.33  5470.7  230.74  5508.3  230.55
#Mann= 4 ,-1 , 0
  4688.6     .12       0  5002.8     .07       0  5008.8     .12       0
  5239.8     .16       0
Bank Sta=5002.8,5008.8
XS Rating Curve= 0 ,0
Exp/Cntr=0.3,0.1

Type RM Length L Ch R = 1 ,744     ,109,109,109
BEGIN DESCRIPTION:
Mapping XS 7c5c26b9
END DESCRIPTION:
XS GIS Cut Line= 4
      3605670.05     10167208.14      3605795.93     10167600.97
      3606048.75     10167554.31      3606211.53     10167391.53
#Sta/Elev= 30
  4460.8  225.92    4475  225.07  4482.1  223.19  4487.3     224    4496  222.54
  4506.5  221.74    4538  220.67  4551.6   220.5  4583.7  221.14  4653.5  220.45
  4737.5  221.07  4744.4   220.6  4776.6  219.98  4781.8  220.41  4800.5  220.07
  4813.9  220.48  4821.5  220.03  4840.8  220.86  4991.4  220.49    5004  218.78
  5006.8  218.28    5010  218.78    5022  222.55  5032.1  224.05  5065.1  225.06
    5078  225.95  5162.9  228.86  5219.5  229.33  5304.4  231.02  5360.6  231.57
#Mann= 4 ,-1 , 0
  4460.8     .12       0    5004     .07       0    5010     .12       0
    5078     .16       0
Bank Sta=5004,5010
XS Rating Curve= 0 ,0
Exp/Cntr=0.3,0.1

Type RM Length L Ch R = 1 ,635     ,116,116,116
BEGIN DESCRIPTION:
Mapping XS 3a23a383
END DESCRIPTION:
XS GIS Cut Line= 3
      3605386.87     10167710.56      3605931.56     10167679.09
       3606219.5     10167416.05
#Sta/Elev= 30
  4477.1   222.8  4502.4  221.85  4546.2  221.49  4572.5  220.74  4672.7     220
  4702.7  219.37  4732.8  220.05  4752.8  219.67  4812.9  219.34  4822.9  219.71
    4863  219.73  4894.9  220.11  4923.1  219.26  4933.1  219.27  4983.2   220.5
  4990.2  218.71  4992.9  218.21  4996.2  218.71  5013.2  220.32  5064.1  220.34
  5070.8  221.34  5091.8  223.33  5141.8  225.56  5184.3  227.47  5205.3  227.96
  5226.6  229.04    5262  228.92  5290.4  229.69  5382.3  231.19  5412.7  231.35
#Mann= 4 ,-1 , 0
  4477.1     .12       0  4990.2     .07       0  4996.2     .12       0
  5141.8     .16       0
Bank Sta=4990.2,4996.2
XS Rating Curve= 0 ,0
Exp/Cntr=0.3,0.1

Type RM Length L Ch R = 1 ,519     ,232,232,232
BEGIN DESCRIPTION:
Mapping XS dfc41241
END DESCRIPTION:
XS GIS Cut Line= 4
      3605700.44     10167852.71      3605998.84     10167768.07
       3606081.3      10167577.1      3606227.42     10167433.15
#Sta/Elev= 30
  4724.1   220.3    4757   220.2  4840.2  219.17  4881.7   219.3  4895.1  219.69
    4929  219.51  4985.7  219.84  4996.1  219.56  4999.1  218.87  5001.8  218.37
  5005.1  218.87  5007.3  219.36  5016.9  219.88  5056.4  219.89  5079.9  218.89
  5095.7  219.09  5103.4  219.53  5126.9  223.36  5132.3  223.19  5155.8  224.85
  5168.9  225.16  5184.8  225.45  5202.8  226.44  5208.3  226.38  5237.1  227.63
  5253.8  227.97  5260.8  228.52  5289.1  228.55  5331.5  230.04  5447.4  231.27
#Mann= 4 ,-1 , 0
  4724.1     .12       0  4999.1     .07       0  5005.1     .12       0
  5168.9     .16       0
Bank Sta=4999.1,5005.1
XS Rating Curve= 0 ,0
Exp/Cntr=0.3,0.1

Type RM Length L Ch R = 1 ,287     ,0,0,0
BEGIN DESCRIPTION:
MILLICAN CREEK TRIB 4 1.0
END DESCRIPTION:
XS GIS Cut Line= 3
       3605832.3     10168024.51      3606081.79     10167989.09
      3606327.62     10167724.04
#Sta/Elev= 30
  4814.9  219.97    4845  219.64  4870.6  219.01  4885.4  218.99  4905.6  218.55
  4941.5  218.42  4946.5  218.02  4956.1  217.91  4986.4  217.21  5003.6  217.07
  5006.4  216.57  5012.4  217.62  5017.5  217.88  5036.9  218.02  5064.5  217.57
  5100.8  217.88  5157.5  217.66  5192.7  218.01  5256.2  218.08  5291.9  218.75
  5320.2  219.78    5327  220.49  5348.6  222.07  5355.4  222.91  5362.7  223.39
  5376.9   224.8  5390.7  225.78  5412.1  226.83  5418.9  226.75  5428.4  227.02
#Mann= 3 , 0 , 0
  4814.9     .07       0  4956.1     .03       0  5017.5     .07       0
Bank Sta=4956.1,5017.5
XS Rating Curve= 0 ,0
Exp/Cntr=0.3,0.1

Chan Stop Cuts=-1
Use User Specified Reach Order=0
Composite Channel Slope=5