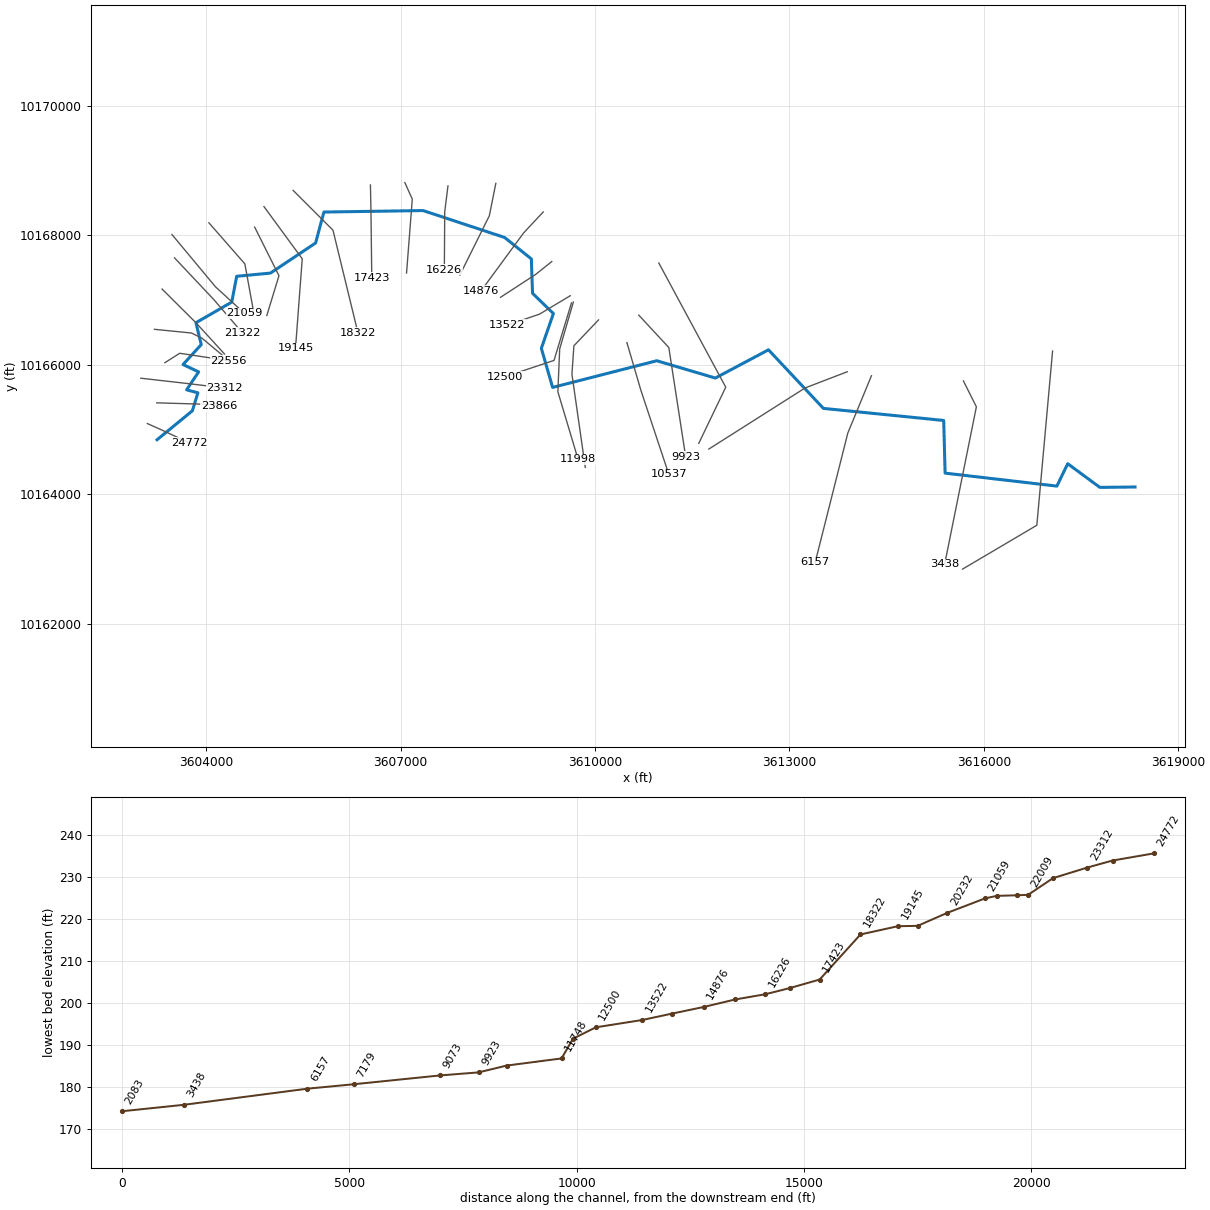
--- MILLICAN CREEK.prj (project) ---

Proj Title=MILLICAN CREEK Base Level Engineering
Current Plan=p01
Default Exp/Contr=0.3,0.1
English Units
Geom File=g01
Flow File=f01
Plan File=p01
Y Axis Title=Elevation
X Axis Title(PF)=Main Channel Distance
X Axis Title(XS)=Station
BEGIN DESCRIPTION:
MILLICAN CREEK
END DESCRIPTION:
DSS Export Rating Curves= 0
DSS Export Rating Curve Sorted= 0
DSS Export Volume Flow Curves= 0
DXF OffsetX= 0
DXF OffsetY= 0
DXF ScaleX= 1
DXF ScaleY= 10

--- MILLICAN CREEK.p01 (plan) ---

Plan Title=Multiple Run
Short Identifier=Multiple
Geom File=g01
Flow File=f01
Subcritical Flow
K Sum by GR= 0
Std Step Tol= 0.01
Critical Tol= 0.01
Num of Std Step Trials= 20
Max Error Tol= 0.3
Flow Tol Ratio= 0.001
Split Flow NTrial= 30
Split Flow Tol= 0.02
Split Flow Ratio= 0.02
Log Output Level= 0
Friction Slope Method= 1
Unsteady Friction Slope Method= 2
Unsteady Bridges Friction Slope Method= 1
Parabolic Critical Depth
Global Vel Dist=  1 , 1 , 1
Global Log Level= 0
CheckData=True
Encroach Param= -1, 0, 0, 0
BEGIN DESCRIPTION:
Multiple Run
END DESCRIPTION:

--- MILLICAN CREEK.f01 (steady flow) ---

Flow Title=Multiple
Program Version=4.10
Number of Profiles= 7
Profile Names=10-year,25-year,50-year,1pct_min,100-year,1pct_plu,500-year
River Rch & RM=MILLICAN CREEK,Reach-1         ,24772
     604     807     971     856    1158    1566    1649
River Rch & RM=MILLICAN CREEK,Reach-1         ,21322
     728     988    1202    1071    1448    1958    2105
River Rch & RM=MILLICAN CREEK,Reach-1         ,19145
     879    1202    1470    1314    1777    2404    2606
River Rch & RM=MILLICAN CREEK,Reach-1         ,11998
    1662    2333    2902    2634    3562    4818    5384
Boundary for River Rch & Prof#=MILLICAN CREEK,Reach-1         , 1
Up Type= 0
Dn Type= 3
Dn Slope=0.005
Boundary for River Rch & Prof#=MILLICAN CREEK,Reach-1         , 2
Up Type= 0
Dn Type= 3
Dn Slope=0.005
Boundary for River Rch & Prof#=MILLICAN CREEK,Reach-1         , 3
Up Type= 0
Dn Type= 3
Dn Slope=0.005
Boundary for River Rch & Prof#=MILLICAN CREEK,Reach-1         , 4
Up Type= 0
Dn Type= 3
Dn Slope=0.005
Boundary for River Rch & Prof#=MILLICAN CREEK,Reach-1         , 5
Up Type= 0
Dn Type= 3
Dn Slope=0.005
Boundary for River Rch & Prof#=MILLICAN CREEK,Reach-1         , 6
Up Type= 0
Dn Type= 3
Dn Slope=0.005
Boundary for River Rch & Prof#=MILLICAN CREEK,Reach-1         , 7
Up Type= 0
Dn Type= 3
Dn Slope=0.005
DSS Import GetInterval= 0
DSS Import GetPeak= 0
DSS Import FillOption= 0

--- MILLICAN CREEK.g01 (geometry) ---

Geom Title=Existing Conditions
Program Version=4.10

River Reach=MILLICAN CREEK  ,Reach-1
Reach XY= 30
      3603242.11     10164841.64      3603786.95     10165289.05
      3603871.67     10165566.14      3603698.06     10165612.66
      3603883.48     10165889.05      3603642.76     10166003.02
      3603923.29     10166311.04       3603841.7     10166648.72
      3604393.73     10166966.73      3604470.68     10167365.76
      3604991.15     10167415.31      3605688.25      10167879.6
      3605816.19     10168358.09      3607346.93     10168380.85
      3608604.52     10167965.39      3609017.14     10167634.48
      3609035.56     10167102.84      3609357.46     10166790.61
      3609171.75      10166253.5      3609345.31     10165649.47
      3610952.21     10166061.53      3611856.46     10165794.33
      3612676.38     10166230.24      3613524.19     10165325.66
      3615380.25     10165139.16      3615401.86     10164326.08
      3617126.43     10164125.54      3617293.76     10164471.47
      3617789.26     10164106.08      3618332.11     10164111.64

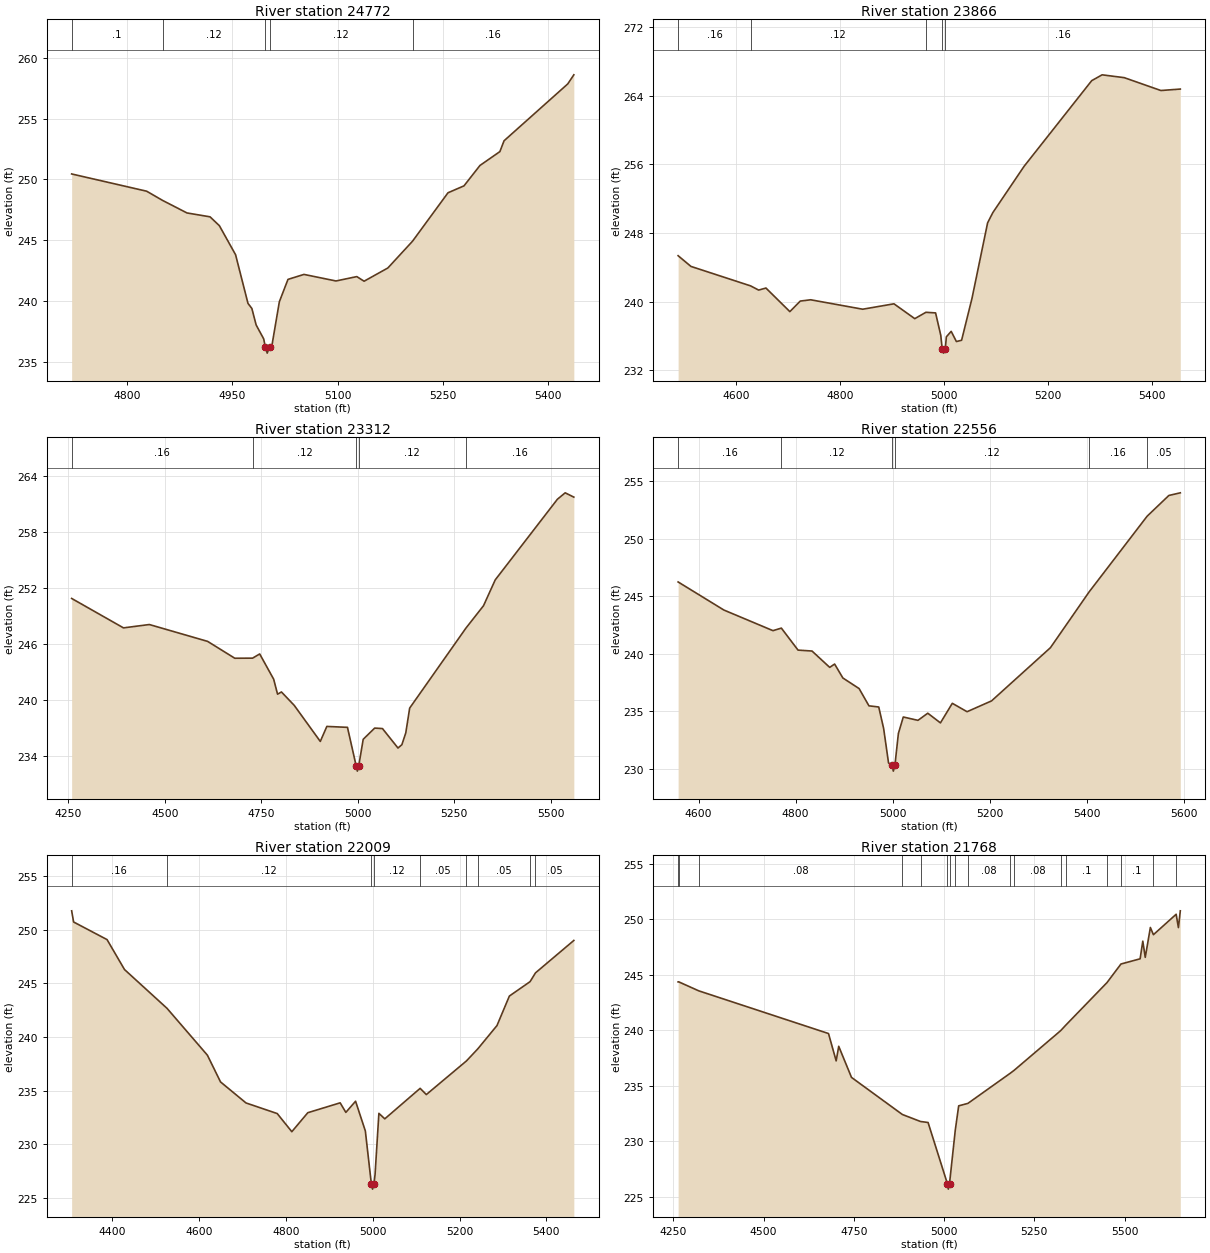
Type RM Length L Ch R = 1 ,24772   ,906,906,906
BEGIN DESCRIPTION:
MILLICAN CREEK 43.0
END DESCRIPTION:
XS GIS Cut Line= 3
      3603092.15     10165091.62      3603346.76     10164977.29
      3603742.14     10164791.63
#Sta/Elev= 30
  4720.9  250.45  4827.8  249.03  4850.6  248.27  4885.3  247.24  4918.2  246.92
  4931.5  246.19  4954.6   243.8  4972.3  239.79  4977.8  239.38  4983.9  238.02
  4994.7  236.87    4997   236.2  4999.7   235.7    5003   236.2  5006.5  236.36
    5017  239.93  5029.3  241.77  5052.1  242.18  5097.7  241.64  5127.4     242
  5137.8  241.62  5171.7  242.71  5206.8  244.91  5257.4   248.9  5280.2  249.47
    5303  251.15  5331.4  252.29  5337.3  253.18  5428.1  257.86  5436.8  258.61
#Mann= 5 ,-1 , 0
  4720.9      .1       0  4850.6     .12       0    4997     .07       0
    5003     .12       0  5206.8     .16       0
Bank Sta=4997,5003
XS Rating Curve= 0 ,0
Exp/Cntr=0.3,0.1

Type RM Length L Ch R = 1 ,23866   ,554,554,554
BEGIN DESCRIPTION:
MILLICAN CREEK 41.0
END DESCRIPTION:
XS GIS Cut Line= 3
      3603237.41     10165411.53      3604140.42     10165385.23
      3604194.94      10165355.9
#Sta/Elev= 30
  4488.4  245.36  4513.1  244.11  4627.8  241.84  4643.2  241.35  4657.2  241.59
  4703.2  238.84  4723.2  240.07  4743.2  240.22  4843.2  239.12  4903.3  239.75
  4943.3  238.02  4964.7  238.76  4983.3  238.69  4993.3  236.07    4996   234.5
  4998.8     234    5002   234.5    5004   235.9  5013.3  236.54  5023.3  235.35
  5033.3   235.5  5053.3  240.39  5083.3  249.19  5093.3  250.38  5153.4  255.78
  5283.4  265.77  5303.4  266.45  5345.9  266.12  5416.4  264.62  5453.7  264.79
#Mann= 5 ,-1 , 0
  4488.4     .16       0  4627.8     .12       0  4964.7     .16       0
    4996     .07       0    5002     .16       0
Bank Sta=4996,5002
XS Rating Curve= 0 ,0
Exp/Cntr=0.3,0.1

Type RM Length L Ch R = 1 ,23312   ,756,756,756
BEGIN DESCRIPTION:
MILLICAN CREEK 40.0
END DESCRIPTION:
XS GIS Cut Line= 3
      3602992.07     10165791.65      3603728.61      10165707.8
      3604284.38     10165640.69
#Sta/Elev= 30
  4258.7  250.87    4393  247.71    4460  248.07    4611  246.26  4681.4  244.45
  4727.5  244.46  4745.9  244.91  4782.1   242.2  4792.2  240.59  4802.2  240.83
  4835.4  239.39  4902.9  235.52  4919.9  237.13  4973.3  237.03  4996.2  232.83
    4999  232.33  5002.2  232.83  5014.1  235.75  5043.8  236.95    5064   236.9
  5104.2  234.81  5114.3  235.17  5124.4  236.44  5134.5   239.1  5280.5   247.7
  5325.8  250.09  5356.1  252.86  5517.2  261.52  5537.4  262.21  5559.8  261.75
#Mann= 5 ,-1 , 0
  4258.7     .16       0  4727.5     .12       0  4996.2     .07       0
  5002.2     .12       0  5280.5     .16       0
Bank Sta=4996.2,5002.2
XS Rating Curve= 0 ,0
Exp/Cntr=0.3,0.1

Type RM Length L Ch R = 1 ,22556   ,547,547,547
BEGIN DESCRIPTION:
MILLICAN CREEK 39.0
END DESCRIPTION:
XS GIS Cut Line= 3
      3603362.48     10166031.33      3603591.63     10166177.15
      3604346.87     10166062.56
#Sta/Elev= 30
  4557.7  246.23  4652.1  243.79  4753.3     242  4770.6  242.22    4805  240.31
  4833.8  240.23  4870.3  238.81  4880.4   239.1  4897.4  237.89  4930.9  236.97
  4951.2  235.47  4971.4  235.37  4981.5   233.5  4991.6  230.51  4998.7   230.3
  5001.5   229.8  5004.7   230.3  5011.9  233.07    5022   234.5  5052.3  234.21
  5072.5  234.83  5098.6  233.99  5123.1  235.69  5153.5  234.96    5204   235.9
  5325.4  240.52  5405.1  245.36  5524.8  251.94  5569.6  253.74  5593.2  253.97
#Mann= 6 ,-1 , 0
  4557.7     .16       0  4770.6     .12       0  4998.7     .07       0
  5004.7     .12       0  5405.1     .16       0  5524.8     .05       0
Bank Sta=4998.7,5004.7
XS Rating Curve= 0 ,0
Exp/Cntr=0.3,0.1

Type RM Length L Ch R = 1 ,22009   ,241,241,241
BEGIN DESCRIPTION:
MILLICAN CREEK 38.0
END DESCRIPTION:
XS GIS Cut Line= 4
      3603201.05     10166546.94      3603773.92     10166489.65
      3603934.26     10166410.45      3604242.94     10166153.18
#Sta/Elev= 30
  4306.8  251.75  4311.3  250.71  4388.3  249.07  4428.5  246.28  4526.3  242.67
  4619.4   238.3  4649.6  235.81  4708.3  233.85  4780.2  232.86  4813.8  231.17
  4850.6  232.94  4925.1  233.86  4938.2  232.97  4960.6  234.01  4983.1  231.24
  4996.9  226.32  4999.7  225.82  5002.9  226.32  5005.5  227.19  5014.3  232.88
  5027.9  232.37  5109.3  235.21  5123.5  234.63  5215.8  237.76  5242.1  238.89
  5286.2  241.06  5314.8  243.81  5362.4  245.15  5374.9  245.97  5463.2  248.99
#Mann= 9 ,-1 , 0
  4306.8     .16       0  4526.3     .12       0  4996.9     .07       0
  5002.9     .12       0  5109.3     .05       0  5215.8     .12       0
  5242.1     .05       0  5362.4     .12       0  5374.9     .05       0
Bank Sta=4996.9,5002.9
XS Rating Curve= 0 ,0
Exp/Cntr=0.3,0.1

Type RM Length L Ch R = 1 ,21768   ,446,446,446
BEGIN DESCRIPTION:
MILLICAN CREEK 37.0
END DESCRIPTION:
XS GIS Cut Line= 3
       3603319.7     10167168.43       3603841.7     10166648.72
      3604282.97     10166165.34
#Sta/Elev= 30
  4263.4  244.37  4264.8  244.38  4320.2  243.57    4680  239.72  4701.2  237.26
  4708.3  238.57  4743.7  235.77  4884.6  232.43  4934.9   231.8  4955.8  231.71
  5009.2  226.21  5011.9  225.71  5015.2  226.21  5031.2  231.03  5040.6  233.21
  5066.1  233.43  5184.1  236.16  5194.6  236.42  5323.1  239.98  5337.1  240.47
  5451.5  244.31  5490.1  245.98  5543.2  246.45  5550.6  248.04  5557.4  246.58
  5571.6  249.27    5580  248.62    5643  250.46  5649.3  249.26  5654.5  250.77
#Mann= 17 ,-1 , 0
  4263.4     .08       0  4264.8     .05       0  4320.2     .08       0
  4884.6      .1       0  4934.9     .08       0  5009.2     .07       0
  5015.2     .08       0  5031.2      .1       0  5066.1     .08       0
  5184.1      .1       0  5194.6     .08       0  5323.1     .05       0
  5337.1      .1       0  5451.5     .05       0  5490.1      .1       0
    5580     .05       0    5643      .1       0
Bank Sta=5009.2,5015.2
XS Rating Curve= 0 ,0
Exp/Cntr=0.3,0.1

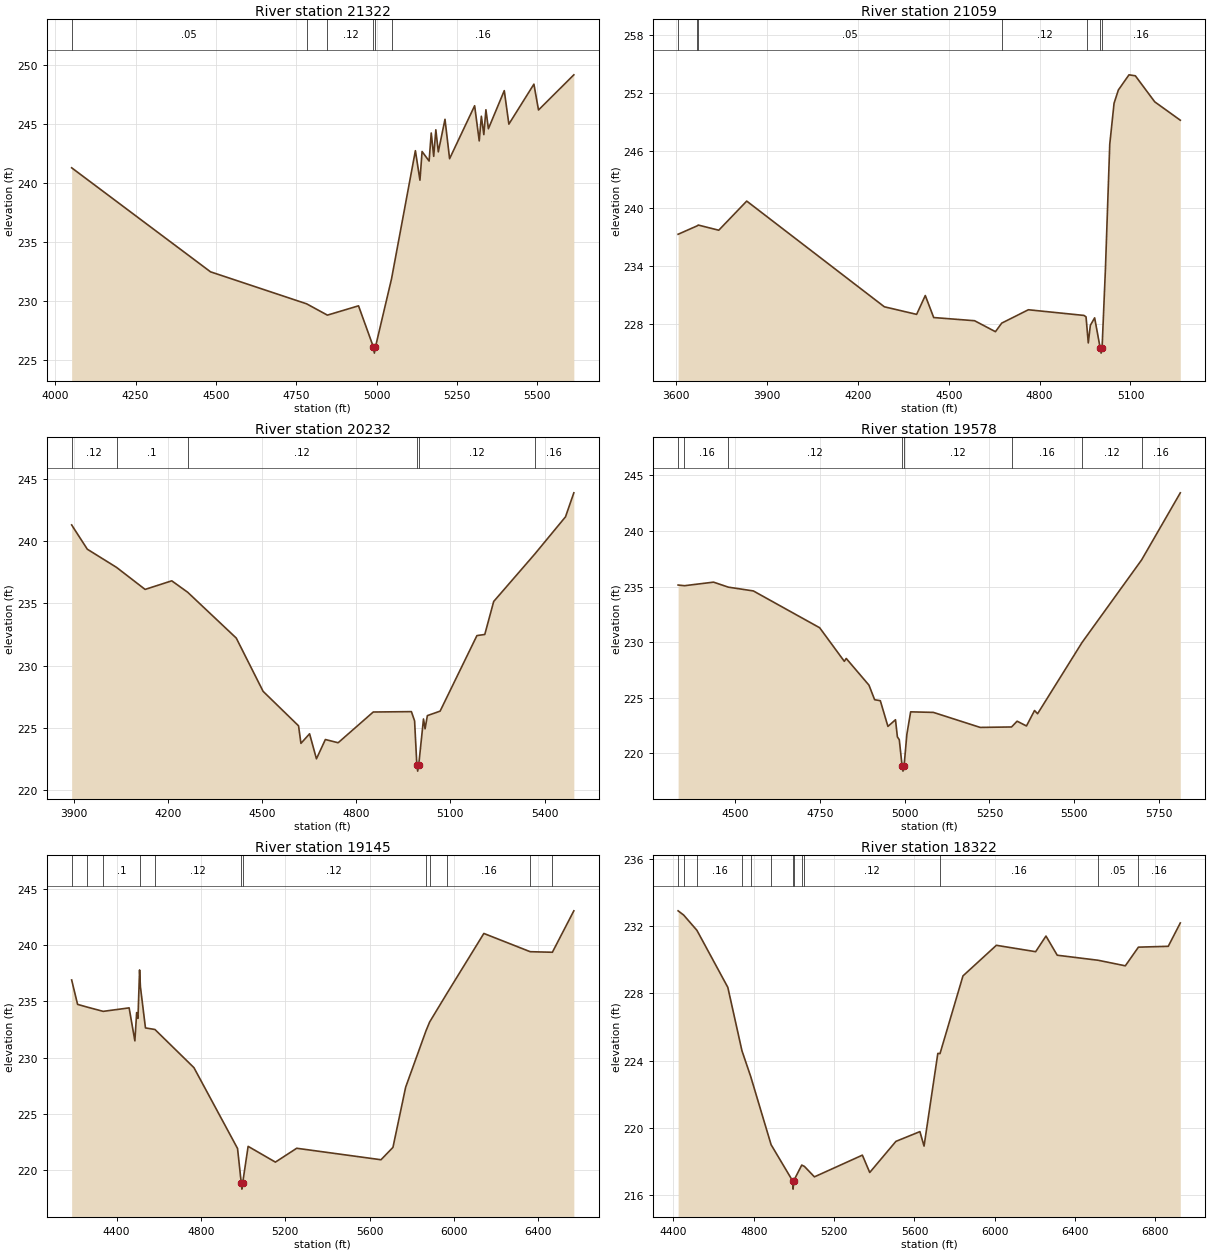
Type RM Length L Ch R = 1 ,21322   ,263,263,263
BEGIN DESCRIPTION:
MILLICAN CREEK 36.0
END DESCRIPTION:
XS GIS Cut Line= 3
      3603510.69     10167651.06      3604118.35      10167005.2
      3604558.19     10166492.63
#Sta/Elev= 30
  4051.2  241.28  4483.3  232.46  4782.1  229.75  4846.8  228.79  4943.6  229.58
  4990.1  226.07  4992.9  225.57  4996.1  226.07  5046.3  231.87  5120.5  242.73
  5134.7  240.23  5141.3  242.66  5163.2  241.85  5169.8  244.23  5177.5  242.25
  5184.1   244.5  5191.8  242.63  5212.6  245.39  5226.9  242.05  5304.8  246.54
  5319.1  243.56  5325.7  245.65  5333.4  244.09  5339.9   246.2  5347.6  244.59
    5397  247.82  5411.3  244.98  5489.2  248.37  5503.5  246.18  5613.4  249.16
#Mann= 6 ,-1 , 0
  4051.2     .05       0  4782.1      .1       0  4846.8     .12       0
  4990.1     .07       0  4996.1     .12       0  5046.3     .16       0
Bank Sta=4990.1,4996.1
XS Rating Curve= 0 ,0
Exp/Cntr=0.3,0.1

Type RM Length L Ch R = 1 ,21059   ,827,827,827
BEGIN DESCRIPTION:
MILLICAN CREEK 35.0
END DESCRIPTION:
XS GIS Cut Line= 3
      3603471.85     10168010.46      3604143.71     10167203.19
      3604591.63     10166791.73
#Sta/Elev= 30
  3606.1  237.32  3670.1  238.21  3672.4  238.28  3740.3  237.74  3832.7  240.77
  4287.1  229.78  4393.8  228.99  4422.4  230.95  4450.2  228.66  4585.2  228.33
  4654.1  227.19  4674.8  228.08  4762.8  229.47  4946.5  228.88  4953.3  228.73
  4956.7  227.48  4960.7  226.02  4967.5  227.85  4981.7  228.63  5000.2  225.46
    5003  224.96  5006.2  225.46  5017.4  233.77  5031.6  246.67  5045.8  250.94
    5060  252.32  5095.1   253.9  5116.1   253.8  5180.2  251.09  5264.6  249.18
#Mann= 7 ,-1 , 0
  3606.1     .05       0  3670.1     .16       0  3672.4     .05       0
  4674.8     .12       0  4956.7     .16       0  5000.2     .07       0
  5006.2     .16       0
Bank Sta=5000.2,5006.2
XS Rating Curve= 0 ,0
Exp/Cntr=0.3,0.1

Type RM Length L Ch R = 1 ,20232   ,654,654,654
BEGIN DESCRIPTION:
MILLICAN CREEK 34.0
END DESCRIPTION:
XS GIS Cut Line= 3
      3604042.08     10168191.67      3604596.84     10167557.36
      3604732.26     10166812.54
#Sta/Elev= 30
  3893.5   241.3  3943.4  239.35  4036.5  237.89  4127.5  236.12  4212.4  236.81
  4263.2  235.89  4417.9  232.21  4503.4  227.93  4616.3  225.16  4623.9  223.75
  4651.4  224.52  4673.3  222.51  4701.7  224.06  4742.4   223.8  4854.2  226.27
  4975.8   226.3  4985.9  225.56  4993.1  222.02  4995.8  221.52  4999.1  222.02
  5014.3  225.71  5019.3  224.92  5026.6  225.98  5067.2  226.34  5184.5  232.41
  5209.5   232.5  5237.9  235.15  5368.4  238.95  5466.6  241.95  5493.2  243.88
#Mann= 6 ,-1 , 0
  3893.5     .12       0  4036.5      .1       0  4263.2     .12       0
  4993.1     .07       0  4999.1     .12       0  5368.4     .16       0
Bank Sta=4993.1,4999.1
XS Rating Curve= 0 ,0
Exp/Cntr=0.3,0.1

Type RM Length L Ch R = 1 ,19578   ,433,433,433
BEGIN DESCRIPTION:
MILLICAN CREEK 33.0
END DESCRIPTION:
XS GIS Cut Line= 3
      3604747.87     10168125.07      3605122.88     10167375.07
      3604935.37     10166760.47
#Sta/Elev= 30
    4332  235.14  4350.7  235.08  4436.5   235.4  4480.1  234.95  4553.9  234.61
  4749.5   231.3  4822.2  228.28  4827.8  228.54  4894.9  226.14  4911.6  224.83
  4928.4  224.74  4950.8  222.43  4973.1  223.03  4978.7  221.49  4984.3  221.23
  4992.5  218.91  4995.2  218.41  4998.5  218.91  5006.7  221.73  5017.8  223.74
  5084.9  223.69  5222.9  222.34  5315.4  222.38  5331.8   222.9  5359.4  222.47
  5383.2  223.86  5392.2  223.57  5523.4  229.98    5699   237.4  5813.1  243.43
#Mann= 8 ,-1 , 0
    4332     .12       0  4350.7     .16       0  4480.1     .12       0
  4992.5     .07       0  4998.5     .12       0  5315.4     .16       0
  5523.4     .12       0    5699     .16       0
Bank Sta=4992.5,4998.5
XS Rating Curve= 0 ,0
Exp/Cntr=0.3,0.1

Type RM Length L Ch R = 1 ,19145   ,823,823,823
BEGIN DESCRIPTION:
MILLICAN CREEK 31.0
END DESCRIPTION:
XS GIS Cut Line= 3
      3604892.09     10168441.67      3605482.25     10167635.48
      3605378.14     10166255.92
#Sta/Elev= 30
  4186.8  236.91    4215  234.74  4260.4   234.5  4336.5  234.12  4459.5  234.43
  4486.8   231.5  4495.2  234.01  4501.4   233.5  4509.1   237.8  4513.1   236.3
    4537  232.65  4581.9  232.51    4767  229.12  4973.9  221.94  4991.8  218.83
  4994.5  218.33  4997.8  218.83  5024.1  222.13  5153.5  220.73  5254.6  221.96
  5654.5  220.94  5711.2  222.04  5771.4  227.38  5867.9  232.39  5885.4  233.18
  5966.2  235.68  6142.5  241.04  6362.3  239.42  6467.6  239.37  6569.4  243.05
#Mann= 12 ,-1 , 0
  4186.8     .05       0  4260.4     .12       0  4336.5      .1       0
  4513.1     .16       0  4581.9     .12       0  4991.8     .07       0
  4997.8     .12       0  5867.9     .16       0  5885.4     .12       0
  5966.2     .16       0  6362.3     .07       0  6467.6     .16       0
Bank Sta=4991.8,4997.8
XS Rating Curve= 0 ,0
Exp/Cntr=0.3,0.1

Type RM Length L Ch R = 1 ,18322   ,899,899,899
BEGIN DESCRIPTION:
MILLICAN CREEK 30.0
END DESCRIPTION:
XS GIS Cut Line= 3
      3605342.09     10168691.65      3605956.21     10168078.19
       3606342.1     10166491.68
#Sta/Elev= 30
    4423  232.91  4450.5  232.66  4516.7  231.75  4670.5  228.36  4740.9  224.59
  4784.4  223.06  4886.1     219  4992.8  216.86  4995.5  216.36  4998.8  216.86
  5038.6  217.79    5052  217.71  5101.8  217.09  5340.6  218.38  5377.2  217.35
  5507.6   219.2  5627.1  219.78  5647.7  218.92  5716.3  224.43  5727.2  224.42
  5841.5  229.04  6007.9  230.86  6203.4  230.48  6254.9  231.41  6310.9  230.27
  6514.8  229.97    6650  229.64  6715.2  230.75  6863.8   230.8  6923.8  232.19
#Mann= 13 ,-1 , 0
    4423     .16       0  4450.5      .1       0  4516.7     .16       0
  4740.9     .05       0  4784.4     .16       0  4886.1     .05       0
  4992.8     .03       0  4998.8     .05       0  5038.6     .16       0
    5052     .12       0  5727.2     .16       0  6514.8     .05       0
  6715.2     .16       0
Bank Sta=4992.8,4998.8
XS Rating Curve= 0 ,0
Exp/Cntr=0.3,0.1

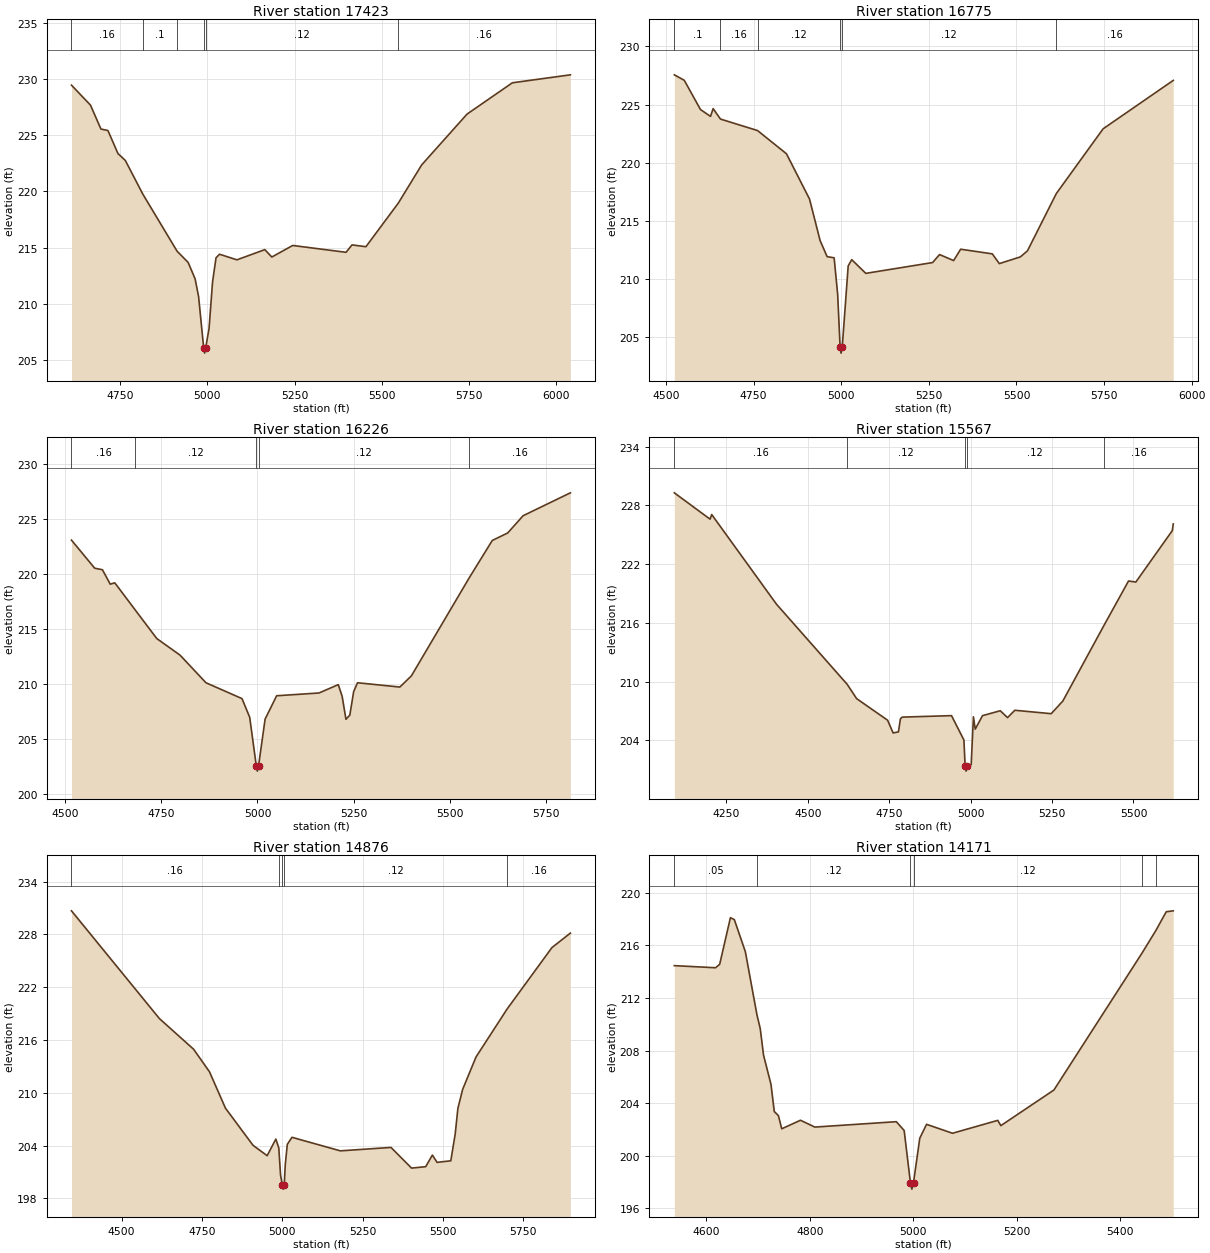
Type RM Length L Ch R = 1 ,17423   ,648,648,648
BEGIN DESCRIPTION:
MILLICAN CREEK 28.0
END DESCRIPTION:
XS GIS Cut Line= 3
      3606534.34     10168776.13      3606542.11     10168391.64
      3606555.15     10167345.19
#Sta/Elev= 30
  4610.1  229.47  4664.6  227.69  4694.6  225.56  4714.6  225.43  4743.4  223.38
  4764.6  222.76  4814.8  219.76    4913  214.68  4944.7  213.68  4964.7  212.22
  4974.7  210.64  4989.2   206.1  4991.9   205.6  4995.2   206.1  5004.7  207.79
  5014.7  211.93  5024.7  214.09  5034.7  214.41  5084.7  213.91  5164.7  214.82
  5184.7  214.16  5244.7  215.19  5397.7  214.58  5414.7  215.24  5454.7  215.08
  5547.5  218.96  5614.7  222.37  5744.7  226.89  5874.7  229.68  6041.2  230.39
#Mann= 6 ,-1 , 0
  4610.1     .16       0  4814.8      .1       0    4913     .12       0
  4989.2     .07       0  4995.2     .12       0  5547.5     .16       0
Bank Sta=4989.2,4995.2
XS Rating Curve= 0 ,0
Exp/Cntr=0.3,0.1

Type RM Length L Ch R = 1 ,16775   ,549,549,549
BEGIN DESCRIPTION:
MILLICAN CREEK 27.0
END DESCRIPTION:
XS GIS Cut Line= 3
      3607065.58     10168812.59      3607180.17     10168557.36
      3607091.63     10167416.76
#Sta/Elev= 30
  4523.7  227.56    4552  227.09  4598.3  224.57    4627  223.98  4634.4  224.65
  4655.3  223.75  4761.2  222.76  4843.7  220.76  4909.5  216.86  4939.6  213.29
  4959.7   211.9  4979.7   211.8  4989.8  208.65  4996.8  204.09  4999.5  203.59
  5002.8  204.09  5019.8   211.1  5029.9  211.64    5070  210.46  5260.6  211.39
  5280.6  212.08  5320.7  211.56  5340.8  212.54  5431.1  212.14  5451.1   211.3
  5511.3  211.88  5531.4   212.4  5613.9  217.34  5747.3  222.91  5947.5  227.08
#Mann= 6 ,-1 , 0
  4523.7      .1       0  4655.3     .16       0  4761.2     .12       0
  4996.8     .07       0  5002.8     .12       0  5613.9     .16       0
Bank Sta=4996.8,5002.8
XS Rating Curve= 0 ,0
Exp/Cntr=0.3,0.1

Type RM Length L Ch R = 1 ,16226   ,659,659,659
BEGIN DESCRIPTION:
MILLICAN CREEK 25.0
END DESCRIPTION:
XS GIS Cut Line= 3
      3607730.65     10168761.46      3607680.65     10168361.43
      3607674.96      10167468.8
#Sta/Elev= 30
    4517  223.08  4577.3  220.53  4597.4  220.39  4617.6  219.08  4629.5   219.2
  4683.1  216.71  4738.5  214.14    4799  212.63  4866.3  210.12  4959.9  208.68
  4979.9  206.98  4996.9  202.59  4999.7  202.09  5002.9  202.59  5019.9  206.82
  5049.9  208.94  5159.9  209.19  5209.9  209.95  5219.9   208.9  5229.9   206.8
  5239.9  207.18  5249.9  209.32  5259.9  210.12  5369.9  209.73  5399.9  210.75
  5550.1  219.66  5609.9  223.05  5649.9  223.73    5690   225.3  5812.8  227.38
#Mann= 5 ,-1 , 0
    4517     .16       0  4683.1     .12       0  4996.9     .07       0
  5002.9     .12       0  5550.1     .16       0
Bank Sta=4996.9,5002.9
XS Rating Curve= 0 ,0
Exp/Cntr=0.3,0.1

Type RM Length L Ch R = 1 ,15567   ,691,691,691
BEGIN DESCRIPTION:
MILLICAN CREEK 24.0
END DESCRIPTION:
XS GIS Cut Line= 3
       3608469.2     10168801.06      3608369.19     10168301.02
      3607914.83     10167386.06
#Sta/Elev= 30
  4090.6  229.29  4200.2   226.6  4205.3  227.07  4404.1  217.91  4621.2  209.72
  4650.1  208.26  4745.3  206.05  4762.2  204.75  4778.5  204.86  4784.6   206.2
  4790.2  206.37  4941.4  206.52  4979.5  204.03  4983.2  201.35    4986  200.85
  4989.2  201.35  5001.8  201.52  5008.7   206.4  5014.2  205.14  5036.6  206.52
  5091.1  207.02  5113.4  206.32  5135.8  207.07  5247.4  206.72  5283.1  208.01
  5408.4  215.68  5484.8  220.28  5507.2  220.17  5619.2  225.43  5622.1  226.11
#Mann= 5 ,-1 , 0
  4090.6     .16       0  4621.2     .12       0  4983.2     .07       0
  4989.2     .12       0  5408.4     .16       0
Bank Sta=4983.2,4989.2
XS Rating Curve= 0 ,0
Exp/Cntr=0.3,0.1

Type RM Length L Ch R = 1 ,14876   ,705,705,705
BEGIN DESCRIPTION:
MILLICAN CREEK 22.0
END DESCRIPTION:
XS GIS Cut Line= 3
        3609201.     10168359.43      3608898.92     10168036.52
      3608242.12     10167141.67
#Sta/Elev= 30
    4344  230.69  4617.4  218.45  4723.9  214.96  4773.3   212.4  4823.1  208.26
  4908.8  204.04  4952.8  202.86  4979.8  204.75    4989  203.74  4994.5  200.63
  4999.9  199.56  5002.7  199.06  5005.9  199.56  5009.1  201.84  5015.5  204.15
    5030  204.95  5180.5  203.41    5338   203.8    5402  201.45  5445.9  201.61
  5466.8  202.93  5481.4   202.1  5524.1  202.28  5537.8  205.32  5546.2  208.24
  5560.9  210.39  5602.6  214.08  5698.7   219.5  5838.7  226.51  5896.2  228.16
#Mann= 5 ,-1 , 0
    4344     .16       0    4989     .12       0  4999.9     .07       0
  5005.9     .12       0  5698.7     .16       0
Bank Sta=4999.9,5005.9
XS Rating Curve= 0 ,0
Exp/Cntr=0.3,0.1

Type RM Length L Ch R = 1 ,14171   ,649,649,649
BEGIN DESCRIPTION:
MILLICAN CREEK 21.0
END DESCRIPTION:
XS GIS Cut Line= 3
      3609332.75     10167593.74      3609082.73     10167393.73
      3608542.06     10167041.62
#Sta/Elev= 30
  4537.8  214.46  4617.5   214.3  4625.5  214.56  4646.3  218.11  4653.9  217.96
  4675.2  215.52  4697.6  210.73    4704  209.67  4710.4  207.65  4724.8  205.43
  4731.2  203.36  4739.2  203.05  4745.6  202.05  4781.9   202.7  4809.6  202.18
  4967.3  202.59  4982.5  201.92  4994.6  197.96  4997.4  197.46  5000.6  197.96
  5012.7  201.33  5025.8  202.39    5076  201.71  5163.6  202.69  5169.6  202.29
  5272.3     205    5443  215.43  5469.5  217.13  5489.6  218.56  5503.2  218.63
#Mann= 6 ,-1 , 0
  4537.8     .05       0  4697.6     .12       0  4994.6     .07       0
  5000.6     .12       0    5443      .1       0  5469.5     .16       0
Bank Sta=4994.6,5000.6
XS Rating Curve= 0 ,0
Exp/Cntr=0.3,0.1

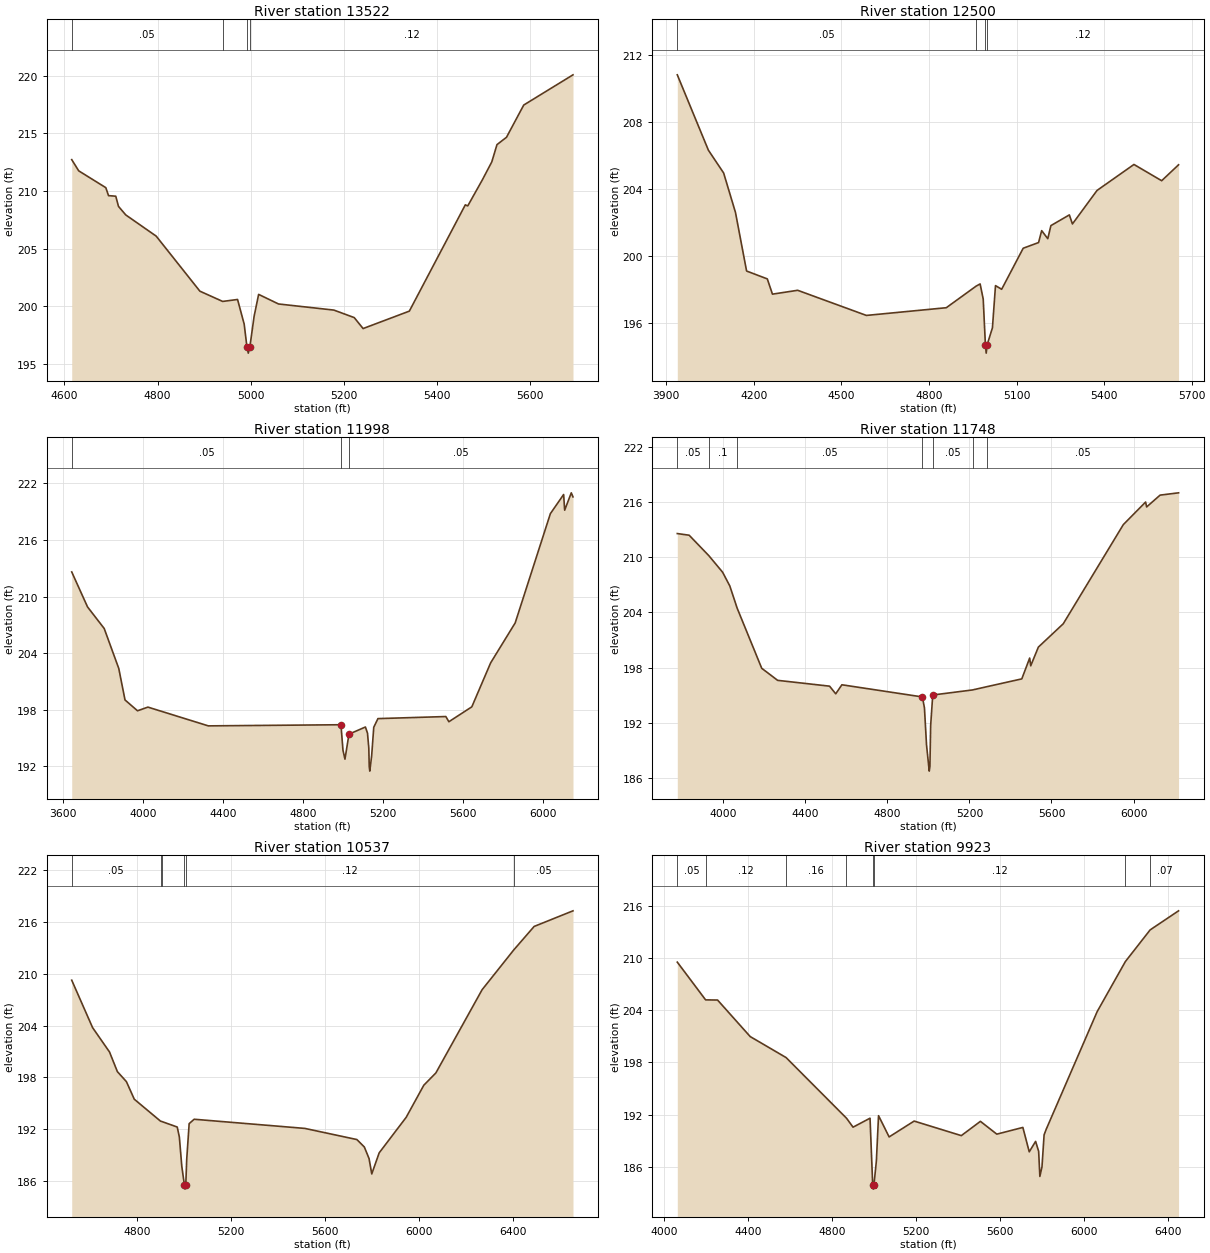
Type RM Length L Ch R = 1 ,13522   ,1022,1022,1022
BEGIN DESCRIPTION:
MILLICAN CREEK 19.0
END DESCRIPTION:
XS GIS Cut Line= 3
      3609617.84     10167065.63      3609143.71     10166781.32
      3608646.81     10166612.61
#Sta/Elev= 30
  4615.6  212.72  4630.6  211.75  4688.9  210.29  4694.7   209.6  4710.3  209.55
  4716.1  208.67  4731.7  207.93  4797.2  206.09  4891.1  201.32  4940.1  200.43
  4972.1   200.6  4986.3  198.47  4992.4  196.45  4995.2  195.95  4998.4  196.45
  5007.7  199.14  5017.4  201.04  5060.2  200.21  5179.2  199.68  5222.9  199.03
    5242  198.08  5341.4  199.59  5461.7   208.8    5467  208.71  5498.4  210.97
  5518.6  212.52  5529.8  214.02  5550.3  214.66  5587.3  217.45  5693.2  220.07
#Mann= 4 ,-1 , 0
  4615.6     .05       0  4940.1     .12       0  4992.4     .07       0
  4998.4     .12       0
Bank Sta=4992.4,4998.4
XS Rating Curve= 0 ,0
Exp/Cntr=0.3,0.1

Type RM Length L Ch R = 1 ,12500   ,502,502,502
BEGIN DESCRIPTION:
MILLICAN CREEK 18.0
END DESCRIPTION:
XS GIS Cut Line= 3
      3609636.04     10166953.63      3609367.11     10166066.64
      3608617.13     10165816.65
#Sta/Elev= 30
  3937.8  210.81  4044.4  206.31  4096.6  204.95  4137.1   202.6  4175.2   199.1
  4246.2  198.63  4263.8  197.72  4350.2  197.95  4585.7  196.45  4859.4  196.91
  4961.8   198.2  4975.3  198.33  4985.9  197.43  4993.4   194.7  4996.2   194.2
  4999.4   194.7  5017.5  195.71    5028  198.23  5049.1  198.01  5122.9  200.46
  5175.6   200.8  5186.2  201.51  5207.2  201.03  5217.8  201.81    5281  202.45
  5291.6  201.91  5375.9  203.91  5502.4  205.46  5597.3  204.49  5655.2  205.44
#Mann= 4 ,-1 , 0
  3937.8     .05       0  4961.8     .12       0  4993.4     .07       0
  4999.4     .12       0
Bank Sta=4993.4,4999.4
XS Rating Curve= 0 ,0
Exp/Cntr=0.3,0.1

Type RM Length L Ch R = 1 ,11998   ,250,250,250
BEGIN DESCRIPTION:
MILLICAN CREEK 17.0
END DESCRIPTION:
XS GIS Cut Line= 4
      3609665.27     10166967.52      3609454.77     10166244.87
      3609426.56     10165582.98      3609739.07     10164536.94
#Sta/Elev= 30
  3642.5  212.61  3721.5   208.9  3804.9  206.61  3877.8  202.37    3909  199.03
  3971.5  197.88  4023.6  198.27  4325.6  196.28    4989   196.4    4999   193.7
    5009  192.75    5029   195.4  5111.3  196.16  5121.7  195.51  5128.2  193.94
  5130.4  191.98  5133.2  191.48  5142.6  193.13    5153  196.13  5173.9  197.05
  5513.4  197.27  5528.7  196.72  5643.5   198.3  5737.5  202.96  5860.3   207.2
  6036.3  218.79  6102.6  220.82  6107.8  219.16  6140.9     221  6149.4  220.57
#Mann= 3 , 0 , 0
  3642.5     .05       0    4989    .035       0    5029     .05       0
Bank Sta=4989,5029
XS Rating Curve= 0 ,0
Exp/Cntr=0.3,0.1

Type RM Length L Ch R = 1 ,11748   ,1211,1211,1211
BEGIN DESCRIPTION:
MILLICAN CREEK 16.0
END DESCRIPTION:
XS GIS Cut Line= 4
      3610053.72     10166691.91      3609673.95     10166292.61
      3609643.57     10165854.25      3609849.49     10164414.98
#Sta/Elev= 30
  3775.3  212.56  3833.1  212.38  3929.1  210.16  3996.1  208.37  4031.3  206.88
  4067.3  204.46    4187  197.94  4264.7  196.63  4517.8     196  4547.9  195.17
  4577.9  196.15  4970.4  194.83  4980.5  193.65  4990.6  189.64  5003.9  186.78
  5007.2  187.28  5010.8  191.73    5021  195.04  5215.1  195.59  5286.4  195.95
  5455.3  196.79  5493.7  199.05  5498.8  198.21  5536.1  200.24  5657.4  202.77
  5950.3  213.53    6059  215.98  6064.1  215.45  6129.7  216.73  6219.7  216.98
#Mann= 7 ,-1 , 0
  3775.3     .05       0  3929.1      .1       0  4067.3     .05       0
  4970.4    .035       0    5021     .05       0  5215.1     .12       0
  5286.4     .05       0
Bank Sta=4970.4,5021
XS Rating Curve= 0 ,0
Exp/Cntr=0.3,0.1

Type RM Length L Ch R = 1 ,10537   ,614,614,614
BEGIN DESCRIPTION:
MILLICAN CREEK 15.0
END DESCRIPTION:
XS GIS Cut Line= 3
      3610492.11     10166341.61      3610706.21     10165609.44
       3611138.5     10164307.36
#Sta/Elev= 30
  4520.6  209.26  4609.4  203.77  4681.5  200.95  4714.9  198.68  4753.6  197.51
    4787  195.48  4898.8  192.94  4903.9   192.9  4969.9  192.26    4979   191.1
  4989.4  187.71  5000.3  185.57  5003.1  185.07  5006.3  185.57  5010.3   188.5
  5020.7  192.65    5042  193.16  5513.3   192.1    5735  190.81  5766.7  189.95
  5786.9  188.61  5798.4  186.83    5830  189.27  5944.9  193.38  6020.1   197.1
  6071.4  198.52  6268.2  208.15  6402.8  212.75  6489.9  215.48  6655.4  217.29
#Mann= 6 ,-1 , 0
  4520.6     .05       0  4898.8     .16       0  4903.9     .12       0
  5000.3     .07       0  5006.3     .12       0  6402.8     .05       0
Bank Sta=5000.3,5006.3
XS Rating Curve= 0 ,0
Exp/Cntr=0.3,0.1

Type RM Length L Ch R = 1 ,9923    ,850,850,850
BEGIN DESCRIPTION:
MILLICAN CREEK 14.0
END DESCRIPTION:
XS GIS Cut Line= 3
      3610674.93     10166765.73       3611138.5     10166265.69
      3611398.91     10164578.23
#Sta/Elev= 30
  4063.1   209.5    4198  205.17  4255.1  205.15  4410.5  200.96  4581.6  198.55
  4869.6  191.59  4900.8  190.56  4981.8  191.59  4994.5  183.95  4997.3  183.45
  5000.5  183.95  5012.1   186.7  5022.3  191.88  5072.8  189.44    5192  191.26
  5416.9  189.59  5507.9  191.23    5586  189.76  5710.3  190.53  5740.7  187.73
    5771  188.93  5785.5  187.79  5791.3  184.91  5801.4  186.01  5811.5  189.68
  5821.6  190.32  6064.4  203.82  6198.7  209.56  6316.9   213.2  6452.4  215.39
#Mann= 8 ,-1 , 0
  4063.1     .05       0    4198     .12       0  4581.6     .16       0
  4869.6     .12       0  4994.5     .07       0  5000.5     .12       0
  6198.7     .16       0  6316.9     .07       0
Bank Sta=4994.5,5000.5
XS Rating Curve= 0 ,0
Exp/Cntr=0.3,0.1

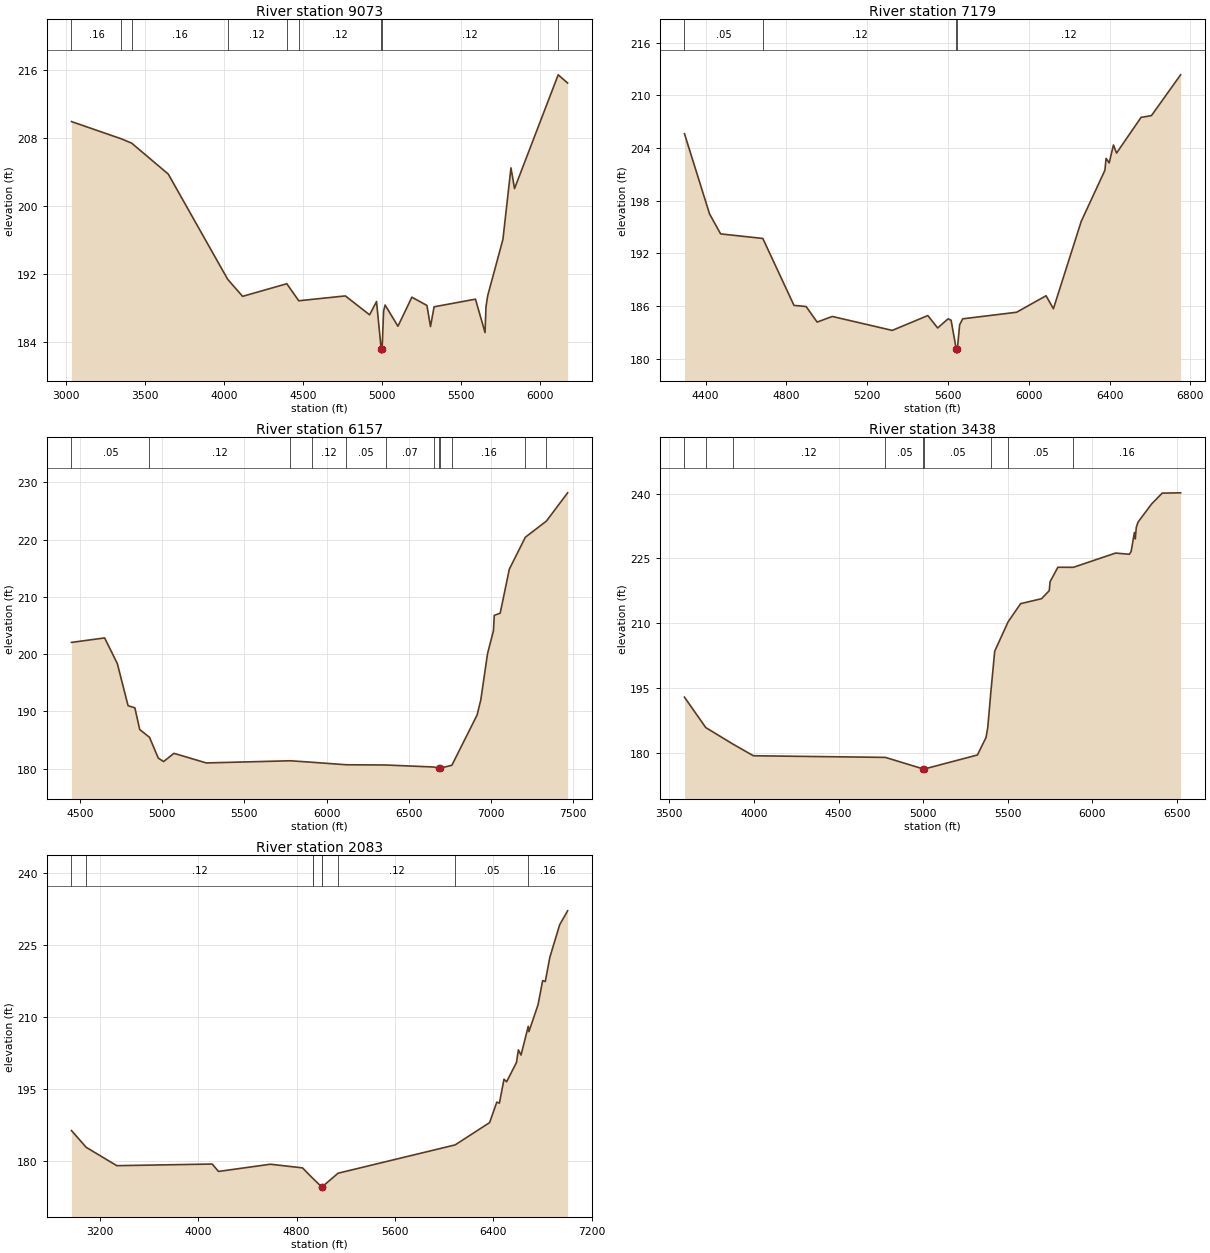
Type RM Length L Ch R = 1 ,9073    ,1894,1894,1894
BEGIN DESCRIPTION:
MILLICAN CREEK 12.0
END DESCRIPTION:
XS GIS Cut Line= 3
      3610983.97     10167571.29      3612016.98     10165652.84
      3611600.77     10164785.75
#Sta/Elev= 30
  3034.4  209.92  3350.3  207.89  3415.8  207.38  3647.2  203.75  4023.3  191.39
  4117.7  189.39  4397.5  190.87  4473.2  188.87  4768.3  189.44  4921.6  187.22
  4965.5  188.78  4994.9  183.22  4997.7  182.72  5000.9  183.22  5010.2  187.65
  5019.8  188.37  5101.1  185.88  5189.4  189.29  5284.5  188.32  5307.2  185.84
  5329.8  188.16  5591.8  189.06  5652.4  185.14  5658.3  188.15  5669.4  189.48
  5765.6  196.08  5816.5  204.48  5839.1  202.05  6115.5  215.41  6175.1  214.45
#Mann= 9 ,-1 , 0
  3034.4     .16       0  3350.3     .05       0  3415.8     .16       0
  4023.3     .12       0  4397.5     .16       0  4473.2     .12       0
  4994.9     .07       0  5000.9     .12       0  6115.5     .16       0
Bank Sta=4994.9,5000.9
XS Rating Curve= 0 ,0
Exp/Cntr=0.3,0.1

Type RM Length L Ch R = 1 ,7179    ,1022,1022,1022
BEGIN DESCRIPTION:
MILLICAN CREEK 10.0
END DESCRIPTION:
XS GIS Cut Line= 3
      3613892.13     10165891.65      3613242.11     10165641.64
      3611756.87     10164698.18
#Sta/Elev= 30
  4295.6  205.63  4419.9  196.48  4474.6  194.21  4683.5  193.69  4837.8  186.06
  4897.8  185.93  4952.4  184.16  5027.6   184.8  5324.1  183.21  5500.2   184.9
  5548.9  183.49  5600.2  184.52  5615.4  184.38  5640.6  181.12  5643.4  180.62
  5646.6  181.12  5657.8  183.85    5673  184.53  5939.8  185.28  6085.5  187.16
  6121.9  185.68  6259.7  195.64  6376.8  201.46  6382.8  202.82    6398   202.3
  6419.2  204.34  6434.4  203.42  6555.9  207.49  6607.2  207.69  6751.6  212.34
#Mann= 4 ,-1 , 0
  4295.6     .05       0  4683.5     .12       0  5640.6     .07       0
  5646.6     .12       0
Bank Sta=5640.6,5646.6
XS Rating Curve= 0 ,0
Exp/Cntr=0.3,0.1

Type RM Length L Ch R = 1 ,6157    ,2719,2719,2719
BEGIN DESCRIPTION:
MILLICAN CREEK 8.0
END DESCRIPTION:
XS GIS Cut Line= 3
      3614265.23     10165829.91      3613900.66     10164944.51
      3613397.17     10162947.93
#Sta/Elev= 30
  4448.6  202.05  4650.3  202.83  4727.5  198.34  4792.8  190.99  4834.1  190.62
  4863.5  186.83    4923  185.47  4976.6  181.83  5009.1  181.23  5071.3  182.67
  5268.6  180.99  5779.7  181.37  5910.8  181.11  6119.8  180.67  6359.7  180.63
  6651.2  180.28  6682.6  180.06  6685.3  179.56  6688.6  180.06  6761.6  180.59
  6914.8  189.36  6937.2  191.98  6978.3  200.08  7014.2  204.07  7019.3  206.77
  7055.3  207.16  7110.7  214.83  7208.1  220.42  7336.6  223.25  7465.2  228.18
#Mann= 12 ,-1 , 0
  4448.6     .05       0    4923     .12       0  5779.7     .05       0
  5910.8     .12       0  6119.8     .05       0  6359.7     .07       0
  6651.2     .12       0  6682.6     .07       0  6688.6     .12       0
  6761.6     .16       0  7208.1      .1       0  7336.6     .05       0
Bank Sta=6682.6,6688.6
XS Rating Curve= 0 ,0
Exp/Cntr=0.3,0.1

Type RM Length L Ch R = 1 ,3438    ,1355,1355,1355
BEGIN DESCRIPTION:
MILLICAN CREEK 5.0
END DESCRIPTION:
XS GIS Cut Line= 3
      3615684.47     10165749.97      3615884.47     10165349.98
      3615394.06     10162914.98
#Sta/Elev= 30
  3589.7  192.84  3715.5   185.8  3874.8     182    3997  179.27  4776.6  178.89
  5001.3  176.21    5004  175.71  5007.3  176.21  5320.5  179.45  5371.5  183.52
  5381.7  185.88  5400.8  194.46  5422.5  203.48  5501.9  210.29  5575.5  214.49
    5699  215.64  5744.7   217.5  5749.8  219.58  5795.6  222.92  5887.5  222.91
  6136.6  226.21  6218.2  225.93  6228.4  226.56  6247.9  230.98    6253  229.49
    6259  232.17  6269.2  233.38  6349.6  237.58    6412  240.09  6520.8  240.16
#Mann= 9 ,-1 , 0
  3589.7     .05       0  3715.5     .16       0  3874.8     .12       0
  4776.6     .05       0  5001.3     .03       0  5007.3     .05       0
  5400.8     .16       0  5501.9     .05       0  5887.5     .16       0
Bank Sta=5001.3,5007.3
XS Rating Curve= 0 ,0
Exp/Cntr=0.3,0.1

Type RM Length L Ch R = 1 ,2083    ,0,0,0
BEGIN DESCRIPTION:
MILLICAN CREEK 1.0
END DESCRIPTION:
XS GIS Cut Line= 3
      3617060.37     10166211.83      3616817.32      10163520.9
       3615671.5     10162843.82
#Sta/Elev= 30
  2970.7  186.37  3090.4  182.88    3339  179.06  4114.6   179.4  4165.7  177.86
  4587.4  179.36  4848.5   178.6  4930.5  176.47  4931.2  176.45  5003.1  174.68
  5005.8  174.18  5009.1  174.68  5137.7  177.49  6089.1  183.38  6369.4  188.02
  6427.9  192.29  6449.3  192.07  6486.4  197.05  6507.8  196.52  6587.8  200.53
  6603.4  203.16  6624.9  202.08  6683.6  208.05  6689.2  206.96  6763.4  212.56
  6800.5  217.57  6821.9  217.38    6859  222.41    6939   229.2  7003.5  232.09
#Mann= 9 ,-1 , 0
  2970.7     .05       0  3090.4     .12       0  4930.5     .05       0
  4931.2     .07       0  5003.1     .07       0  5009.1     .07       0
  5137.7     .12       0  6089.1     .05       0  6683.6     .16       0
Bank Sta=5003.1,5009.1
XS Rating Curve= 0 ,0
Exp/Cntr=0.3,0.1

Chan Stop Cuts=-1
Use User Specified Reach Order=0
Composite Channel Slope=5