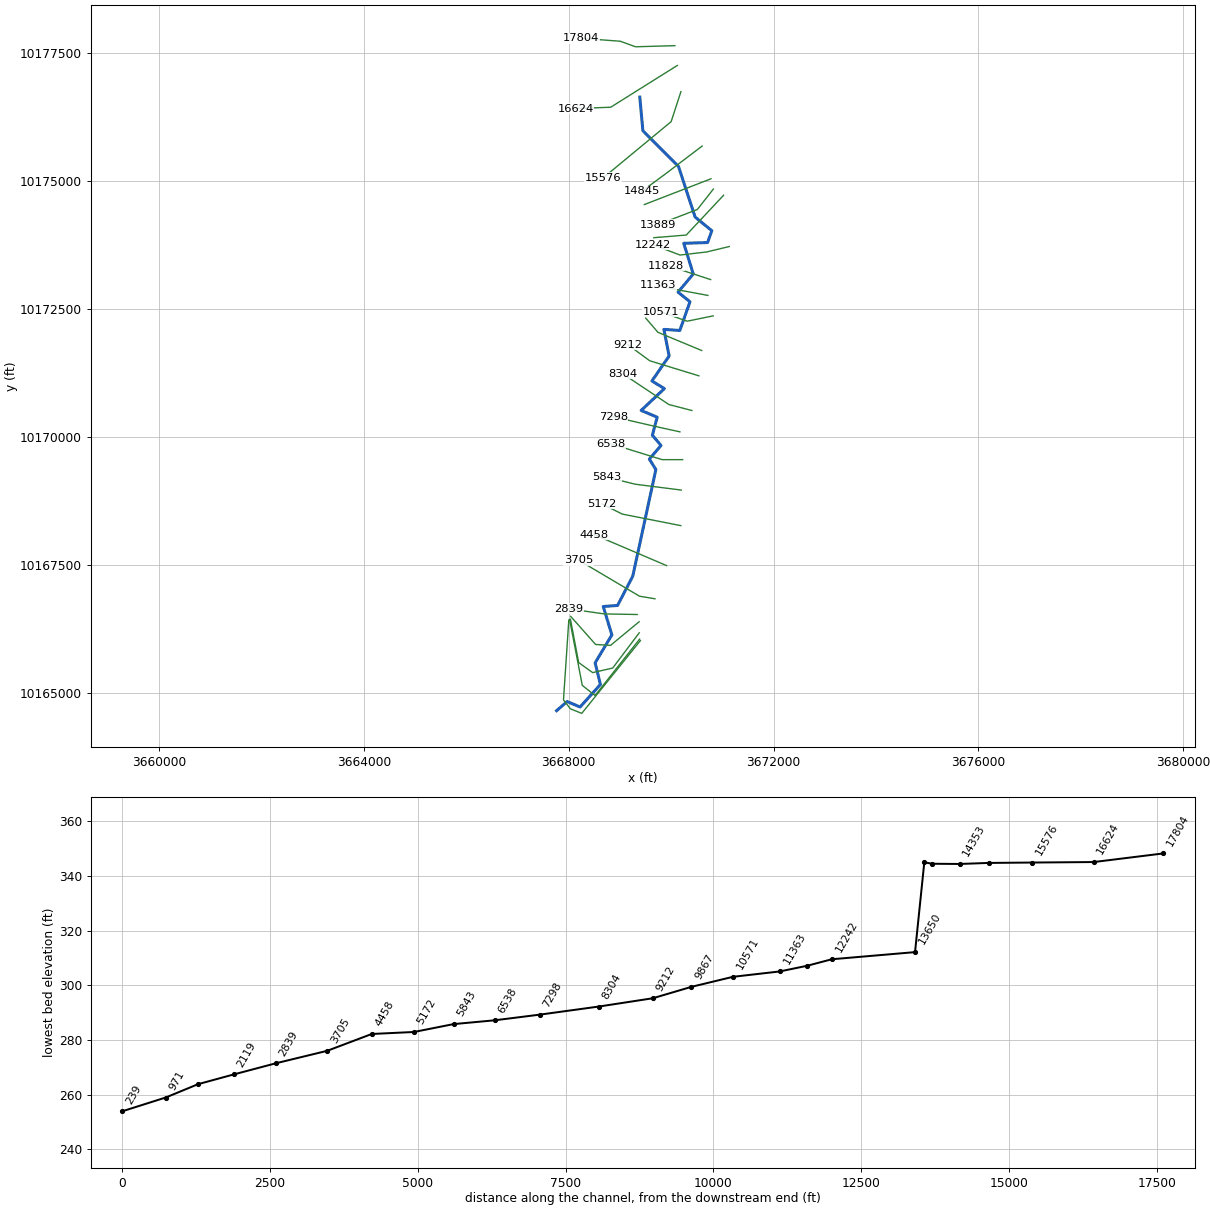
--- NEBLETTS CREEK.prj (project) ---

Proj Title=NEBLETTS CREEK Base Level Engineering
Current Plan=p01
Default Exp/Contr=0.3,0.1
English Units
Geom File=g01
Flow File=f01
Plan File=p01
Y Axis Title=Elevation
X Axis Title(PF)=Main Channel Distance
X Axis Title(XS)=Station
BEGIN DESCRIPTION:
NEBLETTS CREEK
END DESCRIPTION:
DSS Export Rating Curves= 0
DSS Export Rating Curve Sorted= 0
DSS Export Volume Flow Curves= 0
DXF OffsetX= 0
DXF OffsetY= 0
DXF ScaleX= 1
DXF ScaleY= 10

--- NEBLETTS CREEK.p01 (plan) ---

Plan Title=Multiple Run
Short Identifier=Multiple
Geom File=g01
Flow File=f01
Subcritical Flow
K Sum by GR= 0
Std Step Tol= 0.01
Critical Tol= 0.01
Num of Std Step Trials= 20
Max Error Tol= 0.3
Flow Tol Ratio= 0.001
Split Flow NTrial= 30
Split Flow Tol= 0.02
Split Flow Ratio= 0.02
Log Output Level= 0
Friction Slope Method= 1
Unsteady Friction Slope Method= 2
Unsteady Bridges Friction Slope Method= 1
Parabolic Critical Depth
Global Vel Dist=  1 , 1 , 1
Global Log Level= 0
CheckData=True
Encroach Param= -1, 0, 0, 0
BEGIN DESCRIPTION:
Multiple Run
END DESCRIPTION:

--- NEBLETTS CREEK.f01 (steady flow) ---

Flow Title=Multiple
Program Version=4.10
Number of Profiles= 7
Profile Names=10-year,25-year,50-year,1pct_min,100-year,1pct_plu,500-year
River Rch & RM=NEBLETTS CREEK,Reach-1         ,17804
    1280    1801    2246    2049    2771    3748    4220
River Rch & RM=NEBLETTS CREEK,Reach-1         ,14845
    1280    1801    2246    2049    2771    3748    4220
River Rch & RM=NEBLETTS CREEK,Reach-1         ,12242
    1538    2164    2697    2456    3321    4492    5040
Boundary for River Rch & Prof#=NEBLETTS CREEK,Reach-1         , 1
Up Type= 0
Dn Type= 3
Dn Slope=0.005
Boundary for River Rch & Prof#=NEBLETTS CREEK,Reach-1         , 2
Up Type= 0
Dn Type= 3
Dn Slope=0.005
Boundary for River Rch & Prof#=NEBLETTS CREEK,Reach-1         , 3
Up Type= 0
Dn Type= 3
Dn Slope=0.005
Boundary for River Rch & Prof#=NEBLETTS CREEK,Reach-1         , 4
Up Type= 0
Dn Type= 3
Dn Slope=0.005
Boundary for River Rch & Prof#=NEBLETTS CREEK,Reach-1         , 5
Up Type= 0
Dn Type= 3
Dn Slope=0.005
Boundary for River Rch & Prof#=NEBLETTS CREEK,Reach-1         , 6
Up Type= 0
Dn Type= 3
Dn Slope=0.005
Boundary for River Rch & Prof#=NEBLETTS CREEK,Reach-1         , 7
Up Type= 0
Dn Type= 3
Dn Slope=0.005
DSS Import GetInterval= 0
DSS Import GetPeak= 0
DSS Import FillOption= 0

--- NEBLETTS CREEK.g01 (geometry) ---

Geom Title=Existing Conditions
Program Version=4.10

River Reach=NEBLETTS CREEK  ,Reach-1
Reach XY= 30
      3669387.13     10176636.51      3669447.69     10175978.97
      3670143.33     10175280.41      3670467.97     10174292.82
      3670794.36      10174026.5      3670710.93      10173795.2
      3670245.61     10173780.48      3670431.49     10173182.05
      3670134.58     10172826.11      3670367.78     10172638.54
      3670168.73     10172078.02      3669858.01     10172099.08
      3669960.48     10171580.34      3669624.14     10171091.48
      3669867.66     10170942.99      3669413.68     10170515.86
      3669726.81     10170384.31      3669632.96     10170031.03
      3669801.47     10169832.34      3669573.53     10169566.16
      3669701.38     10169361.55      3669249.63      10167278.1
      3668952.62      10166707.1      3668673.73     10166685.95
      3668842.05     10166131.68      3668514.99     10165586.04
      3668618.01     10165163.38      3668221.47     10164723.64
      3667967.26     10164830.23      3667762.11     10164651.64

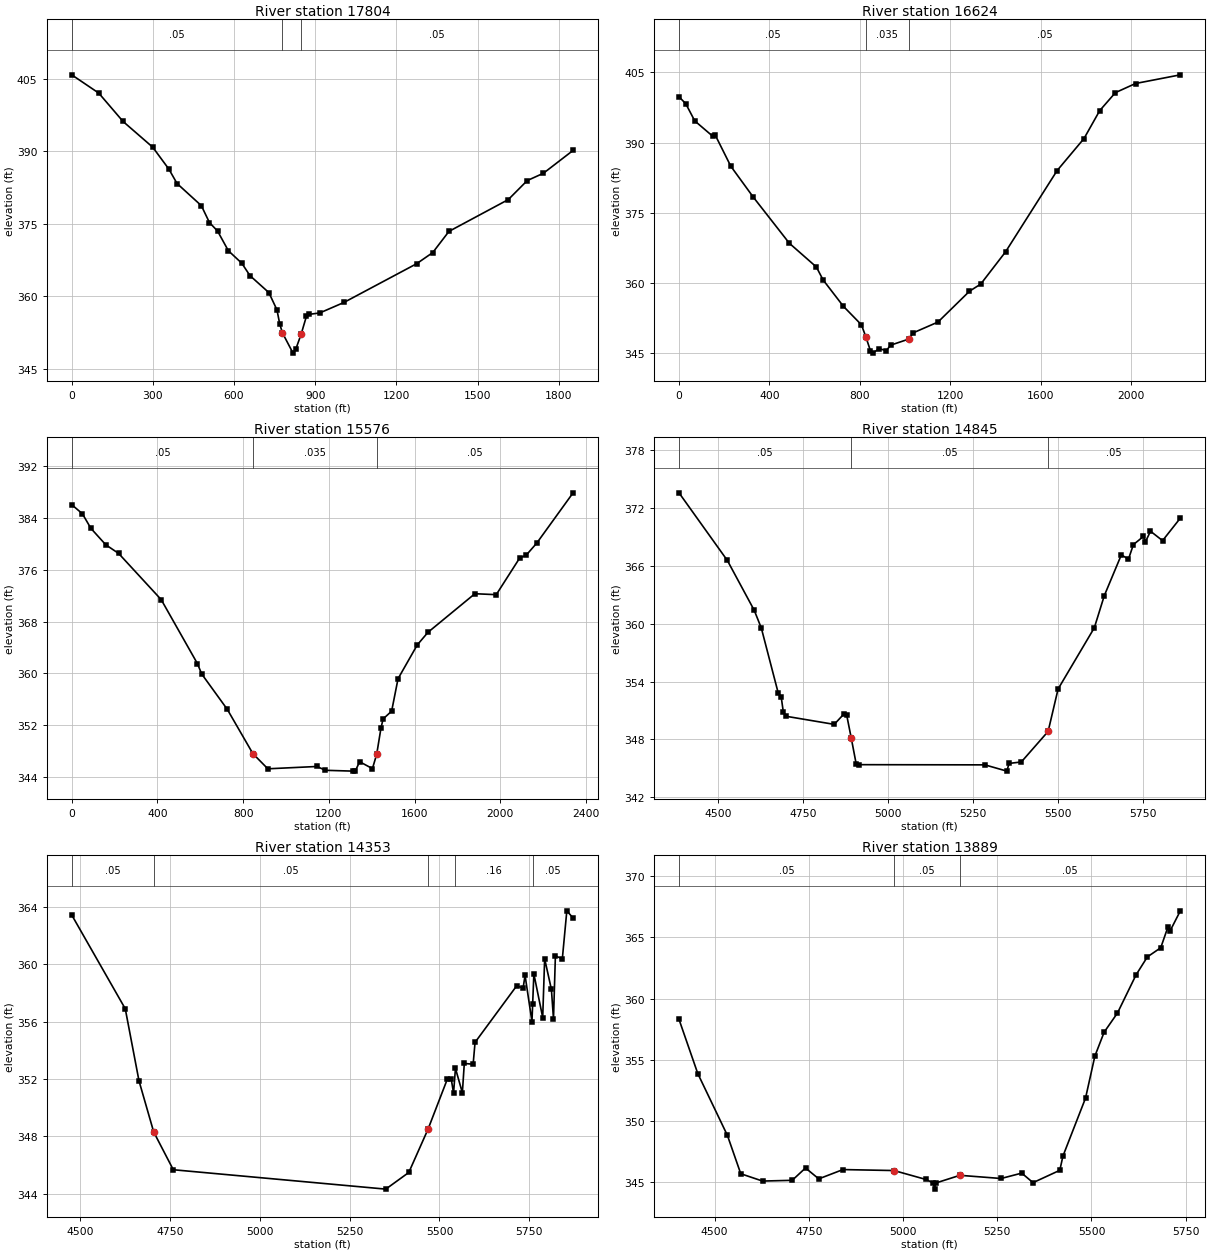
Type RM Length L Ch R = 1 ,17804   ,1180,1180,1180
XS GIS Cut Line= 5
     3670073.134    10177640.595     3669304.904    10177618.893
     3669005.425      10177727.4     3668241.536    10177783.824
3668241.53551305 10177783.824036
#Sta/Elev= 30
       0405.822699.80982402.0424189.6387396.1693299.4295390.8315359.3154 386.277
389.2583383.3153479.0871378.7296509.0301375.2333 538.973373.4765 578.897369.3989
628.8019 366.792658.7448364.2427728.6117360.7291758.5546357.1537768.5356354.3152
 778.426352.4317817.9873348.1904827.8776348.9644847.6583352.0555 867.439355.8061
877.3293356.2174916.8907356.51451005.904358.67791274.566366.69691334.421369.0134
1394.275373.39841613.742 379.9911683.573 383.9191743.427385.43921853.161390.1698
#Mann= 3 , 0 , 0
       0     .05       0 778.426    .035       0847.6583     .05       0
Bank Sta=778.426,847.6583
XS Rating Curve= 0 ,0
Exp/Cntr=0.3,0.1

Type RM Length L Ch R = 1 ,16624   ,1048,1048,1048
XS GIS Cut Line= 3
     3670120.877     10177254.31     3668818.793    10176438.338
      3668137.37    10176412.296
#Sta/Elev= 30
       0399.797429.89854398.323369.76325394.6468149.4927391.3618159.4589 391.708
229.2221384.9684328.8839 378.354488.3427368.5094607.9369363.4393637.8354360.6655
727.5311355.0404807.2605351.0953827.1928348.4852847.1252 345.551857.0914345.0329
886.9899346.0026916.8884345.5364936.8208346.7366 1016.55348.02731036.483349.3671
1146.111351.67081285.637 358.2591335.468359.78921445.096366.65931673.592384.0445
1792.564390.88641861.965396.84241931.365400.68352020.594402.63792218.881404.4913
#Mann= 3 , 0 , 0
       0     .05       0827.1928    .035       0 1016.55     .05       0
Bank Sta=827.1928,1016.55
XS Rating Curve= 0 ,0
Exp/Cntr=0.3,0.1

Type RM Length L Ch R = 1 ,15576   ,731,731,731
XS GIS Cut Line= 4
     3670190.321    10176742.157     3669999.349     10176156.22
     3668671.224    10175058.1293668671.2236236910175058.1286889
#Sta/Elev= 30
       0 386.07249.69948384.672889.45907382.4099159.0383379.8633218.6777378.5367
417.4756371.3831586.4539 361.491606.3337359.8889725.8467354.4107845.3811347.5573
915.1095345.21111144.217345.56991184.062344.97791313.557344.85131323.519344.8854
1343.441346.30751403.208345.2397 1423.13347.46041443.053351.50911453.014352.9277
1492.859354.12921522.743359.15051612.393364.37411662.199366.32151881.346372.2993
1980.958372.15032090.531377.83012120.414378.2453 2170.22380.13652339.561387.9073
#Mann= 3 , 0 , 0
       0     .05       0845.3811    .035       0 1423.13     .05       0
Bank Sta=845.3811,1423.13
XS Rating Curve= 0 ,0
Exp/Cntr=0.3,0.1

Type RM Length L Ch R = 1 ,14845   ,492,492,492
BEGIN DESCRIPTION:
NEBLETTS CREEK 28.0
END DESCRIPTION:
XS GIS Cut Line= 3
      3670604.58     10175679.46      3669884.11      10175132.6
      3669425.58     10174795.19
#Sta/Elev= 30
    4386  373.58  4528.2  366.56  4607.2  361.39  4628.1  359.54    4678  352.77
  4686.3  352.43  4692.5  350.89  4700.8   350.4  4842.3  349.56  4871.4  350.66
  4878.7  350.57  4892.2  348.17  4906.8  345.47    4915  345.38  5285.3  345.36
  5349.8  344.71  5356.2  345.51  5392.3  345.66  5471.1  348.83  5500.4  353.23
  5606.9  359.58  5636.2  362.91  5686.4  367.15  5707.2  366.69  5721.8  368.21
  5751.1  369.05  5757.3   368.5    5772   369.6  5807.5  368.62  5859.8  370.96
#Mann= 3 , 0 , 0
    4386     .05       0  4892.2     .05       0  5471.1     .05       0
Bank Sta=4892.2,5471.1
XS Rating Curve= 0 ,0
Exp/Cntr=0.3,0.1

Type RM Length L Ch R = 1 ,14353   ,464,464,464
BEGIN DESCRIPTION:
Mapping XS f57546df
END DESCRIPTION:
XS GIS Cut Line= 2
      3670776.62     10175040.08      3669475.87     10174537.12
#Sta/Elev= 30
  4477.1  363.42    4626  356.89  4664.2  351.87  4705.1  348.31  4759.6  345.68
  5350.7  344.33  5414.7  345.49  5468.3  348.51  5521.9  351.99  5532.7     352
  5539.2  351.02  5544.5  352.74  5563.7  351.04  5569.1  353.08  5593.7  353.03
    5599  354.55  5714.9  358.49  5732.7  358.33  5738.1  359.22  5757.3     356
  5759.2  357.19  5762.6  359.32  5787.2  356.28  5792.6  360.37  5811.4  358.24
  5817.2  356.18  5822.5  360.57  5841.8  360.37  5854.3  363.71  5871.7  363.21
#Mann= 5 ,-1 , 0
  4477.1     .05       0  4705.1     .05       0  5468.3     .05       0
  5544.5     .16       0  5759.2     .05       0
Bank Sta=4705.1,5468.3
XS Rating Curve= 0 ,0
Exp/Cntr=0.3,0.1

Type RM Length L Ch R = 1 ,13889   ,132,132,132
BEGIN DESCRIPTION:
Mapping XS 2a9e72db
END DESCRIPTION:
XS GIS Cut Line= 3
      3670824.33     10174840.39      3670511.84     10174441.11
      3669743.61     10174145.97
#Sta/Elev= 30
  4405.8   358.3  4455.7  353.86  4534.3   348.8  4569.6  345.67  4627.4  345.07
  4706.1  345.13  4741.4  346.14  4776.6  345.25  4840.8  346.01  4976.3  345.93
  5060.9   345.2  5080.9  344.91  5083.7  344.41  5086.9  344.91    5151  345.54
  5260.3  345.28    5315  345.72    5345  344.94    5416  345.95  5424.3  347.11
  5484.3  351.86    5509  355.29  5533.6  357.25    5569  358.82  5618.3  361.94
  5648.3  363.41  5683.8  364.16    5703  365.87  5708.3  365.52  5735.8  367.18
#Mann= 3 , 0 , 0
  4405.8     .05       0  4976.3     .05       0    5151     .05       0
Bank Sta=4976.3,5151
XS Rating Curve= 0 ,0
Exp/Cntr=0.3,0.1

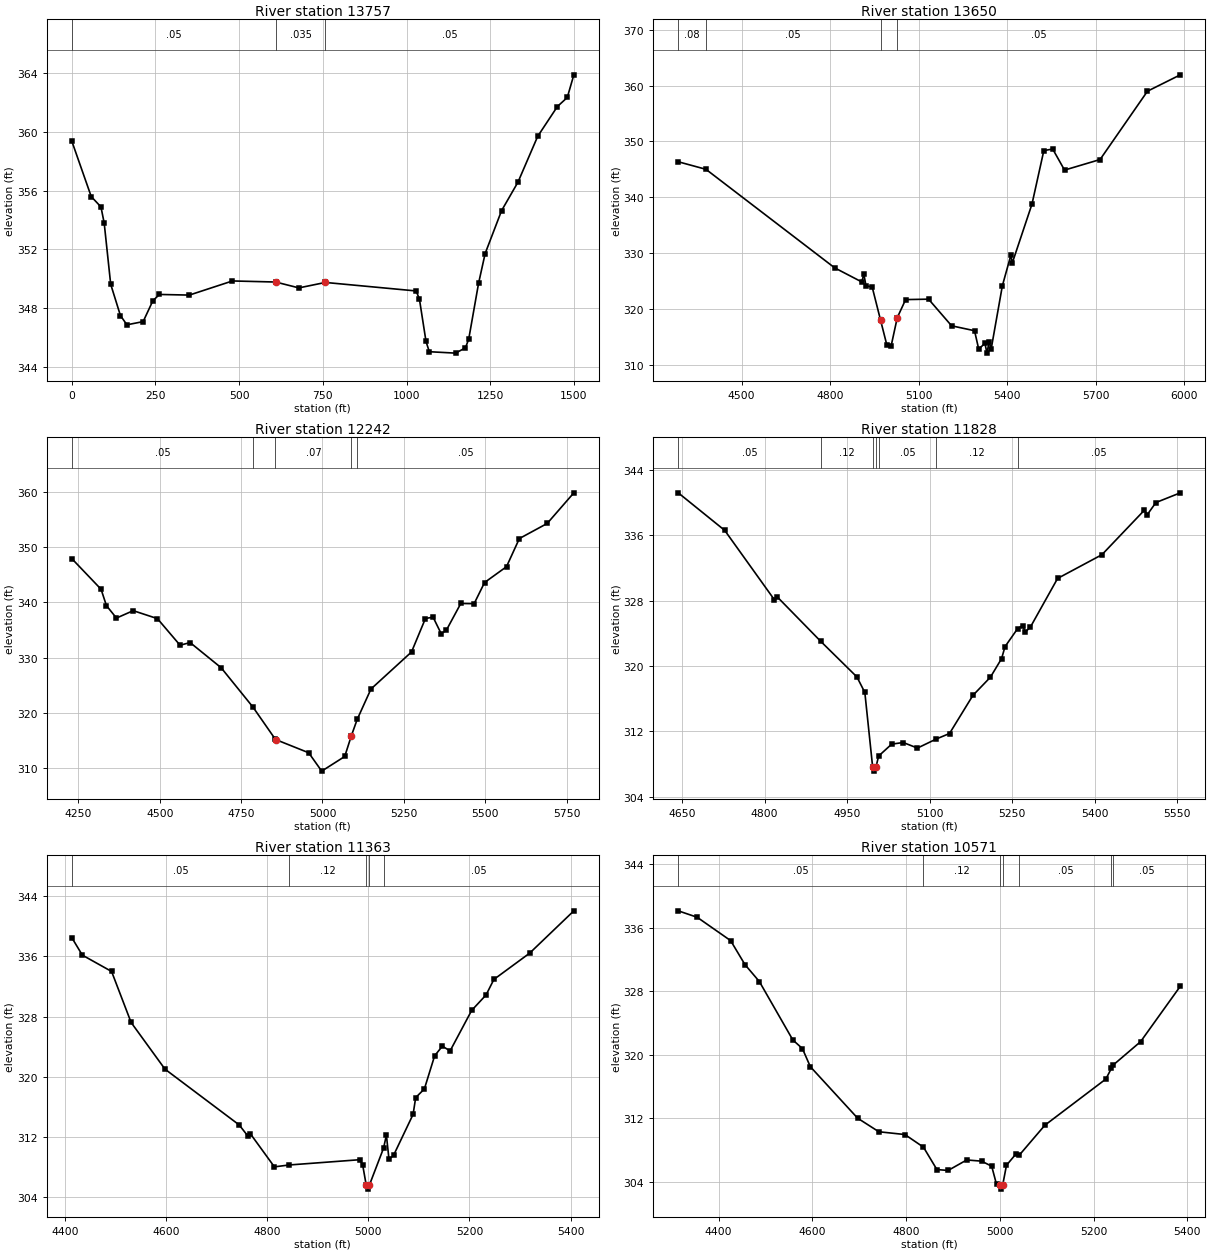
Type RM Length L Ch R = 1 ,13757   ,157,157,157
#Sta/Elev= 30
       0359.373458.13179355.593887.19769354.889196.88632353.7833116.2636349.6279
145.3295347.4986164.7067 346.869213.1499347.0854242.2158348.5027261.8213348.9341
351.0729348.8903479.9919349.8524608.9109349.7794678.3288  349.38757.4337349.7504
1028.669349.17151038.481348.60731058.106 345.7361067.919345.03771146.419344.9415
1175.856345.30261185.669345.89421215.106349.69671234.731 351.7181283.794354.6357
1332.856356.57961391.731359.69391450.606361.72171480.044362.33541499.669363.8771
#Mann= 3 , 0 , 0
       0     .05       0608.9109    .035       0757.4337     .05       0
Bank Sta=608.9109,757.4337
XS Rating Curve= 0 ,0
Exp/Cntr=0.3,0.1

Type RM Length L Ch R = 1 ,13650   ,1408,1408,1408
BEGIN DESCRIPTION:
Mapping XS 60d155f7
END DESCRIPTION:
XS GIS Cut Line= 3
      3671023.99     10174718.88      3670294.83     10173941.98
      3669661.15      10173889.9
#Sta/Elev= 30
  4285.4  346.36  4379.3  345.01  4815.6  327.37  4907.4  324.85  4914.3  326.26
  4921.6  324.16  4942.6  323.94  4970.9  318.02  4992.4  313.54  5006.5  313.32
  5027.6  318.46  5055.9  321.69  5133.6  321.77  5211.7     317  5289.4  316.12
  5303.5  312.84  5324.6  313.85  5331.6  312.11  5338.7  314.13    5346  312.91
  5383.7  324.16  5412.4  329.62  5417.4  328.25  5484.1  338.79  5524.2  348.36
  5554.3  348.64  5594.4  344.87  5714.8  346.76  5875.4  358.99  5986.7  361.92
#Mann= 4 ,-1 , 0
  4285.4     .08       0  4379.3     .05       0  4970.9    .035       0
  5027.6     .05       0
Bank Sta=4970.9,5027.6
XS Rating Curve= 0 ,0
Exp/Cntr=0.3,0.1

Type RM Length L Ch R = 1 ,12242   ,414,414,414
BEGIN DESCRIPTION:
NEBLETTS CREEK 26.0
END DESCRIPTION:
XS GIS Cut Line= 4
      3671135.65      10173717.4      3670692.09     10173610.97
       3670173.3     10173551.35      3669645.43     10173750.39
#Sta/Elev= 30
  4229.7  347.94  4319.7  342.39  4336.2  339.43    4367  337.18  4418.5  338.52
  4492.8  337.08  4562.4  332.27  4593.3  332.75  4688.4  328.21  4786.5  321.07
  4855.5  315.23    4857  315.19  4957.6  312.82  4997.6   309.5  5068.3  312.15
  5088.5  315.87  5106.5  318.84  5148.9  324.35  5273.5  331.05  5316.2   337.1
  5339.7  337.35  5364.5  334.37  5380.3  334.96  5424.9  339.82  5465.8  339.78
  5497.9  343.61  5565.3  346.47  5604.8  351.56  5690.3  354.29  5772.2  359.83
#Mann= 5 ,-1 , 0
  4229.7     .05       0  4786.5     .12       0  4855.5     .07       0
  5088.5     .12       0  5106.5     .05       0
Bank Sta=4857,5088.5
XS Rating Curve= 0 ,0
Exp/Cntr=0.3,0.1

Type RM Length L Ch R = 1 ,11828   ,465,465,465
BEGIN DESCRIPTION:
NEBLETTS CREEK 24.0
END DESCRIPTION:
XS GIS Cut Line= 3
      3670771.05     10173071.58      3670099.05      10173291.3
      3669899.02      10173341.3
#Sta/Elev= 30
  4642.8  341.18  4727.3  336.59  4817.6  328.11  4822.9  328.45  4902.2     323
  4967.8  318.66  4982.2  316.76  4996.4  307.64  4999.2  307.14  5002.4  307.64
  5007.3  308.99    5031  310.44    5052  310.64  5077.9  309.96  5112.5  311.08
  5136.2  311.74  5178.7   316.4  5210.6  318.63  5230.9   320.9  5237.2  322.37
  5260.1  324.57  5269.1  324.94  5274.3  324.16  5283.5  324.78  5332.8  330.71
  5413.4  333.61  5490.7  339.06  5495.8   338.5  5511.6  339.99    5556  341.18
#Mann= 7 ,-1 , 0
  4642.8     .05       0  4902.2     .12       0  4996.4     .07       0
  5002.4     .12       0  5007.3     .05       0  5112.5     .12       0
  5260.1     .05       0
Bank Sta=4996.4,5002.4
XS Rating Curve= 0 ,0
Exp/Cntr=0.3,0.1

Type RM Length L Ch R = 1 ,11363   ,792,792,792
BEGIN DESCRIPTION:
NEBLETTS CREEK 23.0
END DESCRIPTION:
XS GIS Cut Line= 3
      3670717.46      10172762.8      3669896.97     10172915.25
      3669747.01     10172965.24
#Sta/Elev= 30
  4413.7  338.49  4434.6  336.16  4492.4  333.99    4531  327.21    4598     321
  4744.6  313.59  4761.5  312.14  4766.6  312.43  4814.3  308.01  4843.3  308.26
  4982.9  308.96  4988.7  308.31  4995.9  305.55  4998.7  305.05  5001.9  305.55
  5030.1   310.5  5035.7  312.23  5040.8  309.04  5049.8  309.53  5088.5  314.99
  5093.6  317.22  5110.8  318.37  5131.1  322.78  5146.4  324.06  5161.6  323.42
  5204.3  328.81  5232.8  330.87  5248.2  332.93  5318.9  336.42  5406.3  342.05
#Mann= 5 ,-1 , 0
  4413.7     .05       0  4843.3     .12       0  4995.9     .07       0
  5001.9     .12       0  5030.1     .05       0
Bank Sta=4995.9,5001.9
XS Rating Curve= 0 ,0
Exp/Cntr=0.3,0.1

Type RM Length L Ch R = 1 ,10571   ,704,704,704
BEGIN DESCRIPTION:
NEBLETTS CREEK 21.0
END DESCRIPTION:
XS GIS Cut Line= 3
      3670821.65     10172363.51       3670311.9      10172259.1
      3669792.15     10172441.63
#Sta/Elev= 30
    4314  338.11  4354.4   337.3  4425.8  334.36  4456.4  331.34  4487.1  329.21
  4558.5  321.86  4578.9  320.78  4595.8   318.5  4696.7  312.02    4742  310.31
  4797.6  309.96  4837.2  308.37  4865.9  305.55  4889.8  305.44  4929.5  306.76
  4961.3  306.61  4982.8  305.97  4993.1  303.68  5000.2  303.59  5002.9  303.09
  5006.2  303.59  5014.3  306.09  5034.2  307.49    5042  307.39  5096.2  311.13
  5226.3  316.94  5238.3   318.3  5242.1  318.71  5300.5  321.65  5385.2  328.62
#Mann= 7 ,-1 , 0
    4314     .05       0  4837.2     .12       0  5000.2     .07       0
  5006.2     .12       0    5042     .05       0  5238.3     .12       0
  5242.1     .05       0
Bank Sta=5000.2,5006.2
XS Rating Curve= 0 ,0
Exp/Cntr=0.3,0.1

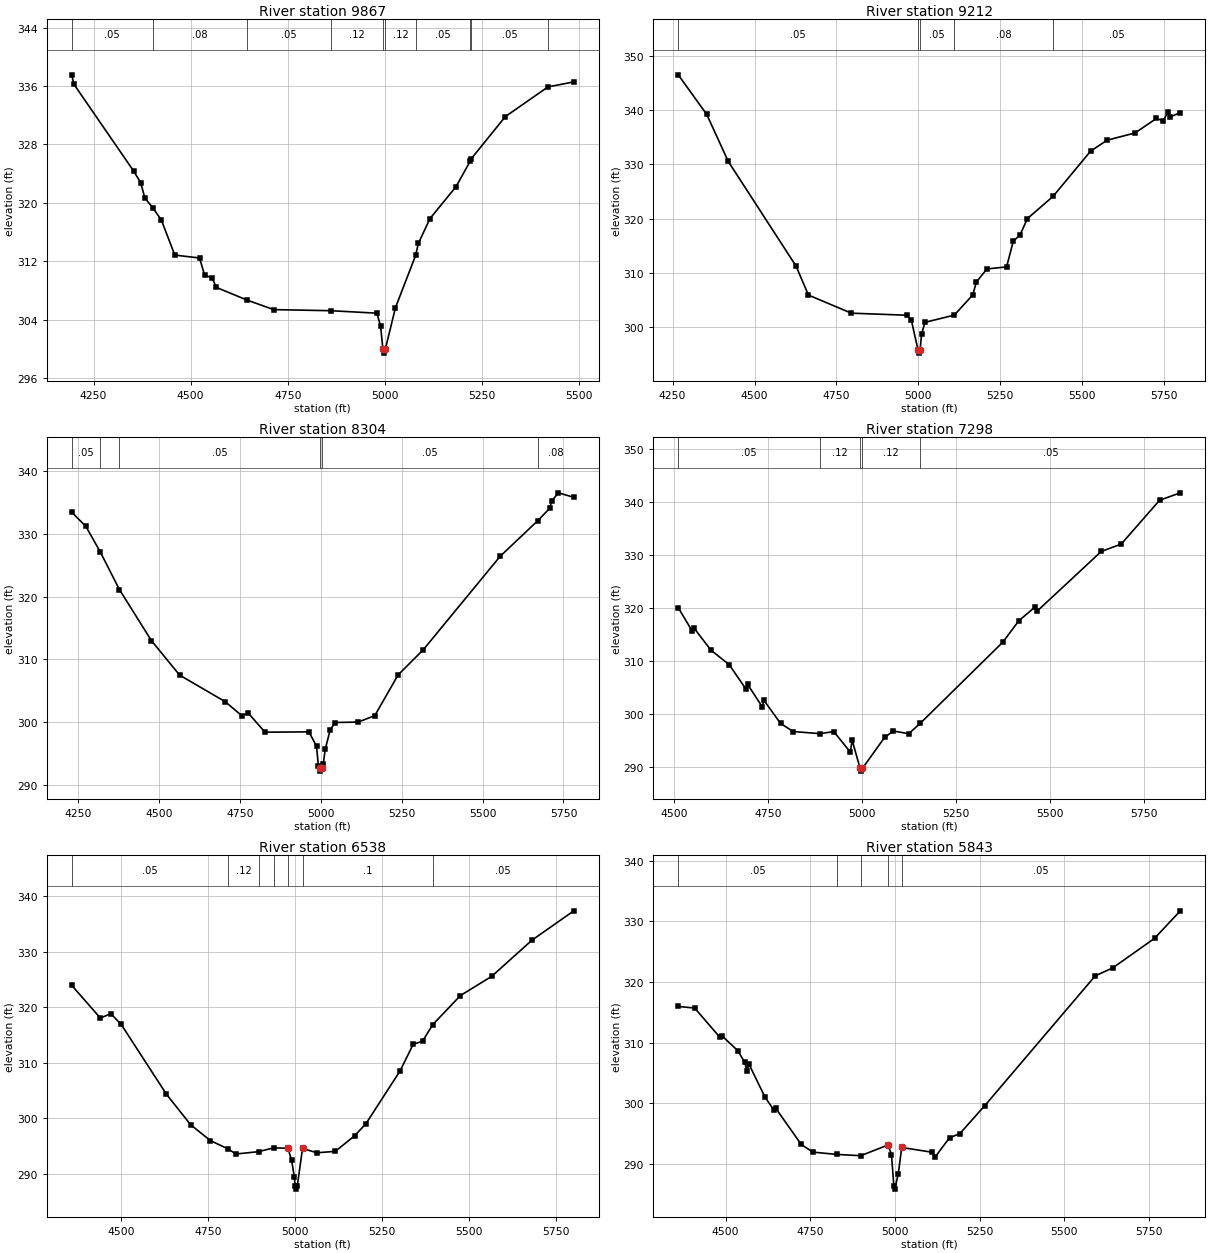
Type RM Length L Ch R = 1 ,9867    ,655,655,655
BEGIN DESCRIPTION:
NEBLETTS CREEK 20.0
END DESCRIPTION:
XS GIS Cut Line= 3
      3670595.89     10171686.43      3669742.11     10172041.64
      3669502.17      10172320.1
#Sta/Elev= 30
    4194  337.54    4199  336.29    4353  324.38  4371.4  322.76  4382.2  320.66
  4402.4  319.34  4424.5  317.66  4459.2  312.85    4523  312.45  4536.1  310.06
  4554.6  309.77  4566.4  308.42  4644.4   306.7  4713.9  305.38  4861.7  305.23
  4979.4  304.89  4988.8  303.14  4994.9  299.92  4997.6  299.42  5000.9  299.92
  5027.1  305.64    5079   312.8  5086.2  314.46    5116  317.85  5182.9  322.21
  5219.2  325.68  5222.3  326.05  5310.2  331.83  5419.9  335.89  5486.3  336.57
#Mann= 10 ,-1 , 0
    4194     .05       0  4402.4     .08       0  4644.4     .05       0
  4861.7     .12       0  4994.9     .07       0  5000.9     .12       0
    5079     .05       0  5219.2     .08       0  5222.3     .05       0
  5419.9     .08       0
Bank Sta=4994.9,5000.9
XS Rating Curve= 0 ,0
Exp/Cntr=0.3,0.1

Type RM Length L Ch R = 1 ,9212    ,908,908,908
BEGIN DESCRIPTION:
NEBLETTS CREEK 18.0
END DESCRIPTION:
XS GIS Cut Line= 3
      3670542.11     10171191.64      3669580.29     10171486.77
      3669156.06     10171798.45
#Sta/Elev= 30
  4267.2  346.49  4354.3  339.19  4419.7  330.56  4626.6  311.29  4664.7  305.93
  4795.5   302.6  4964.4  302.22  4978.5  301.37  4999.4  295.74  5002.1  295.24
  5005.4  295.74  5009.9  298.74  5020.3  300.91  5109.9  302.24  5166.1  305.96
  5177.2  308.33  5209.3  310.74  5269.5  311.12  5289.8  315.84  5310.7  317.03
  5333.1  320.02  5411.2   324.1  5525.9  332.44  5576.1  334.45  5661.7  335.79
  5726.5  338.45  5747.4  338.04    5762  339.64  5768.2  338.71  5799.7  339.55
#Mann= 5 ,-1 , 0
  4267.2     .05       0  4999.4     .03       0  5005.4     .05       0
  5109.9     .08       0  5411.2     .05       0
Bank Sta=4999.4,5005.4
XS Rating Curve= 0 ,0
Exp/Cntr=0.3,0.1

Type RM Length L Ch R = 1 ,8304    ,1006,1006,1006
BEGIN DESCRIPTION:
NEBLETTS CREEK 16.0
END DESCRIPTION:
XS GIS Cut Line= 3
      3670404.89     10170514.56      3669956.27     10170631.02
      3669050.74     10171235.05
#Sta/Elev= 30
  4230.1  333.44  4273.7  331.18  4317.7  327.17  4377.4  321.13  4476.5  312.99
  4563.6  307.51  4704.2  303.29  4755.2  301.08  4776.3  301.43  4827.3  298.43
  4963.1  298.48  4986.6  296.22  4992.6  292.97  4996.1  292.73  4998.9  292.23
  5002.1  292.73  5007.6  293.41  5013.6  295.71  5028.6  298.75  5043.7  299.97
  5115.8  300.04  5166.8  301.07  5238.9  307.55    5317  311.57  5554.4  326.43
  5670.1  332.07  5707.6  334.07  5713.6  335.23  5734.6  336.53  5782.1  335.81
#Mann= 6 ,-1 , 0
  4230.1     .05       0  4317.7     .16       0  4377.4     .05       0
  4996.1     .03       0  5002.1     .05       0  5670.1     .08       0
Bank Sta=4996.1,5002.1
XS Rating Curve= 0 ,0
Exp/Cntr=0.3,0.1

Type RM Length L Ch R = 1 ,7298    ,760,760,760
BEGIN DESCRIPTION:
NEBLETTS CREEK 14.0
END DESCRIPTION:
XS GIS Cut Line= 3
       3670170.6     10170097.87      3669693.34     10170202.56
      3668868.45     10170393.02
#Sta/Elev= 30
  4511.4  320.09    4549  315.62  4554.1  316.18  4597.9  312.11  4646.9  309.34
  4690.7  304.81  4695.8  305.63  4734.5  301.42  4739.6  302.58  4783.4  298.26
    4817  296.72  4888.6  296.32  4925.1  296.71  4968.9  292.85    4974  295.07
  4995.1  289.75  4997.8  289.25  5001.1  289.75  5060.2  295.61  5083.4  296.82
  5124.4  296.31  5155.3  298.29  5374.8   313.6  5417.6  317.66  5460.3  320.21
  5465.4  319.41  5636.4   330.7  5689.5  332.09  5791.5  340.36  5846.6  341.76
#Mann= 5 ,-1 , 0
  4511.4     .05       0  4888.6     .12       0  4995.1     .07       0
  5001.1     .12       0  5155.3     .05       0
Bank Sta=4995.1,5001.1
XS Rating Curve= 0 ,0
Exp/Cntr=0.3,0.1

Type RM Length L Ch R = 1 ,6538    ,695,695,695
BEGIN DESCRIPTION:
NEBLETTS CREEK 12.0
END DESCRIPTION:
XS GIS Cut Line= 3
      3670224.41     10169554.84       3669824.4     10169554.84
      3668826.05      10169863.2
#Sta/Elev= 30
  4356.9  323.94  4439.2  318.05  4469.2  318.84  4499.2  316.89  4629.2  304.32
  4699.2  298.79  4755.6  295.96  4807.9   294.4  4829.1  293.52  4894.4  293.95
  4937.5  294.63  4979.1  294.57  4989.6  292.37  4997.5  289.33  4999.7  287.69
  5002.5  287.19  5005.7  287.69    5021  294.52  5062.8  293.75  5115.2     294
  5171.2  296.83  5203.8  299.02  5301.8  308.53  5339.6  313.33  5366.3  313.87
  5395.6  316.85  5475.4  322.11  5565.2  325.56  5681.7  332.12  5801.8  337.39
#Mann= 7 ,-1 , 0
  4356.9     .05       0  4807.9     .12       0  4894.4     .07       0
  4937.5      .1       0  4979.1     .05       0    5021      .1       0
  5395.6     .05       0
Bank Sta=4979.1,5021
XS Rating Curve= 0 ,0
Exp/Cntr=0.3,0.1

Type RM Length L Ch R = 1 ,5843    ,671,671,671
BEGIN DESCRIPTION:
NEBLETTS CREEK 10.0
END DESCRIPTION:
XS GIS Cut Line= 3
      3670196.59     10168960.73      3669298.97     10169074.85
      3668738.25     10169212.47
#Sta/Elev= 30
  4360.3  315.96  4408.7   315.7  4483.6  310.85  4488.7  311.15  4536.2  308.65
  4556.3  306.76  4563.6  305.29  4568.6  306.48  4616.8  300.95  4643.5   298.8
  4648.6  299.12  4723.5  293.17    4758  291.91  4828.5  291.53  4899.1  291.32
  4979.7  293.09  4989.8  291.49  4996.9   286.3  4999.6   285.8    5010  288.37
  5020.1  292.68  5110.8  291.88  5118.3  291.07  5161.2  294.29  5191.4  294.95
  5265.1  299.57  5591.4  321.02  5642.9  322.32  5766.5  327.21  5842.5  331.75
#Mann= 5 ,-1 , 0
  4360.3     .05       0  4828.5     .12       0  4899.1     .05       0
  4979.7    .035       0  5020.1     .05       0
Bank Sta=4979.7,5020.1
XS Rating Curve= 0 ,0
Exp/Cntr=0.3,0.1

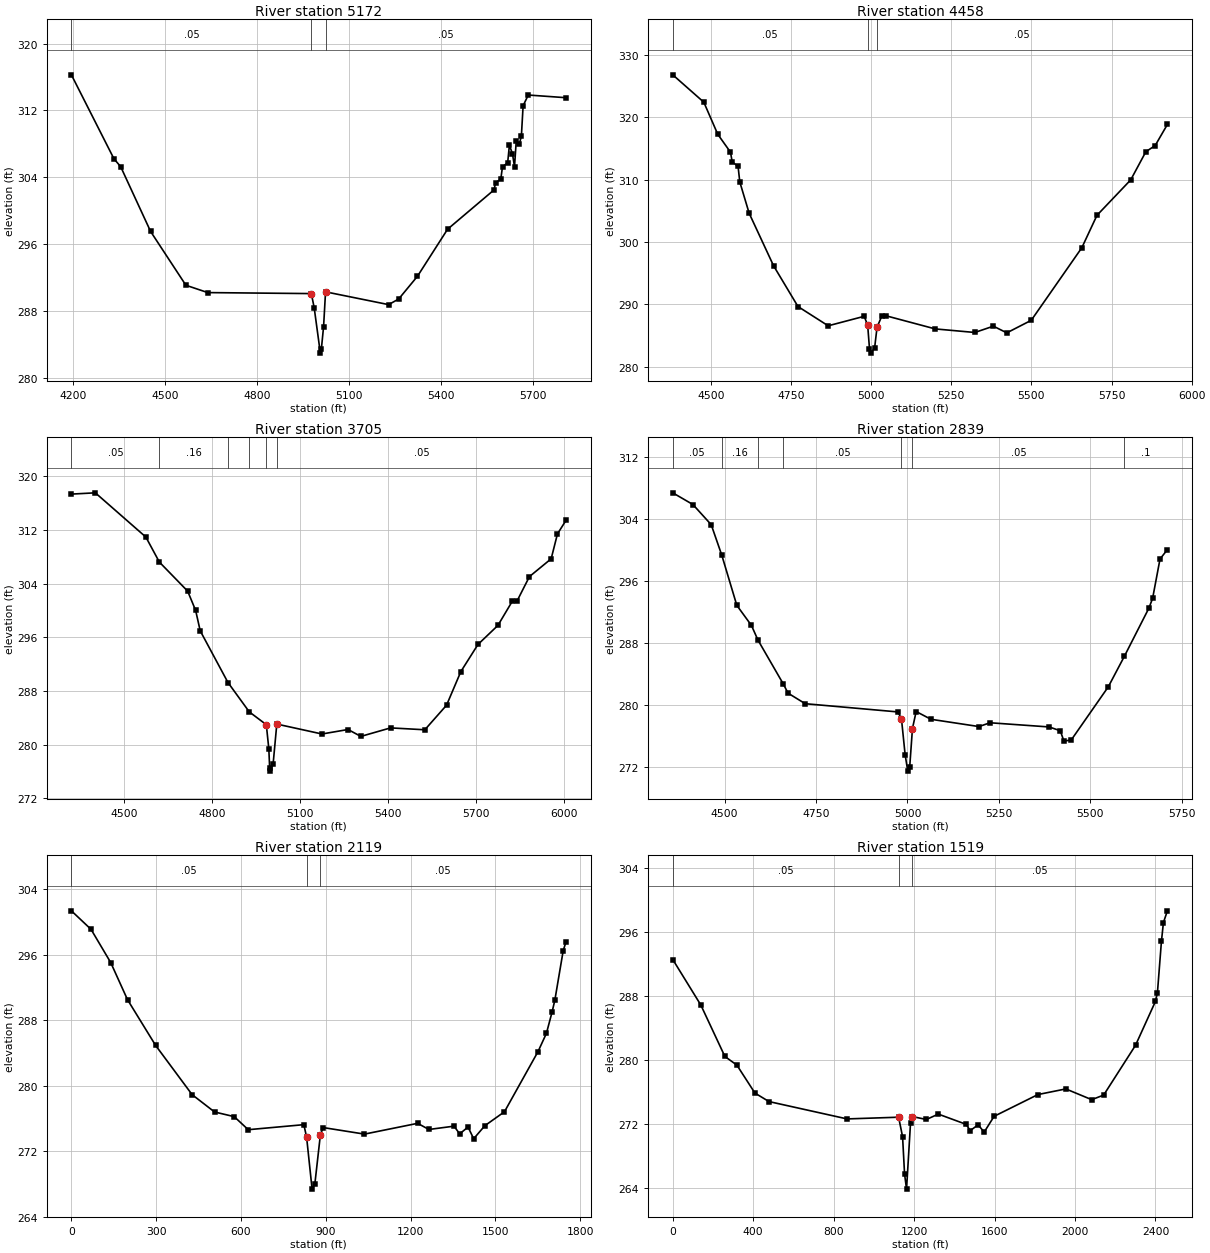
Type RM Length L Ch R = 1 ,5172    ,714,714,714
BEGIN DESCRIPTION:
NEBLETTS CREEK 9.0
END DESCRIPTION:
XS GIS Cut Line= 3
      3670187.96     10168266.27      3669044.88     10168491.64
      3668645.95     10168691.11
#Sta/Elev= 30
  4195.4  316.25  4333.9   306.2  4355.9  305.25  4453.4  297.49  4568.3  291.05
  4639.6  290.17  4976.9  290.05  4986.2  288.36  5006.3  282.92  5009.6  283.42
  5016.8  286.09  5023.2  290.26  5228.5  288.73  5261.4   289.4  5322.5  292.12
  5420.7  297.76  5571.7  302.46  5577.3  303.34    5594  303.76  5599.6  305.25
  5616.4  305.71    5622  307.82  5631.9  306.82  5638.7  305.26  5644.3   308.3
  5654.3  307.93  5661.1  308.94  5666.7  312.55  5683.5  313.83  5806.5  313.51
#Mann= 3 , 0 , 0
  4195.4     .05       0  4976.9    .035       0  5023.2     .05       0
Bank Sta=4976.9,5023.2
XS Rating Curve= 0 ,0
Exp/Cntr=0.3,0.1

Type RM Length L Ch R = 1 ,4458    ,753,753,753
BEGIN DESCRIPTION:
NEBLETTS CREEK 7.0
END DESCRIPTION:
XS GIS Cut Line= 3
      3669911.17     10167485.06       3669561.2     10167635.05
      3668492.08     10168091.65
#Sta/Elev= 30
    4381  326.79  4477.9   322.4  4521.4  317.26  4561.1  314.39  4566.5  312.82
  4584.7  312.14  4590.1  309.63  4619.3  304.61  4695.5  296.19  4771.6  289.66
  4865.9  286.57  4978.2  288.09  4989.1  286.67  4994.8   282.9  4999.9  282.19
  5010.9  283.08  5018.4  286.34  5032.6  288.06  5047.4  288.16  5199.9  286.07
  5323.4   285.5  5381.4  286.51  5423.2  285.44  5499.5  287.45  5657.4  299.09
  5704.6  304.28  5809.9  309.96  5857.1  314.47  5886.1  315.45  5924.3  318.84
#Mann= 3 , 0 , 0
    4381     .05       0  4989.1    .035       0  5018.4     .05       0
Bank Sta=4989.1,5018.4
XS Rating Curve= 0 ,0
Exp/Cntr=0.3,0.1

Type RM Length L Ch R = 1 ,3705    ,866,866,866
BEGIN DESCRIPTION:
NEBLETTS CREEK 5.0
END DESCRIPTION:
XS GIS Cut Line= 3
      3669682.71     10166837.13      3669382.73     10166887.13
      3668192.07     10167591.66
#Sta/Elev= 30
  4320.1  317.37  4401.8  317.56  4574.2  310.96  4620.2  307.23  4716.8  302.89
    4744  300.01  4759.6  296.97  4854.3  289.26    4927  284.88  4985.1  282.97
  4993.7  279.36  4996.5  276.54  4999.2  276.04  5008.4  277.14  5020.9  283.06
    5175  281.58    5264  282.25  5307.6  281.22    5409  282.49    5526  282.21
  5600.1  285.88  5648.8  290.89  5707.3  294.94  5775.3  297.78  5824.3  301.38
    5840  301.37  5882.8  305.06    5957  307.72  5978.4  311.43  6007.7  313.46
#Mann= 6 ,-1 , 0
  4320.1     .05       0  4620.2     .16       0  4854.3     .12       0
    4927     .05       0  4985.1    .035       0  5020.9     .05       0
Bank Sta=4985.1,5020.9
XS Rating Curve= 0 ,0
Exp/Cntr=0.3,0.1

Type RM Length L Ch R = 1 ,2839    ,720,720,720
BEGIN DESCRIPTION:
NEBLETTS CREEK 4.0
END DESCRIPTION:
XS GIS Cut Line= 3
      3669337.21     10166530.17      3668692.11     10166541.64
      3667992.12     10166641.64
#Sta/Elev= 30
  4358.3  307.41  4413.4   305.9  4463.4   303.3  4492.4  299.35  4533.4  292.89
  4573.4   290.3  4591.2  288.41  4660.9  282.71  4673.5  281.56  4720.4   280.2
  4973.5  279.14  4983.5  278.27  4993.5  273.64  5000.8   271.5    5006     272
  5013.6     277  5023.7  279.19  5064.1  278.19  5195.4  277.25  5225.7  277.74
  5387.4   277.2  5417.7  276.71  5427.8  275.36    5448  275.54    5549  282.38
    5593  286.32  5660.1  292.54  5670.2   293.8  5690.4  298.87  5710.6  300.08
#Mann= 7 ,-1 , 0
  4358.3     .05       0  4492.4     .16       0  4591.2     .12       0
  4660.9     .05       0  4983.5    .035       0  5013.6     .05       0
    5593      .1       0
Bank Sta=4983.5,5013.6
XS Rating Curve= 0 ,0
Exp/Cntr=0.3,0.1

Type RM Length L Ch R = 1 ,2119    ,600,600,600
XS GIS Cut Line= 5
     3669374.858    10166389.202      3668815.83    10165927.397
     3668524.164    10165944.758     3668038.053    10166493.369
3668038.0529190410166493.3690914
#Sta/Elev= 30
       0301.381169.53056299.1163139.0611 295.064198.6588290.5178297.9881284.9384
427.1163278.9238506.5798276.8041576.1104276.2354 625.775274.6403822.4987275.2548
832.2382273.7416 851.717267.3786861.4564268.0096880.9353273.9789890.6747274.9019
1037.098274.10061225.299275.4177 1264.92274.66671354.068275.07191373.878  274.13
1403.594274.96661423.405273.53251463.026275.12761532.363276.82871651.227284.1879
1680.943286.41881700.753289.00041710.659290.45731740.375296.5333 1750.28 297.591
#Mann= 3 , 0 , 0
       0     .05       0832.2382    .035       0880.9353     .05       0
Bank Sta=832.2382,880.9353
XS Rating Curve= 0 ,0
Exp/Cntr=0.3,0.1

Type RM Length L Ch R = 1 ,1519    ,548,548,548
XS GIS Cut Line= 5
     3669375.929    10166172.036       3668857.7    10165484.536
     3668466.691    10165395.052      3668193.48    10165591.522
     3668032.179    10166437.661
#Sta/Elev= 30
       0292.5628139.4752286.8722259.0254280.4392318.8004279.3524408.4631275.8596
478.2007274.7959866.6318272.62441122.876272.83821142.587270.39221152.442265.7269
1162.298263.84241182.009272.08941191.865272.91491260.853272.55381320.286273.2268
1458.963271.94271478.774271.15541518.396271.89331548.113 270.966 1597.64272.9501
 1815.52275.67181954.171276.37622082.919275.03292142.341275.60572300.799281.8355
2399.835287.32482409.739288.43352429.546294.8266 2439.45297.18812459.257 298.653
#Mann= 3 , 0 , 0
       0     .05       01122.876    .035       01191.865     .05       0
Bank Sta=1122.876,1191.865
XS Rating Curve= 0 ,0
Exp/Cntr=0.3,0.1

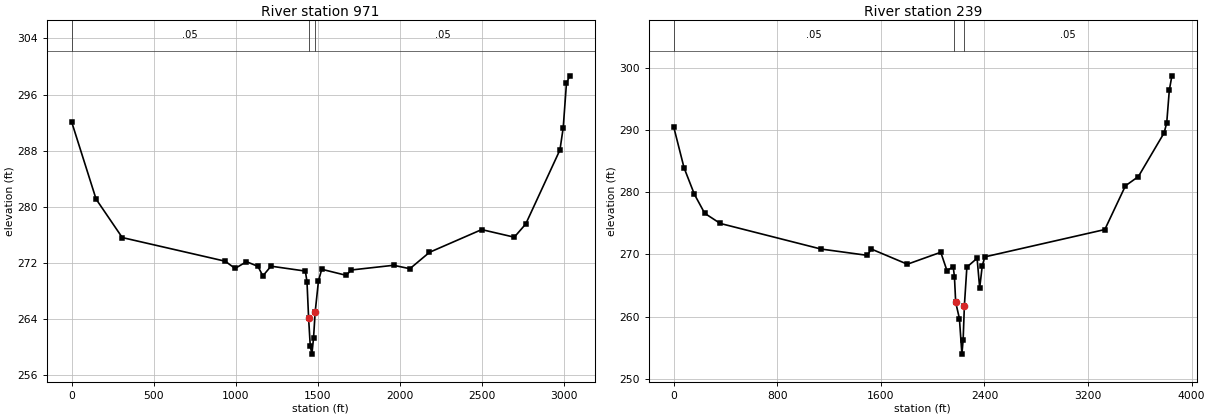
Type RM Length L Ch R = 1 ,971     ,732,732,732
XS GIS Cut Line= 5
     3669383.741    10166049.641      3668513.95    10164948.078
      3668263.95    10165145.995     3668016.554    10166432.453
3668016.5539538910166432.4532397
#Sta/Elev= 30
       0 292.127149.3148281.0733308.5839275.5911935.7059272.2151995.4318271.1868
1065.112272.14741134.792 271.4831164.655270.11811214.427271.50781423.488270.8089
1433.452269.26941443.416264.04951453.381260.11171463.345258.96051473.309261.2594
1483.274264.95611503.202269.39311523.131271.06581672.596270.20091702.489270.9626
 1960.76271.63592060.069271.1468 2179.24273.4852 2497.03276.72762695.649275.6453
2765.166277.51832973.715288.09832993.577291.26323013.439297.62723033.301298.6652
#Mann= 3 , 0 , 0
       0     .05       01443.416    .035       01483.274     .05       0
Bank Sta=1443.416,1483.274
XS Rating Curve= 0 ,0
Exp/Cntr=0.3,0.1

Type RM Length L Ch R = 1 ,239     ,0,0,0
XS GIS Cut Line= 5
     3669399.366    10166020.995     3668253.533     10164599.12
     3668032.179    10164687.661     3667896.762    10164862.141
3668000.9289837310166422.0357564
#Sta/Elev= 30
       0290.474379.74973283.9146159.4995279.6548239.2492276.5992358.8738274.9706
1136.434270.85571495.307269.83471525.214270.85691804.338268.41112062.278270.3342
2110.292267.37472158.305 268.0122167.908266.42062177.511262.27792206.319 259.677
2225.525253.95092235.127256.2521 2244.73261.75792263.936267.93912342.921269.3741
2362.847264.58522382.774268.15952402.701269.59263329.286 273.9863488.699281.0255
3588.332282.50493787.598289.54623807.524291.17033827.451296.40743847.377298.7095
#Mann= 3 ,-1 , 0
       0     .05       02167.908    .035       0 2244.73     .05       0
Bank Sta=2177.511,2244.73
XS Rating Curve= 0 ,0
Exp/Cntr=0.3,0.1

Chan Stop Cuts=-1
Use User Specified Reach Order=0
Composite Channel Slope=5