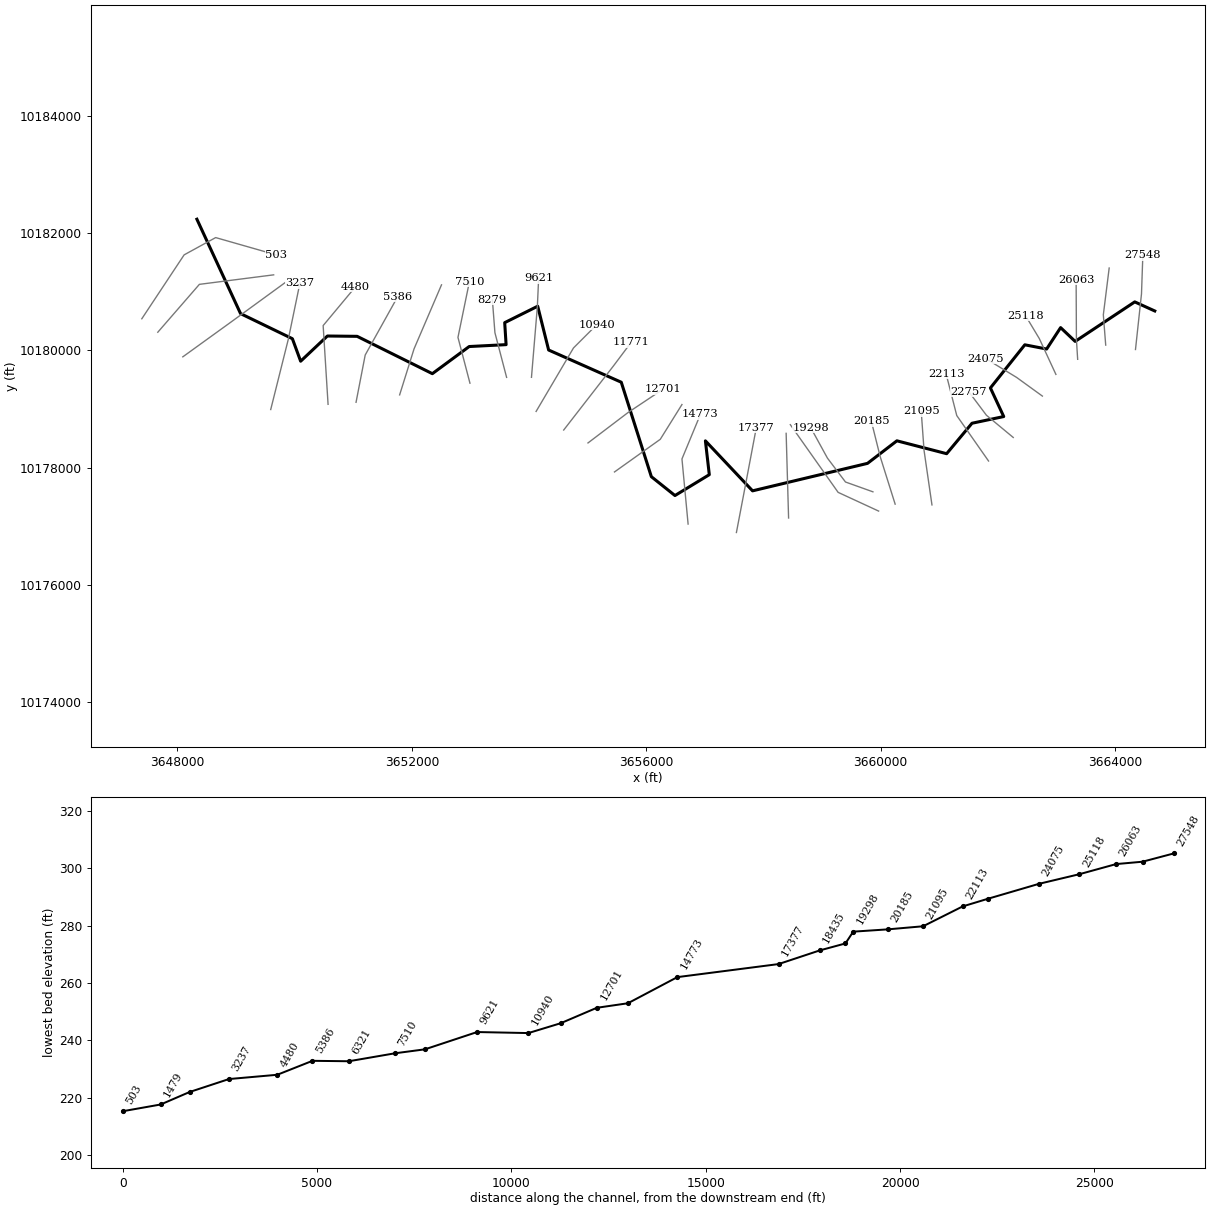
--- PINE CREEK.prj (project) ---

Proj Title=PINE CREEK Base Level Engineering
Current Plan=p01
Default Exp/Contr=0.3,0.1
English Units
Geom File=g01
Flow File=f01
Plan File=p01
Y Axis Title=Elevation
X Axis Title(PF)=Main Channel Distance
X Axis Title(XS)=Station
BEGIN DESCRIPTION:
PINE CREEK
END DESCRIPTION:
DSS Export Rating Curves= 0
DSS Export Rating Curve Sorted= 0
DSS Export Volume Flow Curves= 0
DXF OffsetX= 0
DXF OffsetY= 0
DXF ScaleX= 1
DXF ScaleY= 10

--- PINE CREEK.p01 (plan) ---

Plan Title=Multiple Run
Short Identifier=Multiple
Geom File=g01
Flow File=f01
Subcritical Flow
K Sum by GR= 0
Std Step Tol= 0.01
Critical Tol= 0.01
Num of Std Step Trials= 20
Max Error Tol= 0.3
Flow Tol Ratio= 0.001
Split Flow NTrial= 30
Split Flow Tol= 0.02
Split Flow Ratio= 0.02
Log Output Level= 0
Friction Slope Method= 1
Unsteady Friction Slope Method= 2
Unsteady Bridges Friction Slope Method= 1
Parabolic Critical Depth
Global Vel Dist=  1 , 1 , 1
Global Log Level= 0
CheckData=True
Encroach Param= -1, 0, 0, 0
BEGIN DESCRIPTION:
Multiple Run
END DESCRIPTION:

--- PINE CREEK.f01 (steady flow) ---

Flow Title=Multiple
Program Version=4.10
Number of Profiles= 7
Profile Names=10-year,25-year,50-year,1pct_min,100-year,1pct_plu,500-year
River Rch & RM=PINE CREEK,Reach-1         ,27548
    1114    1551    1920    1740    2353    3182    3534
River Rch & RM=PINE CREEK,Reach-1         ,21095
    1779    2536    3189    2930    3962    5358    6122
River Rch & RM=PINE CREEK,Reach-1         ,17377
    2113    3023    3809    3505    4740    6410    7349
River Rch & RM=PINE CREEK,Reach-1         ,6321
    2485    3572    4516    4166    5634    7619    8785
Boundary for River Rch & Prof#=PINE CREEK,Reach-1         , 1
Up Type= 0
Dn Type= 3
Dn Slope=0.003
Boundary for River Rch & Prof#=PINE CREEK,Reach-1         , 2
Up Type= 0
Dn Type= 3
Dn Slope=0.003
Boundary for River Rch & Prof#=PINE CREEK,Reach-1         , 3
Up Type= 0
Dn Type= 3
Dn Slope=0.003
Boundary for River Rch & Prof#=PINE CREEK,Reach-1         , 4
Up Type= 0
Dn Type= 3
Dn Slope=0.003
Boundary for River Rch & Prof#=PINE CREEK,Reach-1         , 5
Up Type= 0
Dn Type= 3
Dn Slope=0.003
Boundary for River Rch & Prof#=PINE CREEK,Reach-1         , 6
Up Type= 0
Dn Type= 3
Dn Slope=0.003
Boundary for River Rch & Prof#=PINE CREEK,Reach-1         , 7
Up Type= 0
Dn Type= 3
Dn Slope=0.003
DSS Import GetInterval= 0
DSS Import GetPeak= 0
DSS Import FillOption= 0

--- PINE CREEK.g01 (geometry) ---

Geom Title=Existing Conditions
Program Version=4.10

River Reach=PINE CREEK      ,Reach-1
Reach XY= 30
      3664679.38     10180674.72      3664337.99      10180829.8
      3663320.73       10180155.      3663072.57     10180390.48
       3662833.9     10180024.63      3662461.74     10180096.93
      3661874.44     10179360.32      3662101.73     10178871.57
      3661560.26     10178757.48      3661127.42     10178237.37
      3660278.51      10178457.3      3659777.06     10178072.36
      3657815.17     10177602.96      3657010.51     10178456.68
      3657076.95     10177879.11      3656491.06      10177522.8
      3656088.03     10177844.72      3655574.44     10179457.93
      3654334.97     10180007.92      3654148.29     10180755.74
      3653585.26     10180475.26      3653608.99     10180099.59
        3652979.     10180067.31      3652350.69     10179603.97
      3651066.84     10180241.52      3650559.33     10180247.06
      3650102.85     10179816.47      3649961.76     10180201.03
      3649077.47     10180629.32      3648332.11     10182241.64

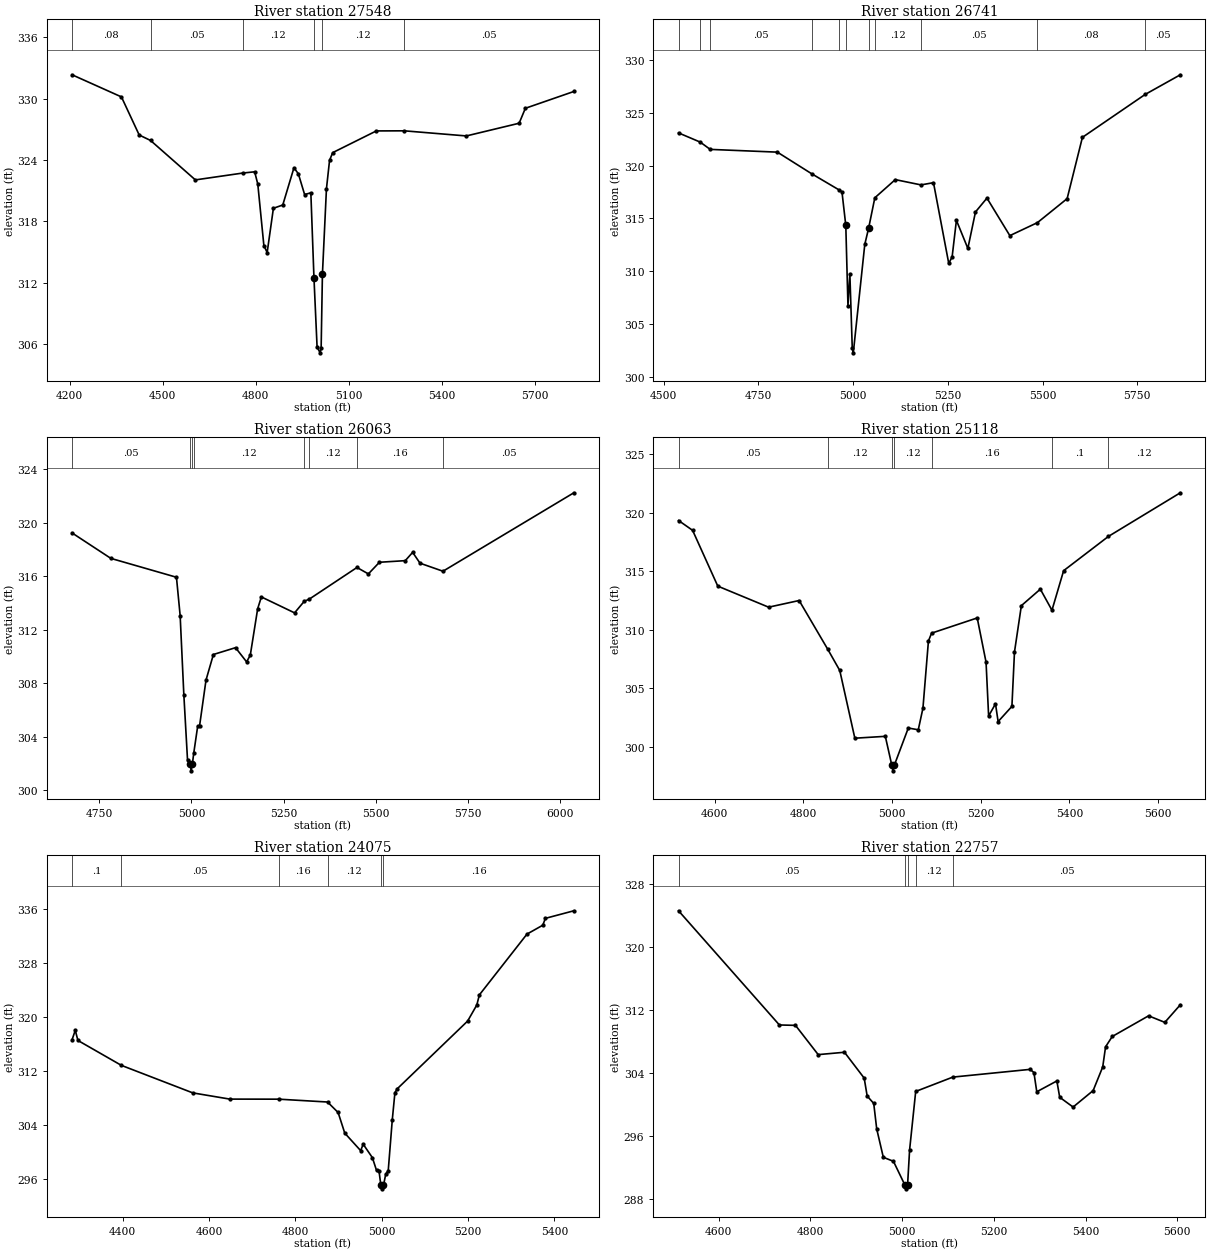
Type RM Length L Ch R = 1 ,27548   ,807,807,807
BEGIN DESCRIPTION:
PINE CREEK 55.0
END DESCRIPTION:
XS GIS Cut Line= 3
      3664350.24     10180016.51       3664452.7     10180965.19
      3664475.89     10181627.89
#Sta/Elev= 30
    4208  332.32  4367.1  330.16  4424.4  326.44  4460.9  325.91  4605.4  322.06
  4758.6  322.73  4796.5  322.85  4806.6  321.65  4826.2  315.65  4836.8  314.97
  4856.9  319.29  4887.1  319.61  4923.1  323.24  4937.3  322.66  4957.5  320.63
  4977.6   320.8  4987.6  312.52  4997.7  305.74  5007.5  305.18  5010.8  305.68
  5014.9  312.85  5027.9   321.2  5037.9  323.97    5048  324.72  5188.7  326.84
  5278.7  326.85  5478.8  326.35  5648.9  327.59    5669  329.05  5825.3  330.69
#Mann= 6 ,-1 , 0
    4208     .08       0  4460.9     .05       0  4758.6     .12       0
  4987.6     .07       0  5014.9     .12       0  5278.7     .05       0
Bank Sta=4987.6,5014.9
XS Rating Curve= 0 ,0
Exp/Cntr=0.3,0.1

Type RM Length L Ch R = 1 ,26741   ,678,678,678
BEGIN DESCRIPTION:
PINE CREEK 53.0
END DESCRIPTION:
XS GIS Cut Line= 3
      3663842.11     10180091.63       3663801.5     10180609.43
      3663901.33     10181408.02
#Sta/Elev= 30
  4539.4  323.09  4596.6  322.22    4623  321.53  4800.2  321.27  4890.5  319.23
  4963.3  317.69  4970.7  317.51  4980.8  314.33  4986.5  306.75  4991.5  309.76
  4997.8  302.78  5000.6  302.28  5030.9  312.54    5041  314.07  5057.4  316.95
  5111.4  318.67  5179.2  318.17  5212.2  318.38  5252.5  310.74  5261.4  311.36
  5272.7  314.82  5302.9  312.16    5323  315.61  5353.3  316.92  5413.7  313.37
  5486.5   314.6  5564.9  316.87  5605.2  322.67  5770.8  326.73  5863.6  328.59
#Mann= 11 ,-1 , 0
  4539.4     .05       0  4596.6      .1       0    4623     .05       0
  4890.5     .12       0  4963.3     .07       0  4980.8     .05       0
    5041     .07       0  5057.4     .12       0  5179.2     .05       0
  5486.5     .08       0  5770.8     .05       0
Bank Sta=4980.8,5041
XS Rating Curve= 0 ,0
Exp/Cntr=0.3,0.1

Type RM Length L Ch R = 1 ,26063   ,945,945,945
BEGIN DESCRIPTION:
PINE CREEK 52.0
END DESCRIPTION:
XS GIS Cut Line= 3
      3663363.51     10179849.31      3663342.11     10180191.64
      3663337.35     10181208.53
#Sta/Elev= 30
  4676.4  319.23  4781.5  317.33  4959.3  315.92  4969.3  313.06  4979.3  307.15
  4989.3  302.27  4996.4  301.96  4999.1  301.46  5002.4  301.96  5006.1  302.77
  5016.9  304.81  5021.9  304.81  5039.4  308.24  5059.4  310.15  5119.4  310.66
  5149.4   309.6  5159.4   310.1  5179.4  313.57  5189.4  314.45  5279.4  313.26
  5305.5  314.12  5319.5  314.29  5448.5  316.65  5479.4  316.17  5509.4  317.04
  5579.4  317.16  5599.4  317.78  5619.4  316.97  5681.6  316.37  6036.3  322.23
#Mann= 8 ,-1 , 0
  4676.4     .05       0  4996.4     .03       0  5002.4     .05       0
  5006.1     .12       0  5305.5     .16       0  5319.5     .12       0
  5448.5     .16       0  5681.6     .05       0
Bank Sta=4996.4,5002.4
XS Rating Curve= 0 ,0
Exp/Cntr=0.3,0.1

Type RM Length L Ch R = 1 ,25118   ,1043,1043,1043
BEGIN DESCRIPTION:
PINE CREEK 49.0
END DESCRIPTION:
XS GIS Cut Line= 3
      3662992.12     10179591.62      3662709.15     10180202.71
      3662473.57     10180595.33
#Sta/Elev= 30
  4518.6  319.33  4550.3  318.49  4607.1  313.72  4721.7  311.92  4790.5  312.49
  4855.2  308.31  4882.1  306.51  4916.1  300.72  4984.8  300.88  4999.3  298.43
    5002  297.93  5005.3  298.43  5036.6  301.59  5059.1  301.44  5069.6  303.28
    5082  309.03  5089.1   309.7    5192     311  5211.9  307.22  5217.7  302.62
  5233.2  303.66  5239.1  302.14  5270.2  303.44    5276  308.09  5291.5  312.05
  5334.3  313.46  5360.5  311.66  5386.8  315.04  5487.8  317.97  5649.9   321.7
#Mann= 7 ,-1 , 0
  4518.6     .05       0  4855.2     .12       0  4999.3     .07       0
  5005.3     .12       0  5089.1     .16       0  5360.5      .1       0
  5487.8     .12       0
Bank Sta=4999.3,5005.3
XS Rating Curve= 0 ,0
Exp/Cntr=0.3,0.1

Type RM Length L Ch R = 1 ,24075   ,1318,1318,1318
BEGIN DESCRIPTION:
PINE CREEK 47.0
END DESCRIPTION:
XS GIS Cut Line= 3
      3662761.49     10179221.16      3662321.26     10179540.09
      3661793.06     10179862.42
#Sta/Elev= 30
  4282.5  316.61  4289.9     318  4296.1   316.5  4396.7  312.82  4562.1  308.75
  4647.9  307.83  4761.1  307.82  4874.3   307.4  4898.8  305.85  4914.2   302.8
    4951  300.21  4956.9  301.16  4978.2  299.17  4987.8  297.28  4993.6  297.17
  4997.9  295.06  5000.6  294.56  5003.9  295.06  5009.1  296.73  5014.9  297.26
  5024.3  304.79  5030.4  308.79  5036.3  309.39  5198.8  319.37  5220.1  321.75
    5226  323.24  5336.3  332.23    5373  333.55  5378.9  334.56  5444.9  335.68
#Mann= 6 ,-1 , 0
  4282.5      .1       0  4396.7     .05       0  4761.1     .16       0
  4874.3     .12       0  4997.9     .07       0  5003.9     .16       0
Bank Sta=4997.9,5003.9
XS Rating Curve= 0 ,0
Exp/Cntr=0.3,0.1

Type RM Length L Ch R = 1 ,22757   ,644,644,644
BEGIN DESCRIPTION:
PINE CREEK 45.0
END DESCRIPTION:
XS GIS Cut Line= 3
      3662264.16     10178514.45      3661806.53     10178893.99
       3661506.8     10179293.64
#Sta/Elev= 30
  4512.4  324.59  4732.3  310.11  4767.4  310.06  4816.9  306.35  4874.2  306.65
  4917.2  303.37  4923.7   301.1    4938  300.16  4944.5  296.93  4958.9  293.33
    4981  292.82  5005.8  289.83  5008.5  289.33  5011.8  289.83  5016.2  294.26
  5029.5  301.68  5110.5   303.5    5279  304.48  5287.3  304.07  5293.5  301.64
  5337.3  303.01  5343.5  300.94  5372.7   299.7  5416.4  301.79  5437.3  304.79
  5443.5  307.34  5458.1  308.65  5537.3  311.27  5572.7  310.44  5606.5  312.67
#Mann= 5 ,-1 , 0
  4512.4     .05       0  5005.8     .03       0  5011.8     .05       0
  5029.5     .12       0  5110.5     .05       0
Bank Sta=5005.8,5011.8
XS Rating Curve= 0 ,0
Exp/Cntr=0.3,0.1

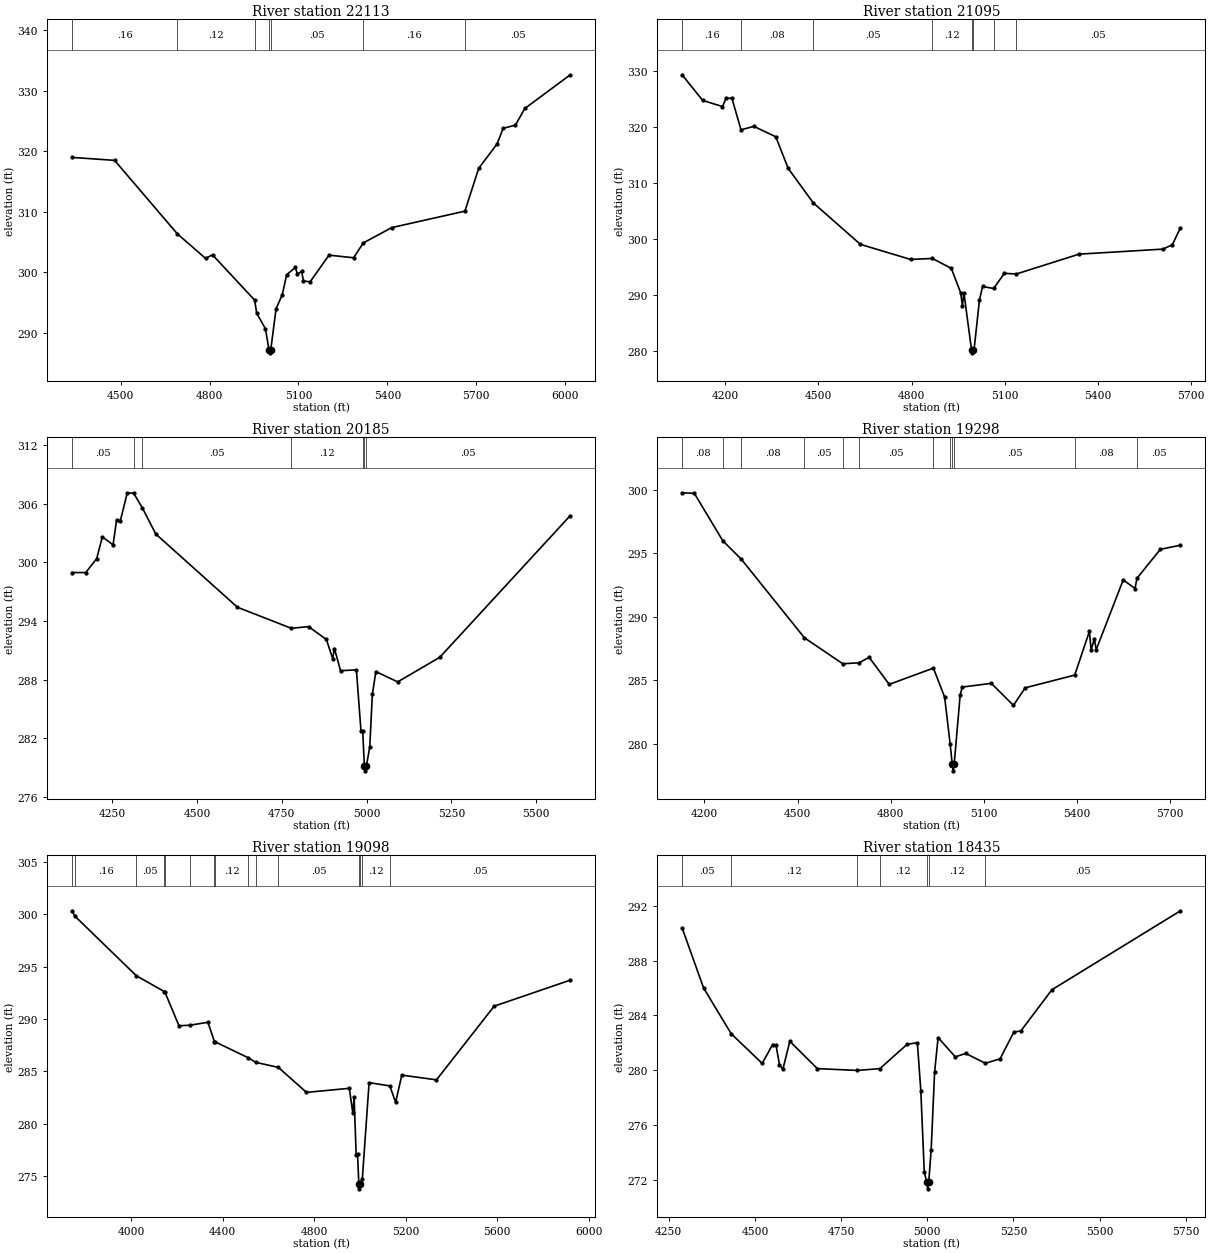
Type RM Length L Ch R = 1 ,22113   ,1018,1018,1018
BEGIN DESCRIPTION:
PINE CREEK 43.0
END DESCRIPTION:
XS GIS Cut Line= 3
      3661842.49      10178112.6      3661300.09     10178888.59
      3661117.97     10179601.22
#Sta/Elev= 30
  4335.3  318.97  4479.4  318.48  4691.2  306.34  4786.4  302.29  4809.9  302.87
    4952   295.4  4959.1  293.23  4988.7  290.64  5000.5  287.18  5003.3  286.68
  5006.5  287.18  5024.5  293.96  5045.4  296.29  5060.2  299.59  5089.9  300.79
    5096  299.69  5110.8  300.12  5116.9  298.56  5139.4  298.41  5203.2  302.82
  5286.2  302.39  5318.9  304.84  5414.8  307.37    5662  310.09  5708.4  317.17
  5770.3  321.19    5791  323.77  5832.3   324.3    5864  327.05  6017.6  332.62
#Mann= 7 ,-1 , 0
  4335.3     .16       0  4691.2     .12       0    4952     .05       0
  5000.5     .03       0  5006.5     .05       0  5318.9     .16       0
    5662     .05       0
Bank Sta=5000.5,5006.5
XS Rating Curve= 0 ,0
Exp/Cntr=0.3,0.1

Type RM Length L Ch R = 1 ,21095   ,910,910,910
BEGIN DESCRIPTION:
PINE CREEK 41.0
END DESCRIPTION:
XS GIS Cut Line= 3
      3660876.91     10177362.77      3660742.11     10178291.64
       3660693.8     10178957.99
#Sta/Elev= 30
  4060.3  329.41  4126.7  324.83  4190.5  323.74  4201.9   325.2  4220.8  325.23
  4250.2  319.58  4291.6   320.2  4362.3  318.34  4402.4  312.69  4483.5  306.52
  4635.1  299.13  4796.8  296.44  4867.3  296.61  4928.2  294.84  4958.5  290.46
  4963.8   288.2  4968.9  290.44  4993.4  280.26  4996.1  279.76  4999.4  280.26
  5001.4  280.26    5019  289.25    5029  291.61  5064.5  291.25  5099.2  293.96
  5137.3  293.83  5339.7  297.38  5610.5  298.28  5640.6  299.06    5667   302.1
#Mann= 8 ,-1 , 0
  4060.3     .16       0  4250.2     .08       0  4483.5     .05       0
  4867.3     .12       0  4993.4     .07       0  4999.4     .12       0
  5064.5     .16       0  5137.3     .05       0
Bank Sta=4993.4,4999.4
XS Rating Curve= 0 ,0
Exp/Cntr=0.3,0.1

Type RM Length L Ch R = 1 ,20185   ,887,887,887
BEGIN DESCRIPTION:
PINE CREEK 39.0
END DESCRIPTION:
XS GIS Cut Line= 3
      3660248.72     10177375.86      3659992.11     10178191.64
      3659843.34     10178787.98
#Sta/Elev= 30
  4130.9  298.96  4171.6  298.96    4204  300.38  4220.8  302.61  4252.3  301.79
  4262.8  304.36    4274  304.28  4294.2  307.12  4313.1  307.07    4339  305.56
  4378.1  302.91  4619.2  295.41  4777.9  293.26  4828.8  293.43  4881.3  292.12
  4899.9  290.17  4905.1  291.19  4923.2  288.92  4969.9  289.01  4983.5  282.72
  4988.6  282.72  4993.4  279.18  4996.1  278.68  4999.4  279.18  5009.3  281.13
    5017   286.5  5027.3  288.83  5091.8  287.78  5215.7  290.29  5600.7  304.79
#Mann= 7 ,-1 , 0
  4130.9     .05       0  4313.1      .1       0    4339     .05       0
  4777.9     .12       0  4988.6     .05       0  4993.4     .03       0
  4999.4     .05       0
Bank Sta=4993.4,4999.4
XS Rating Curve= 0 ,0
Exp/Cntr=0.3,0.1

Type RM Length L Ch R = 1 ,19298   ,200,200,200
BEGIN DESCRIPTION:
PINE CREEK 37.0
END DESCRIPTION:
XS GIS Cut Line= 4
      3659869.43     10177586.35      3659401.14     10177753.92
      3659092.96     10178162.34      3658806.41     10178684.69
#Sta/Elev= 30
  4128.4  299.75    4168   299.7  4259.3  295.98  4319.2  294.52  4522.4  288.34
  4645.9   286.3  4698.4  286.38  4730.7  286.81  4795.3  284.68  4937.6  285.96
  4973.7  283.68  4991.4  280.01  4998.4  278.38  5001.1  277.88  5004.4  278.38
  5023.8  283.85  5030.5  284.47    5124  284.76  5195.3  283.03  5233.2  284.41
  5392.6  285.41  5439.8  288.84  5445.5  287.39  5455.9  288.27  5461.6   287.4
  5548.8   292.9  5586.7  292.22  5593.2  293.03  5668.2   295.3  5733.2  295.63
#Mann= 12 ,-1 , 0
  4128.4     .08       0  4259.3     .05       0  4319.2     .08       0
  4522.4     .05       0  4645.9     .08       0  4698.4     .05       0
  4937.6     .12       0  4991.4     .05       0  4998.4     .04       0
  5004.4     .05       0  5392.6     .08       0  5593.2     .05       0
Bank Sta=4998.4,5004.4
XS Rating Curve= 0 ,0
Exp/Cntr=0.3,0.1

Type RM Length L Ch R = 1 ,19098   ,663,663,663
BEGIN DESCRIPTION:
PINE CREEK 35.0
END DESCRIPTION:
XS GIS Cut Line= 3
      3659966.54     10177257.49      3659275.61     10177576.92
      3658459.62     10178733.19
#Sta/Elev= 30
  3742.3  300.35  3756.7  299.81  4023.1  294.15  4146.3  292.62  4148.8  292.56
  4209.9  289.36  4257.1  289.41  4336.3  289.69  4364.8  287.84  4367.8  287.82
  4511.4  286.31  4545.4  285.86  4643.8  285.38  4766.7  282.99  4953.9  283.38
  4968.7  281.05  4974.8  282.51  4983.5  277.04  4989.6  277.07  4995.3  274.27
    4998  273.77  5001.3  274.27  5010.6  274.73  5040.1  283.92  5130.8  283.61
  5155.9  282.03  5182.9  284.64  5334.4  284.19  5586.3  291.23  5918.7  293.72
#Mann= 15 ,-1 , 0
  3742.3     .05       0  3756.7     .16       0  4023.1     .05       0
  4146.3     .12       0  4148.8     .05       0  4257.1     .12       0
  4364.8     .05       0  4367.8     .12       0  4511.4     .05       0
  4545.4     .12       0  4643.8     .05       0  4995.3     .03       0
  5001.3     .05       0  5010.6     .12       0  5130.8     .05       0
Bank Sta=4995.3,5001.3
XS Rating Curve= 0 ,0
Exp/Cntr=0.3,0.1

Type RM Length L Ch R = 1 ,18435   ,1058,1058,1058
BEGIN DESCRIPTION:
Mapping XS 26c5ca23
END DESCRIPTION:
XS GIS Cut Line= 2
      3658430.09      10177139.3      3658388.42      10178584.7
#Sta/Elev= 30
  4288.6  290.39    4351     286    4431  282.66    4521  280.49  4551.1  281.87
  4561.1  281.82  4571.1   280.4  4581.1  280.07  4601.1  282.11  4681.1  280.11
  4796.8  279.98  4862.5  280.11  4941.2  281.88  4971.2  282.01  4981.2   278.5
  4991.2  272.58  4998.2  271.83    5001  271.33  5004.2  271.83  5011.2  274.18
  5021.2  279.85  5031.3  282.38  5081.3  280.97  5111.3  281.22  5168.6   280.5
  5211.3  280.83  5251.3  282.79  5271.4  282.86  5361.4  285.87  5734.6  291.64
#Mann= 7 ,-1 , 0
  4288.6     .05       0    4431     .12       0  4796.8     .05       0
  4862.5     .12       0  4998.2     .07       0  5004.2     .12       0
  5168.6     .05       0
Bank Sta=4998.2,5004.2
XS Rating Curve= 0 ,0
Exp/Cntr=0.3,0.1

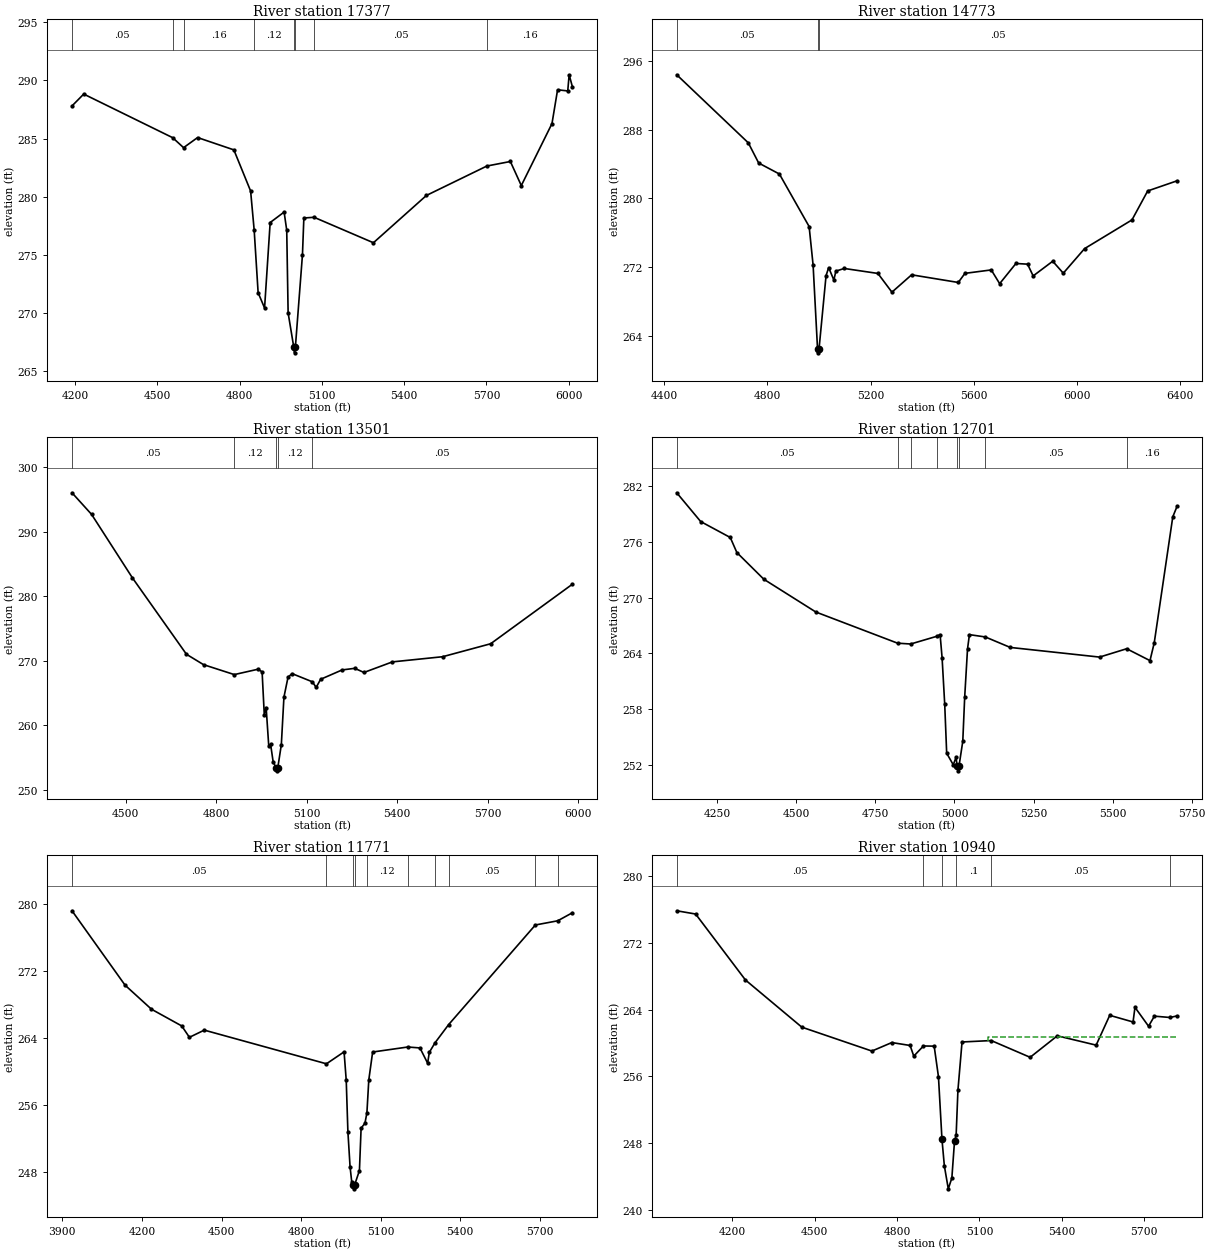
Type RM Length L Ch R = 1 ,17377   ,2604,2604,2604
BEGIN DESCRIPTION:
PINE CREEK 33.0
END DESCRIPTION:
XS GIS Cut Line= 3
      3657539.65     10176891.65      3657692.11     10177691.64
      3657879.91     10178684.55
#Sta/Elev= 30
  4188.6  287.81  4231.4  288.83  4555.7  285.08  4595.6  284.22  4646.7  285.09
    4779  284.03  4840.1  280.49  4853.1  277.12  4867.5  271.74    4891  270.43
  4911.4  277.78  4962.3  278.68  4971.8  277.12  4976.9  270.01  4997.4  267.07
  5000.2  266.57  5003.4  267.07  5029.2  275.01  5034.3  278.17  5071.6  278.23
    5288  276.04  5481.3  280.11  5701.8  282.64  5787.5  283.03  5827.4  280.96
  5939.3  286.29  5959.7   289.2  5996.8   289.1  6001.9  290.49  6013.5  289.48
#Mann= 8 ,-1 , 0
  4188.6     .05       0  4555.7     .12       0  4595.6     .16       0
  4853.1     .12       0  4997.4     .07       0  5003.4     .12       0
  5071.6     .05       0  5701.8     .16       0
Bank Sta=4997.4,5003.4
XS Rating Curve= 0 ,0
Exp/Cntr=0.3,0.1

Type RM Length L Ch R = 1 ,14773   ,1272,1272,1272
BEGIN DESCRIPTION:
PINE CREEK 30.0
END DESCRIPTION:
XS GIS Cut Line= 3
      3656715.14     10177035.56      3656610.44       10178148.
      3656924.45     10178906.84
#Sta/Elev= 30
  4448.6  294.38  4725.9  286.46  4766.1  284.11  4846.4  282.83  4961.6  276.72
    4977  272.23  4994.1  262.52  4996.8  262.02  5000.1  262.52  5027.2  271.01
  5037.3  271.94  5057.4  270.49  5065.2  271.53  5097.5  271.84  5228.1  271.26
  5282.4  269.08  5358.7   271.1  5539.5  270.21  5565.3  271.27  5667.3  271.67
  5699.8  270.07  5762.9  272.42    5808  272.34  5829.6  270.97  5905.4  272.68
  5946.4  271.29  6028.9  274.15  6212.5  277.49  6273.4  280.86  6387.2  282.04
#Mann= 3 ,-1 , 0
  4448.6     .05       0  4994.1     .03       0  5000.1     .05       0
Bank Sta=4994.1,5000.1
XS Rating Curve= 0 ,0
Exp/Cntr=0.3,0.1

Type RM Length L Ch R = 1 ,13501   ,800,800,800
BEGIN DESCRIPTION:
PINE CREEK 28.0
END DESCRIPTION:
XS GIS Cut Line= 3
      3655458.79     10177925.54      3656240.27     10178483.12
      3656610.25     10179076.88
#Sta/Elev= 30
  4321.3  296.03  4386.4  292.67  4521.9  282.82    4701  270.98  4757.6  269.37
  4859.7  267.83  4938.2  268.66  4951.9  268.26  4959.1  261.62  4965.3  262.72
  4973.9  256.78    4980  257.04  4988.6  254.28    4998   253.4  5000.8   252.9
    5004   253.4  5015.7  256.97  5024.3  264.33  5037.9  267.43  5051.3  267.98
  5118.6  266.71  5131.2  265.84    5146   267.1  5217.2  268.55    5259   268.8
  5289.8  268.16  5384.2   269.8  5550.6   270.6  5709.9  272.61  5980.9  281.84
#Mann= 5 ,-1 , 0
  4321.3     .05       0  4859.7     .12       0    4998     .07       0
    5004     .12       0  5118.6     .05       0
Bank Sta=4998,5004
XS Rating Curve= 0 ,0
Exp/Cntr=0.3,0.1

Type RM Length L Ch R = 1 ,12701   ,930,930,930
BEGIN DESCRIPTION:
PINE CREEK 26.0
END DESCRIPTION:
XS GIS Cut Line= 3
      3655006.63     10178420.95      3655692.11     10178941.64
      3656292.09     10179341.63
#Sta/Elev= 30
    4122  281.29  4197.7  278.19  4291.3  276.47  4312.1  274.85  4397.4  271.97
  4561.7  268.44  4820.2  265.08  4861.6  264.99  4945.1  265.83  4954.7     266
    4961   263.5  4969.3  258.49  4975.5  253.22  4996.3  251.97  5005.3  252.79
  5008.4  251.82  5011.1  251.32  5014.4  251.82  5026.4   254.5  5032.4  259.24
  5041.4  264.46  5047.4     266  5097.6  265.75  5176.6  264.62    5459  263.58
  5544.6  264.48  5618.3   263.2  5631.8  265.13  5690.4   278.7  5703.9  279.83
#Mann= 8 ,-1 , 0
    4122     .05       0  4820.2      .1       0  4861.6     .05       0
  4945.1     .12       0  5008.4     .07       0  5014.4     .12       0
  5097.6     .05       0  5544.6     .16       0
Bank Sta=5008.4,5014.4
XS Rating Curve= 0 ,0
Exp/Cntr=0.3,0.1

Type RM Length L Ch R = 1 ,11771   ,831,831,831
BEGIN DESCRIPTION:
PINE CREEK 24.0
END DESCRIPTION:
XS GIS Cut Line= 3
      3654592.11     10178641.65      3655441.76     10179736.78
      3655741.71     10180136.72
#Sta/Elev= 30
  3936.4   279.2  4136.4   270.3    4236  267.42  4350.1  265.42    4379  264.06
  4435.1  264.92  4895.6  260.89    4962  262.32  4970.1  258.93  4976.4  252.78
  4984.6  248.56  4990.9  246.75  4996.1  246.43  4998.8  245.93  5002.1  246.43
  5019.9  248.12  5026.2  253.19  5040.7  253.78  5048.1  255.04  5055.2  258.97
  5069.7   262.3  5202.2   262.9    5248  262.79    5277  260.96  5283.3  262.26
  5304.7   263.4  5356.1  265.58  5683.1   277.5  5767.2     278  5822.4  278.96
#Mann= 10 ,-1 , 0
  3936.4     .05       0  4895.6      .1       0  4996.1     .07       0
  5002.1      .1       0  5048.1     .12       0  5202.2      .1       0
  5304.7     .12       0  5356.1     .05       0  5683.1     .16       0
  5767.2     .05       0
Bank Sta=4996.1,5002.1
XS Rating Curve= 0 ,0
Exp/Cntr=0.3,0.1

Type RM Length L Ch R = 1 ,10940   ,1319,1319,1319
BEGIN DESCRIPTION:
PINE CREEK 22.0
END DESCRIPTION:
XS GIS Cut Line= 3
      3654121.19     10178959.13      3654759.47     10180043.38
       3655158.3     10180442.21
#Sta/Elev= 30
  3997.6  275.88  4066.4  275.49  4247.9  267.57  4453.1  261.91  4708.4  259.04
  4780.9  260.06  4847.6  259.71  4860.9  258.43  4896.1  259.65  4935.2  259.63
  4950.8  255.96  4963.6  248.44  4972.3  245.25  4986.6   242.5  4999.6   243.8
  5009.4  248.28  5015.2  248.93  5021.7  254.33  5036.7  260.13    5143   260.3
  5284.7  258.29  5383.7  260.87  5525.1  259.75  5574.6  263.33  5659.5  262.53
  5666.5  264.29    5716  262.02  5737.2  263.23  5794.1  263.07  5819.8  263.26
#Mann= 6 ,-1 , 0
  3997.6     .05       0  4896.1      .1       0  4963.6     .05       0
  5015.2      .1       0    5143     .05       0  5794.1     .12       0
#XS Ineff= 2 , 0
                         5130.68          260.73
Permanent Ineff=
       F       F
Bank Sta=4963.6,5009.4
XS Rating Curve= 0 ,0
Exp/Cntr=0.3,0.1

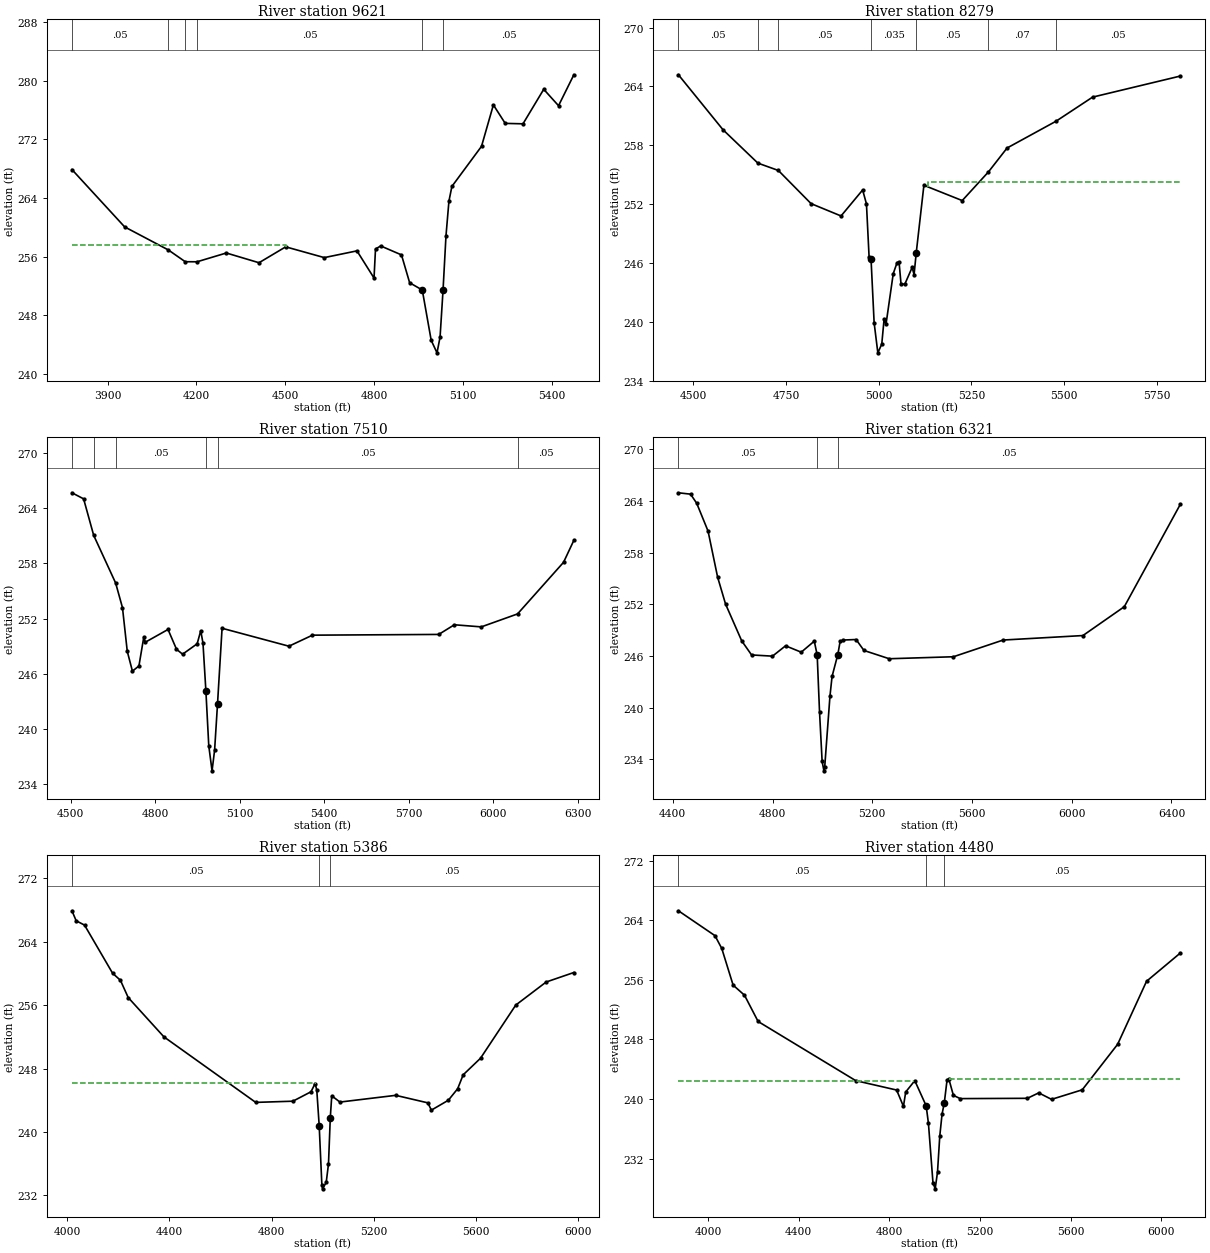
Type RM Length L Ch R = 1 ,9621    ,1342,1342,1342
BEGIN DESCRIPTION:
PINE CREEK 20.0
END DESCRIPTION:
XS GIS Cut Line= 3
      3654042.11     10179541.66      3654142.11     10180741.64
      3654164.59     10181233.38
#Sta/Elev= 30
  3779.1  267.86  3957.2  260.04  4104.7   256.9    4162  255.29  4201.8  255.28
  4300.9  256.48  4411.3  255.15  4501.6  257.32    4632  255.85  4742.4  256.77
  4800.1  253.06  4805.1  257.03  4822.7  257.44  4892.9  256.22  4920.5  252.42
  4963.2  251.43  4993.3  244.57    5013  242.86  5023.3  245.01  5033.3  251.37
  5043.3  258.82  5053.3  263.56  5063.3  265.56  5163.4  271.03  5203.5  276.68
  5243.5  274.16  5303.6   274.1  5373.7  278.81  5423.7  276.57  5475.5  280.79
#Mann= 6 ,-1 , 0
  3779.1     .05       0  4104.7     .12       0    4162      .1       0
  4201.8     .05       0  4963.2    .035       0  5033.3     .05       0
#XS Ineff= 2 , 0
         4501.14  257.52
Permanent Ineff=
       F       F
Bank Sta=4963.2,5033.3
XS Rating Curve= 0 ,0
Exp/Cntr=0.3,0.1

Type RM Length L Ch R = 1 ,8279    ,769,769,769
BEGIN DESCRIPTION:
PINE CREEK 17.0
END DESCRIPTION:
XS GIS Cut Line= 3
      3653617.71     10179540.74      3653418.27     10180303.84
      3653374.75     10180867.73
#Sta/Elev= 30
  4459.5  265.19  4579.9  259.58  4673.9  256.18  4729.2  255.43  4817.4  252.05
  4898.3  250.79  4956.6  253.44  4966.9  252.02    4974  246.61  4979.2  246.44
  4987.6   239.9  4997.6  236.83  5008.2  237.72  5014.5  240.27  5019.6  239.73
  5039.2  244.91  5049.6  246.04  5054.9  246.08  5060.1  243.88  5070.2  243.82
  5090.2  245.54  5095.4  244.81  5101.3  247.06  5121.9  253.92  5225.3  252.36
  5296.2  255.29  5346.3  257.72  5478.3  260.45    5577  262.91  5813.8  265.06
#Mann= 7 ,-1 , 0
  4459.5     .05       0  4673.9     .07       0  4729.2     .05       0
  4979.2    .035       0  5101.3     .05       0  5296.2     .07       0
  5478.3     .05       0
#XS Ineff= 2 , 0
         4956.36   253.4 5131.82          254.23
Permanent Ineff=
       F       F
Bank Sta=4979.2,5101.3
XS Rating Curve= 0 ,0
Exp/Cntr=0.3,0.1

Type RM Length L Ch R = 1 ,7510    ,1189,1189,1189
BEGIN DESCRIPTION:
PINE CREEK 15.0
END DESCRIPTION:
XS GIS Cut Line= 3
      3652992.11     10179441.61      3652787.59     10180223.59
      3652983.44     10181177.41
#Sta/Elev= 30
  4504.1  265.68  4545.5  265.02  4581.3  261.05  4659.2  255.87  4683.5  253.19
  4700.5  248.44  4718.8  246.29  4741.9  246.85  4759.2     250  4764.4  249.43
  4845.2  250.82  4875.3  248.67  4896.9  248.13  4948.6  249.26  4961.4  250.68
  4969.3  249.34  4979.6  244.16  4989.9  238.17  5001.5  235.45  5010.6   237.7
    5021  242.76  5037.1  250.95  5274.5     249    5358   250.2  5806.3  250.28
  5861.8  251.33  5957.5   251.1  6086.2  252.51  6249.5  258.12  6286.1  260.51
#Mann= 6 ,-1 , 0
  4504.1      .1       0  4581.3     .12       0  4659.2     .05       0
  4979.6    .035       0    5021     .05       0  6086.2     .05       0
Bank Sta=4979.6,5021
XS Rating Curve= 0 ,0
Exp/Cntr=0.3,0.1

Type RM Length L Ch R = 1 ,6321    ,935,935,935
BEGIN DESCRIPTION:
PINE CREEK 13.0
END DESCRIPTION:
XS GIS Cut Line= 3
      3651792.09      10179241.6      3652037.86     10180026.84
      3652506.62     10181120.62
#Sta/Elev= 30
  4422.6  264.94  4471.3  264.78    4496  263.72  4541.5  260.49  4579.8  255.15
  4611.6  252.03  4676.5  247.75    4716  246.12  4799.9  245.98  4852.3  247.18
  4915.1  246.44  4967.5  247.72  4979.1  246.11  4988.5  239.52  4998.9  233.78
  5006.1  232.67  5009.4  233.17  5030.4  241.36  5038.8  243.63  5061.8  246.16
  5071.3  247.72  5082.8  247.85  5135.2  247.91  5166.6  246.64  5267.9  245.68
  5525.4  245.91  5724.9  247.85  6044.8  248.37  6210.8  251.72  6435.4   263.6
#Mann= 3 , 0 , 0
  4422.6     .05       0  4979.1    .035       0  5061.8     .05       0
Bank Sta=4979.1,5061.8
XS Rating Curve= 0 ,0
Exp/Cntr=0.3,0.1

Type RM Length L Ch R = 1 ,5386    ,906,906,906
BEGIN DESCRIPTION:
PINE CREEK 11.0
END DESCRIPTION:
XS GIS Cut Line= 3
      3651048.28     10179115.42      3651204.52     10179922.67
      3651760.09     10180920.95
#Sta/Elev= 30
  4018.7  267.91  4035.2  266.65    4068   266.1  4177.8  260.03  4208.4  259.14
  4238.9  256.96  4378.7     252    4738  243.73  4883.6  243.88  4954.5  245.07
  4970.5  246.11  4977.1  245.29  4986.5  240.81    4997  233.32  4999.7  232.82
    5014  233.63  5022.9  235.95    5030  241.82  5035.7  244.56  5067.7  243.77
  5286.1  244.62    5412  243.67  5425.6  242.75  5492.1     244  5528.5  245.45
  5550.2  247.21    5618   249.3    5756  256.01    5875  258.92  5983.4  260.12
#Mann= 3 , 0 , 0
  4018.7     .05       0  4986.5     .04       0    5030     .05       0
#XS Ineff= 2 , 0
         4970.68  246.13
Permanent Ineff=
       F       F
Bank Sta=4986.5,5030
XS Rating Curve= 0 ,0
Exp/Cntr=0.3,0.1

Type RM Length L Ch R = 1 ,4480    ,1243,1243,1243
BEGIN DESCRIPTION:
PINE CREEK 8.0
END DESCRIPTION:
XS GIS Cut Line= 3
      3650570.84     10179080.67       3650486.8     10180425.28
      3651042.08     10181091.61
#Sta/Elev= 30
  3869.4  265.27  4030.7  261.93  4060.7  260.21  4110.8  255.29  4160.9  253.94
  4221.1  250.41  4651.9  242.47  4832.2  241.21  4862.3  239.02  4872.3  240.95
  4912.4  242.47  4962.5   239.1  4972.5  236.77  4992.6  228.77  5002.3  227.95
  5012.6   230.2  5022.6  235.03  5032.6  237.96  5042.7  239.52  5054.6  242.53
  5062.7  242.69  5082.7   240.5  5112.8  240.06  5409.1   240.1  5459.2  240.83
  5515.8  239.96  5651.2  241.24  5807.4  247.35    5935  255.81    6084   259.6
#Mann= 3 , 0 , 0
  3869.4     .05       0  4962.5    .035       0  5042.7     .05       0
#XS Ineff= 2 , 0
         4910.86  242.48 5061.65          242.75
Permanent Ineff=
       F       F
Bank Sta=4962.5,5042.7
XS Rating Curve= 0 ,0
Exp/Cntr=0.3,0.1

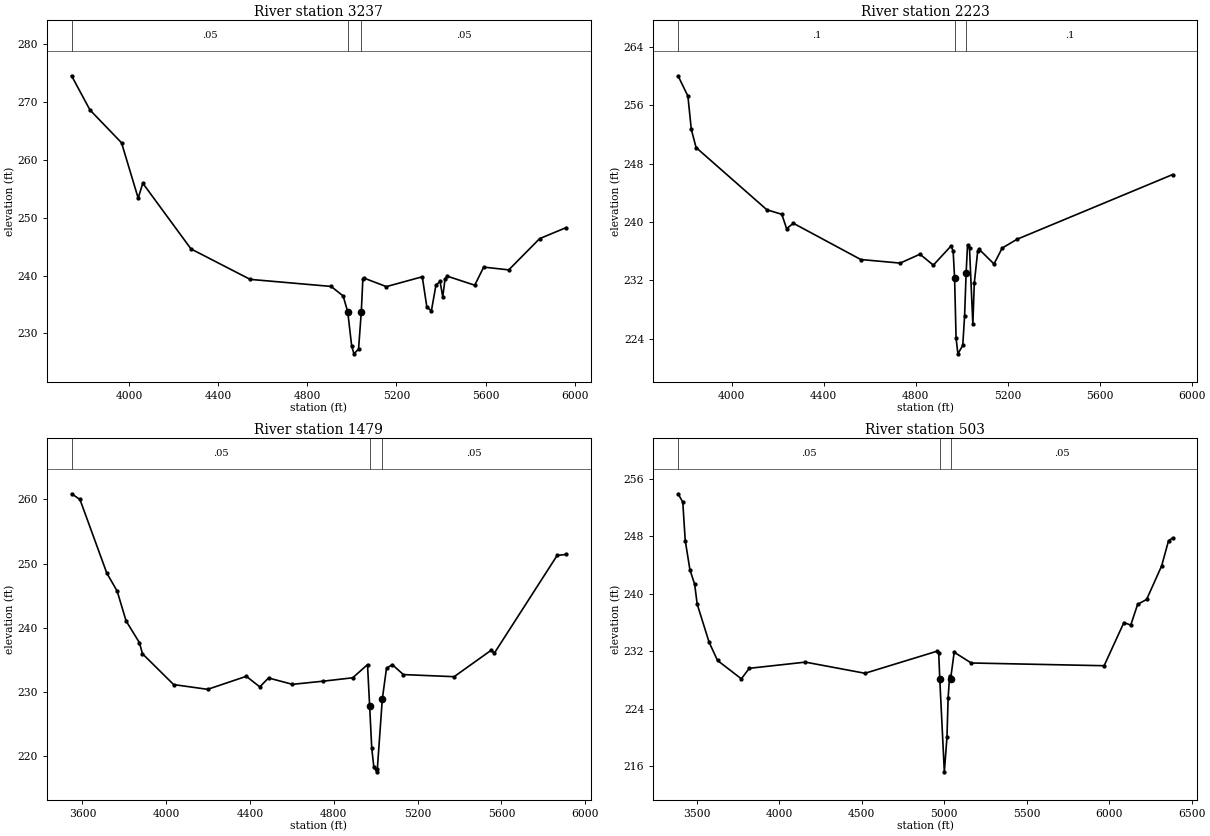
Type RM Length L Ch R = 1 ,3237    ,1014,1014,1014
BEGIN DESCRIPTION:
PINE CREEK 7.0
END DESCRIPTION:
XS GIS Cut Line= 3
       3649592.1     10178991.62      3649892.11     10180191.64
      3650090.97     10181153.45
#Sta/Elev= 30
  3742.3  274.52  3824.8  268.61  3966.5  262.94  4041.2  253.37  4061.9  255.95
  4278.3  244.59  4543.7  239.33  4907.1  238.11  4961.2  236.46  4981.8  233.68
  4999.3  227.82  5009.6  226.46  5030.3  227.29 5042.52  233.73  5049.5  239.36
  5054.6  239.55    5155  238.08  5316.2  239.78  5336.7  234.56  5357.1  233.89
  5377.5  238.33  5395.9  238.99  5408.1  236.31  5418.3  239.39  5428.6  239.88
  5551.7  238.32  5591.7  241.45  5704.3  240.97  5842.8  246.37  5961.4  248.27
#Mann= 3 , 0 , 0
  3742.3     .05       0  4981.8    .035       0 5042.52     .05       0
Bank Sta=4981.8,5042.52
XS Rating Curve= 0 ,0
Exp/Cntr=0.3,0.1

Type RM Length L Ch R = 1 ,2223    ,744,744,744
BEGIN DESCRIPTION:
PINE CREEK 5.0
END DESCRIPTION:
XS GIS Cut Line= 3
      3648092.11     10179891.65      3648904.17     10180478.23
      3649833.02     10181155.33
#Sta/Elev= 30
    3766  260.05  3808.9  257.26  3823.6  252.71  3844.5  250.21  4152.4  241.68
  4217.4  241.06  4238.3  239.09  4267.7  239.83  4560.9  234.86  4732.6  234.37
  4818.4  235.59  4876.6  234.09  4954.4  236.74  4962.9  235.98  4969.1  232.35
  4975.6  224.09  4983.5  221.93  5004.6  223.08  5012.7  227.15  5019.3  233.01
  5025.5  236.88    5034  236.39  5048.6  225.98  5054.8  231.61  5069.5  235.96
  5075.7  236.27  5140.6  234.25  5176.1  236.43    5241  237.64  5917.2   246.5
#Mann= 3 , 0 , 0
    3766      .1       0  4969.1     .05       0  5019.3      .1       0
Bank Sta=4969.1,5019.3
XS Rating Curve= 0 ,0
Exp/Cntr=0.3,0.1

Type RM Length L Ch R = 1 ,1479    ,976,976,976
BEGIN DESCRIPTION:
PINE CREEK 3.0
END DESCRIPTION:
XS GIS Cut Line= 3
      3647664.99     10180311.74      3648374.66     10181129.27
      3649642.12     10181291.64
#Sta/Elev= 30
  3548.2  260.89  3588.2     260  3716.4  248.53  3765.8  245.73  3808.5  241.08
  3872.1   237.7  3886.4  235.98  4035.5  231.17  4197.8  230.43  4382.3  232.46
  4446.7  230.81  4488.4   232.2  4602.4  231.21  4749.2   231.7  4890.3  232.23
  4960.9  234.28    4971  227.87  4981.1  221.26  4991.1  218.31  5004.7  217.58
  5007.9  218.08  5031.5   228.9  5051.6  233.74  5079.6  234.26  5132.3  232.73
  5374.3   232.4  5552.6  236.55  5565.8  236.04  5866.2  251.29  5908.6  251.44
#Mann= 3 , 0 , 0
  3548.2     .05       0    4971    .035       0  5031.5     .05       0
#XS Ineff= 2 , 0
         4960.64  234.27 5080.53          234.22
Permanent Ineff=
       F       F
Bank Sta=4971,5031.5
XS Rating Curve= 0 ,0
Exp/Cntr=0.3,0.1

Type RM Length L Ch R = 1 ,503     ,0,0,0
BEGIN DESCRIPTION:
PINE CREEK 1.0
END DESCRIPTION:
XS GIS Cut Line= 4
      3647392.11     10180541.65      3648114.24     10181632.74
      3648652.44     10181927.88      3649685.38     10181632.75
#Sta/Elev= 30
  3387.5  253.88  3416.1  252.73  3431.1  247.38  3459.4  243.33  3488.3  241.29
  3503.3  238.56  3575.6  233.25  3626.7  230.71  3771.1  228.16  3819.2  229.62
  4159.3  230.48  4520.3  228.93  4957.5     232  4967.2  231.75  4973.6   228.1
  5001.2  215.23  5017.3  220.09  5024.2  225.53  5033.4  228.56  5039.1  228.11
  5060.9  231.86  5164.2  230.36  5969.6  229.98  6089.4  235.98    6131  235.63
  6172.6  238.51    6227  239.19  6318.2  243.86  6359.8  247.35    6384  247.73
#Mann= 3 , 0 , 0
  3387.5     .05       0  4973.6    .035       0  5039.1     .05       0
Bank Sta=4973.6,5039.1
XS Rating Curve= 0 ,0
Exp/Cntr=0.3,0.1

Chan Stop Cuts=-1
Use User Specified Reach Order=0
Composite Channel Slope=5