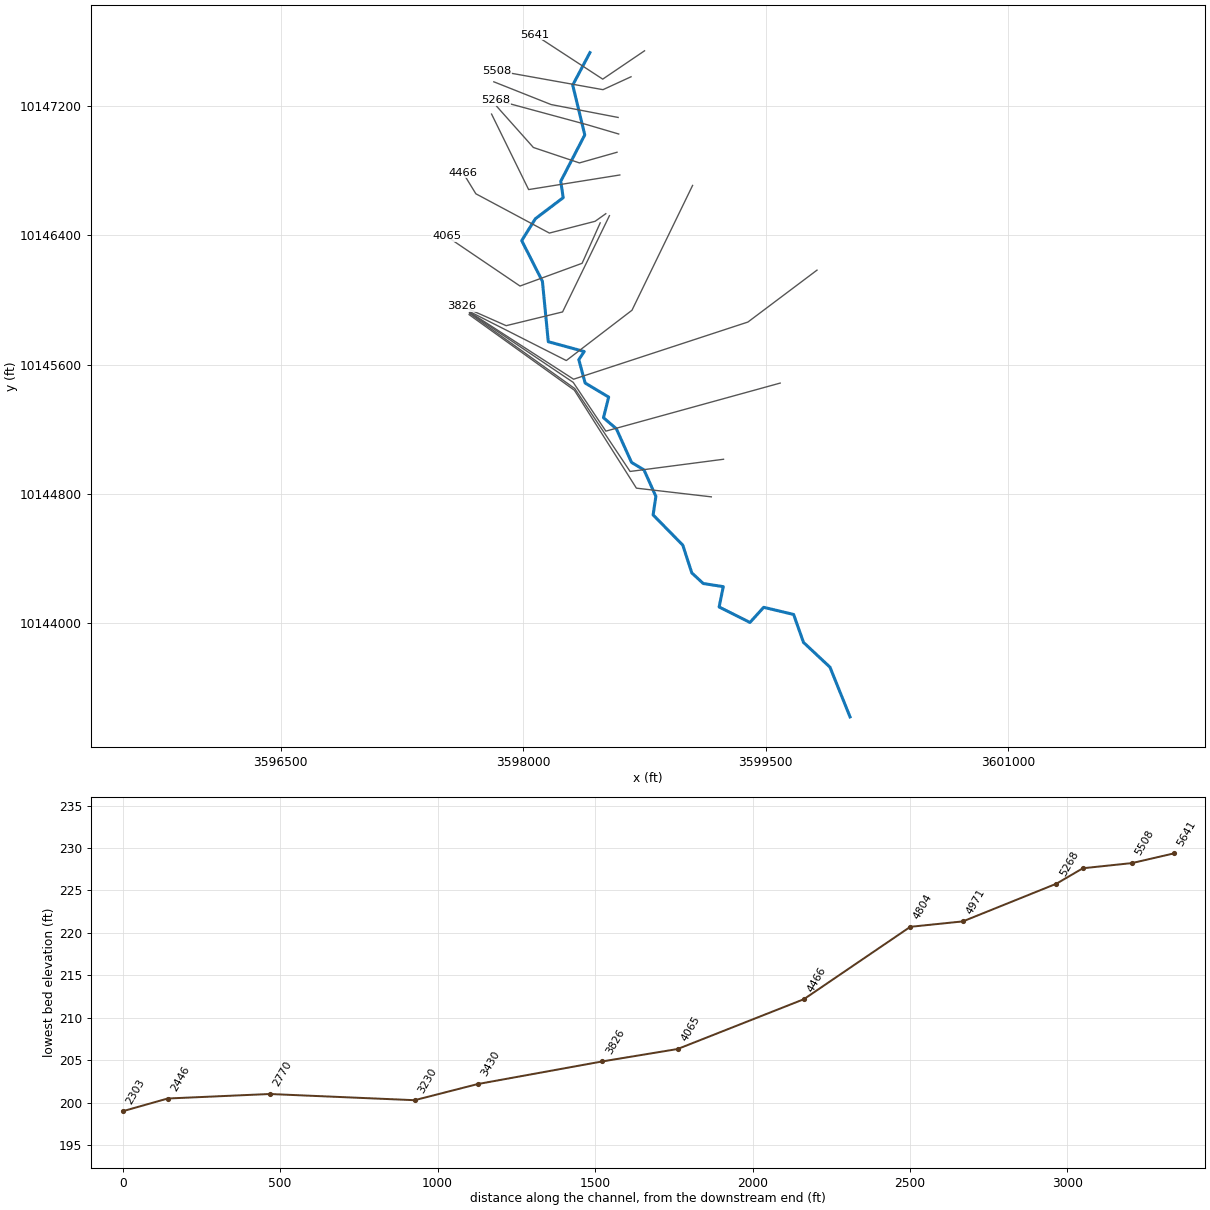
--- SPRING BRANCH 2.prj (project) ---

Proj Title=SPRING BRANCH 2 Base Level Engineering
Current Plan=p01
Default Exp/Contr=0.3,0.1
English Units
Geom File=g01
Flow File=f01
Plan File=p01
Y Axis Title=Elevation
X Axis Title(PF)=Main Channel Distance
X Axis Title(XS)=Station
BEGIN DESCRIPTION:
SPRING BRANCH 2
END DESCRIPTION:
DSS Export Rating Curves= 0
DSS Export Rating Curve Sorted= 0
DSS Export Volume Flow Curves= 0
DXF OffsetX= 0
DXF OffsetY= 0
DXF ScaleX= 1
DXF ScaleY= 10

--- SPRING BRANCH 2.p01 (plan) ---

Plan Title=Multiple Run
Short Identifier=Multiple
Geom File=g01
Flow File=f01
Subcritical Flow
K Sum by GR= 0
Std Step Tol= 0.01
Critical Tol= 0.01
Num of Std Step Trials= 20
Max Error Tol= 0.3
Flow Tol Ratio= 0.001
Split Flow NTrial= 30
Split Flow Tol= 0.02
Split Flow Ratio= 0.02
Log Output Level= 0
Friction Slope Method= 1
Unsteady Friction Slope Method= 2
Unsteady Bridges Friction Slope Method= 1
Parabolic Critical Depth
Global Vel Dist=  1 , 1 , 1
Global Log Level= 0
CheckData=True
Encroach Param= -1, 0, 0, 0
BEGIN DESCRIPTION:
Multiple Run
END DESCRIPTION:

--- SPRING BRANCH 2.f01 (steady flow) ---

Flow Title=Multiple
Program Version=4.10
Number of Profiles= 7
Profile Names=10-year,25-year,50-year,1pct_min,100-year,1pct_plu,500-year
River Rch & RM=SPRING BRANCH 2,Reach-1         ,5641
     708     967    1182    1058    1431    1936    2103
Boundary for River Rch & Prof#=SPRING BRANCH 2,Reach-1         , 1
Up Type= 0
Dn Type= 3
Dn Slope=0.01
Boundary for River Rch & Prof#=SPRING BRANCH 2,Reach-1         , 2
Up Type= 0
Dn Type= 3
Dn Slope=0.01
Boundary for River Rch & Prof#=SPRING BRANCH 2,Reach-1         , 3
Up Type= 0
Dn Type= 3
Dn Slope=0.01
Boundary for River Rch & Prof#=SPRING BRANCH 2,Reach-1         , 4
Up Type= 0
Dn Type= 3
Dn Slope=0.01
Boundary for River Rch & Prof#=SPRING BRANCH 2,Reach-1         , 5
Up Type= 0
Dn Type= 3
Dn Slope=0.01
Boundary for River Rch & Prof#=SPRING BRANCH 2,Reach-1         , 6
Up Type= 0
Dn Type= 3
Dn Slope=0.01
Boundary for River Rch & Prof#=SPRING BRANCH 2,Reach-1         , 7
Up Type= 0
Dn Type= 3
Dn Slope=0.01
DSS Import GetInterval= 0
DSS Import GetPeak= 0
DSS Import FillOption= 0

--- SPRING BRANCH 2.g01 (geometry) ---

Geom Title=Existing Conditions
Program Version=4.10

River Reach=SPRING BRANCH 2 ,Reach-1
Reach XY= 30
      3598412.94     10147531.33      3598306.46     10147330.38
      3598381.03     10147022.25      3598232.46     10146735.25
      3598247.49      10146633.9      3598075.61      10146503.7
      3597990.98     10146368.28      3598119.01     10146116.31
      3598155.28      10145742.9      3598377.61     10145682.08
      3598344.07     10145631.65      3598383.39     10145487.08
      3598528.91     10145400.27      3598496.73     10145272.48
      3598576.38     10145204.11      3598670.41     10144995.96
      3598747.52     10144949.67      3598820.84     10144786.01
      3598803.79     10144671.46      3598987.34     10144484.36
      3599043.14     10144312.63      3599113.87     10144247.02
      3599237.87     10144227.43      3599212.26     10144101.66
      3599402.86     10144005.97      3599487.89      10144099.7
      3599672.97     10144055.52      3599734.24      10143882.5
      3599897.97     10143729.33      3600022.11     10143421.64

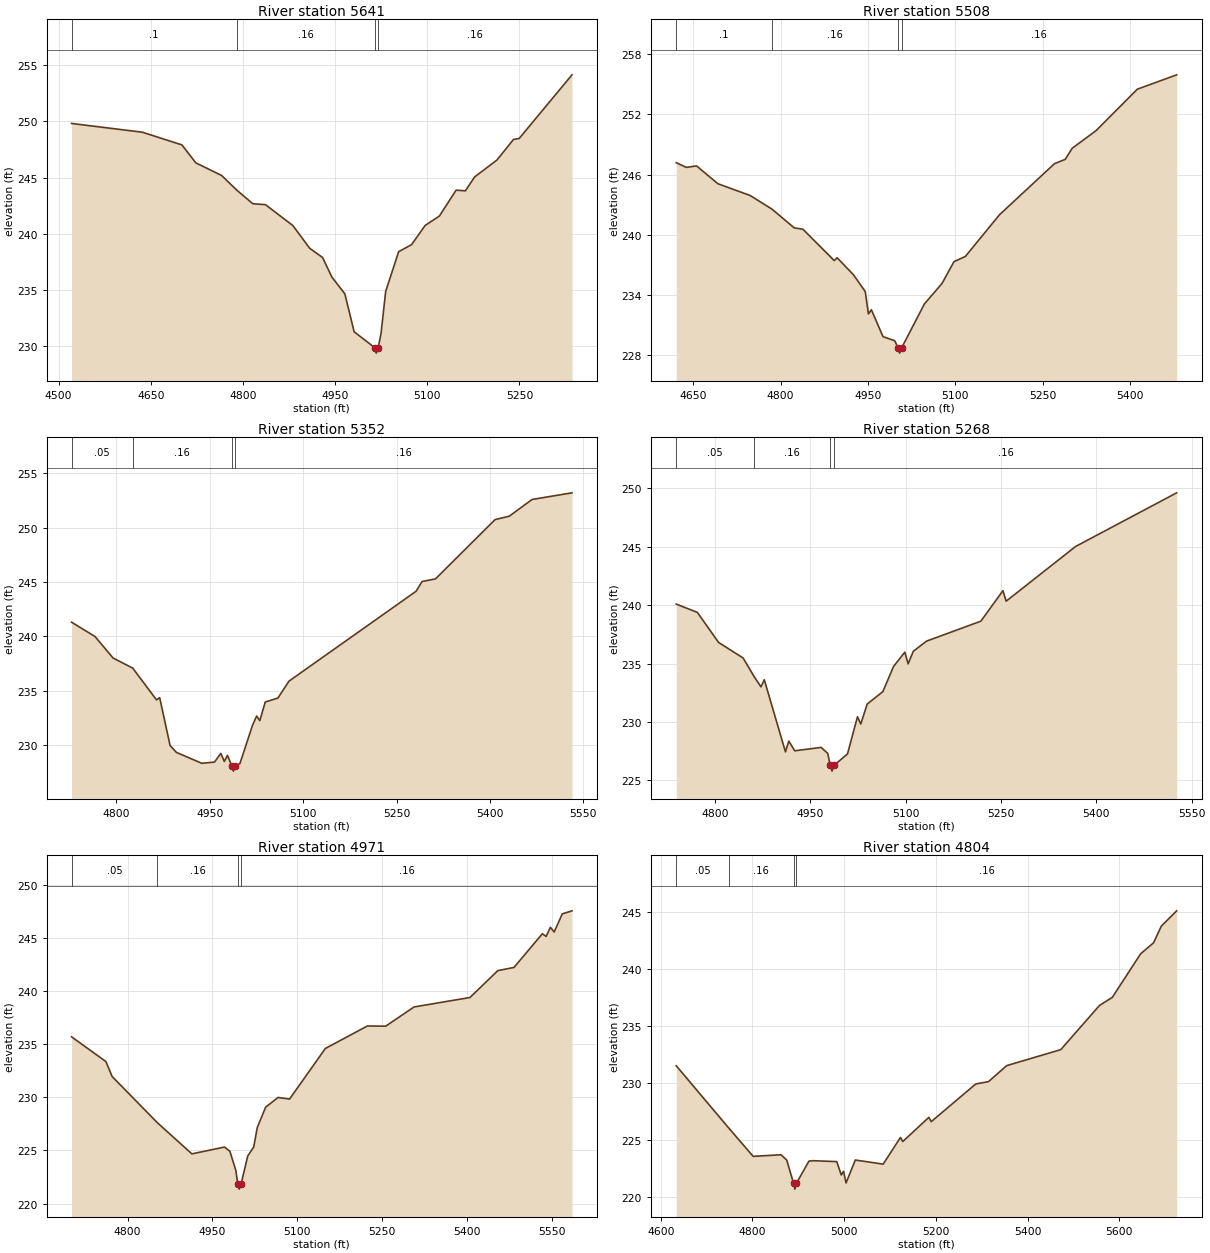
Type RM Length L Ch R = 1 ,5641    ,133,133,133
BEGIN DESCRIPTION:
SPRING BRANCH 2 47.0
END DESCRIPTION:
XS GIS Cut Line= 3
      3598750.76     10147542.57      3598492.08     10147367.22
      3598071.92     10147641.54
#Sta/Elev= 30
  4521.2  249.82  4636.5  249.04  4700.8  247.91  4723.4  246.31  4765.3  245.19
  4790.1  243.88  4816.2  242.67  4836.7  242.59  4881.5  240.72  4908.6  238.71
  4929.7  237.88  4944.8  236.14  4965.9  234.65    4981  231.27  5014.2  229.87
  5016.9  229.37  5020.2  229.87  5024.8  231.13  5032.3  234.86  5053.4   238.4
  5074.5  239.03  5096.4  240.73  5119.8  241.58  5146.9  243.88    5162  243.82
  5177.1  245.06  5213.3  246.56  5240.4   248.4  5249.5  248.48  5335.5  254.15
#Mann= 4 ,-1 , 0
  4521.2      .1       0  4790.1     .16       0  5014.2     .07       0
  5020.2     .16       0
Bank Sta=5014.2,5020.2
XS Rating Curve= 0 ,0
Exp/Cntr=0.3,0.1

Type RM Length L Ch R = 1 ,5508    ,156,156,156
BEGIN DESCRIPTION:
Mapping XS e115f62e
END DESCRIPTION:
XS GIS Cut Line= 3
      3598667.28      10147381.9       3598493.7     10147302.06
      3597835.52     10147419.84
#Sta/Elev= 30
  4620.6  247.18    4638  246.71  4655.5  246.86  4692.3  245.08  4747.4  243.92
    4785  242.56  4823.4  240.69  4838.2  240.56    4892  237.44    4897  237.72
    4925  236.03  4945.3  234.36  4950.8  232.13  4955.9  232.54  4975.8  229.87
  4996.1  229.46  5001.6  228.73  5004.4  228.23  5007.6  228.73  5046.9  233.12
  5077.4  235.18  5097.7  237.33  5117.3  237.85  5176.1  242.01  5270.4  247.08
  5288.8  247.51  5300.9  248.62  5341.5  250.35  5412.7  254.49  5480.3  255.92
#Mann= 4 ,-1 , 0
  4620.6      .1       0    4785     .16       0  5001.6     .07       0
  5007.6     .16       0
Bank Sta=5001.6,5007.6
XS Rating Curve= 0 ,0
Exp/Cntr=0.3,0.1

Type RM Length L Ch R = 1 ,5352    ,84,84,84
BEGIN DESCRIPTION:
Mapping XS b48c6420
END DESCRIPTION:
XS GIS Cut Line= 3
      3598587.49     10147130.18      3598172.52     10147210.04
      3597818.39     10147350.65
#Sta/Elev= 30
  4728.2  241.31  4765.9  239.99  4794.8  238.02  4826.4  237.09  4864.6  234.17
  4869.7  234.37  4886.4  229.98  4896.6  229.34  4937.3  228.34  4957.7  228.45
  4967.9  229.25  4973.5  228.51  4978.6  229.07  4985.3  228.12    4988  227.62
  4991.3  228.12  4998.5  228.31  5018.8  231.84  5025.4  232.68  5030.5  232.26
  5039.2  233.97  5059.6  234.34  5077.3  235.89  5281.4  244.15  5291.1  245.05
  5312.6  245.29  5408.3  250.74    5431  251.05  5467.7  252.59  5531.8   253.2
#Mann= 4 ,-1 , 0
  4728.2     .05       0  4826.4     .16       0  4985.3     .07       0
  4991.3     .16       0
Bank Sta=4985.3,4991.3
XS Rating Curve= 0 ,0
Exp/Cntr=0.3,0.1

Type RM Length L Ch R = 1 ,5268    ,297,297,297
BEGIN DESCRIPTION:
Mapping XS e066591b
END DESCRIPTION:
XS GIS Cut Line= 3
      3598590.89     10147027.76      3598396.48     10147085.04
      3597832.27     10147237.81
#Sta/Elev= 30
  4739.3  240.09  4772.6  239.38  4805.9  236.81  4844.5  235.48  4861.9  233.88
  4872.6  233.01  4877.8  233.62  4911.1  227.45  4916.4  228.37  4925.7  227.54
  4967.2  227.83  4977.6  227.32  4981.6   226.3  4984.3   225.8  4987.6   226.3
  5008.7  227.27  5024.4  230.45  5029.6  229.83  5039.7  231.54  5064.3   232.6
  5081.2  234.76  5098.9  235.98  5104.1  234.98  5112.3  236.06    5133  236.92
  5218.5  238.63  5253.2  241.24  5258.3  240.34  5367.5  245.02  5526.5  249.61
#Mann= 4 ,-1 , 0
  4739.3     .05       0  4861.9     .16       0  4981.6     .07       0
  4987.6     .16       0
Bank Sta=4981.6,4987.6
XS Rating Curve= 0 ,0
Exp/Cntr=0.3,0.1

Type RM Length L Ch R = 1 ,4971    ,167,167,167
BEGIN DESCRIPTION:
Mapping XS d94db6f9
END DESCRIPTION:
XS GIS Cut Line= 4
      3598580.55     10146914.92      3598347.87     10146848.93
      3598063.15     10146944.42      3597835.72     10147199.62
#Sta/Elev= 30
  4701.1   235.7  4761.8  233.37  4772.8  231.96  4852.9   227.6  4913.6  224.68
  4971.3  225.32  4980.7  224.93  4991.2  223.14  4994.6  221.86  4997.3  221.36
  5000.6  221.86  5012.3  224.48  5022.9  225.33  5029.1  227.15    5044  229.08
  5065.9  229.99  5086.2  229.84  5149.4   234.6  5223.7  236.72    5256   236.7
  5306.1  238.51  5404.8   239.4  5454.1  241.93  5482.6  242.23  5532.7   245.4
  5539.4  245.15  5546.9  246.01  5553.6  245.56  5567.9  247.27  5585.1  247.56
#Mann= 4 ,-1 , 0
  4701.1     .05       0  4852.9     .16       0  4994.6     .07       0
  5000.6     .16       0
Bank Sta=4994.6,5000.6
XS Rating Curve= 0 ,0
Exp/Cntr=0.3,0.1

Type RM Length L Ch R = 1 ,4804    ,338,338,338
BEGIN DESCRIPTION:
Mapping XS f22b5f16
END DESCRIPTION:
XS GIS Cut Line= 3
      3598597.83     10146774.27      3598033.63       10146684.
      3597804.46     10147151.03
#Sta/Elev= 30
  4633.7  231.53  4748.5  226.06  4801.5  223.59  4862.3  223.73  4874.7  223.27
  4889.7  221.22  4892.4  220.72  4895.7  221.22  4923.1  223.17  4931.7  223.21
  4983.8  223.13  4993.7  221.96  4998.7  222.28  5004.1  221.26  5024.3  223.27
  5085.1  222.91  5122.8  225.25  5127.9  224.89  5184.8  227.01  5189.9  226.63
    5287  229.93    5315  230.14  5354.5  231.54  5472.5  232.94  5556.9  236.81
  5584.9  237.52  5646.8  241.34  5674.9   242.3  5691.8  243.76  5725.3   245.1
#Mann= 4 ,-1 , 0
  4633.7     .05       0  4748.5     .16       0  4889.7     .07       0
  4895.7     .16       0
Bank Sta=4889.7,4895.7
XS Rating Curve= 0 ,0
Exp/Cntr=0.3,0.1

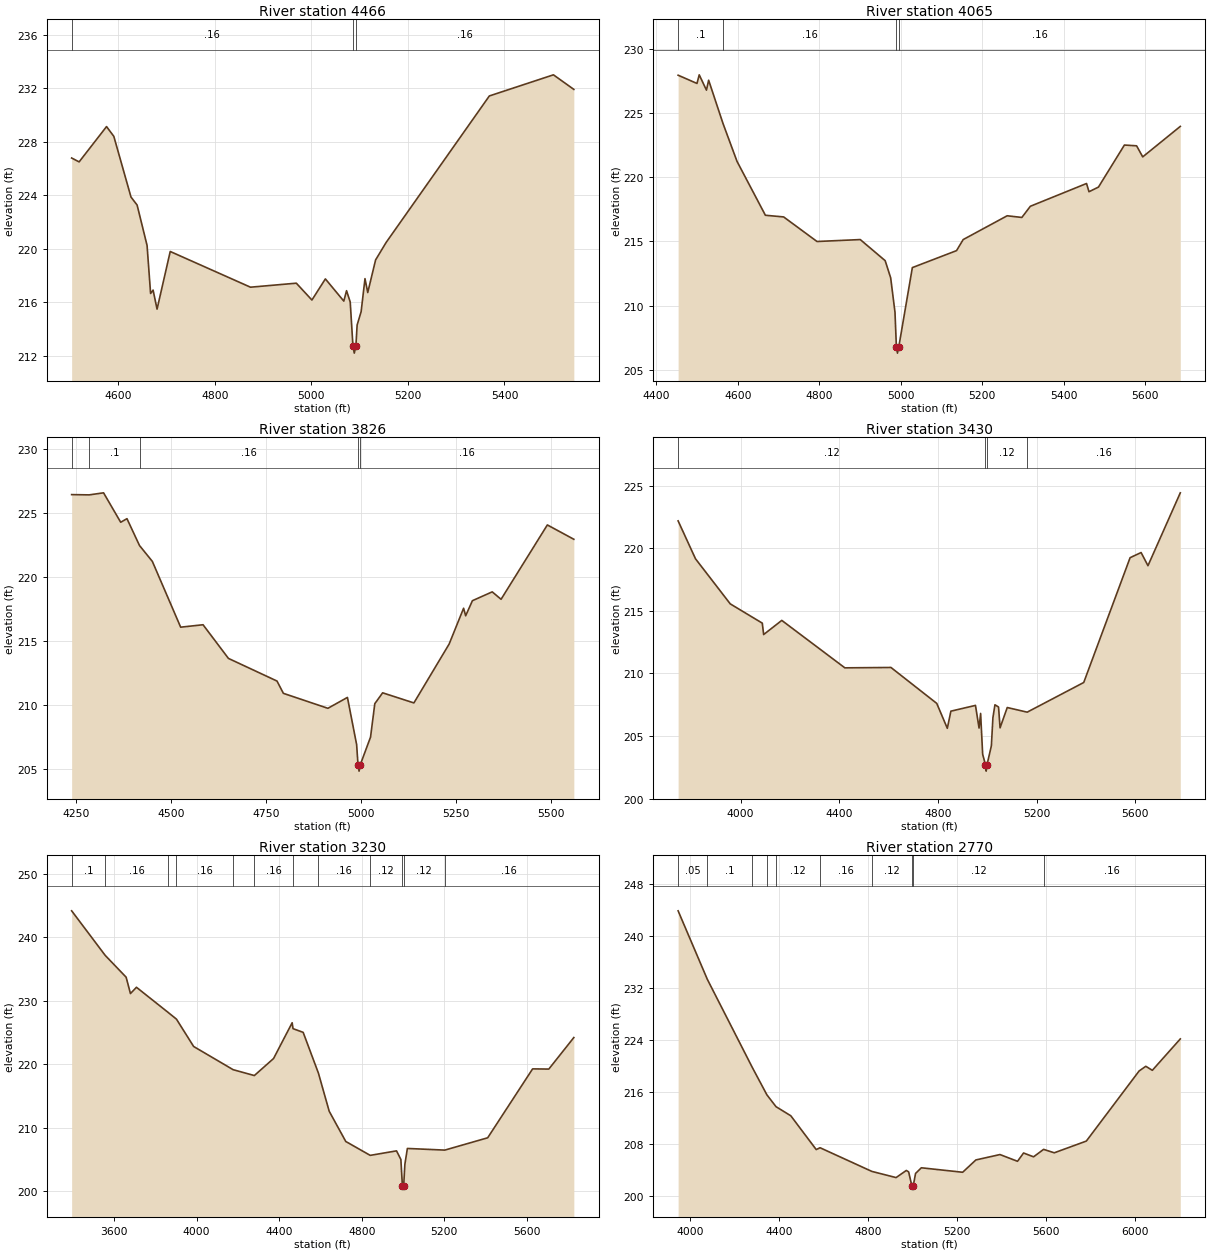
Type RM Length L Ch R = 1 ,4466    ,401,401,401
BEGIN DESCRIPTION:
Mapping XS 5c238336
END DESCRIPTION:
XS GIS Cut Line= 5
      3598511.07      10146534.7      3598445.09     10146487.82
       3598162.1     10146414.91      3597707.24     10146657.96
      3597627.87     10146787.36
#Sta/Elev= 30
  4503.1  226.78  4518.6  226.49  4575.4  229.13  4590.5   228.4  4626.1  223.86
  4638.8  223.26  4659.4  220.24  4666.7  216.65  4671.9   216.9  4680.1  215.48
  4707.4  219.79  4873.7  217.12  4968.7  217.42    5001  216.16  5028.9  217.74
  5067.1  216.08  5072.8  216.86  5080.4  216.01  5086.1  212.69  5088.8  212.19
  5092.1  212.69  5094.7  214.29    5103  215.29    5111  217.76  5116.7  216.72
    5133  219.16  5154.9  220.47  5368.7  231.42  5501.5     233  5543.8  231.91
#Mann= 3 ,-1 , 0
  4503.1     .16       0  5086.1     .07       0  5092.1     .16       0
Bank Sta=5086.1,5092.1
XS Rating Curve= 0 ,0
Exp/Cntr=0.3,0.1

Type RM Length L Ch R = 1 ,4065    ,239,239,239
BEGIN DESCRIPTION:
Mapping XS 135eaeb1
END DESCRIPTION:
XS GIS Cut Line= 4
      3598476.46     10146477.91      3598364.47      10146227.9
      3597980.36     10146087.27      3597525.85     10146395.04
#Sta/Elev= 30
  4453.7  227.93    4500  227.29  4505.5  227.96  4523.2  226.77  4528.6  227.54
    4564  224.16  4598.2  221.23  4667.8  217.04  4712.6  216.91  4794.4     215
  4900.5  215.15  4961.6  213.51  4975.1  212.18  4985.7   209.5  4989.1  206.82
  4991.8  206.32  4995.1  206.82  5028.3  212.97  5136.7  214.29    5153  215.15
  5260.9     217  5296.9  216.87  5317.8  217.74  5455.6  219.51  5461.6  218.87
  5484.8  219.23  5548.5   222.5  5578.4  222.44  5593.4  221.58  5685.6  223.95
#Mann= 4 ,-1 , 0
  4453.7      .1       0    4564     .16       0  4989.1     .07       0
  4995.1     .16       0
Bank Sta=4989.1,4995.1
XS Rating Curve= 0 ,0
Exp/Cntr=0.3,0.1

Type RM Length L Ch R = 1 ,3826    ,396,396,396
BEGIN DESCRIPTION:
Mapping XS 30de3ea8
END DESCRIPTION:
XS GIS Cut Line= 4
      3598533.65     10146522.59       3598243.7     10145927.06
      3597894.74     10145841.99      3597620.41     10145963.53
#Sta/Elev= 30
  4238.6  226.47  4284.9  226.45  4322.6  226.61  4367.7  224.31  4384.2  224.59
  4417.2  222.49    4451  221.25  4525.5  216.11  4584.4   216.3  4651.2  213.67
    4779   211.9  4795.8  210.94  4912.9  209.77  4964.4  210.62  4988.6  206.93
  4992.2  205.36    4995  204.86  4998.2  205.36  5025.2  207.52  5036.4  210.13
    5057  210.98  5139.3  210.19    5232  214.79  5270.1  217.59  5275.5     217
  5293.3  218.18  5345.4  218.87  5368.7  218.29  5490.5   224.1  5560.2  222.98
#Mann= 5 ,-1 , 0
  4238.6     .16       0  4284.9      .1       0  4417.2     .16       0
  4992.2     .07       0  4998.2     .16       0
Bank Sta=4992.2,4998.2
XS Rating Curve= 0 ,0
Exp/Cntr=0.3,0.1

Type RM Length L Ch R = 1 ,3430    ,200,200,200
BEGIN DESCRIPTION:
Mapping XS 8c9078af
END DESCRIPTION:
XS GIS Cut Line= 4
      3599048.08      10146709.7      3598673.07     10145937.53
      3598266.82     10145626.33      3597672.84     10145927.22
#Sta/Elev= 30
  3746.9  222.18  3817.4  219.15  3958.3  215.55  4088.2  214.01  4093.7   213.1
  4167.2  214.23  4422.9  210.44  4609.8  210.47  4795.5   207.6  4838.3  205.61
  4852.8  206.98  4952.5  207.44    4967  205.63  4973.3   206.8  4981.6  203.54
  4993.1  202.69  4995.8  202.19  4999.1  202.69  5016.9  204.21  5023.2  206.46
  5031.4  207.49    5046  207.31  5052.2  205.65  5081.3  207.27  5162.1   206.9
  5391.4  209.27  5579.4  219.24    5624  219.65  5651.8   218.6  5782.9  224.42
#Mann= 4 ,-1 , 0
  3746.9     .12       0  4993.1     .07       0  4999.1     .12       0
  5162.1     .16       0
Bank Sta=4993.1,4999.1
XS Rating Curve= 0 ,0
Exp/Cntr=0.3,0.1

Type RM Length L Ch R = 1 ,3230    ,460,460,460
BEGIN DESCRIPTION:
Mapping XS 1c00597d
END DESCRIPTION:
XS GIS Cut Line= 4
      3599817.78     10146185.67       3599390.3     10145864.51
      3598311.74     10145510.77      3597669.52     10145925.21
#Sta/Elev= 30
  3394.1  244.15  3556.7  237.13  3658.2  233.69  3679.1  231.11  3708.2   232.1
  3859.4   228.2  3902.1  227.08  3985.4  222.77  4177.1  219.11  4279.6  218.19
  4372.7  220.87  4462.9  226.51  4467.1  225.58  4516.2     225  4590.1  218.58
  4642.5  212.56  4722.8   207.8  4841.2  205.61  4968.8  206.32  4989.8  204.97
  4997.3  200.79  5000.1  200.29  5003.3  200.79  5009.3  204.21  5021.4   206.7
  5202.7  206.44  5410.6  208.38  5628.4  219.24  5706.9  219.21  5828.2  224.18
#Mann= 12 ,-1 , 0
  3394.1      .1       0  3556.7     .16       0  3859.4      .1       0
  3902.1     .16       0  4177.1     .12       0  4279.6     .16       0
  4467.1      .1       0  4590.1     .16       0  4841.2     .12       0
  4997.3     .07       0  5003.3     .12       0  5202.7     .16       0
Bank Sta=4997.3,5003.3
XS Rating Curve= 0 ,0
Exp/Cntr=0.3,0.1

Type RM Length L Ch R = 1 ,2770    ,324,324,324
BEGIN DESCRIPTION:
Mapping XS e5b0955d
END DESCRIPTION:
XS GIS Cut Line= 4
      3599589.94      10145486.9      3598511.39     10145189.59
      3598309.57     10145491.24      3597667.91     10145922.62
#Sta/Elev= 30
  3946.7  243.93  4077.7  233.38  4280.3  219.75  4345.5  215.55  4386.4  213.73
  4452.7  212.33  4566.8  207.12  4584.1   207.4  4816.8  203.75  4925.4   202.8
  4971.4   203.9  4981.8  203.68  4996.3  201.52  4999.1  201.02  5002.3  201.52
  5012.9  203.44  5038.9  204.31  5224.4  203.62  5283.7  205.52  5391.8  206.35
  5470.7  205.31  5497.8  206.59  5542.7     206  5587.8  207.15  5635.7  206.62
  5779.7  208.43  6016.7  219.24  6046.7  219.96    6076  219.34  6201.6  224.18
#Mann= 10 ,-1 , 0
  3946.7     .05       0  4077.7      .1       0  4280.3     .16       0
  4345.5      .1       0  4386.4     .12       0  4584.1     .16       0
  4816.8     .12       0  4996.3     .07       0  5002.3     .12       0
  5587.8     .16       0
Bank Sta=4996.3,5002.3
XS Rating Curve= 0 ,0
Exp/Cntr=0.3,0.1

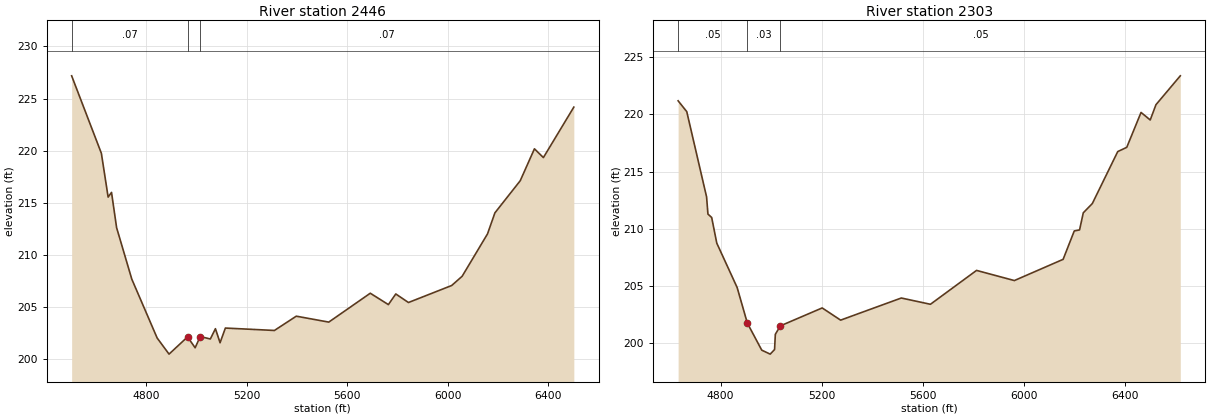
Type RM Length L Ch R = 1 ,2446    ,143,143,143
BEGIN DESCRIPTION:
Mapping XS e1073e8d
END DESCRIPTION:
XS GIS Cut Line= 4
      3599239.45     10145015.65      3598661.35     10144940.14
       3598318.9     10145453.16      3597668.78     10145917.24
#Sta/Elev= 30
    4503  227.18  4621.3  219.75  4648.2  215.55  4661.7     216  4681.9  212.62
  4742.4  207.68  4843.2  202.04  4890.6  200.49  4964.2  202.14  4994.5   201.1
  5014.7  202.18    5055  201.94  5075.2  202.93  5093.7  201.58  5114.8  202.99
    5310  202.76  5397.1  204.13  5526.3  203.56  5691.5  206.33  5763.5  205.24
    5793  206.26  5843.4  205.44  6015.4  207.07  6057.2  207.96    6158  212.02
  6187.5  214.04  6288.3  217.12  6344.8  220.18  6380.4  219.34  6501.6  224.18
#Mann= 3 , 0 , 0
    4503     .07       0  4964.2     .03       0  5014.7     .07       0
Bank Sta=4964.2,5014.7
XS Rating Curve= 0 ,0
Exp/Cntr=0.3,0.1

Type RM Length L Ch R = 1 ,2303    ,0,0,0
BEGIN DESCRIPTION:
SPRING BRANCH 2 1.0
END DESCRIPTION:
XS GIS Cut Line= 4
      3599163.94     10144783.02      3598700.41     10144836.84
      3598316.73     10145442.74      3597665.54     10145910.35
#Sta/Elev= 30
  4632.2   221.2  4666.4  220.25  4744.8  212.77  4750.1  211.27  4764.9  210.97
  4785.1  208.72  4865.6  204.83  4905.9  201.71 4962.77  199.34  4996.2  198.99
 5013.56  199.39  5016.6  200.73  5036.7  201.47  5201.8  203.04  5274.7  201.97
  5514.6  203.91  5629.8  203.36  5812.1  206.33  5961.6  205.44  6154.4   207.3
  6198.5  209.79  6219.4  209.88  6234.1  211.38  6269.8  212.19  6370.4  216.75
    6406  217.12  6462.5  220.18  6498.8  219.52  6521.5  220.86  6617.7  223.39
#Mann= 3 , 0 , 0
  4632.2     .05       0  4905.9     .03       0  5036.7     .05       0
#XS Ineff= 2 , 0
                         5202.58          203.02
Permanent Ineff=
       F       F
Bank Sta=4905.9,5036.7
XS Rating Curve= 0 ,0
Exp/Cntr=0.3,0.1

Chan Stop Cuts=-1
Use User Specified Reach Order=0
Composite Channel Slope=5