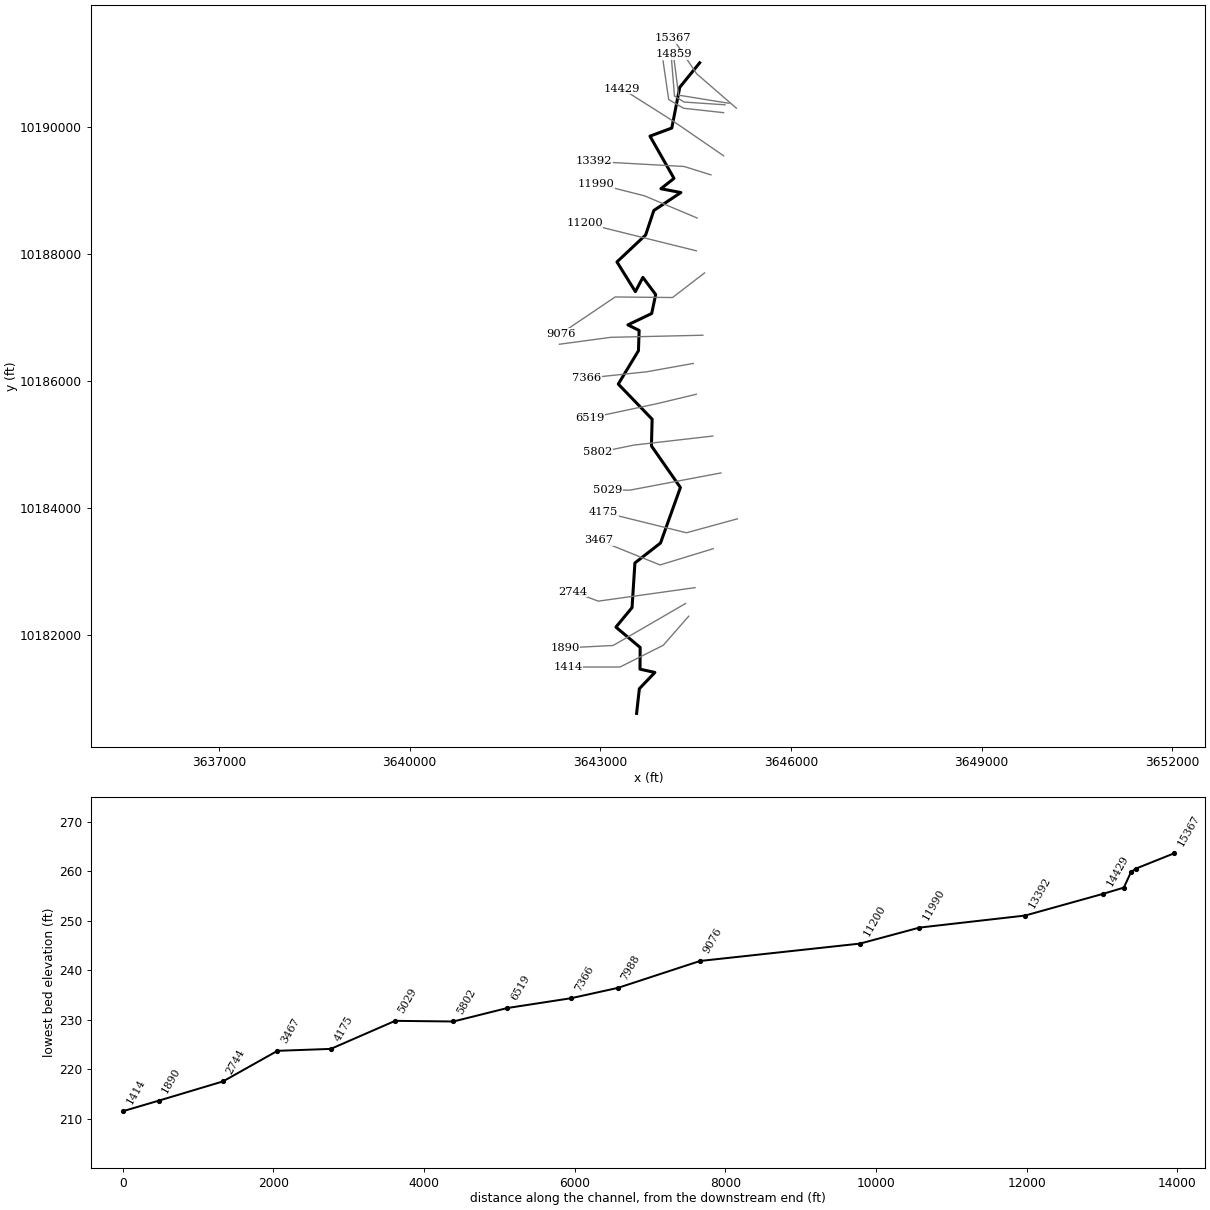
--- TANYARD BRANCH.prj (project) ---

Proj Title=TANYARD BRANCH Base Level Engineering
Current Plan=p01
Default Exp/Contr=0.3,0.1
English Units
Geom File=g01
Flow File=f01
Plan File=p01
BEGIN DESCRIPTION:
TANYARD BRANCH
END DESCRIPTION:

--- TANYARD BRANCH.p01 (plan) ---

Plan Title=Multiple Run
Short Identifier=Multiple
Geom File=g01
Flow File=f01
Subcritical Flow
K Sum by GR= 0
Std Step Tol= 0.01
Critical Tol= 0.01
Num of Std Step Trials= 20
Max Error Tol= 0.3
Flow Tol Ratio= 0.001
Split Flow NTrial= 30
Split Flow Tol= 0.02
Split Flow Ratio= 0.02
Log Output Level= 0
Friction Slope Method= 1
Unsteady Friction Slope Method= 2
Unsteady Bridges Friction Slope Method= 1
Parabolic Critical Depth
Global Vel Dist=  1 , 1 , 1
Global Log Level= 0
CheckData=True
Encroach Param= -1, 0, 0, 0
BEGIN DESCRIPTION:
Multiple Run
END DESCRIPTION:

--- TANYARD BRANCH.f01 (steady flow) ---

Flow Title=Multiple
Number of Profiles=7
Profile Names=10-year,25-year,50-year,1pct_min,100-year,1pct_plu,500-year
River Rch & RM= TANYARD BRANCH,Reach-1,15367
     658     892    1083     965    1306    1766    1898
River Rch & RM= TANYARD BRANCH,Reach-1,14429
    1110    1538    1897    1712    2315    3131    3454
River Rch & RM= TANYARD BRANCH,Reach-1,7366
    1228    1707    2109    1905    2576    3484    3853
Boundary for River Rch & Prof#=TANYARD BRANCH,Reach-1,1
Up Type=0
Dn Type=3
Dn Slope=0.005
Boundary for River Rch & Prof#=TANYARD BRANCH,Reach-1,2
Up Type=0
Dn Type=3
Dn Slope=0.005
Boundary for River Rch & Prof#=TANYARD BRANCH,Reach-1,3
Up Type=0
Dn Type=3
Dn Slope=0.005
Boundary for River Rch & Prof#=TANYARD BRANCH,Reach-1,4
Up Type=0
Dn Type=3
Dn Slope=0.005
Boundary for River Rch & Prof#=TANYARD BRANCH,Reach-1,5
Up Type=0
Dn Type=3
Dn Slope=0.005
Boundary for River Rch & Prof#=TANYARD BRANCH,Reach-1,6
Up Type=0
Dn Type=3
Dn Slope=0.005
Boundary for River Rch & Prof#=TANYARD BRANCH,Reach-1,7
Up Type=0
Dn Type=3
Dn Slope=0.005

--- TANYARD BRANCH.g01 (geometry) ---

Geom Title=Existing Conditions

River Reach=TANYARD BRANCH,Reach-1
Reach XY= 30
      3644564.26     10191005.90      3644250.91     10190620.12
      3644125.79     10189979.24      3643782.58     10189851.15
      3644160.39     10189185.99      3643954.72     10189023.08
      3644268.87     10188963.33      3643843.00     10188680.88
      3643714.22     10188295.34      3643263.10     10187870.88
      3643552.72     10187403.36      3643670.82     10187627.19
      3643872.58     10187356.61      3643809.01     10187058.03
      3643435.19     10186879.52      3643612.11     10186791.64
      3643601.12     10186472.07      3643283.70     10185947.36
      3643816.51     10185394.21      3643805.49     10184973.14
      3644261.31     10184318.67      3643948.09     10183443.91
      3643545.66     10183130.25      3643500.29     10182427.30
      3643246.56     10182120.12      3643628.26     10181799.86
      3643625.62     10181457.56      3643859.95     10181406.37
      3643615.40     10181150.10      3643572.11     10180761.64

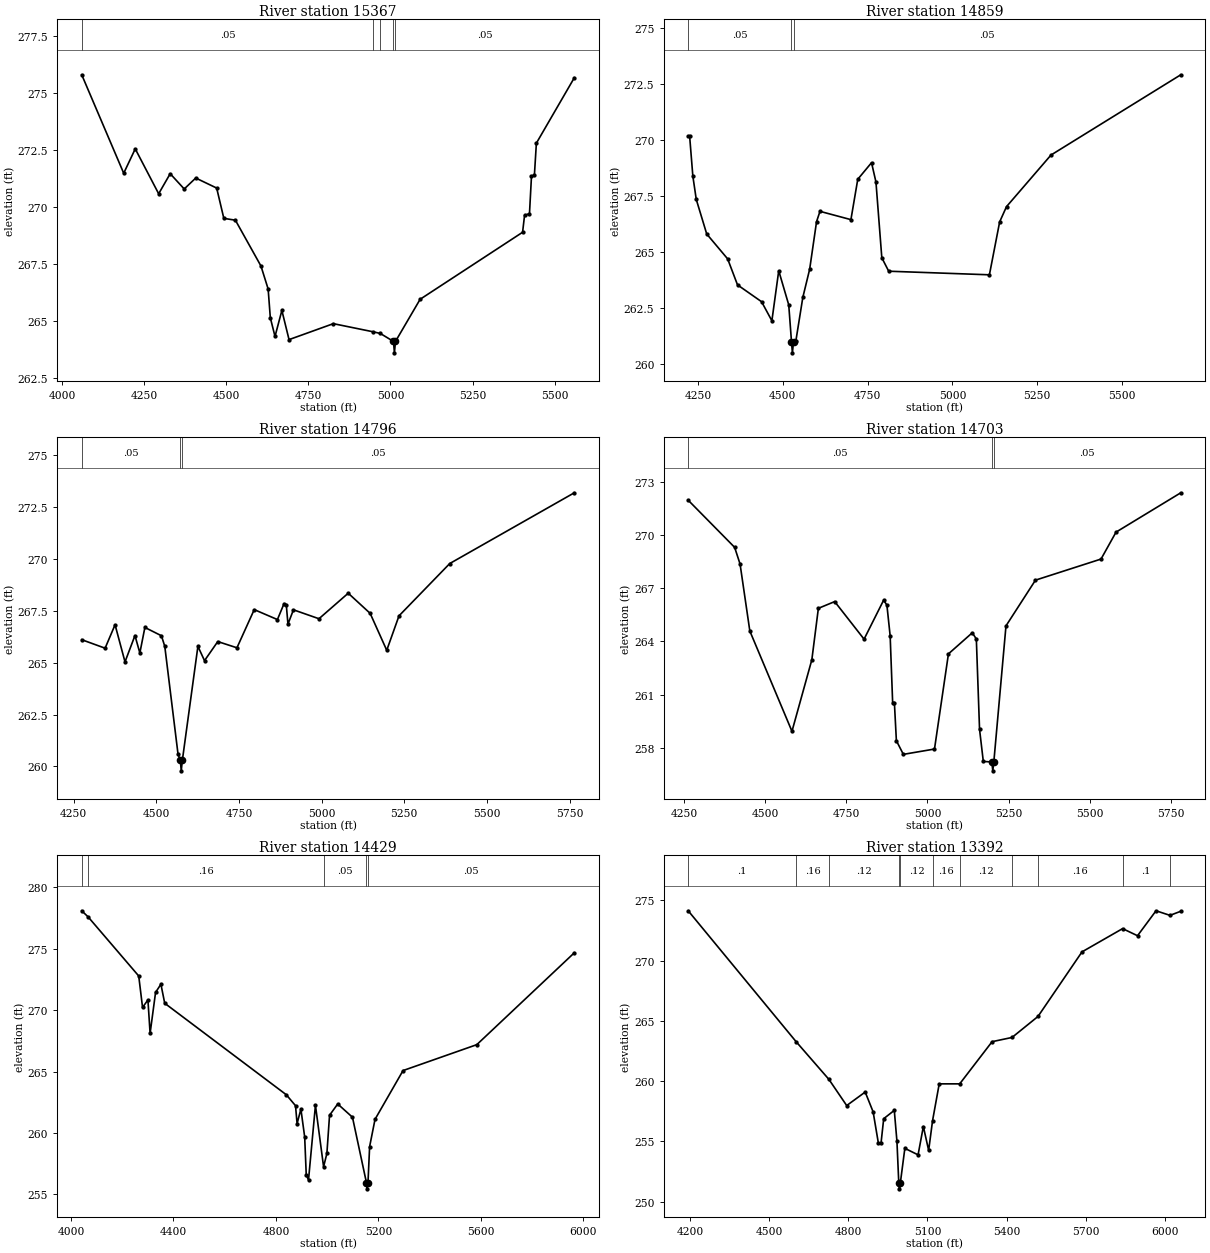
Type RM Length L Ch R = 1,15367,508,508,508
BEGIN DESCRIPTION:
TANYARD BRANCH 28.0
END DESCRIPTION:
XS GIS Cut Line= 3
      3645142.14     10190291.61      3644517.27     10190833.34
      3644142.13     10191391.61
#Sta/Elev= 30
  4060.1  275.80  4187.9  271.48  4223.0  272.55  4294.3  270.58  4329.4  271.46
  4372.1  270.79  4407.2  271.27  4470.9  270.83  4492.7  269.50  4527.9  269.42
  4605.7  267.41  4627.6  266.40  4634.2  265.14  4648.5  264.32  4669.4  265.46
  4691.2  264.18  4826.1  264.88  4948.3  264.52  4969.1  264.45  5009.2  264.10
  5012.0  263.60  5015.2  264.10  5090.3  265.95  5402.2  268.89  5408.2  269.63
  5423.2  269.71  5429.3  271.35  5438.2  271.40  5444.2  272.80  5559.7  275.67
#Mann=5,-1,0
  4060.1    0.05       0  4948.3    0.07       0  4969.1    0.05       0
  5009.2    0.03       0  5015.2    0.05       0
Bank Sta=5009.2,5015.2
Exp/Cntr=0.3,0.1

Type RM Length L Ch R = 1,14859,63,63,63
BEGIN DESCRIPTION:
Mapping XS c4776f5e
END DESCRIPTION:
XS GIS Cut Line= 3
      3645025.63     10190368.67      3644233.54     10190496.71
      3644151.07     10191141.28
#Sta/Elev= 30
  4220.9  270.16  4225.2  270.16  4234.6  268.39  4244.7  267.35  4275.5  265.81
  4337.2  264.70  4366.3  263.54  4437.2  262.79  4467.6  261.94  4487.8  264.17
  4517.3  262.65  4525.4  261.01  4528.1  260.51  4531.4  261.01  4538.5  261.06
  4558.8  262.98  4579.0  264.24  4599.3  266.36  4609.4  266.82  4700.6  266.45
  4720.8  268.25  4761.4  268.99  4774.4  268.13  4791.7  264.75  4812.0  264.15
  5108.9  263.99  5139.1  266.35  5159.3  267.03  5290.4  269.33  5673.1  272.91
#Mann=3,-1,0
  4220.9    0.05       0  4525.4    0.03       0  4531.4    0.05       0
Bank Sta=4525.4,4531.4
Exp/Cntr=0.3,0.1

Type RM Length L Ch R = 1,14796,93,93,93
BEGIN DESCRIPTION:
Mapping XS 176b8cb7
END DESCRIPTION:
XS GIS Cut Line= 4
      3644962.69     10190344.80      3644320.34     10190388.20
      3644168.43     10190481.52      3644114.22     10191147.22
#Sta/Elev= 30
  4274.4  266.11  4345.1  265.70  4375.2  266.83  4405.3  265.04  4435.4  266.31
  4450.2  265.47  4465.4  266.70  4515.5  266.30  4525.6  265.79  4565.7  260.59
  4572.7  260.29  4575.4  259.79  4578.7  260.29  4625.8  265.79  4645.8  265.10
  4685.9  266.02  4743.9  265.72  4796.2  267.56  4866.3  267.08  4886.4  267.85
  4893.2  267.78  4898.2  266.86  4914.8  267.55  4992.0  267.12  5080.5  268.35
  5146.8  267.38  5197.0  265.60  5234.1  267.26  5387.6  269.78  5764.4  273.19
#Mann=3,-1,0
  4274.4    0.05       0  4572.7    0.03       0  4578.7    0.05       0
Bank Sta=4572.7,4578.7
Exp/Cntr=0.3,0.1

Type RM Length L Ch R = 1,14703,274,274,274
BEGIN DESCRIPTION:
Mapping XS 73dd6f82
END DESCRIPTION:
XS GIS Cut Line= 4
      3644940.99     10190221.10      3644311.66     10190290.55
      3644077.29     10190427.27      3643988.31     10191034.90
#Sta/Elev= 30
  4262.4  271.97  4405.6  269.31  4422.3  268.37  4452.4  264.59  4582.3  258.93
  4643.6  262.97  4663.7  265.87  4714.0  266.25  4804.6  264.13  4864.9  266.33
  4875.0  266.05  4885.0  264.32  4892.8  260.50  4898.2  260.50  4904.2  258.40
  4925.7  257.63  5021.7  257.93  5064.7  263.30  5138.2  264.49  5150.7  264.14
  5160.6  259.04  5172.2  257.23  5198.6  257.20  5201.4  256.70  5204.6  257.20
  5242.1  264.88  5333.0  267.46  5535.1  268.65  5581.4  270.17  5781.0  272.39
#Mann=3,-1,0
  4262.4    0.05       0  5198.6    0.03       0  5204.6    0.05       0
Bank Sta=5198.6,5204.6
Exp/Cntr=0.3,0.1

Type RM Length L Ch R = 1,14429,1037,1037,1037
BEGIN DESCRIPTION:
TANYARD BRANCH 26.0
END DESCRIPTION:
XS GIS Cut Line= 3
      3644942.14     10189541.62      3644142.11     10190091.64
      3643337.26     10190601.66
#Sta/Elev= 30
  4041.7  278.09  4066.3  277.60  4264.3  272.78  4279.2  270.22  4300.2  270.83
  4308.7  268.11  4330.0  271.44  4350.9  272.11  4365.8  270.56  4840.7  263.11
  4876.6  262.22  4882.7  260.76  4897.6  261.94  4912.4  259.67  4918.5  256.58
  4927.3  256.17  4954.4  262.25  4986.2  257.25  4999.1  258.33  5009.5  261.44
  5041.4  262.36  5099.0  261.28  5153.6  255.95  5156.4  255.45  5159.6  255.95
  5166.0  258.89  5187.1  261.11  5296.5  265.08  5584.6  267.19  5965.4  274.67
#Mann=5,-1,0
  4041.7     0.1       0  4066.3    0.16       0  4986.2    0.05       0
  5153.6    0.03       0  5159.6    0.05       0
Bank Sta=5153.6,5159.6
Exp/Cntr=0.3,0.1

Type RM Length L Ch R = 1,13392,1402,1402,1402
BEGIN DESCRIPTION:
TANYARD BRANCH 24.0
END DESCRIPTION:
XS GIS Cut Line= 3
      3644742.11     10189241.64      3644320.11     10189373.51
      3642898.45     10189452.83
#Sta/Elev= 30
  4193.7  274.13  4602.1  263.28  4726.8  260.14  4794.1  257.97  4864.2  259.09
  4894.2  257.45  4914.3  254.83  4924.3  254.88  4934.3  256.88  4974.4  257.57
  4984.4  255.02  4991.4  251.56  4994.1  251.06  4997.4  251.56  5014.4  254.42
  5064.5  253.88  5084.5  256.23  5104.6  254.25  5119.4  256.72  5144.6  259.77
  5222.2  259.77  5344.9  263.27  5420.4  263.62  5518.7  265.36  5685.5  270.72
  5839.3  272.65  5895.8  272.06  5965.9  274.13  6018.8  273.75  6059.7  274.09
#Mann=11,-1,0
  4193.7     0.1       0  4602.1    0.16       0  4726.8    0.12       0
  4991.4    0.07       0  4997.4    0.12       0  5119.4    0.16       0
  5222.2    0.12       0  5420.4     0.1       0  5518.7    0.16       0
  5839.3     0.1       0  6018.8    0.16       0
Bank Sta=4991.4,4997.4
Exp/Cntr=0.3,0.1

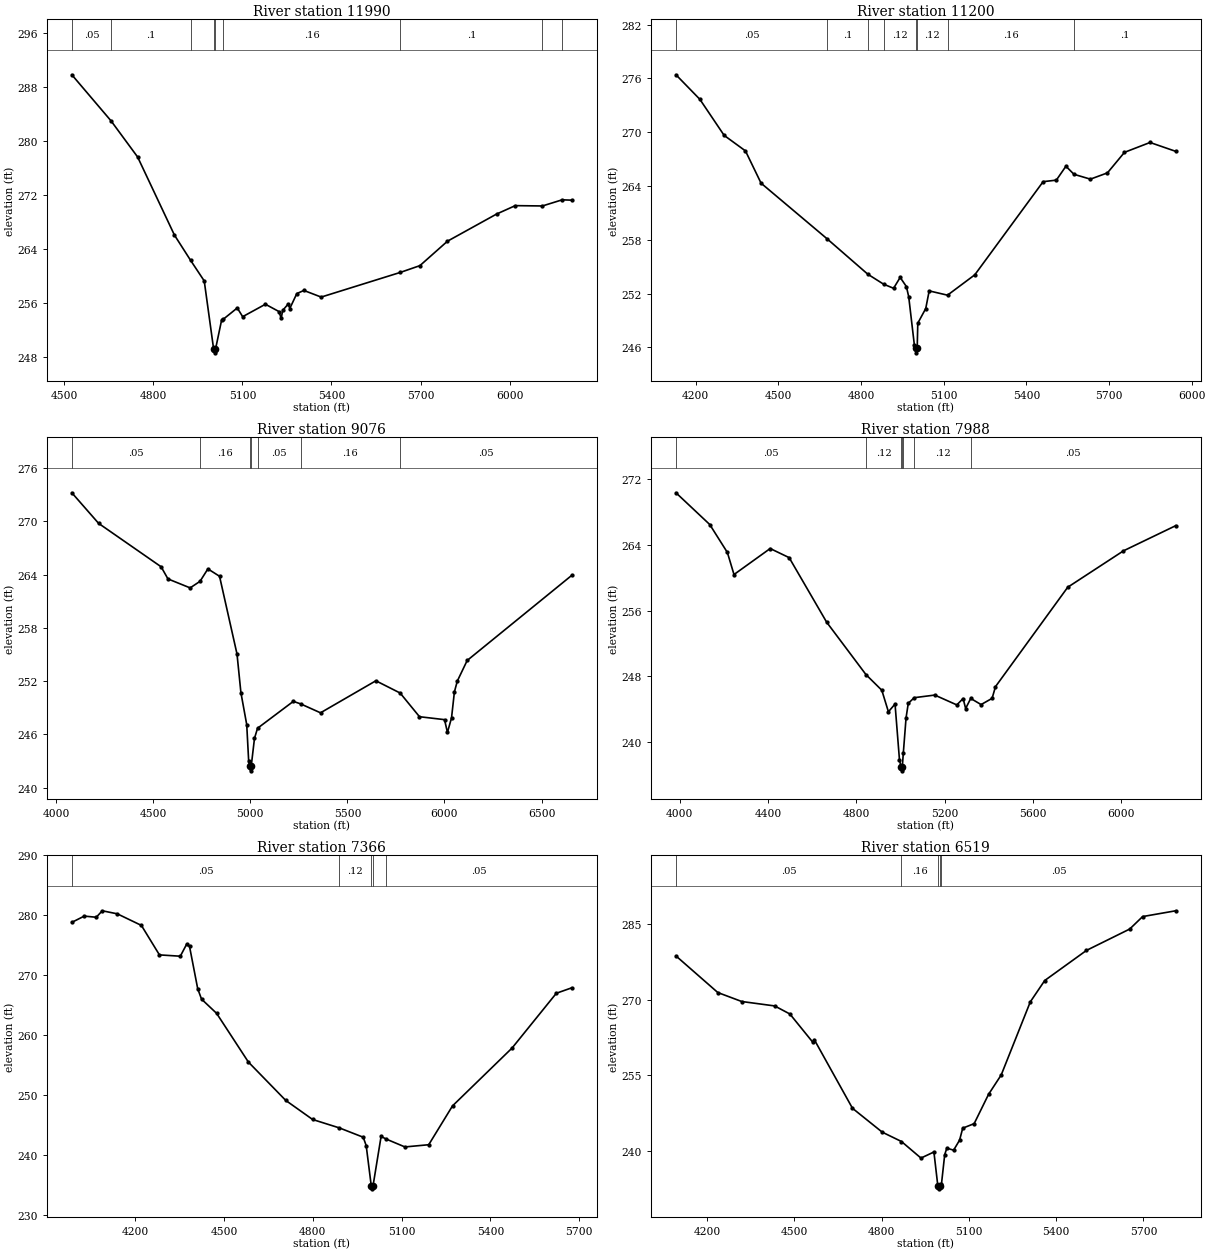
Type RM Length L Ch R = 1,11990,790,790,790
BEGIN DESCRIPTION:
TANYARD BRANCH 22.0
END DESCRIPTION:
XS GIS Cut Line= 3
      3644524.84     10188562.17      3643698.70     10188910.70
      3642937.08     10189104.33
#Sta/Elev= 30
  4525.9  289.77  4657.9  282.95  4747.3  277.61  4871.3  266.05  4925.6  262.32
  4971.6  259.27  5003.4  249.13  5006.2  248.63  5009.4  249.13  5029.9  253.44
  5034.8  253.57  5082.8  255.27  5101.0  253.98  5177.6  255.82  5223.5  254.73
  5230.5  253.72  5235.9  254.92  5254.2  255.85  5259.6  255.19  5283.3  257.40
  5307.1  257.86  5365.3  256.88  5631.7  260.53  5697.6  261.53  5790.5  265.15
  5955.6  269.16  6018.8  270.41  6110.0  270.36  6176.6  271.27  6208.4  271.22
#Mann=9,-1,0
  4525.9    0.05       0  4657.9     0.1       0  4925.6    0.12       0
  5003.4    0.07       0  5009.4    0.12       0  5034.8    0.16       0
  5631.7     0.1       0  6110.0    0.16       0  6176.6     0.1       0
Bank Sta=5003.4,5009.4
Exp/Cntr=0.3,0.1

Type RM Length L Ch R = 1,11200,2124,2124,2124
BEGIN DESCRIPTION:
TANYARD BRANCH 20.0
END DESCRIPTION:
XS GIS Cut Line= 3
      3644511.87     10188045.87      3643151.60     10188383.63
      3642751.59     10188483.63
#Sta/Elev= 30
  4128.4  276.41  4215.2  273.67  4303.3  269.65  4380.6  267.92  4437.3  264.32
  4676.4  258.13  4824.6  254.17  4881.8  253.06  4918.2  252.60  4942.1  253.81
  4964.7  252.79  4973.1  251.66  4993.7  246.25  4997.9  245.90  5000.7  245.40
  5003.9  245.90  5006.1  248.71  5034.9  250.34  5047.4  252.31  5113.9  251.83
  5212.9  254.10  5461.0  264.49  5508.9  264.66  5543.7  266.21  5573.0  265.31
  5632.5  264.77  5694.4  265.47  5756.2  267.76  5849.0  268.86  5942.3  267.87
#Mann=8,-1,0
  4128.4    0.05       0  4676.4     0.1       0  4824.6    0.05       0
  4881.8    0.12       0  4997.9    0.07       0  5003.9    0.12       0
  5113.9    0.16       0  5573.0     0.1       0
Bank Sta=4997.9,5003.9
Exp/Cntr=0.3,0.1

Type RM Length L Ch R = 1,9076,1088,1088,1088
BEGIN DESCRIPTION:
TANYARD BRANCH 18.0
END DESCRIPTION:
XS GIS Cut Line= 4
      3644640.97     10187697.34      3644137.57     10187310.11
      3643234.73     10187318.86      3642376.50     10186739.07
#Sta/Elev= 30
  4081.0  273.23  4219.0  269.78  4540.7  264.89  4576.0  263.52  4690.2  262.51
  4741.1  263.25  4781.6  264.65  4841.6  263.82  4931.6  255.05  4951.6  250.71
  4981.6  247.10  4991.6  242.99  4998.6  242.39  5001.3  241.89  5004.6  242.39
  5021.6  245.56  5037.3  246.69  5221.6  249.72  5258.8  249.44  5361.6  248.43
  5646.6  252.04  5771.6  250.66  5871.3  247.99  6000.2  247.66  6015.2  246.22
  6036.2  247.85  6051.1  250.79  6066.1  252.01  6116.9  254.33  6654.7  263.91
#Mann=7,-1,0
  4081.0    0.05       0  4741.1    0.16       0  4998.6    0.07       0
  5004.6    0.16       0  5037.3    0.05       0  5258.8    0.16       0
  5771.6    0.05       0
Bank Sta=4998.6,5004.6
Exp/Cntr=0.3,0.1

Type RM Length L Ch R = 1,7988,622,622,622
BEGIN DESCRIPTION:
TANYARD BRANCH 17.0
END DESCRIPTION:
XS GIS Cut Line= 3
      3644615.15     10186716.34      3643166.39     10186683.38
      3642356.73     10186574.41
#Sta/Elev= 30
  3982.4  270.38  4135.5  266.51  4215.5  263.10  4245.5  260.41  4409.6  263.58
  4495.6  262.47  4665.6  254.60  4844.1  248.20  4915.7  246.30  4945.7  243.67
  4975.7  244.62  4995.7  237.84  5002.7  236.97  5005.5  236.47  5008.7  236.97
  5013.1  238.59  5025.7  242.94  5035.7  244.70  5062.5  245.39  5155.8  245.71
  5255.8  244.51  5284.4  245.29  5295.8  244.07  5318.9  245.30  5365.8  244.55
  5415.8  245.31  5431.2  246.74  5758.7  258.86  6011.5  263.30  6248.5  266.37
#Mann=7,-1,0
  3982.4    0.05       0  4844.1    0.12       0  5002.7    0.07       0
  5008.7    0.12       0  5013.1    0.05       0  5062.5    0.12       0
  5318.9    0.05       0
Bank Sta=5002.7,5008.7
Exp/Cntr=0.3,0.1

Type RM Length L Ch R = 1,7366,847,847,847
BEGIN DESCRIPTION:
TANYARD BRANCH 15.0
END DESCRIPTION:
XS GIS Cut Line= 3
      3644463.32     10186272.21      3643728.87     10186140.29
      3642792.06     10186041.64
#Sta/Elev= 30
  3985.9  278.84  4027.8  279.88  4068.4  279.69  4088.7  280.77  4139.5  280.26
  4220.8  278.33  4281.8  273.41  4352.3  273.19  4373.2  275.15  4383.4  274.83
  4411.1  267.76  4424.0  266.03  4474.9  263.66  4582.3  255.53  4708.5  249.13
  4799.2  245.95  4889.9  244.54  4970.2  242.99  4980.2  241.59  4997.3  234.88
  5000.1  234.38  5003.3  234.88  5030.5  243.12  5048.4  242.67  5111.0  241.37
  5191.4  241.74  5271.8  248.22  5472.9  257.87  5622.5  267.01  5674.1  267.91
#Mann=5,-1,0
  3985.9    0.05       0  4889.9    0.12       0  4997.3    0.07       0
  5003.3    0.12       0  5048.4    0.05       0
Bank Sta=4997.3,5003.3
Exp/Cntr=0.3,0.1

Type RM Length L Ch R = 1,6519,717,717,717
BEGIN DESCRIPTION:
TANYARD BRANCH 13.0
END DESCRIPTION:
XS GIS Cut Line= 3
      3644511.91     10185786.96      3643892.25     10185638.38
      3642835.44     10185412.97
#Sta/Elev= 30
  4093.2  278.66  4237.0  271.39  4319.2  269.61  4432.4  268.73  4484.7  267.13
  4563.6  261.51  4568.7  262.03  4699.9  248.40  4802.1  243.66  4868.3  241.80
  4935.3  238.51  4979.8  239.72  4993.4  232.90  4996.2  232.40  4999.4  232.90
  5005.8  233.38  5016.9  239.20  5024.2  240.48  5047.5  240.08  5068.0  242.07
  5078.8  244.45  5118.1  245.35  5167.7  251.18  5211.1  255.02  5311.1  269.54
  5360.7  273.78  5504.2  279.76  5652.7  284.00  5697.2  286.48  5811.0  287.63
#Mann=5,-1,0
  4093.2    0.05       0  4868.3    0.16       0  4993.4    0.07       0
  4999.4    0.16       0  5005.8    0.05       0
Bank Sta=4993.4,4999.4
Exp/Cntr=0.3,0.1

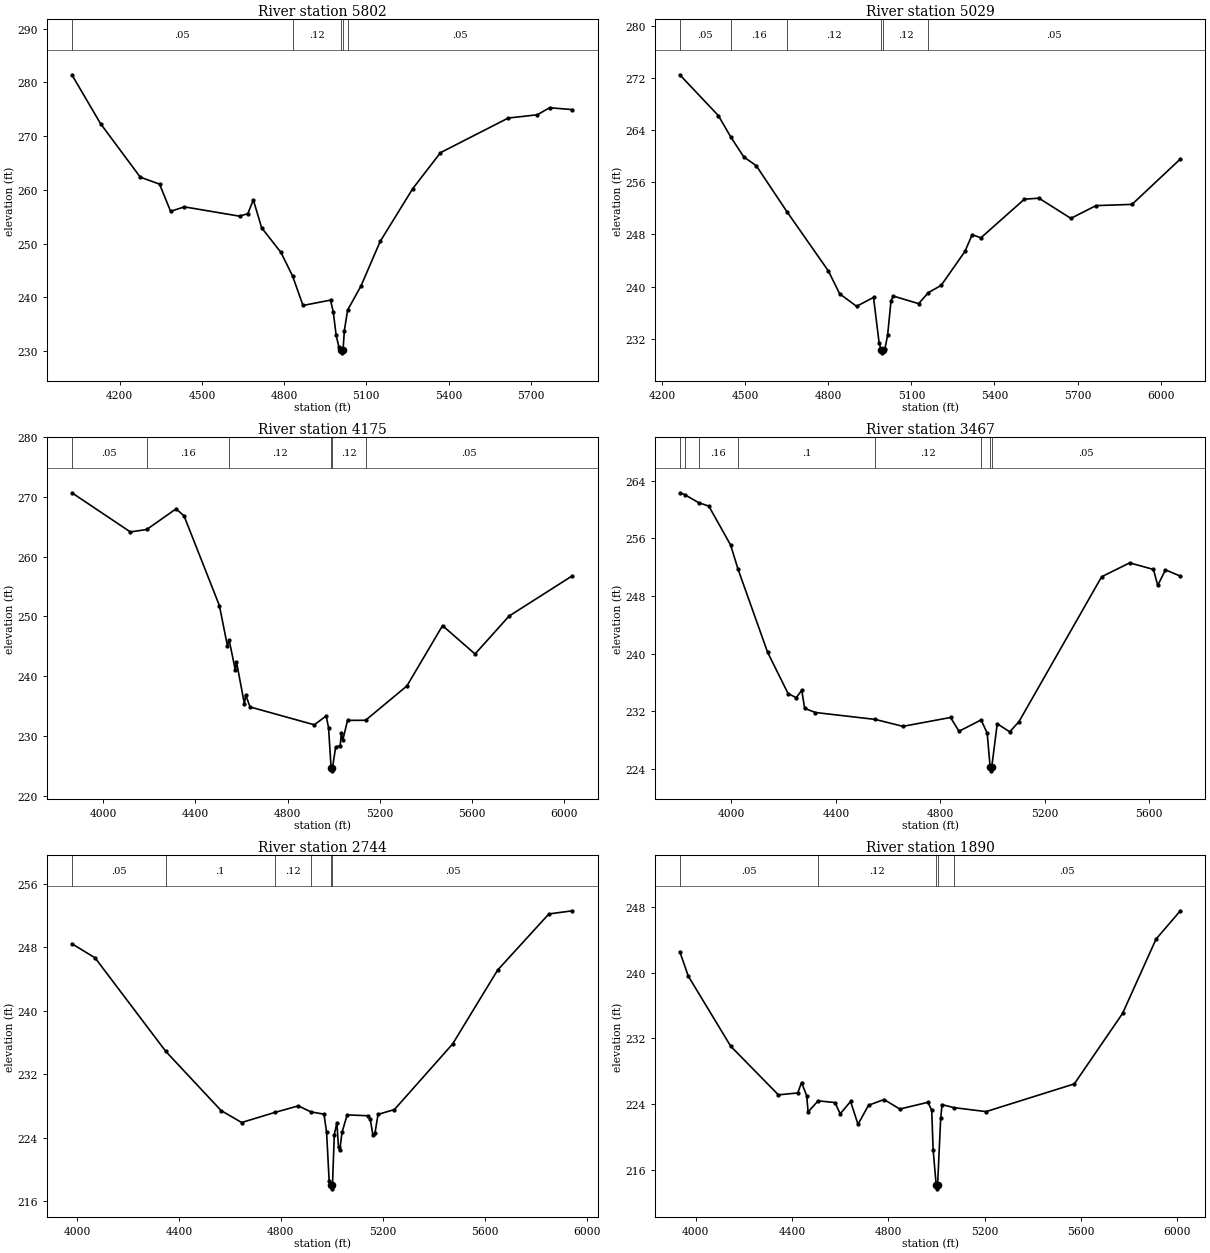
Type RM Length L Ch R = 1,5802,773,773,773
BEGIN DESCRIPTION:
TANYARD BRANCH 12.0
END DESCRIPTION:
XS GIS Cut Line= 3
      3644770.01     10185128.65      3643530.89     10184986.67
      3642962.98     10184870.50
#Sta/Elev= 30
  4025.5  281.40  4130.0  272.32  4275.0  262.36  4345.5  261.06  4385.7  256.01
  4436.1  256.83  4637.4  255.10  4667.6  255.57  4687.7  258.13  4717.9  252.95
  4788.4  248.36  4831.1  243.95  4868.9  238.49  4969.5  239.49  4979.6  237.21
  4989.7  233.03  4999.7  230.80  5009.1  230.18  5011.9  229.68  5015.1  230.18
  5019.9  233.82  5031.8  237.64  5080.3  242.09  5150.7  250.41  5269.6  260.23
  5370.6  266.91  5617.8  273.35  5723.8  273.96  5769.2  275.27  5852.4  274.92
#Mann=5,-1,0
  4025.5    0.05       0  4831.1    0.12       0  5009.1    0.07       0
  5015.1    0.12       0  5031.8    0.05       0
Bank Sta=5009.1,5015.1
Exp/Cntr=0.3,0.1

Type RM Length L Ch R = 1,5029,854,854,854
BEGIN DESCRIPTION:
TANYARD BRANCH 9.0
END DESCRIPTION:
XS GIS Cut Line= 3
      3644899.15     10184547.80      3643467.63     10184277.10
      3643117.62     10184277.10
#Sta/Elev= 30
  4264.1  272.55  4403.6  266.26  4448.6  262.95  4495.2  259.92  4540.2  258.57
  4650.6  251.52  4800.5  242.39  4841.2  238.88  4902.3  236.96  4963.3  238.33
  4983.7  231.31  4990.9  230.31  4993.6  229.81  4996.9  230.31  5004.0  230.33
  5014.2  232.51  5026.6  237.85  5034.6  238.54  5126.2  237.37  5161.2  239.06
  5207.6  240.18  5293.5  245.41  5319.5  247.98  5350.9  247.49  5508.0  253.43
  5560.4  253.58  5675.7  250.48  5766.5  252.44  5896.5  252.63  6071.0  259.61
#Mann=6,-1,0
  4264.1    0.05       0  4448.6    0.16       0  4650.6    0.12       0
  4990.9    0.07       0  4996.9    0.12       0  5161.2    0.05       0
Bank Sta=4990.9,4996.9
Exp/Cntr=0.3,0.1

Type RM Length L Ch R = 1,4175,708,708,708
BEGIN DESCRIPTION:
TANYARD BRANCH 8.0
END DESCRIPTION:
XS GIS Cut Line= 3
      3645157.33     10183824.95      3644357.00     10183605.51
      3643055.16     10183927.75
#Sta/Elev= 30
  3864.1  270.72  4117.8  264.16  4188.7  264.57  4316.0  268.03  4350.5  266.85
  4503.9  251.82  4538.4  245.13  4546.2  246.06  4572.8  241.04  4578.0  242.39
  4612.5  235.32  4617.7  236.88  4636.8  234.85  4915.3  231.86  4966.9  233.34
  4977.2  231.38  4988.3  224.65  4991.1  224.15  4994.3  224.65  5008.1  228.16
  5027.6  228.36  5032.7  230.42  5039.0  229.30  5059.6  232.60  5137.8  232.62
  5317.1  238.37  5471.6  248.47  5612.5  243.72  5760.1  250.07  6035.1  256.83
#Mann=6,-1,0
  3864.1    0.05       0  4188.7    0.16       0  4546.2    0.12       0
  4988.3    0.07       0  4994.3    0.12       0  5137.8    0.05       0
Bank Sta=4988.3,4994.3
Exp/Cntr=0.3,0.1

Type RM Length L Ch R = 1,3467,723,723,723
BEGIN DESCRIPTION:
TANYARD BRANCH 6.0
END DESCRIPTION:
XS GIS Cut Line= 3
      3644778.36     10183355.06      3643941.23     10183099.04
      3642976.50     10183489.07
#Sta/Elev= 30
  3802.7  262.32  3821.1  262.07  3875.4  260.94  3913.8  260.47  3997.4  255.06
  4025.1  251.78  4138.9  240.19  4217.1  234.48  4248.4  233.90  4269.4  234.94
  4280.5  232.43  4321.6  231.85  4551.0  230.89  4656.8  229.93  4839.0  231.16
  4871.3  229.25  4955.9  230.82  4979.2  229.00  4990.6  224.26  4993.4  223.76
  4996.6  224.26  5017.7  230.29  5065.5  229.17  5100.9  230.58  5417.4  250.68
  5524.7  252.60  5615.6  251.69  5632.0  249.48  5661.5  251.63  5718.7  250.76
#Mann=8,-1,0
  3802.7    0.05       0  3821.1     0.1       0  3875.4    0.16       0
  4025.1     0.1       0  4551.0    0.12       0  4955.9    0.05       0
  4990.6    0.03       0  4996.6    0.05       0
Bank Sta=4990.6,4996.6
Exp/Cntr=0.3,0.1

Type RM Length L Ch R = 1,2744,854,854,854
BEGIN DESCRIPTION:
TANYARD BRANCH 3.0
END DESCRIPTION:
XS GIS Cut Line= 3
      3644492.13     10182741.65      3642969.41     10182528.88
      3642569.42     10182678.88
#Sta/Elev= 30
  3979.8  248.44  4070.7  246.67  4348.1  234.90  4565.5  227.44  4646.2  225.94
  4776.5  227.21  4868.4  228.03  4918.6  227.27  4969.3  226.99  4979.4  224.72
  4989.5  218.60  4996.6  218.09  4999.4  217.59  5002.6  218.09  5009.7  224.40
  5019.8  225.90  5026.3  222.82  5031.3  222.46  5040.0  224.71  5060.2  226.90
  5141.0  226.79  5151.1  226.33  5161.2  224.34  5169.2  224.59  5181.4  226.96
  5245.7  227.57  5474.2  235.83  5650.6  245.12  5851.8  252.19  5944.5  252.59
#Mann=6,-1,0
  3979.8    0.05       0  4348.1     0.1       0  4776.5    0.12       0
  4918.6    0.05       0  4996.6    0.03       0  5002.6    0.05       0
Bank Sta=4996.6,5002.6
Exp/Cntr=0.3,0.1

Type RM Length L Ch R = 1,1890,476,476,476
BEGIN DESCRIPTION:
TANYARD BRANCH 2.0
END DESCRIPTION:
XS GIS Cut Line= 3
      3644342.15     10182491.67      3643204.02     10181831.00
      3642442.12     10181791.64
#Sta/Elev= 30
  3934.0  242.57  3969.2  239.59  4145.6  231.05  4343.5  225.14  4423.8  225.37
  4439.5  226.63  4461.0  225.03  4466.8  223.06  4508.3  224.41  4578.6  224.20
  4600.1  222.83  4643.2  224.33  4674.1  221.55  4717.7  223.87  4782.3  224.57
  4847.5  223.41  4964.4  224.23  4980.1  223.28  4986.3  218.37  4998.7  214.20
  5001.4  213.70  5004.7  214.20  5017.4  222.29  5023.2  223.95  5072.9  223.58
  5205.9  223.10  5572.3  226.47  5772.6  235.04  5911.9  244.10  6012.9  247.54
#Mann=5,-1,0
  3934.0    0.05       0  4508.3    0.12       0  4998.7    0.07       0
  5004.7    0.12       0  5072.9    0.05       0
Bank Sta=4998.7,5004.7
Exp/Cntr=0.3,0.1

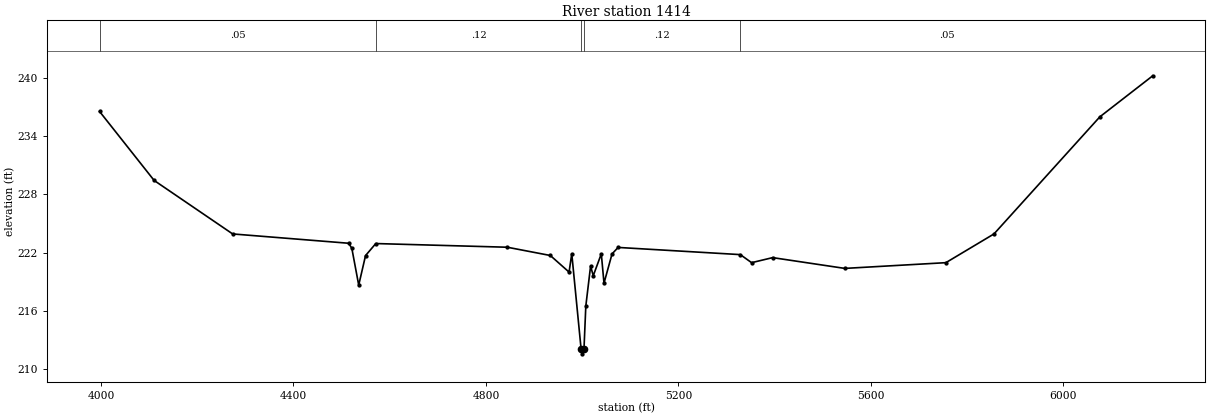
Type RM Length L Ch R = 1,1414,0,0,0
BEGIN DESCRIPTION:
TANYARD BRANCH 1.0
END DESCRIPTION:
XS GIS Cut Line= 4
      3644392.13     10182291.67      3643991.71     10181834.05
      3643311.46     10181491.64      3642492.09     10181491.64
#Sta/Elev= 30
  3997.0  236.54  4110.5  229.43  4273.7  223.92  4514.8  222.96  4521.4  222.44
  4535.7  218.65  4549.9  221.69  4571.2  222.93  4844.6  222.55  4933.9  221.70
  4972.9  219.99  4978.5  221.88  4997.9  212.07  5000.6  211.57  5003.9  212.07
  5007.7  216.49  5017.6  220.60  5023.2  219.62  5039.9  221.87  5045.5  218.85
  5062.2  221.86  5074.8  222.53  5328.8  221.79  5352.3  220.96  5396.0  221.48
  5546.0  220.37  5756.0  220.96  5856.0  223.92  6076.0  235.98  6186.0  240.21
#Mann=5,-1,0
  3997.0    0.05       0  4571.2    0.12       0  4997.9    0.07       0
  5003.9    0.12       0  5328.8    0.05       0
Bank Sta=4997.9,5003.9
Exp/Cntr=0.3,0.1

Chan Stop Cuts=-1