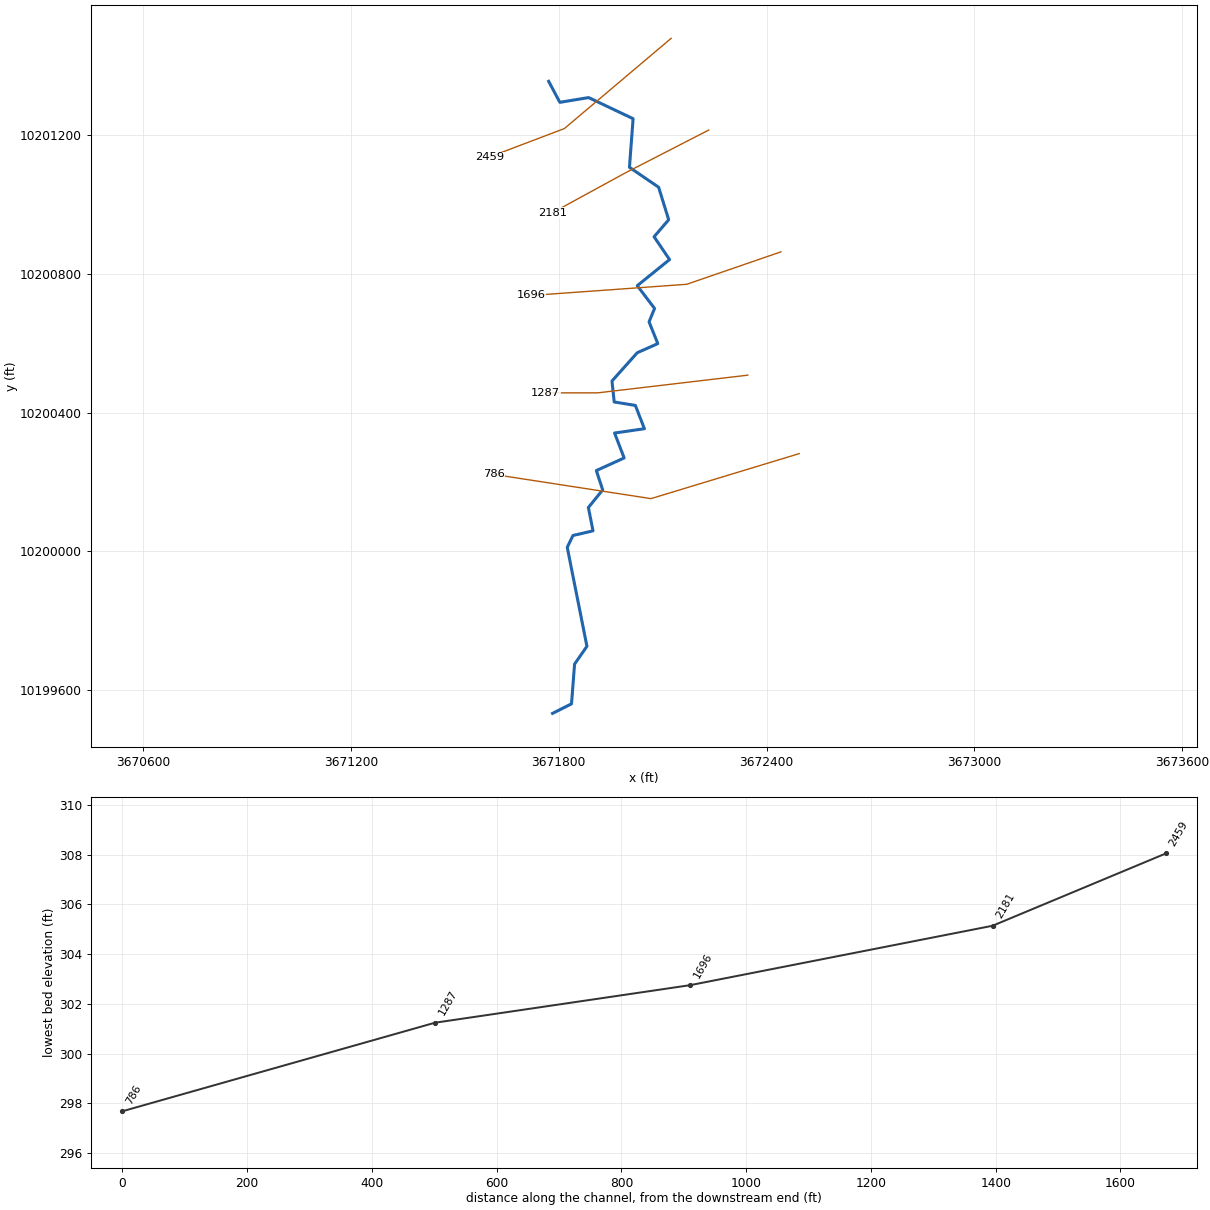
--- UNT002 IN ROCK.prj (project) ---

Proj Title=UNT002 IN ROCK Base Level Engineering
Current Plan=p01
Default Exp/Contr=0.3,0.1
English Units
Geom File=g01
Flow File=f01
Plan File=p01
BEGIN DESCRIPTION:
UNT002 IN ROCK
END DESCRIPTION:

--- UNT002 IN ROCK.p01 (plan) ---

Plan Title=Multiple Run
Short Identifier=Multiple
Geom File=g01
Flow File=f01
Subcritical Flow
K Sum by GR= 0
Std Step Tol= 0.01
Critical Tol= 0.01
Num of Std Step Trials= 20
Max Error Tol= 0.3
Flow Tol Ratio= 0.001
Split Flow NTrial= 30
Split Flow Tol= 0.02
Split Flow Ratio= 0.02
Log Output Level= 0
Friction Slope Method= 1
Unsteady Friction Slope Method= 2
Unsteady Bridges Friction Slope Method= 1
Parabolic Critical Depth
Global Vel Dist=  1 , 1 , 1
Global Log Level= 0
CheckData=True
Encroach Param= -1, 0, 0, 0
BEGIN DESCRIPTION:
Multiple Run
END DESCRIPTION:

--- UNT002 IN ROCK.f01 (steady flow) ---

Flow Title=Multiple
Number of Profiles=7
Profile Names=10-year,25-year,50-year,1pct_min,100-year,1pct_plu,500-year
River Rch & RM= UNT002 IN ROCK,Reach-1,2459
     349     450     529     457     618     836     841
Boundary for River Rch & Prof#=UNT002 IN ROCK,Reach-1,1
Up Type=0
Dn Type=3
Dn Slope=0.005
Boundary for River Rch & Prof#=UNT002 IN ROCK,Reach-1,2
Up Type=0
Dn Type=3
Dn Slope=0.005
Boundary for River Rch & Prof#=UNT002 IN ROCK,Reach-1,3
Up Type=0
Dn Type=3
Dn Slope=0.005
Boundary for River Rch & Prof#=UNT002 IN ROCK,Reach-1,4
Up Type=0
Dn Type=3
Dn Slope=0.005
Boundary for River Rch & Prof#=UNT002 IN ROCK,Reach-1,5
Up Type=0
Dn Type=3
Dn Slope=0.005
Boundary for River Rch & Prof#=UNT002 IN ROCK,Reach-1,6
Up Type=0
Dn Type=3
Dn Slope=0.005
Boundary for River Rch & Prof#=UNT002 IN ROCK,Reach-1,7
Up Type=0
Dn Type=3
Dn Slope=0.005

--- UNT002 IN ROCK.g01 (geometry) ---

Geom Title=Existing Conditions

River Reach=UNT002 IN ROCK,Reach-1
Reach XY= 30
      3671770.87     10201356.05      3671803.05     10201295.39
      3671886.11     10201309.10      3672014.57     10201248.16
      3672004.03     10201107.79      3672088.27     10201050.32
      3672117.24     10200956.56      3672075.17     10200907.31
      3672119.79     10200841.50      3672026.61     10200766.17
      3672076.48     10200700.52      3672060.62     10200661.67
      3672085.91     10200598.96      3672026.52     10200572.60
      3671953.60     10200490.94      3671960.05     10200430.46
      3672021.09     10200420.58      3672047.22     10200353.27
      3671961.07     10200340.87      3671988.75     10200268.90
      3671908.46     10200232.51      3671926.90     10200176.78
      3671885.42     10200125.86      3671898.87     10200058.48
      3671841.03     10200045.07      3671824.47     10200010.98
      3671881.34     10199725.23      3671845.64     10199673.90
      3671836.78     10199559.14      3671782.11     10199531.64

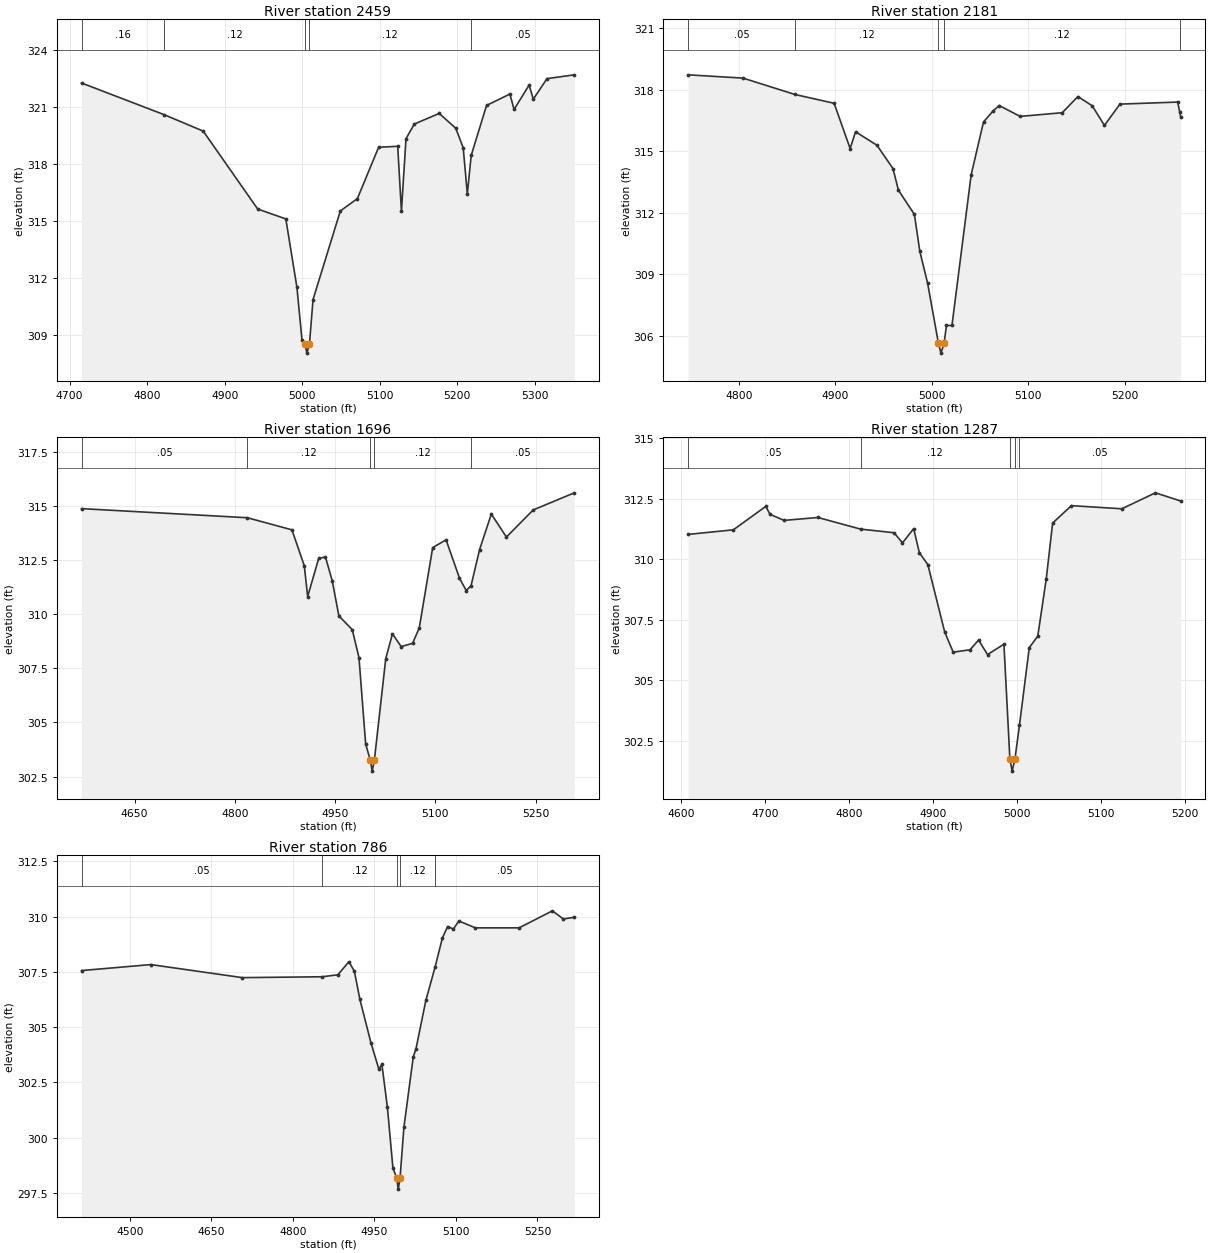
Type RM Length L Ch R = 1,2459,278,278,278
BEGIN DESCRIPTION:
UNT002 IN ROCK 5.0
END DESCRIPTION:
XS GIS Cut Line= 3
      3672124.36     10201480.11      3671816.19     10201219.68
      3671599.21     10201137.23
#Sta/Elev= 30
  4715.4  322.26  4822.2  320.59  4872.3  319.73  4942.6  315.63  4978.9  315.11
  4993.2  311.51  4999.7  308.76  5003.4  308.55  5006.1  308.05  5009.4  308.55
  5014.0  310.87  5049.2  315.53  5071.2  316.18  5098.6  318.88  5123.2  318.93
  5128.0  315.52  5133.9  319.33  5144.6  320.10  5176.7  320.66  5198.1  319.88
  5207.7  318.85  5213.0  316.42  5218.0  318.45  5237.8  321.08  5267.9  321.68
  5273.3  320.87  5292.7  322.15  5298.1  321.41  5315.8  322.49  5351.0  322.69
#Mann=5,-1,0
  4715.4    0.16       0  4822.2    0.12       0  5003.4    0.07       0
  5009.4    0.12       0  5218.0    0.05       0
Bank Sta=5003.4,5009.4
Exp/Cntr=0.3,0.1

Type RM Length L Ch R = 1,2181,485,485,485
BEGIN DESCRIPTION:
UNT002 IN ROCK 4.0
END DESCRIPTION:
XS GIS Cut Line= 3
      3672232.83     10201215.33      3671992.11     10201091.64
      3671781.50     10200976.64
#Sta/Elev= 30
  4747.4  318.73  4804.4  318.57  4858.2  317.77  4898.8  317.34  4915.4  315.13
  4921.0  315.95  4943.2  315.29  4959.8  314.15  4965.4  313.10  4982.0  311.91
  4987.6  310.11  4995.6  308.57  5006.8  305.64  5009.5  305.14  5012.8  305.64
  5015.2  306.49  5020.9  306.49  5040.8  313.85  5053.6  316.43  5063.6  316.97
  5069.8  317.23  5091.6  316.70  5135.2  316.88  5151.4  317.67  5166.2  317.22
  5178.9  316.26  5195.0  317.30  5254.8  317.40  5256.9  316.92  5258.0  316.67
#Mann=5,-1,0
  4747.4    0.05       0  4858.2    0.12       0  5006.8    0.07       0
  5012.8    0.12       0  5256.9    0.05       0
Bank Sta=5006.8,5012.8
Exp/Cntr=0.3,0.1

Type RM Length L Ch R = 1,1696,409,409,409
BEGIN DESCRIPTION:
UNT002 IN ROCK 3.0
END DESCRIPTION:
XS GIS Cut Line= 3
      3672441.20     10200863.79      3672169.42     10200770.18
      3671720.73     10200737.91
#Sta/Elev= 30
  4570.6  314.87  4818.7  314.45  4885.4  313.89  4903.9  312.23  4908.9  310.81
  4925.5  312.58  4935.6  312.63  4945.6  311.55  4955.6  309.92  4975.7  309.28
  4985.7  307.99  4995.7  304.00  5002.7  303.25  5005.5  302.75  5008.7  303.25
  5025.8  307.95  5035.8  309.09  5048.8  308.50  5065.9  308.65  5075.9  309.36
  5096.0  313.07  5116.0  313.43  5136.1  311.66  5146.1  311.09  5153.3  311.30
  5166.2  312.98  5183.7  314.62  5206.3  313.56  5246.4  314.81  5307.9  315.60
#Mann=5,-1,0
  4570.6    0.05       0  4818.7    0.12       0  5002.7    0.07       0
  5008.7    0.12       0  5153.3    0.05       0
Bank Sta=5002.7,5008.7
Exp/Cntr=0.3,0.1

Type RM Length L Ch R = 1,1287,501,501,501
BEGIN DESCRIPTION:
UNT002 IN ROCK 2.0
END DESCRIPTION:
XS GIS Cut Line= 3
      3672345.73     10200507.88      3671911.90     10200456.75
      3671761.93     10200456.75
#Sta/Elev= 30
  4608.6  311.03  4662.6  311.22  4701.2  312.19  4706.3  311.86  4723.0  311.61
  4763.3  311.73  4814.0  311.25  4853.9  311.10  4864.0  310.68  4877.3  311.27
  4884.1  310.27  4894.2  309.78  4914.3  306.99  4924.4  306.16  4944.5  306.26
  4954.6  306.66  4965.3  306.06  4984.8  306.49  4991.9  301.74  4994.6  301.24
  4997.9  301.74  5003.3  303.14  5015.0  306.35  5025.1  306.82  5035.2  309.19
  5042.8  311.50  5065.2  312.22  5125.2  312.09  5165.2  312.75  5195.4  312.41
#Mann=5,-1,0
  4608.6    0.05       0  4814.0    0.12       0  4991.9    0.07       0
  4997.9    0.12       0  5003.3    0.05       0
Bank Sta=4991.9,4997.9
Exp/Cntr=0.3,0.1

Type RM Length L Ch R = 1,786,0,0,0
BEGIN DESCRIPTION:
UNT002 IN ROCK 1.0
END DESCRIPTION:
XS GIS Cut Line= 3
      3672494.11     10200281.42      3672066.20     10200151.52
      3671612.25     10200221.41
#Sta/Elev= 30
  4411.4  307.56  4538.9  307.83  4707.3  307.24  4854.6  307.28  4883.0  307.37
  4903.2  307.96  4913.3  307.53  4923.4  306.26  4943.7  304.30  4958.4  303.10
  4963.9  303.32  4974.0  301.39  4984.2  298.63  4991.3  298.18  4994.0  297.68
  4997.3  298.18  5004.4  300.47  5021.6  303.65  5026.7  304.03  5044.9  306.22
  5061.9  307.73  5075.2  309.03  5084.8  309.55  5095.4  309.44  5105.6  309.80
  5135.9  309.49  5216.3  309.49  5277.6  310.26  5297.8  309.89  5317.9  309.97
#Mann=5,-1,0
  4411.4    0.05       0  4854.6    0.12       0  4991.3    0.07       0
  4997.3    0.12       0  5061.9    0.05       0
Bank Sta=4991.3,4997.3
Exp/Cntr=0.3,0.1

Chan Stop Cuts=-1