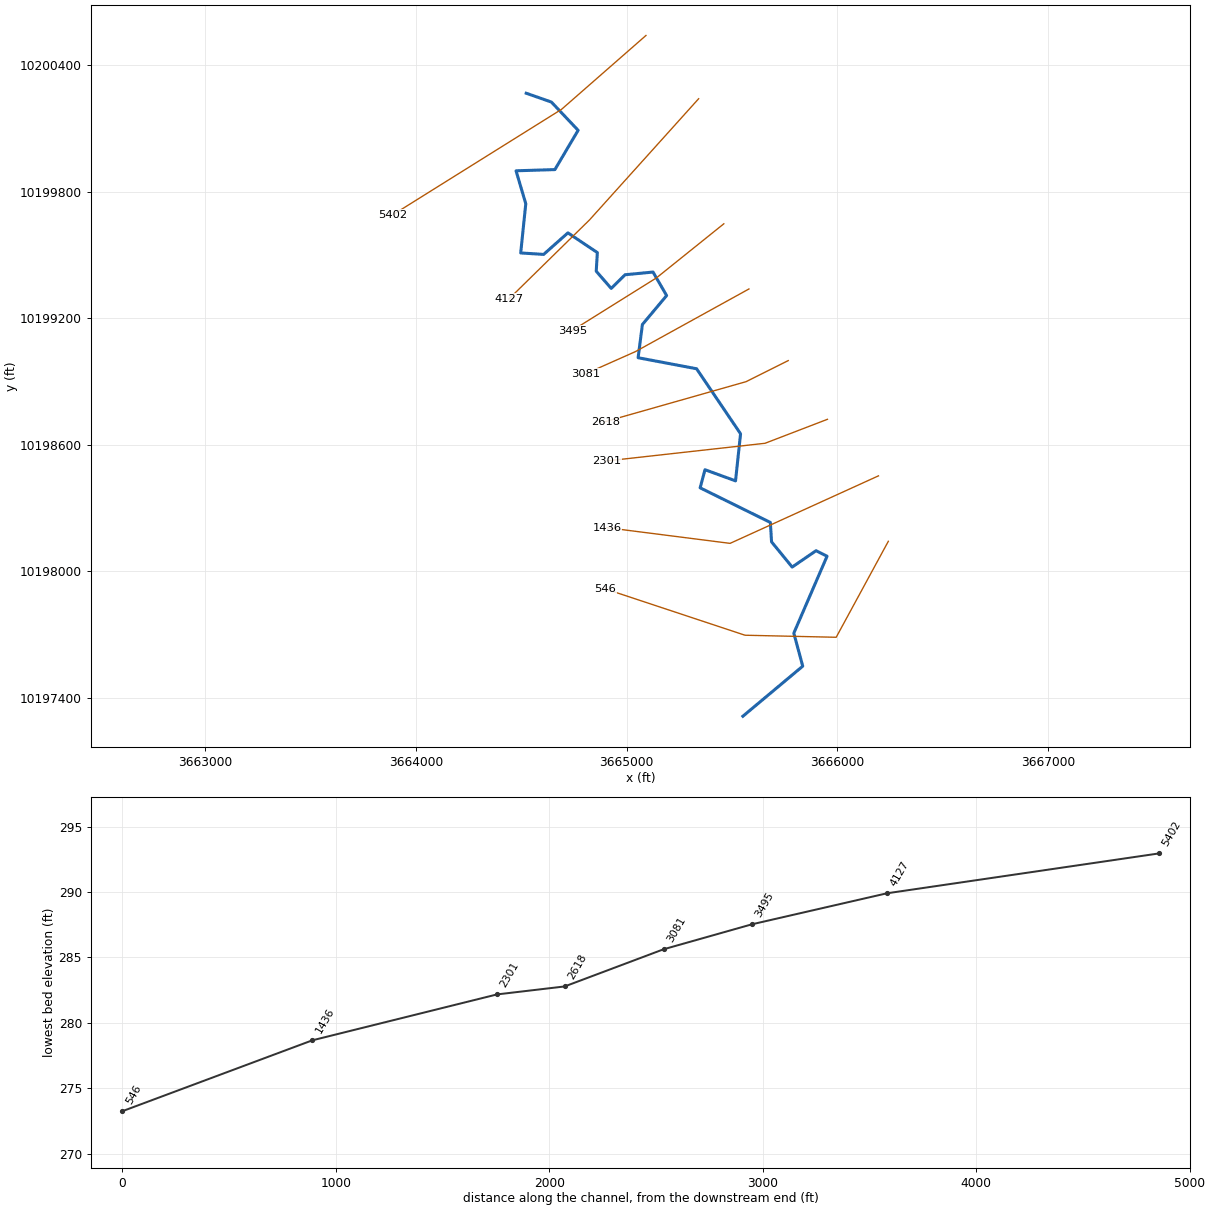
--- UNT003 IN ROCK.prj (project) ---

Proj Title=UNT003 IN ROCK Base Level Engineering
Current Plan=p01
Default Exp/Contr=0.3,0.1
English Units
Geom File=g01
Flow File=f01
Plan File=p01
Y Axis Title=Elevation
X Axis Title(PF)=Main Channel Distance
X Axis Title(XS)=Station
BEGIN DESCRIPTION:
UNT003 IN ROCK
END DESCRIPTION:
DSS Export Rating Curves= 0
DSS Export Rating Curve Sorted= 0
DSS Export Volume Flow Curves= 0
DXF OffsetX= 0
DXF OffsetY= 0
DXF ScaleX= 1
DXF ScaleY= 10

--- UNT003 IN ROCK.p01 (plan) ---

Plan Title=Multiple Run
Short Identifier=Multiple
Geom File=g01
Flow File=f01
Subcritical Flow
K Sum by GR= 0
Std Step Tol= 0.01
Critical Tol= 0.01
Num of Std Step Trials= 20
Max Error Tol= 0.3
Flow Tol Ratio= 0.001
Split Flow NTrial= 30
Split Flow Tol= 0.02
Split Flow Ratio= 0.02
Log Output Level= 0
Friction Slope Method= 1
Unsteady Friction Slope Method= 2
Unsteady Bridges Friction Slope Method= 1
Parabolic Critical Depth
Global Vel Dist=  1 , 1 , 1
Global Log Level= 0
CheckData=True
Encroach Param= -1, 0, 0, 0
BEGIN DESCRIPTION:
Multiple Run
END DESCRIPTION:

--- UNT003 IN ROCK.f01 (steady flow) ---

Flow Title=Multiple
Number of Profiles=7
Profile Names=10-year,25-year,50-year,1pct_min,100-year,1pct_plu,500-year
River Rch & RM= UNT003 IN ROCK,Reach-1,5402
     879    1199    1462    1306    1766    2389    2575
Boundary for River Rch & Prof#=UNT003 IN ROCK,Reach-1,1
Up Type=0
Dn Type=3
Dn Slope=0.005
Boundary for River Rch & Prof#=UNT003 IN ROCK,Reach-1,2
Up Type=0
Dn Type=3
Dn Slope=0.005
Boundary for River Rch & Prof#=UNT003 IN ROCK,Reach-1,3
Up Type=0
Dn Type=3
Dn Slope=0.005
Boundary for River Rch & Prof#=UNT003 IN ROCK,Reach-1,4
Up Type=0
Dn Type=3
Dn Slope=0.005
Boundary for River Rch & Prof#=UNT003 IN ROCK,Reach-1,5
Up Type=0
Dn Type=3
Dn Slope=0.005
Boundary for River Rch & Prof#=UNT003 IN ROCK,Reach-1,6
Up Type=0
Dn Type=3
Dn Slope=0.005
Boundary for River Rch & Prof#=UNT003 IN ROCK,Reach-1,7
Up Type=0
Dn Type=3
Dn Slope=0.005

--- UNT003 IN ROCK.g01 (geometry) ---

Geom Title=Existing Conditions
Program Version=4.10

River Reach=UNT003 IN ROCK  ,Reach-1
Reach XY= 30
      3664523.78     10200267.75      3664643.37     10200225.89
      3664770.28     10200091.79      3664660.01     10199905.35
       3664475.7     10199899.67      3664521.88     10199743.33
      3664497.83     10199509.89      3664606.52     10199502.86
      3664721.84     10199605.13      3664861.47      10199511.6
      3664856.17     10199423.02      3664927.23     10199341.53
      3664993.08      10199406.4       3665125.7     10199419.14
      3665190.22     10199307.57      3665075.26     10199170.33
      3665054.93     10199012.67      3665332.37     10198960.34
      3665541.02      10198651.8      3665517.13     10198428.41
      3665372.25     10198481.28       3665349.2     10198395.36
      3665682.41     10198231.07      3665688.07     10198139.04
      3665785.83     10198019.37      3665899.24     10198097.02
      3665951.35     10198070.76       3665793.7     10197705.92
      3665836.02     10197549.15      3665552.11     10197311.64

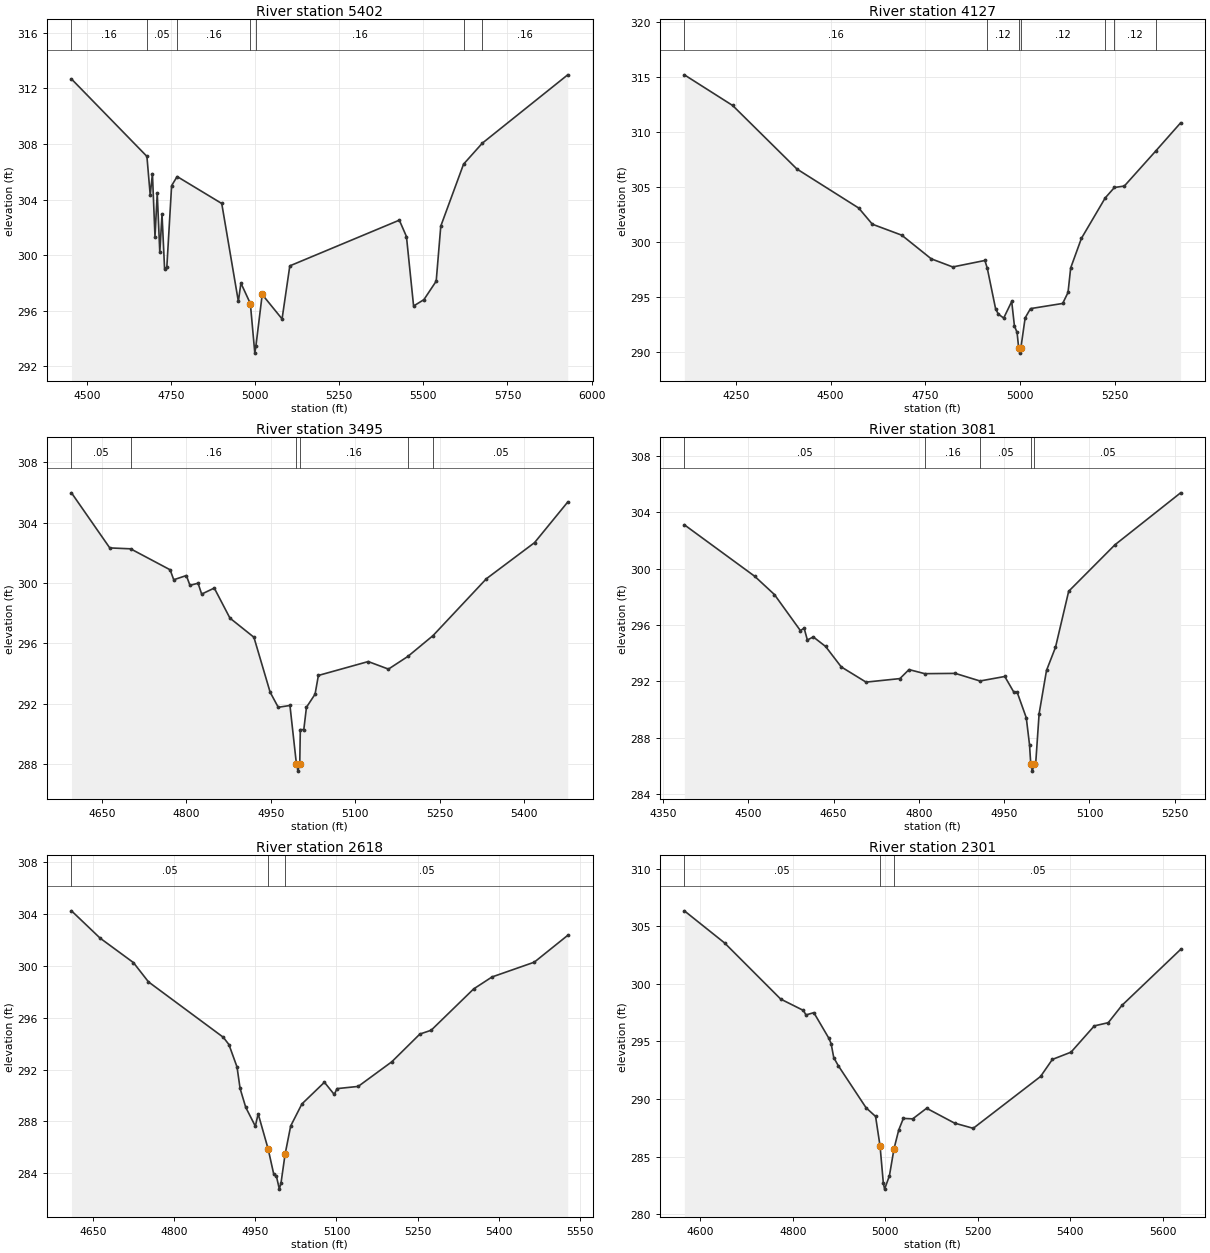
Type RM Length L Ch R = 1 ,5402    ,1275,1275,1275
BEGIN DESCRIPTION:
UNT003 IN ROCK 10.0
END DESCRIPTION:
XS GIS Cut Line= 3
      3665092.14     10200541.67      3664692.11     10200191.64
      3663892.15     10199691.67
#Sta/Elev= 30
  4454.1  312.68  4678.3  307.11  4688.1  304.33  4694.7  305.87  4702.3  301.34
    4709  304.45  4716.6  300.21  4723.2  302.93  4730.8  299.03  4737.5  299.14
  4751.7     305  4768.1  305.66  4900.7  303.72  4950.1  296.67  4957.7  297.99
  4985.7  296.52    4999  292.95  5002.2  293.45    5021  297.17    5080  295.41
    5103  299.23  5428.5  302.52  5449.7  301.34  5470.9  296.34  5501.6   296.8
  5538.1  298.13  5551.7  302.09  5619.4  306.55  5675.1  308.06    5929  312.98
#Mann= 7 ,-1 , 0
  4454.1     .16       0  4678.3     .05       0  4768.1     .16       0
  4985.7     .07       0  5002.2     .16       0  5619.4     .05       0
  5675.1     .16       0
Bank Sta=4985.7,5021
XS Rating Curve= 0 ,0
Exp/Cntr=0.3,0.1

Type RM Length L Ch R = 1 ,4127    ,632,632,632
BEGIN DESCRIPTION:
UNT003 IN ROCK 9.0
END DESCRIPTION:
XS GIS Cut Line= 3
      3665342.07     10200241.61       3664824.5     10199666.76
      3664442.09     10199291.63
#Sta/Elev= 30
  4114.4  315.22  4241.8  312.43  4411.4  306.65  4574.4   303.1  4610.3  301.63
    4688  300.63  4765.7  298.48  4822.5  297.74  4907.3  298.33  4913.6  297.62
  4935.6  293.92  4942.8  293.45  4956.9  293.09    4978   294.6  4985.2  292.37
  4992.2  291.78  4996.3   290.4  4999.1   289.9  5002.3   290.4  5013.5  293.11
  5027.6  293.95  5112.5  294.42  5126.6  295.42  5133.6  297.65  5161.9  300.34
  5224.7  304.02    5249  304.97  5275.1   305.1  5357.5  308.27  5423.6  310.85
#Mann= 7 ,-1 , 0
  4114.4     .16       0  4913.6     .12       0  4996.3     .07       0
  5002.3     .12       0  5224.7     .05       0    5249     .12       0
  5357.5     .05       0
Bank Sta=4996.3,5002.3
XS Rating Curve= 0 ,0
Exp/Cntr=0.3,0.1

Type RM Length L Ch R = 1 ,3495    ,414,414,414
BEGIN DESCRIPTION:
UNT003 IN ROCK 7.0
END DESCRIPTION:
XS GIS Cut Line= 3
      3665461.53     10199648.11      3665142.11     10199391.64
      3664742.14     10199141.66
#Sta/Elev= 30
  4596.3  305.97  4664.3  302.32  4701.3  302.26  4771.5  300.87  4777.9  300.21
  4800.3  300.49  4806.7  299.84  4821.1  299.98  4827.5  299.26  4849.9  299.66
  4877.7  297.67  4920.3   296.4  4949.1  292.76  4963.5  291.76  4984.3  291.88
  4995.7  288.03  4998.5  287.53  5001.7  288.03  5002.7  290.28  5008.9  290.28
  5013.6  291.76  5028.9  292.63  5034.8  293.87  5123.3  294.79  5159.2  294.29
  5193.7  295.13  5238.4  296.51  5333.2  300.28  5418.7  302.67  5477.6  305.36
#Mann= 6 ,-1 , 0
  4596.3     .05       0  4701.3     .16       0  4995.7     .07       0
  5001.7     .16       0  5193.7     .12       0  5238.4     .05       0
Bank Sta=4995.7,5001.7
XS Rating Curve= 0 ,0
Exp/Cntr=0.3,0.1

Type RM Length L Ch R = 1 ,3081    ,463,463,463
BEGIN DESCRIPTION:
UNT003 IN ROCK 6.0
END DESCRIPTION:
XS GIS Cut Line= 3
      3665580.77     10199338.92      3665042.11     10199041.64
       3664806.6     10198936.89
#Sta/Elev= 30
  4387.3  303.11  4510.9  299.46  4545.7  298.16  4591.4   295.6    4598  295.77
  4603.7  294.93  4614.1  295.15  4635.8  294.47  4663.3  293.02  4706.9  291.94
  4766.5  292.19  4782.5  292.83  4810.2  292.54  4863.9  292.56  4907.4  292.02
    4951  292.34    4967  291.22  4972.7  291.23  4988.8  289.41  4994.5   287.5
  4996.7  286.12  4999.4  285.62  5002.7  286.12  5005.3  286.12  5011.4   289.7
  5024.4  292.77  5040.2  294.41  5063.4  298.39  5144.8  301.69  5260.3  305.38
#Mann= 5 ,-1 , 0
  4387.3     .05       0  4810.2     .16       0  4907.4     .05       0
  4996.7     .03       0  5002.7     .05       0
Bank Sta=4996.7,5002.7
XS Rating Curve= 0 ,0
Exp/Cntr=0.3,0.1

Type RM Length L Ch R = 1 ,2618    ,317,317,317
BEGIN DESCRIPTION:
UNT003 IN ROCK 5.0
END DESCRIPTION:
XS GIS Cut Line= 3
      3665767.18     10198999.08       3665567.2     10198899.09
      3664899.01     10198709.31
#Sta/Elev= 30
  4609.7  304.24  4662.8  302.13  4724.3  300.25  4752.2  298.76  4890.6  294.49
    4901  293.93    4916   292.2  4921.7  290.54  4932.1  289.09  4949.9  287.63
  4955.1  288.59  4973.7  285.86  4983.8  283.96    4989  283.76  4994.3  282.78
  4997.5  283.28  5004.9  285.46  5015.3  287.65  5036.1  289.35  5077.7  291.02
  5095.9  290.08  5101.1  290.53  5140.2   290.7  5202.4   292.6  5254.4  294.74
  5275.2  295.03  5353.9  298.22  5387.8  299.14    5466  300.28  5527.9  302.35
#Mann= 3 , 0 , 0
  4609.7     .05       0  4973.7    .035       0  5004.9     .05       0
Bank Sta=4973.7,5004.9
XS Rating Curve= 0 ,0
Exp/Cntr=0.3,0.1

Type RM Length L Ch R = 1 ,2301    ,865,865,865
BEGIN DESCRIPTION:
UNT003 IN ROCK 4.0
END DESCRIPTION:
XS GIS Cut Line= 3
       3665953.3     10198720.48      3665657.23     10198606.77
      3664906.73     10198523.07
#Sta/Elev= 30
  4565.9  306.33  4652.9  303.54    4774  298.67  4823.3  297.68  4828.6  297.29
  4845.7  297.49  4877.8  295.29    4883  294.81  4888.7  293.59  4898.3   292.9
  4958.6  289.23  4979.1  288.48  4988.8   285.9  4995.9  282.67  4998.6  282.17
    5009  283.33    5019  285.69  5029.1   287.3  5039.1  288.31  5059.3  288.27
  5089.4  289.19  5149.8   287.9  5190.1  287.45  5335.6  291.95  5361.1  293.43
  5401.4  294.06  5451.7  296.34  5481.9  296.62  5511.4  298.12  5638.2  302.98
#Mann= 3 , 0 , 0
  4565.9     .05       0  4988.8    .035       0    5019     .05       0
Bank Sta=4988.8,5019
XS Rating Curve= 0 ,0
Exp/Cntr=0.3,0.1

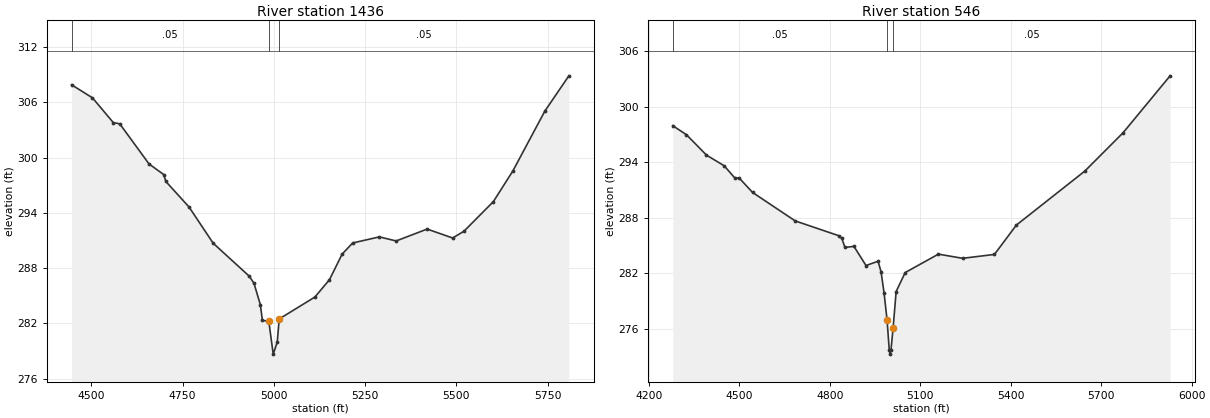
Type RM Length L Ch R = 1 ,1436    ,890,890,890
BEGIN DESCRIPTION:
UNT003 IN ROCK 3.0
END DESCRIPTION:
XS GIS Cut Line= 3
      3666195.44     10198452.23      3665491.36     10198131.86
      3664906.82     10198206.32
#Sta/Elev= 30
  4445.7  307.91  4503.1  306.49  4560.2   303.8  4577.8  303.67  4658.1  299.31
  4698.6  298.15  4704.1  297.41  4767.8  294.63  4833.9   290.7  4932.8  287.12
  4945.7  286.35  4963.2  284.01  4968.7  282.33  4986.3  282.22  4998.4  278.66
  5009.4  279.96  5014.8  282.48  5112.6  284.86  5152.5  286.74  5187.2  289.52
  5216.1  290.73  5289.1  291.39  5335.3  290.95  5420.2  292.24  5490.1  291.27
  5520.9     292  5601.6  295.22  5654.9  298.54  5742.7  305.05  5808.5  308.88
#Mann= 3 , 0 , 0
  4445.7     .05       0  4986.3    .035       0  5014.8     .05       0
Bank Sta=4986.3,5014.8
XS Rating Curve= 0 ,0
Exp/Cntr=0.3,0.1

Type RM Length L Ch R = 1 ,546     ,0,0,0
BEGIN DESCRIPTION:
UNT003 IN ROCK 1.0
END DESCRIPTION:
XS GIS Cut Line= 4
       3666242.1     10198141.63      3665994.79     10197686.26
      3665562.15     10197695.98      3664898.97     10197915.79
#Sta/Elev= 30
  4278.9  297.94  4324.4  296.96  4390.6  294.76  4449.6   293.6  4483.7  292.32
  4499.8  292.26  4543.6  290.72  4685.2  287.64  4829.8  286.04  4839.8  285.75
  4849.8  284.78  4879.8  284.89  4919.8  282.82  4959.8  283.28  4969.8  282.14
  4979.8  279.84  4989.8  276.91  4996.8  273.74  4999.6  273.24  5002.8  273.74
  5009.8   276.1  5019.8  280.01  5049.8  282.06  5159.9  284.05  5240.4   283.6
  5345.8  284.02  5418.5  287.19  5645.6  293.03  5772.4  297.17  5928.5  303.33
#Mann= 3 , 0 , 0
  4278.9     .05       0  4989.8    .035       0  5009.8     .05       0
Bank Sta=4989.8,5009.8
XS Rating Curve= 0 ,0
Exp/Cntr=0.3,0.1

Chan Stop Cuts=-1
Use User Specified Reach Order=0
Composite Channel Slope=5