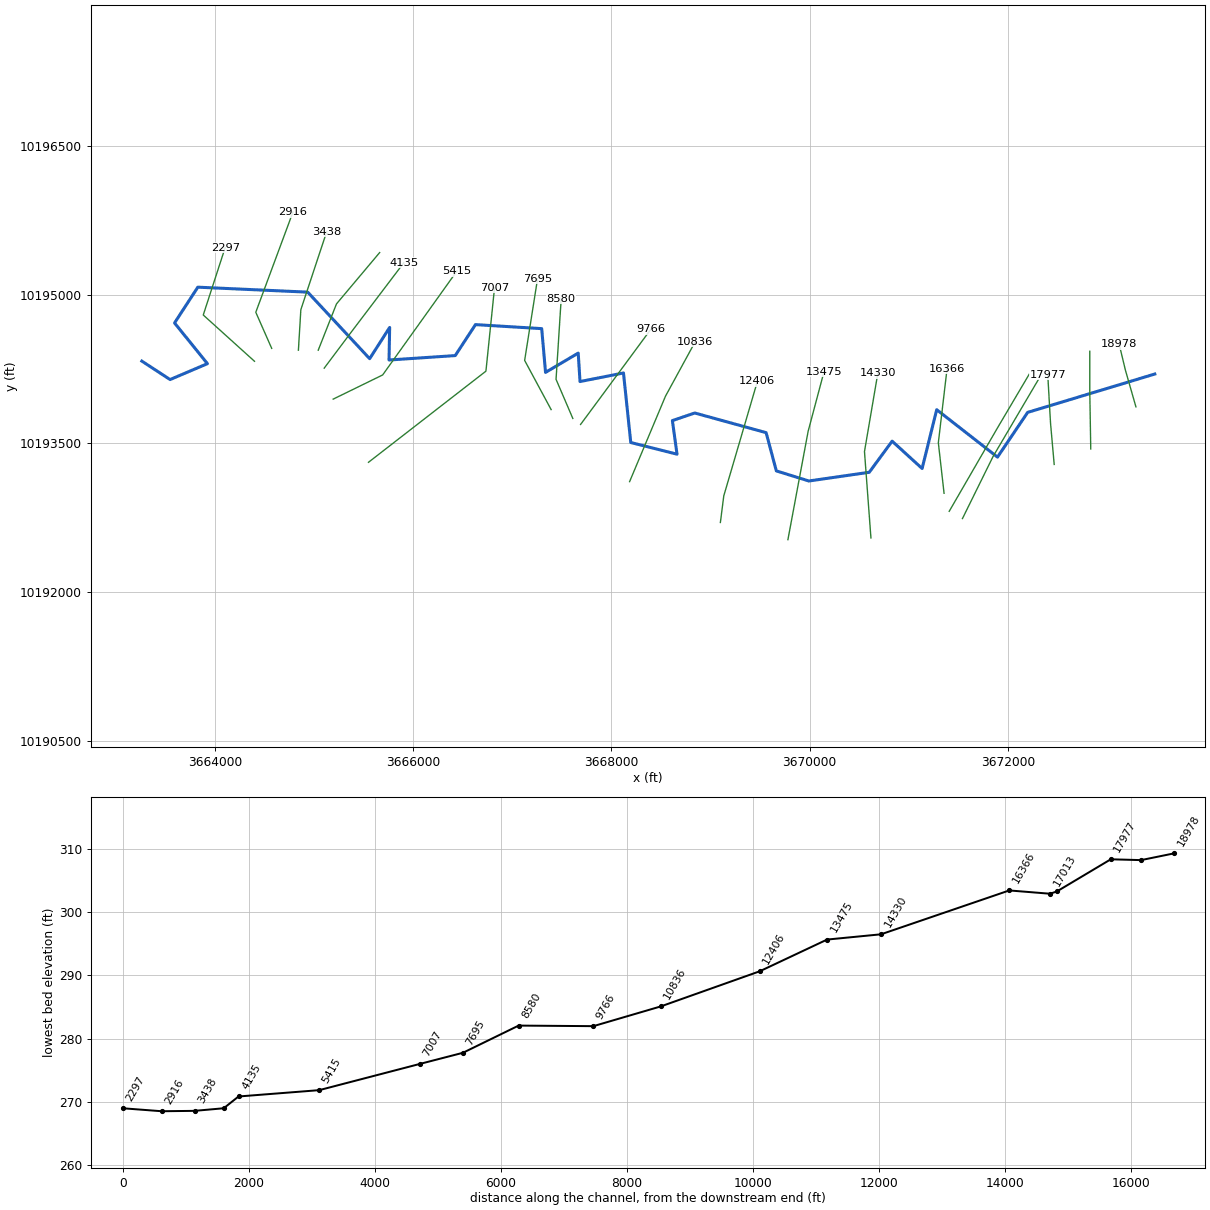
--- UNT004 IN ROCK.prj (project) ---

Proj Title=UNT004 IN ROCK Base Level Engineering
Current Plan=p01
Default Exp/Contr=0.3,0.1
English Units
Geom File=g01
Flow File=f01
Plan File=p01
Y Axis Title=Elevation
X Axis Title(PF)=Main Channel Distance
X Axis Title(XS)=Station
BEGIN DESCRIPTION:
UNT004 IN ROCK
END DESCRIPTION:
DSS Export Rating Curves= 0
DSS Export Rating Curve Sorted= 0
DSS Export Volume Flow Curves= 0
DXF OffsetX= 0
DXF OffsetY= 0
DXF ScaleX= 1
DXF ScaleY= 10

--- UNT004 IN ROCK.p01 (plan) ---

Plan Title=Multiple Run
Short Identifier=Multiple
Geom File=g01
Flow File=f01
Subcritical Flow
K Sum by GR= 0
Std Step Tol= 0.01
Critical Tol= 0.01
Num of Std Step Trials= 20
Max Error Tol= 0.3
Flow Tol Ratio= 0.001
Split Flow NTrial= 30
Split Flow Tol= 0.02
Split Flow Ratio= 0.02
Log Output Level= 0
Friction Slope Method= 1
Unsteady Friction Slope Method= 2
Unsteady Bridges Friction Slope Method= 1
Parabolic Critical Depth
Global Vel Dist=  1 , 1 , 1
Global Log Level= 0
CheckData=True
Encroach Param= -1, 0, 0, 0
BEGIN DESCRIPTION:
Multiple Run
END DESCRIPTION:

--- UNT004 IN ROCK.f01 (steady flow) ---

Flow Title=Multiple
Program Version=4.10
Number of Profiles= 7
Profile Names=10-year,25-year,50-year,1pct_min,100-year,1pct_plu,500-year
River Rch & RM=UNT004 IN ROCK,Reach-1         ,18978
    1207    1667    2052    1845    2495    3375    3693
River Rch & RM=UNT004 IN ROCK,Reach-1         ,7007
    2049    2913    3655    3347    4527    6122    6947
River Rch & RM=UNT004 IN ROCK,Reach-1         ,5415
    2049    2913    3655    3347    4527    6122    6947
Boundary for River Rch & Prof#=UNT004 IN ROCK,Reach-1         , 1
Up Type= 0
Dn Type= 3
Dn Slope=0.01
Boundary for River Rch & Prof#=UNT004 IN ROCK,Reach-1         , 2
Up Type= 0
Dn Type= 3
Dn Slope=0.01
Boundary for River Rch & Prof#=UNT004 IN ROCK,Reach-1         , 3
Up Type= 0
Dn Type= 3
Dn Slope=0.01
Boundary for River Rch & Prof#=UNT004 IN ROCK,Reach-1         , 4
Up Type= 0
Dn Type= 3
Dn Slope=0.01
Boundary for River Rch & Prof#=UNT004 IN ROCK,Reach-1         , 5
Up Type= 0
Dn Type= 3
Dn Slope=0.01
Boundary for River Rch & Prof#=UNT004 IN ROCK,Reach-1         , 6
Up Type= 0
Dn Type= 3
Dn Slope=0.01
Boundary for River Rch & Prof#=UNT004 IN ROCK,Reach-1         , 7
Up Type= 0
Dn Type= 3
Dn Slope=0.01
DSS Import GetInterval= 0
DSS Import GetPeak= 0
DSS Import FillOption= 0

--- UNT004 IN ROCK.g01 (geometry) ---

Geom Title=Existing Conditions
Program Version=4.10

River Reach=UNT004 IN ROCK  ,Reach-1
Reach XY= 30
      3673482.42     10194200.91      3672199.97     10193813.67
      3671895.46     10193362.24      3671282.29     10193840.85
      3671135.11     10193247.19      3670832.56     10193523.21
      3670601.66     10193208.97      3669991.97     10193120.99
      3669664.17     10193223.15      3669561.06     10193609.17
      3668841.24     10193807.56      3668615.36     10193730.84
      3668662.11     10193391.64      3668195.41     10193509.69
      3668121.87     10194211.62      3667683.51     10194124.98
       3667665.1     10194412.17      3667335.54     10194217.41
      3667296.76     10194659.36      3666628.73     10194699.92
      3666424.46     10194387.28      3665756.47     10194342.53
      3665762.72     10194671.13      3665560.98     10194355.93
      3664935.98     10195027.81       3663827.3      10195077.9
      3663592.31     10194716.72      3663924.23     10194305.75
      3663547.31     10194145.16      3663262.11     10194331.64

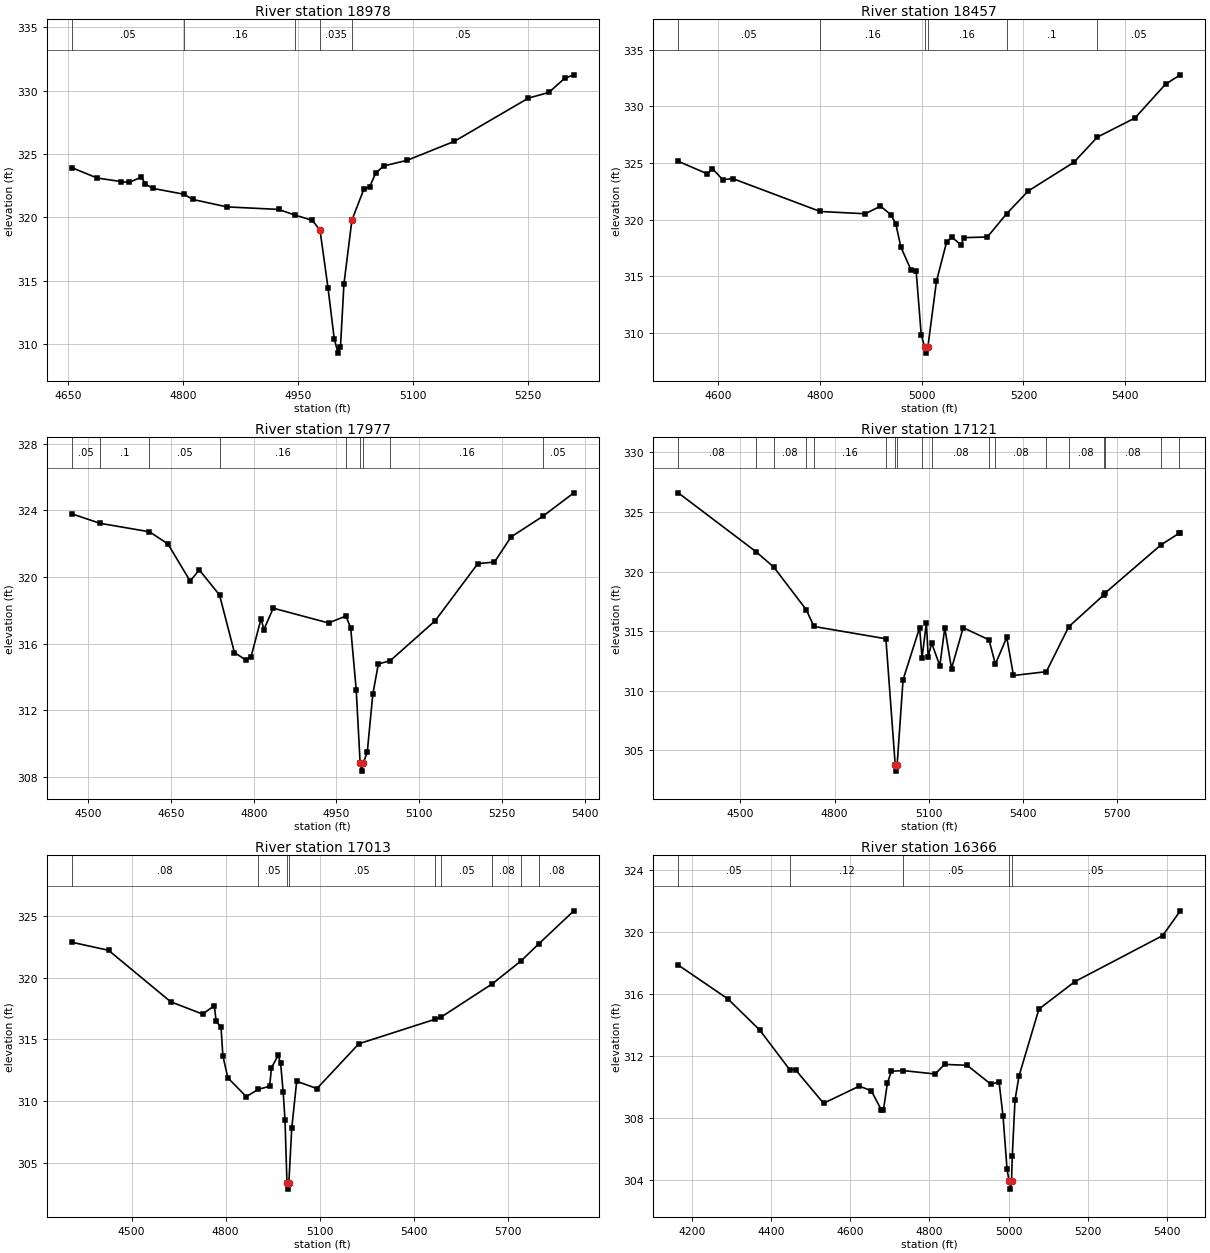
Type RM Length L Ch R = 1 ,18978   ,521,521,521
BEGIN DESCRIPTION:
UNT004 IN ROCK 21.0
END DESCRIPTION:
XS GIS Cut Line= 3
      3673292.24     10193869.73      3673185.86     10194241.47
      3673122.98     10194503.36
#Sta/Elev= 30
  4654.3  323.92  4687.5   323.1  4718.7  322.82  4729.1  322.75  4745.2  323.17
  4750.4  322.63  4760.3  322.28  4800.8  321.82  4812.3  321.41  4856.9  320.82
  4924.5  320.62    4946  320.17  4968.6  319.76  4978.7  318.96  4989.1  314.42
  4997.2  310.42  5002.2  309.27  5005.4  309.77  5009.9  314.72  5020.3  319.77
  5036.2  322.26  5043.6  322.41  5051.4  323.49  5061.7  324.05  5092.6   324.5
  5154.3     326  5250.9  329.41  5277.7  329.86  5298.2  330.97  5310.3  331.25
#Mann= 5 ,-1 , 0
  4654.3     .05       0  4800.8     .16       0    4946     .05       0
  4978.7    .035       0  5020.3     .05       0
Bank Sta=4978.7,5020.3
XS Rating Curve= 0 ,0
Exp/Cntr=0.3,0.1

Type RM Length L Ch R = 1 ,18457   ,480,480,480
BEGIN DESCRIPTION:
UNT004 IN ROCK 19.0
END DESCRIPTION:
XS GIS Cut Line= 3
      3672836.52     10193444.33      3672826.65      10194030.7
      3672826.65     10194430.75
#Sta/Elev= 30
  4521.8  325.14  4579.1  324.03  4589.1  324.49  4609.1  323.52  4629.1  323.61
  4800.7  320.71  4889.2  320.51  4919.2  321.18  4939.2  320.44  4949.2  319.64
  4959.2  317.57  4979.2  315.55  4989.2  315.49  4999.2  309.84  5006.2  308.71
  5008.9  308.21  5012.2  308.71  5029.2  314.56  5049.2  318.03  5059.2  318.44
  5077.8  317.76  5082.8   318.4  5129.2  318.46    5167  320.51  5209.2  322.51
  5299.2  325.05  5345.2  327.27  5419.2  328.96  5479.2  331.94  5508.3  332.77
#Mann= 6 ,-1 , 0
  4521.8     .05       0  4800.7     .16       0  5006.2     .07       0
  5012.2     .16       0    5167      .1       0  5345.2     .05       0
Bank Sta=5006.2,5012.2
XS Rating Curve= 0 ,0
Exp/Cntr=0.3,0.1

Type RM Length L Ch R = 1 ,17977   ,856,856,856
BEGIN DESCRIPTION:
UNT004 IN ROCK 18.0
END DESCRIPTION:
XS GIS Cut Line= 3
      3672467.59     10193288.08      3672430.92     10193702.82
      3672402.49     10194195.24
#Sta/Elev= 30
  4470.4   323.8  4521.3  323.23  4611.1  322.72  4644.6  321.99  4684.8  319.76
  4701.4  320.43  4738.1  318.92  4765.1  315.46  4785.2  315.03  4795.2  315.21
  4813.4   317.5  4818.4  316.84  4835.4  318.13  4935.7  317.24  4967.1  317.66
  4975.7  316.94  4985.7  313.24  4992.8  308.84  4995.5  308.34  4998.8  308.84
  5005.8   309.5  5015.8  312.96  5025.8  314.78  5047.2  314.97  5128.7  317.37
  5206.1  320.81  5236.2   320.9  5266.2  322.41  5323.4  323.64    5380  325.06
#Mann= 9 ,-1 , 0
  4470.4     .05       0  4521.3      .1       0  4611.1     .05       0
  4738.1     .16       0  4967.1     .12       0  4992.8     .07       0
  4998.8     .12       0  5047.2     .16       0  5323.4     .05       0
Bank Sta=4992.8,4998.8
XS Rating Curve= 0 ,0
Exp/Cntr=0.3,0.1

Type RM Length L Ch R = 1 ,17121   ,108,108,108
BEGIN DESCRIPTION:
UNT004 IN ROCK 17.0
END DESCRIPTION:
XS GIS Cut Line= 3
      3671542.13     10192741.69      3671850.28     10193367.42
      3672307.01     10194143.15
#Sta/Elev= 30
  4302.5   326.6  4550.1  321.66  4606.5  320.37  4709.5  316.81  4734.6  315.39
  4963.3  314.36    4993  303.76  4995.7  303.26    4999  303.76  5017.9  310.92
  5070.6  315.29  5078.3  312.76  5092.1  315.69  5097.9  312.87    5109  313.99
    5135   312.1  5150.7  315.27  5172.1  311.86  5209.3  315.29  5291.4  314.27
  5311.7  312.23  5347.9  314.48  5369.3  311.28  5473.9   311.6  5545.2  315.37
  5656.4  318.03  5661.9  318.22  5838.9  322.24  5895.3  323.19  5900.2   323.2
#Mann= 18 ,-1 , 0
  4302.5     .08       0  4550.1     .05       0  4606.5     .08       0
  4709.5     .05       0  4734.6     .16       0  4963.3     .08       0
    4993     .07       0    4999     .08       0  5078.3     .05       0
    5109     .08       0  5291.4     .05       0  5311.7     .08       0
  5473.9     .12       0  5545.2     .08       0  5656.4     .16       0
  5661.9     .08       0  5838.9     .16       0  5895.3     .08       0
Bank Sta=4993,4999
XS Rating Curve= 0 ,0
Exp/Cntr=0.3,0.1

Type RM Length L Ch R = 1 ,17013   ,647,647,647
BEGIN DESCRIPTION:
UNT004 IN ROCK 16.0
END DESCRIPTION:
XS GIS Cut Line= 3
      3671408.57     10192815.02      3671890.33     10193648.35
      3672214.98     10194198.08
#Sta/Elev= 30
  4309.4  322.86  4426.6  322.21  4624.7  318.05  4726.6  317.05  4763.9  317.73
  4769.7  316.49  4785.4  315.98  4791.2  313.69    4807   311.9  4865.8  310.38
  4903.6  310.96  4940.4  311.22  4946.2  312.72  4967.7  313.71  4975.5  313.06
  4983.5  310.73  4989.3  308.51  4995.6   303.4  4998.3   302.9  5001.6   303.4
  5010.8  307.81  5026.6  311.62  5091.2  311.03  5224.7  314.65  5468.8  316.64
  5485.5  316.78  5650.9  319.51    5742  321.35  5798.9  322.74  5910.4   325.4
#Mann= 9 ,-1 , 0
  4309.4     .08       0  4903.6     .05       0  4995.6     .04       0
  5001.6     .05       0  5468.8     .08       0  5485.5     .05       0
  5650.9     .08       0    5742     .05       0  5798.9     .08       0
Bank Sta=4995.6,5001.6
XS Rating Curve= 0 ,0
Exp/Cntr=0.3,0.1

Type RM Length L Ch R = 1 ,16366   ,2036,2036,2036
BEGIN DESCRIPTION:
UNT004 IN ROCK 15.0
END DESCRIPTION:
XS GIS Cut Line= 3
      3671356.48      10192997.3      3671298.75     10193507.27
      3671386.86     10194255.97
#Sta/Elev= 30
  4166.1  317.88  4291.2   315.7  4371.7  313.69  4447.4  311.13  4462.3  311.12
  4532.8  308.96  4623.3  310.07  4653.5  309.76    4679  308.52    4684  308.52
  4693.8  310.24  4703.9  311.03  4733.6  311.07  4814.6  310.85  4838.1  311.47
  4895.2  311.41  4955.6  310.18  4975.7  310.35  4985.8  308.13  4995.9  304.71
  5001.2  303.92    5004  303.42  5007.2  303.92  5009.2  305.59    5016  309.16
  5026.1  310.72  5076.4  315.04    5167  316.81  5388.6  319.78  5433.2  321.38
#Mann= 5 ,-1 , 0
  4166.1     .05       0  4447.4     .12       0  4733.6     .05       0
  5001.2    .035       0  5007.2     .05       0
Bank Sta=5001.2,5007.2
XS Rating Curve= 0 ,0
Exp/Cntr=0.3,0.1

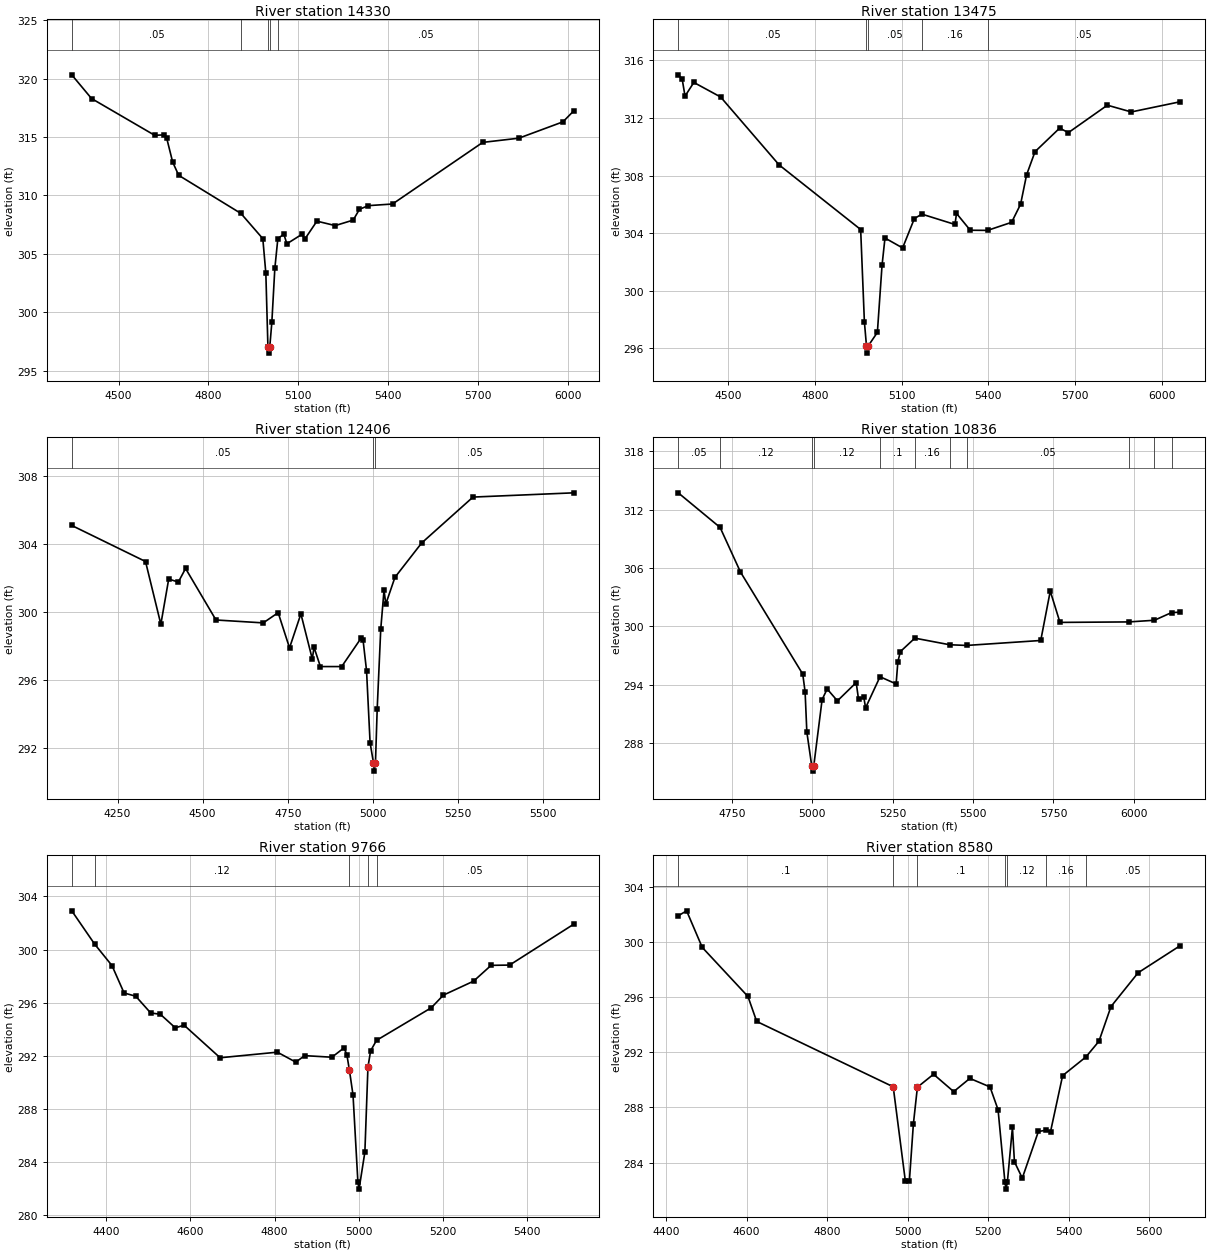
Type RM Length L Ch R = 1 ,14330   ,855,855,855
BEGIN DESCRIPTION:
UNT004 IN ROCK 14.0
END DESCRIPTION:
XS GIS Cut Line= 3
      3670618.64     10192545.88      3670553.53     10193418.31
      3670687.95     10194207.49
#Sta/Elev= 30
  4343.9  320.34  4409.8  318.31  4620.4  315.16  4650.5  315.19  4660.5  314.93
  4680.6  312.86  4700.7  311.73  4908.4  308.46  4981.4   306.3  4991.5  303.34
  4998.5  296.99  5001.2  296.49  5004.5  296.99  5011.5  299.12  5021.5  303.75
  5031.6  306.31  5051.6  306.68  5061.7  305.86  5111.8  306.67  5121.8  306.27
  5161.9   307.8    5223  307.42    5283  307.89    5304  308.82  5333.7  309.13
  5414.3  309.27  5715.3  314.55  5835.7  314.91  5982.9  316.31  6019.3  317.26
#Mann= 5 ,-1 , 0
  4343.9     .05       0  4908.4     .12       0  4998.5     .07       0
  5004.5     .12       0  5031.6     .05       0
Bank Sta=4998.5,5004.5
XS Rating Curve= 0 ,0
Exp/Cntr=0.3,0.1

Type RM Length L Ch R = 1 ,13475   ,1069,1069,1069
BEGIN DESCRIPTION:
UNT004 IN ROCK 13.0
END DESCRIPTION:
XS GIS Cut Line= 3
      3669780.96     10192528.56      3669984.95      10193622.3
      3670145.54     10194225.59
#Sta/Elev= 30
  4327.6     315  4340.9  314.74  4351.1  313.52  4381.6  314.47  4474.2  313.46
  4676.6  308.74  4958.7  304.25  4971.6  297.83  4978.8  296.16  4981.5  295.66
  4984.8  296.16  5016.5   297.1  5032.6  301.75  5042.8  303.66  5103.8  302.97
  5144.5  305.01  5170.3  305.32  5285.1   304.6  5290.2  305.37  5337.8   304.2
  5397.8  304.19  5480.9  304.75    5512  306.01  5532.7  308.05  5561.9  309.66
  5647.3   311.3  5677.1  310.98  5812.1  312.89  5894.8  312.42  6064.5  313.13
#Mann= 5 ,-1 , 0
  4327.6     .05       0  4978.8     .07       0  4984.8     .05       0
  5170.3     .16       0  5397.8     .05       0
Bank Sta=4978.8,4984.8
XS Rating Curve= 0 ,0
Exp/Cntr=0.3,0.1

Type RM Length L Ch R = 1 ,12406   ,1570,1570,1570
BEGIN DESCRIPTION:
UNT004 IN ROCK 12.0
END DESCRIPTION:
XS GIS Cut Line= 3
      3669099.54      10192702.2      3669133.95     10192970.98
      3669472.81     10194125.81
#Sta/Elev= 30
  4115.7   305.1  4332.3  302.98  4377.3  299.29  4400.4  301.95  4428.6  301.77
  4449.9  302.57  4539.2  299.54    4678  299.37  4721.8  299.97  4755.2   297.9
  4788.6   299.9    4822  297.25  4827.2  297.93  4845.9   296.8  4908.4   296.8
    4966  298.49  4971.2  298.35  4981.4  296.56  4991.8  292.33  5001.6  291.15
  5004.3  290.65  5007.6  291.15  5012.7  294.32  5023.1     299  5032.7  301.29
    5038  300.48  5064.8  302.05  5143.3  304.07    5294  306.77  5590.2  307.02
#Mann= 3 ,-1 , 0
  4115.7     .05       0  5001.6     .03       0  5007.6     .05       0
Bank Sta=5001.6,5007.6
XS Rating Curve= 0 ,0
Exp/Cntr=0.3,0.1

Type RM Length L Ch R = 1 ,10836   ,1070,1070,1070
BEGIN DESCRIPTION:
UNT004 IN ROCK 11.0
END DESCRIPTION:
XS GIS Cut Line= 3
      3668183.73     10193114.48      3668545.58     10193976.89
      3668845.51     10194526.76
#Sta/Elev= 30
  4582.9  313.73  4713.1  310.17  4776.5  305.58  4970.2  295.08  4977.5  293.25
  4982.9  289.12  4998.3   285.6    5001   285.1  5004.3   285.6  5030.4  292.46
  5046.1  293.55    5078  292.33  5136.4  294.21  5143.7  292.48  5160.1   292.7
  5165.6  291.61  5210.5  294.81  5260.6  294.07    5266  296.36  5273.9   297.4
  5318.8  298.78  5427.2   298.1  5479.9  298.03  5710.4  298.54    5740  303.62
  5770.2   300.4  5984.4  300.45  6063.9  300.62  6117.2  301.41  6144.5  301.45
#Mann= 11 ,-1 , 0
  4582.9     .05       0  4713.1     .12       0  4998.3     .07       0
  5004.3     .12       0  5210.5      .1       0  5318.8     .16       0
  5427.2      .1       0  5479.9     .05       0  5984.4     .07       0
  6063.9     .05       0  6117.2     .07       0
Bank Sta=4998.3,5004.3
XS Rating Curve= 0 ,0
Exp/Cntr=0.3,0.1

Type RM Length L Ch R = 1 ,9766    ,1186,1186,1186
BEGIN DESCRIPTION:
UNT004 IN ROCK 10.0
END DESCRIPTION:
XS GIS Cut Line= 3
      3667688.95     10193691.75      3667867.41     10193933.15
      3668396.42     10194650.97
#Sta/Elev= 30
  4318.3  302.91  4372.5  300.41  4413.8  298.79  4442.5  296.73  4470.1  296.49
  4505.6  295.23  4528.6  295.13  4564.1  294.11  4584.9  294.31  4670.5  291.86
  4806.3  292.28  4850.2  291.53  4871.1  292.02  4935.8   291.9  4964.5   292.6
  4971.3   292.1  4977.5  290.91    4986  289.05  4997.6  282.48  5000.3  281.98
  5014.1  284.76  5021.4  291.15  5027.7  292.38  5041.8  293.17  5171.8  295.62
  5200.5  296.57  5272.1  297.62  5313.8  298.81  5357.7  298.83  5510.2  301.91
#Mann= 5 ,-1 , 0
  4318.3     .16       0  4372.5     .12       0  4977.5     .07       0
  5021.4     .12       0  5041.8     .05       0
Bank Sta=4977.5,5021.4
XS Rating Curve= 0 ,0
Exp/Cntr=0.3,0.1

Type RM Length L Ch R = 1 ,8580    ,885,885,885
BEGIN DESCRIPTION:
UNT004 IN ROCK 9.0
END DESCRIPTION:
XS GIS Cut Line= 3
      3667610.83     10193752.49      3667441.55     10194147.48
      3667493.63     10194963.48
#Sta/Elev= 30
    4430  301.89  4450.8  302.25  4489.6   299.6  4603.2  296.04  4624.9  294.23
  4964.1  289.49  4994.2  282.67  5004.2  282.63  5014.2  286.79  5024.2  289.46
  5064.3   290.4  5114.4  289.14  5154.5   290.1  5204.6  289.48  5224.6  287.83
  5241.7  282.57  5244.4  282.07  5247.7  282.57  5260.3  286.54  5265.3  284.05
  5284.8  282.87  5324.8  286.25  5343.6  286.34  5354.9  286.23    5385   290.3
  5442.7  291.65  5475.2  292.79  5505.2  295.31  5572.6  297.76  5677.4  299.73
#Mann= 7 ,-1 , 0
    4430      .1       0  4964.1     .05       0  5024.2      .1       0
  5241.7     .07       0  5247.7     .12       0  5343.6     .16       0
  5442.7     .05       0
Bank Sta=4964.1,5024.2
XS Rating Curve= 0 ,0
Exp/Cntr=0.3,0.1

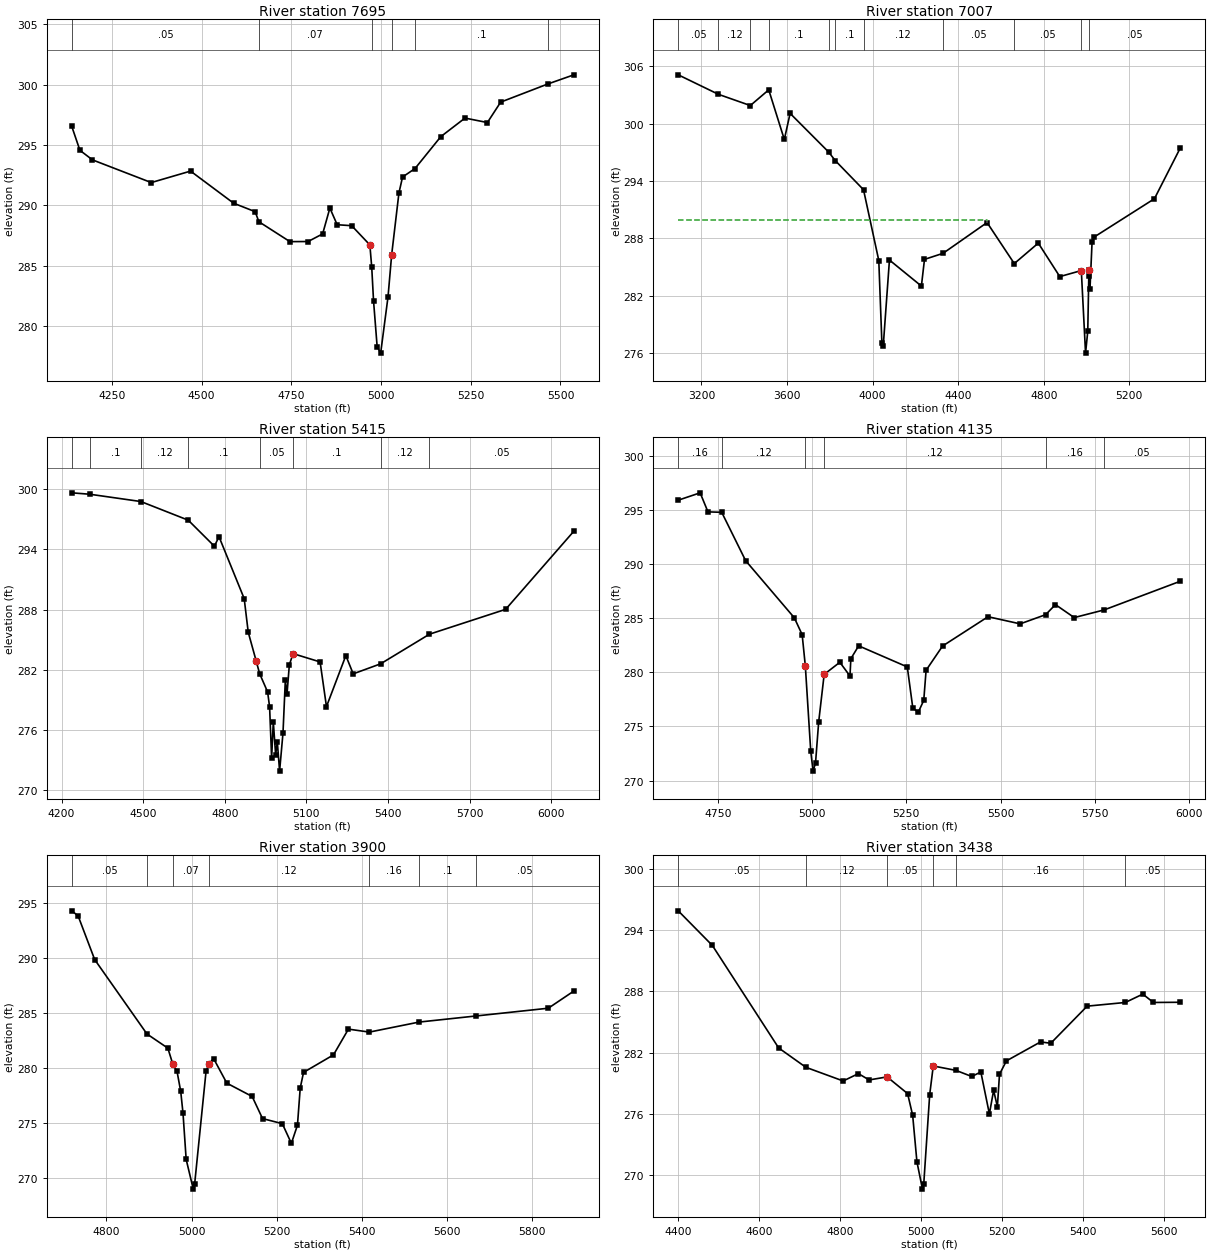
Type RM Length L Ch R = 1 ,7695    ,688,688,688
BEGIN DESCRIPTION:
UNT004 IN ROCK 8.0
END DESCRIPTION:
XS GIS Cut Line= 3
      3667392.09     10193841.68      3667124.71     10194338.45
      3667254.91     10195163.08
#Sta/Elev= 30
  4138.3  296.54    4161  294.56  4195.9  293.77  4359.8  291.89  4469.3  292.84
  4589.4  290.18  4649.3  289.48  4659.6  288.65  4746.2     287  4796.8  287.01
  4837.3  287.64  4857.5  289.78  4877.8   288.4  4918.3  288.32  4968.9  286.73
  4974.1  284.89  4979.2  282.08  4989.2  278.31    4999  277.77  5019.5  282.43
  5029.7  285.93  5049.9  291.03    5060  292.35  5094.7  293.05  5166.5  295.69
    5234  297.23  5296.4  296.86  5333.4  298.55  5464.6  300.05  5537.3  300.81
#Mann= 6 ,-1 , 0
  4138.3     .05       0  4659.6     .07       0  4974.1    .035       0
  5029.7     .07       0  5094.7      .1       0  5464.6     .05       0
Bank Sta=4968.9,5029.7
XS Rating Curve= 0 ,0
Exp/Cntr=0.3,0.1

Type RM Length L Ch R = 1 ,7007    ,1592,1592,1592
BEGIN DESCRIPTION:
UNT004 IN ROCK 7.0
END DESCRIPTION:
XS GIS Cut Line= 3
      3665549.16     10193309.78      3666734.08     10194229.94
      3666820.89     10195071.93
#Sta/Elev= 30
  3091.7  305.09  3279.8  303.05  3428.6  301.88  3514.7  303.52  3587.5  298.33
  3614.6  301.06  3794.7  297.02  3825.4  296.13  3957.7  293.08  4029.1  285.68
  4043.6  277.05  4049.9  276.76  4078.9  285.73  4228.2  283.01  4242.7   285.8
  4329.2  286.43  4535.1  289.65  4662.4  285.36  4774.6   287.5  4875.1     284
  4975.7  284.63  4995.5     276  5005.8  278.28  5011.2  284.71  5012.9  284.04
  5016.2  282.73  5025.9  287.58    5036  288.14  5317.5  292.14  5438.4  297.45
#Mann= 11 ,-1 , 0
  3091.7     .05       0  3279.8     .12       0  3428.6     .05       0
  3514.7      .1       0  3794.7     .05       0  3825.4      .1       0
  3957.7     .12       0  4329.2     .05       0  4662.4     .05       0
  4975.7    .035       0  5012.9     .05       0
#XS Ineff= 2 , 0
         4534.73  289.89
Permanent Ineff=
       F       F
Bank Sta=4975.7,5011.2
XS Rating Curve= 0 ,0
Exp/Cntr=0.3,0.1

Type RM Length L Ch R = 1 ,5415    ,1280,1280,1280
BEGIN DESCRIPTION:
UNT004 IN ROCK 6.0
END DESCRIPTION:
XS GIS Cut Line= 3
      3665193.31     10193947.84      3665692.11     10194191.64
      3666442.08     10195241.61
#Sta/Elev= 30
  4237.6  299.65  4303.6  299.51  4491.7  298.78  4665.7  296.92  4761.8  294.32
  4778.8  295.27  4871.4  289.09  4886.2  285.74  4915.7  282.84    4928  281.61
  4957.5  279.77  4964.8  278.27  4972.2  273.18  4978.4  276.79    4987  273.48
  4993.1  274.81  5001.5  271.87    5014  275.68  5022.6  280.94  5028.7  279.55
  5037.3  282.47  5050.9   283.6  5150.4  282.77  5173.8  278.31    5245   283.4
  5272.1  281.58  5372.7  282.58  5552.5  285.54  5832.4  288.02  6083.1  295.82
#Mann= 8 ,-1 , 0
  4237.6     .05       0  4303.6      .1       0  4491.7     .12       0
  4665.7      .1       0    4928     .05       0  5050.9      .1       0
  5372.7     .12       0  5552.5     .05       0
Bank Sta=4915.7,5050.9
XS Rating Curve= 0 ,0
Exp/Cntr=0.3,0.1

Type RM Length L Ch R = 1 ,4135    ,235,235,235
BEGIN DESCRIPTION:
UNT004 IN ROCK 5.0
END DESCRIPTION:
XS GIS Cut Line= 3
      3665102.12      10194260.3      3665375.58     10194624.91
      3665905.09     10195323.69
#Sta/Elev= 30
  4644.6  295.91  4702.7  296.59  4723.5  294.83    4760  294.79  4823.5  290.32
  4952.7  285.04  4973.5  283.48  4981.9  280.59  4996.3  272.69  5002.5  270.87
    5009  271.64  5017.3  275.41  5031.9  279.81  5073.5  280.93  5100.4  279.66
  5102.7  281.26  5123.5  282.45  5252.5   280.5  5267.1  276.72  5281.6  276.31
  5296.2  277.41  5302.4  280.19  5346.1  282.43  5466.8  285.14  5552.1  284.48
  5619.7  285.33  5645.7  286.26  5695.6  285.06    5775  285.77  5977.1  288.42
#Mann= 6 ,-1 , 0
  4644.6     .16       0    4760     .12       0  4981.9     .07       0
  5031.9     .12       0  5619.7     .16       0    5775     .05       0
Bank Sta=4981.9,5031.9
XS Rating Curve= 0 ,0
Exp/Cntr=0.3,0.1

Type RM Length L Ch R = 1 ,3900    ,462,462,462
BEGIN DESCRIPTION:
UNT004 IN ROCK 4.0
END DESCRIPTION:
XS GIS Cut Line= 3
      3665042.09     10194441.61      3665226.26     10194909.03
      3665661.73     10195427.26
#Sta/Elev= 30
  4718.6   294.3  4733.5  293.84  4772.4  289.87  4895.2  283.11  4944.3  281.82
  4955.5  280.42  4965.8  279.72  4974.5  277.89  4979.9   275.9  4987.3  271.71
    5004  269.01  5007.3  269.51    5034  279.72  5041.1  280.42  5051.8  280.87
  5082.8  278.64  5142.3  277.43  5166.7  275.42  5213.1  274.96  5234.4  273.17
  5248.7  274.82  5255.2   278.2    5263  279.62  5333.3  281.21  5368.4  283.55
  5417.6  283.28  5534.2  284.19  5666.9  284.74  5837.9  285.45  5897.9  287.01
#Mann= 7 ,-1 , 0
  4718.6     .05       0  4895.2     .12       0  4955.5     .07       0
  5041.1     .12       0  5417.6     .16       0  5534.2      .1       0
  5666.9     .05       0
Bank Sta=4955.5,5041.1
XS Rating Curve= 0 ,0
Exp/Cntr=0.3,0.1

Type RM Length L Ch R = 1 ,3438    ,522,522,522
BEGIN DESCRIPTION:
UNT004 IN ROCK 3.0
END DESCRIPTION:
XS GIS Cut Line= 3
       3664842.1     10194441.61      3664866.58      10194850.4
      3665128.05     10195639.59
#Sta/Elev= 30
  4400.1   295.9  4484.5   292.5  4648.3  282.45  4715.6  280.55  4807.7  279.21
  4845.4  279.93  4871.9  279.31  4916.3  279.61    4967  277.97  4979.5  275.84
    4990  271.29  5003.7   268.6  5006.9   269.1  5021.6  277.88  5030.4  280.68
  5086.4  280.25  5125.5  279.65    5148  280.09  5169.1  275.98  5179.6  278.29
  5188.9  276.68  5194.1  279.87  5211.2  281.18  5295.5  283.04  5320.9  282.91
  5410.8  286.55  5505.1  286.91  5548.3  287.73  5574.5  286.91    5641  286.93
#Mann= 6 ,-1 , 0
  4400.1     .05       0  4715.6     .12       0  4916.3     .05       0
  5030.4     .12       0  5086.4     .16       0  5505.1     .05       0
Bank Sta=4916.3,5030.4
XS Rating Curve= 0 ,0
Exp/Cntr=0.3,0.1

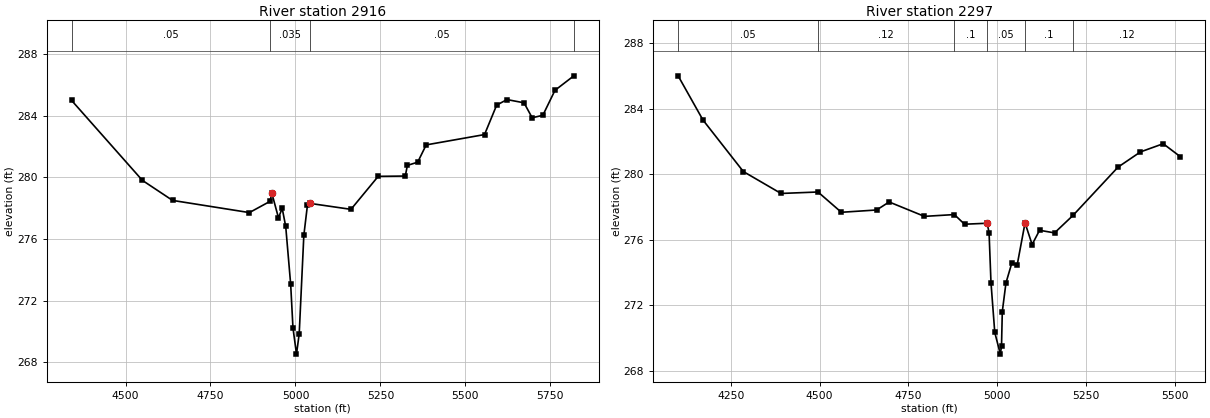
Type RM Length L Ch R = 1 ,2916    ,619,619,619
BEGIN DESCRIPTION:
UNT004 IN ROCK 2.0
END DESCRIPTION:
XS GIS Cut Line= 3
      3664572.63     10194459.98      3664412.04     10194824.56
      3664787.16     10195836.59
#Sta/Elev= 30
  4341.5  284.99  4549.6  279.81  4638.4  278.51  4864.5  277.72  4925.3  278.45
  4930.6  278.97  4950.1  277.38    4961     278  4971.4  276.82    4986  273.06
  4992.7  270.25  5003.1  268.54  5011.1  269.86  5024.7  276.24  5035.4  278.22
  5041.5  278.32  5163.4  277.93  5243.5  280.07  5323.3  280.09  5329.3  280.78
  5359.7  280.99  5384.7  282.11  5556.4  282.78  5592.1  284.69  5622.5  285.05
  5672.6  284.84  5696.6  283.87    5728  284.03  5763.7  285.65  5819.2  286.59
#Mann= 4 ,-1 , 0
  4341.5     .05       0  4925.3    .035       0  5041.5     .05       0
  5819.2     .16       0
Bank Sta=4930.6,5041.5
XS Rating Curve= 0 ,0
Exp/Cntr=0.3,0.1

Type RM Length L Ch R = 1 ,2297    ,0,0,0
BEGIN DESCRIPTION:
UNT004 IN ROCK 1.0
END DESCRIPTION:
XS GIS Cut Line= 3
      3664399.01     10194329.78      3663882.08      10194796.9
      3664103.33     10195478.26
#Sta/Elev= 30
  4101.8  286.02  4171.7  283.32  4285.3  280.17  4391.4  278.83  4495.4  278.92
  4561.1  277.68  4660.4  277.82  4695.6  278.31  4794.9  277.43  4879.1  277.54
  4907.7  276.95  4971.6  277.01  4976.8  276.42  4982.2  273.37  4992.8  270.34
  5008.5  269.01  5011.8  269.51    5014  271.61  5024.3  273.36  5040.8  274.58
  5055.8  274.45    5078  277.03  5097.9  275.71  5118.9  276.58    5161  276.42
  5213.5   277.5  5339.7  280.44  5402.8  281.37  5466.8  281.87  5514.9  281.08
#Mann= 6 ,-1 , 0
  4101.8     .05       0  4495.4     .12       0  4879.1      .1       0
  4971.6     .05       0    5078      .1       0  5213.5     .12       0
Bank Sta=4971.6,5078
XS Rating Curve= 0 ,0
Exp/Cntr=0.3,0.1

Chan Stop Cuts=-1
Use User Specified Reach Order=0
Composite Channel Slope=5