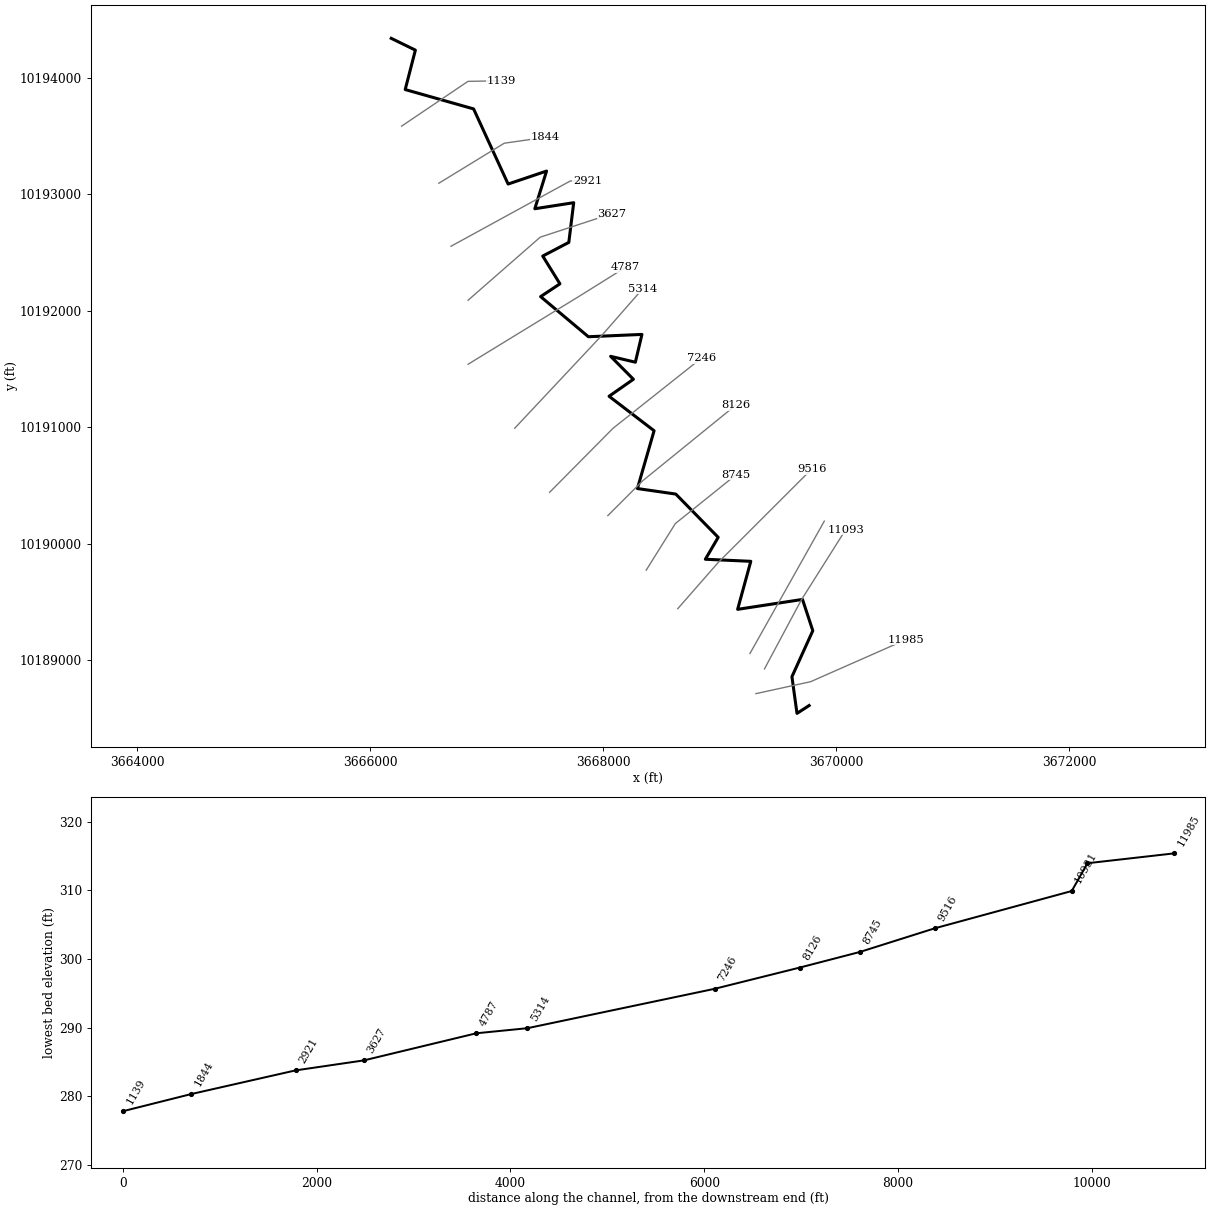
--- UNT005 IN ROCK.prj (project) ---

Proj Title=UNT005 IN ROCK Base Level Engineering
Current Plan=p01
Default Exp/Contr=0.3,0.1
English Units
Geom File=g01
Flow File=f01
Plan File=p01
BEGIN DESCRIPTION:
UNT005 IN ROCK
END DESCRIPTION:

--- UNT005 IN ROCK.p01 (plan) ---

Plan Title=Multiple Run
Short Identifier=Multiple
Geom File=g01
Flow File=f01
Subcritical Flow
K Sum by GR= 0
Std Step Tol= 0.01
Critical Tol= 0.01
Num of Std Step Trials= 20
Max Error Tol= 0.3
Flow Tol Ratio= 0.001
Split Flow NTrial= 30
Split Flow Tol= 0.02
Split Flow Ratio= 0.02
Log Output Level= 0
Friction Slope Method= 1
Unsteady Friction Slope Method= 2
Unsteady Bridges Friction Slope Method= 1
Parabolic Critical Depth
Global Vel Dist=  1 , 1 , 1
Global Log Level= 0
CheckData=True
Encroach Param= -1, 0, 0, 0
BEGIN DESCRIPTION:
Multiple Run
END DESCRIPTION:

--- UNT005 IN ROCK.f01 (steady flow) ---

Flow Title=Multiple
Number of Profiles=7
Profile Names=10-year,25-year,50-year,1pct_min,100-year,1pct_plu,500-year
River Rch & RM= UNT005 IN ROCK,Reach-1,11985
    1089    1503    1848    1662    2248    3041    3328
Boundary for River Rch & Prof#=UNT005 IN ROCK,Reach-1,1
Up Type=0
Dn Type=3
Dn Slope=0.005
Boundary for River Rch & Prof#=UNT005 IN ROCK,Reach-1,2
Up Type=0
Dn Type=3
Dn Slope=0.005
Boundary for River Rch & Prof#=UNT005 IN ROCK,Reach-1,3
Up Type=0
Dn Type=3
Dn Slope=0.005
Boundary for River Rch & Prof#=UNT005 IN ROCK,Reach-1,4
Up Type=0
Dn Type=3
Dn Slope=0.005
Boundary for River Rch & Prof#=UNT005 IN ROCK,Reach-1,5
Up Type=0
Dn Type=3
Dn Slope=0.005
Boundary for River Rch & Prof#=UNT005 IN ROCK,Reach-1,6
Up Type=0
Dn Type=3
Dn Slope=0.005
Boundary for River Rch & Prof#=UNT005 IN ROCK,Reach-1,7
Up Type=0
Dn Type=3
Dn Slope=0.005

--- UNT005 IN ROCK.g01 (geometry) ---

Geom Title=Existing Conditions

River Reach=UNT005 IN ROCK,Reach-1
Reach XY= 30
      3669769.79     10188609.58      3669665.62     10188542.21
      3669622.16     10188857.08      3669801.43     10189252.51
      3669712.87     10189521.14      3669156.00     10189436.05
      3669268.99     10189848.54      3668878.90     10189866.34
      3668989.22     10190054.59      3668625.17     10190426.29
      3668295.59     10190473.81      3668438.80     10190970.37
      3668052.37     10191266.57      3668261.20     10191412.62
      3668065.84     10191609.67      3668278.14     10191559.20
      3668334.46     10191797.93      3667874.82     10191778.03
      3667464.64     10192122.76      3667630.48     10192232.58
      3667482.79     10192471.16      3667706.74     10192588.61
      3667748.76     10192929.62      3667414.89     10192877.70
      3667515.84     10193201.42      3667185.68     10193089.85
      3666889.32     10193735.31      3666302.08     10193901.64
      3666389.53     10194240.41      3666182.11     10194341.64

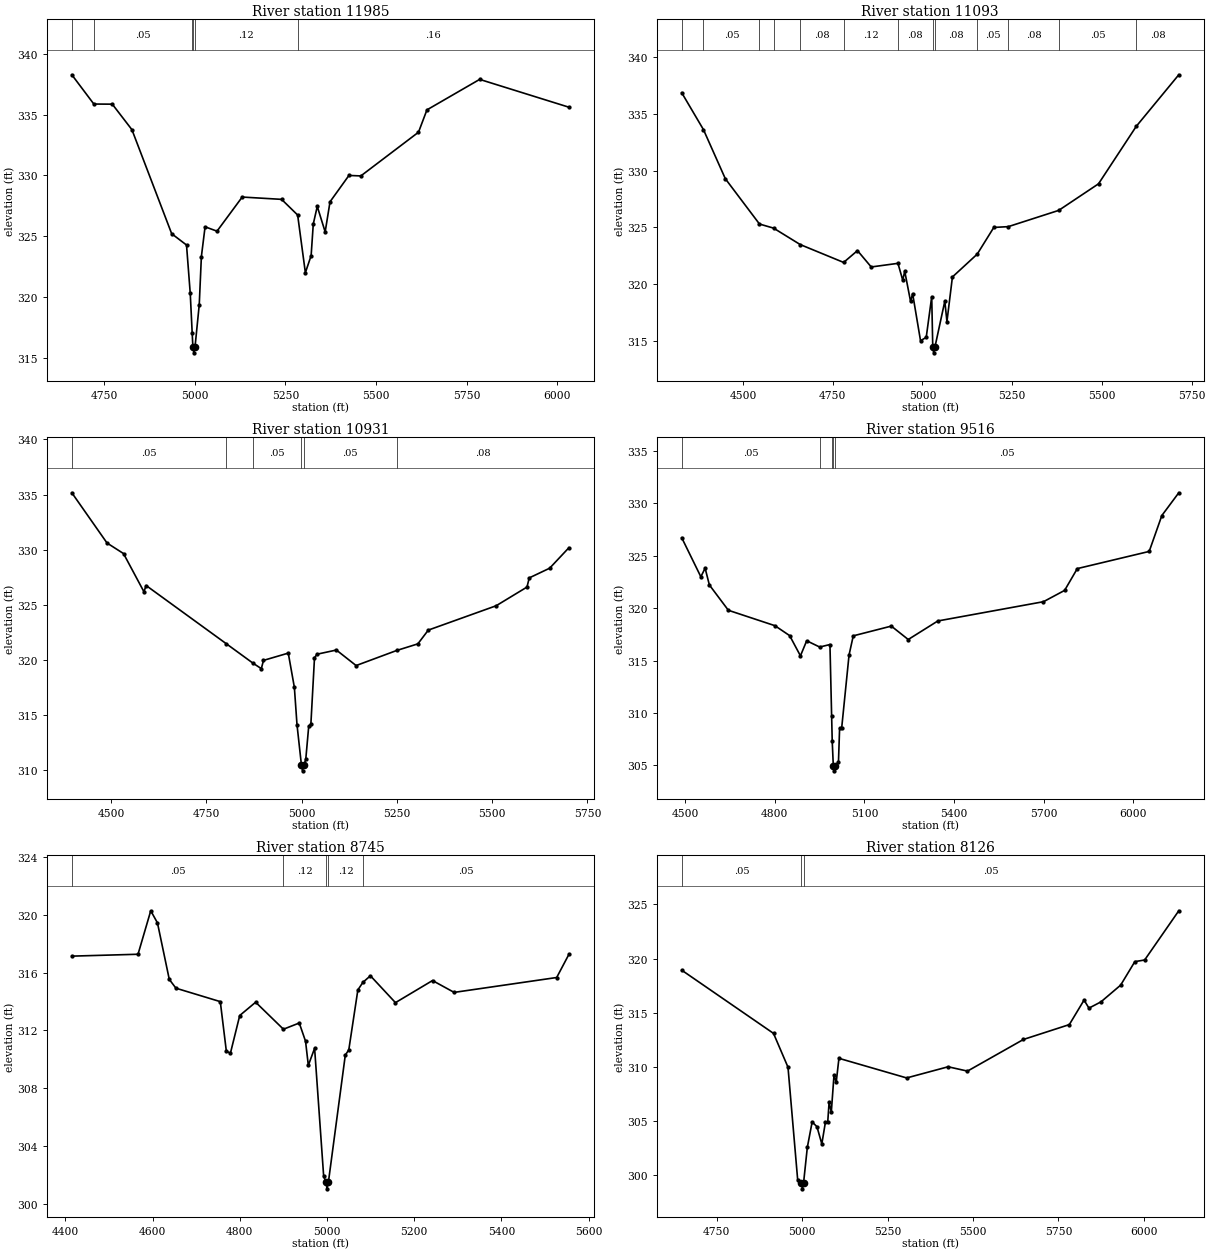
Type RM Length L Ch R = 1,11985,892,892,892
BEGIN DESCRIPTION:
UNT005 IN ROCK 17.0
END DESCRIPTION:
XS GIS Cut Line= 3
      3669313.07     10188711.70      3669782.65     10188814.42
      3670597.04     10189173.93
#Sta/Elev= 30
  4661.2  338.29  4721.9  335.88  4772.8  335.87  4826.9  333.77  4936.6  325.20
  4977.5  324.27  4987.8  320.28  4993.1  317.05  4995.0  315.89  4997.8  315.39
  5001.0  315.89  5012.6  319.35  5018.5  323.32  5028.7  325.77  5061.6  325.41
  5131.1  328.22  5239.7  328.03  5284.0  326.74  5305.3  321.99  5321.2  323.40
  5327.1  326.00  5338.1  327.45  5359.9  325.35  5373.3  327.83  5425.5  330.00
  5458.3  329.96  5617.3  333.56  5640.6  335.40  5786.0  337.91  6032.1  335.62
#Mann=6,-1,0
  4661.2    0.08       0  4721.9    0.05       0  4993.1    0.12       0
  4995.0    0.07       0  5001.0    0.12       0  5284.0    0.16       0
Bank Sta=4995,5001
Exp/Cntr=0.3,0.1

Type RM Length L Ch R = 1,11093,162,162,162
BEGIN DESCRIPTION:
UNT005 IN ROCK 16.0
END DESCRIPTION:
XS GIS Cut Line= 3
      3669386.43     10188924.47      3669702.48     10189516.37
      3670083.49     10190120.46
#Sta/Elev= 30
  4329.0  336.86  4389.6  333.61  4450.5  329.29  4545.7  325.30  4584.9  324.94
  4659.4  323.49  4780.2  321.92  4818.8  322.96  4857.1  321.52  4931.6  321.84
  4944.9  320.36  4950.5  321.14  4966.8  318.48  4972.5  319.17  4994.5  315.03
  5010.4  315.32  5025.7  318.91  5028.6  314.46  5031.3  313.96  5034.6  314.46
  5062.2  318.51  5068.1  316.71  5083.4  320.64  5152.5  322.65  5198.7  325.00
  5239.0  325.07  5379.5  326.50  5490.5  328.84  5595.7  333.90  5714.2  338.44
#Mann=13,-1,0
  4329.0    0.08       0  4389.6    0.05       0  4545.7    0.08       0
  4584.9    0.12       0  4659.4    0.08       0  4780.2    0.12       0
  4931.6    0.08       0  5028.6    0.07       0  5034.6    0.08       0
  5152.5    0.05       0  5239.0    0.08       0  5379.5    0.05       0
  5595.7    0.08       0
Bank Sta=5028.6,5034.6
Exp/Cntr=0.3,0.1

Type RM Length L Ch R = 1,10931,1415,1415,1415
BEGIN DESCRIPTION:
UNT005 IN ROCK 15.0
END DESCRIPTION:
XS GIS Cut Line= 3
      3669261.71     10189056.55      3669596.21     10189651.88
      3669900.06     10190193.84
#Sta/Elev= 30
  4397.2  335.16  4489.5  330.60  4532.8  329.64  4586.4  326.17  4592.1  326.74
  4801.8  321.47  4872.4  319.69  4894.4  319.19  4900.1  319.94  4965.1  320.60
  4981.1  317.49  4988.0  314.10  4999.7  310.41  5002.5  309.91  5005.7  310.41
  5011.0  310.95  5018.7  313.94  5024.4  314.14  5033.9  320.17  5040.4  320.50
  5091.3  320.88  5143.1  319.47  5249.6  320.84  5305.1  321.44  5332.5  322.69
  5510.5  324.90  5591.5  326.60  5597.3  327.43  5650.9  328.31  5701.4  330.17
#Mann=6,-1,0
  4397.2    0.05       0  4801.8    0.12       0  4872.4    0.05       0
  4999.7    0.04       0  5005.7    0.05       0  5249.6    0.08       0
Bank Sta=4999.7,5005.7
Exp/Cntr=0.3,0.1

Type RM Length L Ch R = 1,9516,771,771,771
BEGIN DESCRIPTION:
UNT005 IN ROCK 14.0
END DESCRIPTION:
XS GIS Cut Line= 3
      3668642.12     10189441.66      3668992.11     10189841.64
      3669792.14     10190641.67
#Sta/Elev= 30
  4488.7  326.73  4552.7  323.00  4567.0  323.82  4581.2  322.22  4644.8  319.80
  4800.5  318.33  4849.8  317.38  4885.9  315.45  4906.8  316.89  4950.3  316.29
  4984.6  316.53  4990.2  309.74  4992.2  307.32  4995.8  304.97  4998.6  304.47
  5001.8  304.97  5013.1  305.31  5016.9  308.52  5023.7  308.52  5048.5  315.53
  5062.6  317.36  5189.9  318.29  5246.5  317.01  5345.5  318.78  5699.0  320.62
  5769.7  321.70  5812.1  323.78  6052.6  325.42  6095.0  328.85  6151.6  331.02
#Mann=5,-1,0
  4488.7    0.05       0  4950.3    0.12       0  4990.2    0.05       0
  4995.8    0.03       0  5001.8    0.05       0
Bank Sta=4995.8,5001.8
Exp/Cntr=0.3,0.1

Type RM Length L Ch R = 1,8745,619,619,619
BEGIN DESCRIPTION:
UNT005 IN ROCK 12.0
END DESCRIPTION:
XS GIS Cut Line= 3
      3668371.28     10189772.91      3668621.27     10190172.89
      3669142.12     10190591.66
#Sta/Elev= 30
  4414.8  317.14  4566.6  317.27  4595.8  320.28  4611.2  319.44  4638.3  315.53
  4653.6  314.92  4755.3  313.99  4769.2  310.55  4778.6  310.43  4799.9  313.03
  4836.4  313.95  4900.1  312.08  4936.4  312.51  4950.8  311.25  4957.2  309.58
  4971.6  310.76  4992.4  301.89  4997.4  301.53  5000.1  301.03  5003.4  301.53
  5042.0  310.29  5050.0  310.65  5070.8  314.80  5082.5  315.33  5099.6  315.78
  5157.0  313.92  5242.0  315.45  5291.6  314.63  5526.8  315.66  5554.8  317.26
#Mann=5,-1,0
  4414.8    0.05       0  4900.1    0.12       0  4997.4    0.07       0
  5003.4    0.12       0  5082.5    0.05       0
Bank Sta=4997.4,5003.4
Exp/Cntr=0.3,0.1

Type RM Length L Ch R = 1,8126,880,880,880
BEGIN DESCRIPTION:
UNT005 IN ROCK 11.0
END DESCRIPTION:
XS GIS Cut Line= 3
      3668042.13     10190241.67      3668342.11     10190541.64
      3669142.11     10191191.64
#Sta/Elev= 30
  4647.3  318.93  4916.0  313.10  4958.4  309.98  4986.7  299.60  4997.8  299.26
  5000.6  298.76  5003.8  299.26  5015.0  302.59  5029.1  304.93  5043.2  304.49
  5057.4  302.90  5068.0  304.92  5074.7  304.92  5078.7  306.73  5085.2  305.84
  5093.1  309.27  5099.5  308.58  5107.5  310.80  5305.7  308.99  5427.1  310.02
  5483.8  309.62  5647.6  312.54  5781.9  313.91  5825.0  316.17  5839.4  315.43
  5874.6  316.01  5932.1  317.55  5973.7  319.72  6002.4  319.87  6102.3  324.41
#Mann=3,-1,0
  4647.3    0.05       0  4997.8    0.03       0  5003.8    0.05       0
Bank Sta=4997.8,5003.8
Exp/Cntr=0.3,0.1

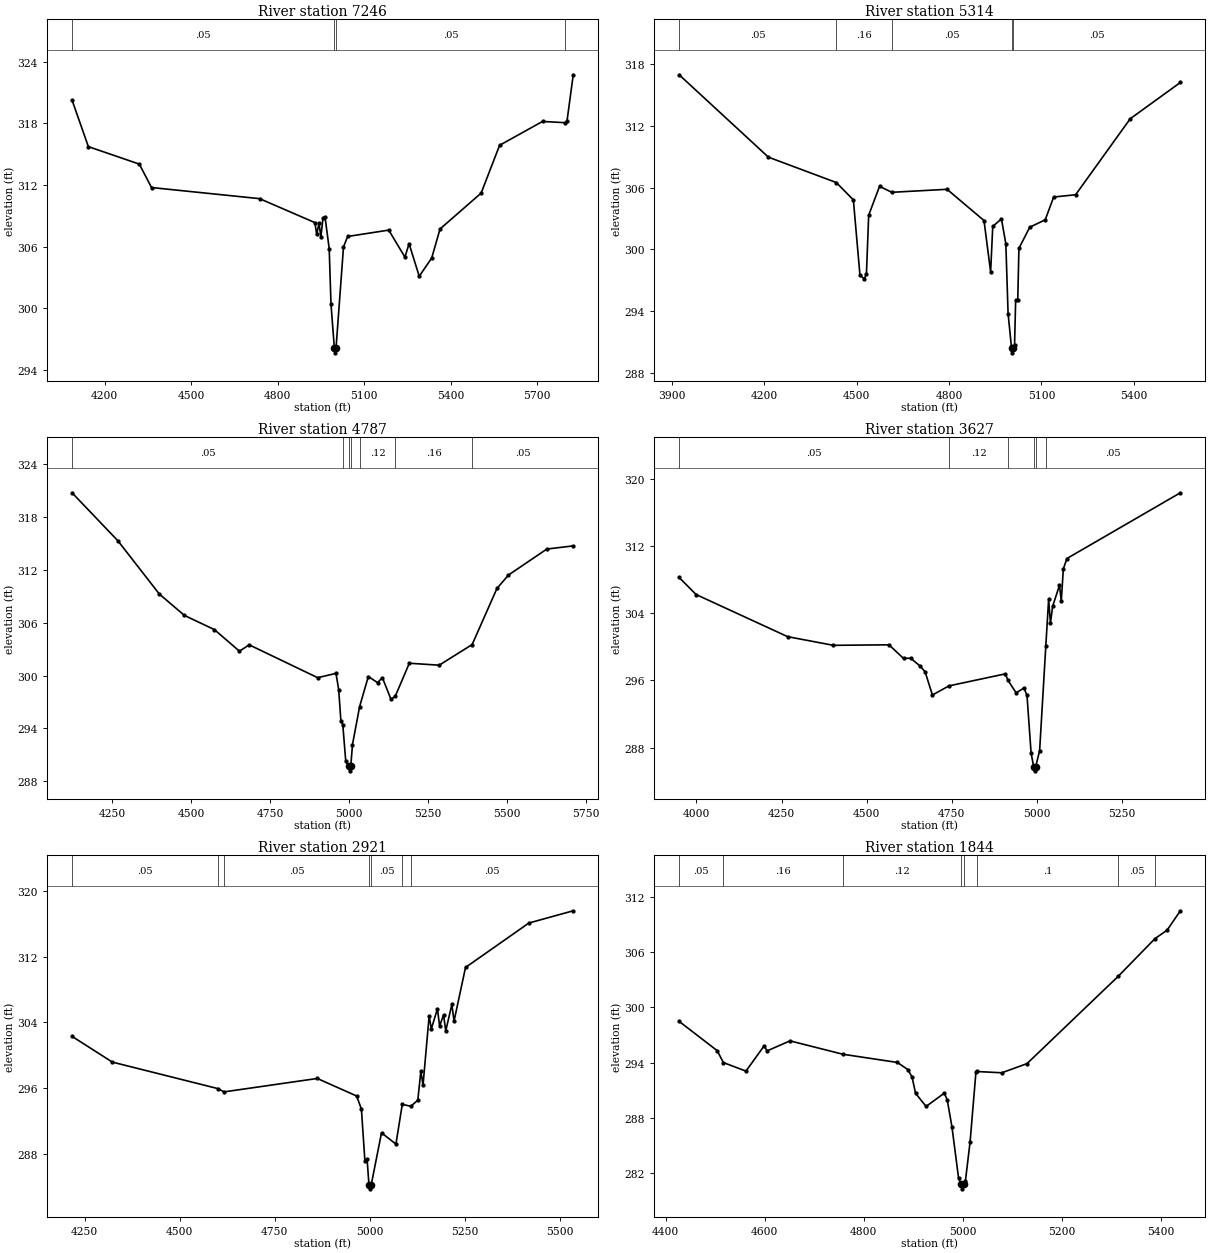
Type RM Length L Ch R = 1,7246,1932,1932,1932
BEGIN DESCRIPTION:
UNT005 IN ROCK 9.0
END DESCRIPTION:
XS GIS Cut Line= 3
      3667542.08     10190441.62      3668086.38     10190991.49
      3668842.07     10191591.61
#Sta/Elev= 30
  4087.0  320.25  4143.6  315.72  4320.4  314.02  4362.8  311.74  4737.6  310.66
  4929.4  308.33  4935.8  307.18  4943.8  308.28  4950.2  306.92  4957.4  308.75
  4964.6  308.89  4979.1  305.79  4985.4  300.37  4996.9  296.16  4999.6  295.66
  5002.9  296.16  5028.7  305.96  5043.1  306.98  5185.7  307.60  5241.8  304.97
  5256.2  306.28  5291.4  303.11  5334.7  304.88  5363.6  307.71  5506.2  311.20
  5570.2  315.85  5719.2  318.17  5798.0  318.05  5804.1  318.22  5825.7  322.71
#Mann=4,-1,0
  4087.0    0.05       0  4996.9    0.03       0  5002.9    0.05       0
  5798.0    0.08       0
Bank Sta=4996.9,5002.9
Exp/Cntr=0.3,0.1

Type RM Length L Ch R = 1,5314,527,527,527
BEGIN DESCRIPTION:
UNT005 IN ROCK 7.0
END DESCRIPTION:
XS GIS Cut Line= 3
      3667242.12     10190991.65      3667992.11     10191791.64
      3668342.12     10192191.66
#Sta/Elev= 30
  3923.3  316.99  4213.2  308.97  4433.8  306.50  4489.2  304.81  4510.6  297.48
  4524.8  297.11  4531.7  297.63  4539.0  303.32  4574.2  306.13  4614.0  305.55
  4793.5  305.84  4913.6  302.80  4935.1  297.80  4942.0  302.23  4970.3  302.96
  4984.5  300.53  4991.8  293.74  5002.9  290.42  5005.7  289.92  5008.9  290.42
  5012.8  290.66  5016.4  295.06  5023.2  295.06  5027.0  300.09  5062.1  302.15
  5112.4  302.87  5139.9  305.09  5211.1  305.31  5388.6  312.71  5551.4  316.24
#Mann=5,-1,0
  3923.3    0.05       0  4433.8    0.16       0  4614.0    0.05       0
  5002.9    0.03       0  5008.9    0.05       0
Bank Sta=5002.9,5008.9
Exp/Cntr=0.3,0.1

Type RM Length L Ch R = 1,4787,1160,1160,1160
BEGIN DESCRIPTION:
UNT005 IN ROCK 6.0
END DESCRIPTION:
XS GIS Cut Line= 3
      3666842.14     10191541.66      3667793.15     10192123.93
      3668193.14     10192373.93
#Sta/Elev= 30
  4123.4  320.76  4268.5  315.31  4400.0  309.25  4479.3  306.83  4574.1  305.22
  4653.4  302.77  4684.3  303.49  4901.0  299.76  4959.1  300.25  4967.6  298.41
  4974.5  294.89  4980.6  294.42  4990.0  290.26  4999.8  289.68  5002.5  289.18
  5005.8  289.68  5011.3  292.17  5033.9  296.48  5061.4  299.89  5090.6  299.20
  5106.0  299.76  5133.2  297.30  5146.9  297.67  5191.2  301.40  5285.8  301.18
  5390.1  303.52  5468.6  309.89  5505.2  311.42  5626.6  314.37  5710.2  314.73
#Mann=7,-1,0
  4123.4    0.05       0  4980.6    0.16       0  4999.8    0.07       0
  5005.8    0.16       0  5033.9    0.12       0  5146.9    0.16       0
  5390.1    0.05       0
Bank Sta=4999.8,5005.8
Exp/Cntr=0.3,0.1

Type RM Length L Ch R = 1,3627,706,706,706
BEGIN DESCRIPTION:
UNT005 IN ROCK 4.0
END DESCRIPTION:
XS GIS Cut Line= 3
      3666842.10     10192091.63      3667461.31     10192633.45
      3668078.77     10192835.93
#Sta/Elev= 30
  3949.2  308.26  3999.0  306.23  4268.1  301.21  4402.4  300.18  4565.7  300.24
  4608.4  298.62  4629.3  298.65  4657.7  297.69  4672.0  297.01  4693.3  294.26
  4741.9  295.35  4907.5  296.78  4915.5  296.00  4939.3  294.52  4962.3  295.10
  4971.2  294.21  4983.3  287.33  4990.8  285.73  4993.6  285.23  4996.8  285.73
  5008.3  287.62  5026.5  300.12  5034.8  305.66  5040.1  302.82  5046.5  304.81
  5066.7  307.34  5071.9  305.45  5078.0  309.28  5088.5  310.52  5421.8  318.35
#Mann=6,-1,0
  3949.2    0.05       0  4741.9    0.12       0  4915.5    0.16       0
  4990.8    0.07       0  4996.8    0.16       0  5026.5    0.05       0
Bank Sta=4990.8,4996.8
Exp/Cntr=0.3,0.1

Type RM Length L Ch R = 1,2921,1077,1077,1077
BEGIN DESCRIPTION:
UNT005 IN ROCK 3.0
END DESCRIPTION:
XS GIS Cut Line= 3
      3666695.11     10192555.25      3667720.23     10193116.64
      3667868.66     10193116.64
#Sta/Elev= 30
  4217.0  302.31  4322.9  299.18  4599.3  295.97  4616.7  295.56  4861.5  297.19
  4964.9  295.06  4977.5  293.47  4986.7  287.13  4992.4  287.42  4997.3  284.27
  5000.0  283.77  5003.3  284.27  5030.3  290.58  5068.2  289.21  5084.9  294.04
  5107.4  293.81  5125.7  294.55  5133.7  298.08  5139.4  296.38  5155.5  304.79
  5161.2  303.22  5177.3  305.65  5183.0  303.57  5193.4  304.92  5199.1  302.97
  5215.2  306.19  5220.9  304.16  5251.1  310.69  5417.6  316.09  5534.2  317.58
#Mann=7,-1,0
  4217.0    0.05       0  4599.3     0.1       0  4616.7    0.05       0
  4997.3    0.03       0  5003.3    0.05       0  5084.9    0.16       0
  5107.4    0.05       0
Bank Sta=4997.3,5003.3
Exp/Cntr=0.3,0.1

Type RM Length L Ch R = 1,1844,705,705,705
BEGIN DESCRIPTION:
UNT005 IN ROCK 2.0
END DESCRIPTION:
XS GIS Cut Line= 3
      3666590.94     10193096.92      3667152.52     10193440.60
      3667502.57     10193490.61
#Sta/Elev= 30
  4427.5  298.47  4504.3  295.30  4516.7  294.01  4562.4  293.08  4599.1  295.82
  4605.0  295.27  4651.3  296.36  4758.0  294.91  4868.1  294.02  4889.4  293.24
  4897.8  292.43  4904.8  290.68  4926.1  289.25  4962.8  290.69  4968.7  289.99
  4978.3  287.05  4991.6  281.52  4996.6  280.82  4999.3  280.32  5002.6  280.82
  5005.4  281.13  5015.0  285.44  5026.8  293.01  5028.0  293.04  5078.9  292.90
  5129.8  293.89  5314.1  303.36  5388.4  307.45  5412.6  308.35  5439.5  310.46
#Mann=8,-1,0
  4427.5    0.05       0  4516.7    0.16       0  4758.0    0.12       0
  4996.6    0.07       0  5002.6    0.12       0  5028.0     0.1       0
  5314.1    0.05       0  5388.4     0.1       0
Bank Sta=4996.6,5002.6
Exp/Cntr=0.3,0.1

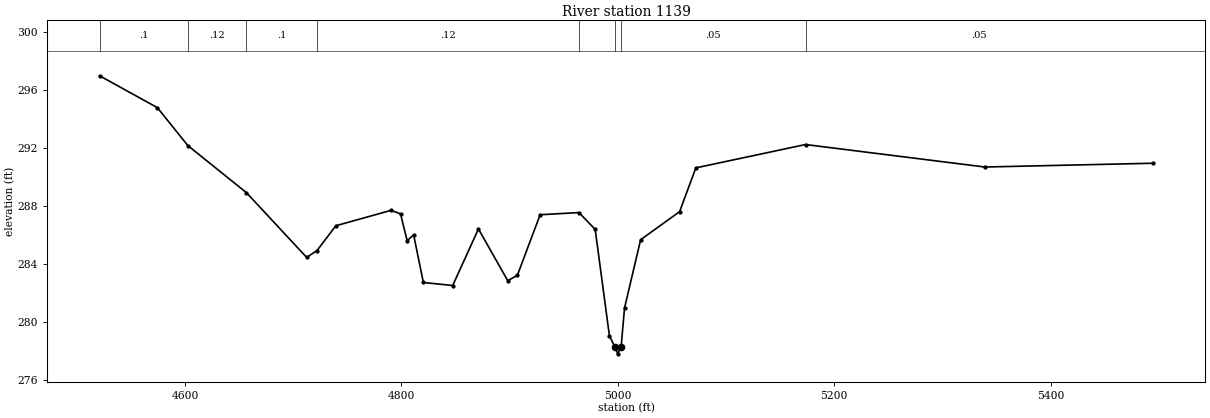
Type RM Length L Ch R = 1,1139,0,0,0
BEGIN DESCRIPTION:
UNT005 IN ROCK 1.0
END DESCRIPTION:
XS GIS Cut Line= 3
      3666271.64     10193587.54      3666840.93     10193971.92
      3667127.28     10193977.12
#Sta/Elev= 30
  4521.2  296.99  4574.6  294.79  4602.7  292.18  4656.9  288.93  4712.5  284.47
  4722.1  284.94  4739.5  286.65  4790.4  287.71  4799.3  287.47  4805.4  285.62
  4811.4  286.02  4820.4  282.74  4847.5  282.53  4871.3  286.43  4898.4  282.86
  4907.3  283.24  4928.3  287.41  4964.2  287.56  4979.2  286.40  4992.3  279.08
  4997.2  278.32  5000.0  277.82  5003.2  278.32  5006.3  280.98  5021.2  285.69
  5057.2  287.62  5072.2  290.64  5173.6  292.25  5339.3  290.70  5494.5  290.96
#Mann=8,-1,0
  4521.2     0.1       0  4602.7    0.12       0  4656.9     0.1       0
  4722.1    0.12       0  4964.2    0.05       0  4997.2    0.07       0
  5003.2    0.05       0  5173.6    0.05       0
Bank Sta=4997.2,5003.2
Exp/Cntr=0.3,0.1

Chan Stop Cuts=-1