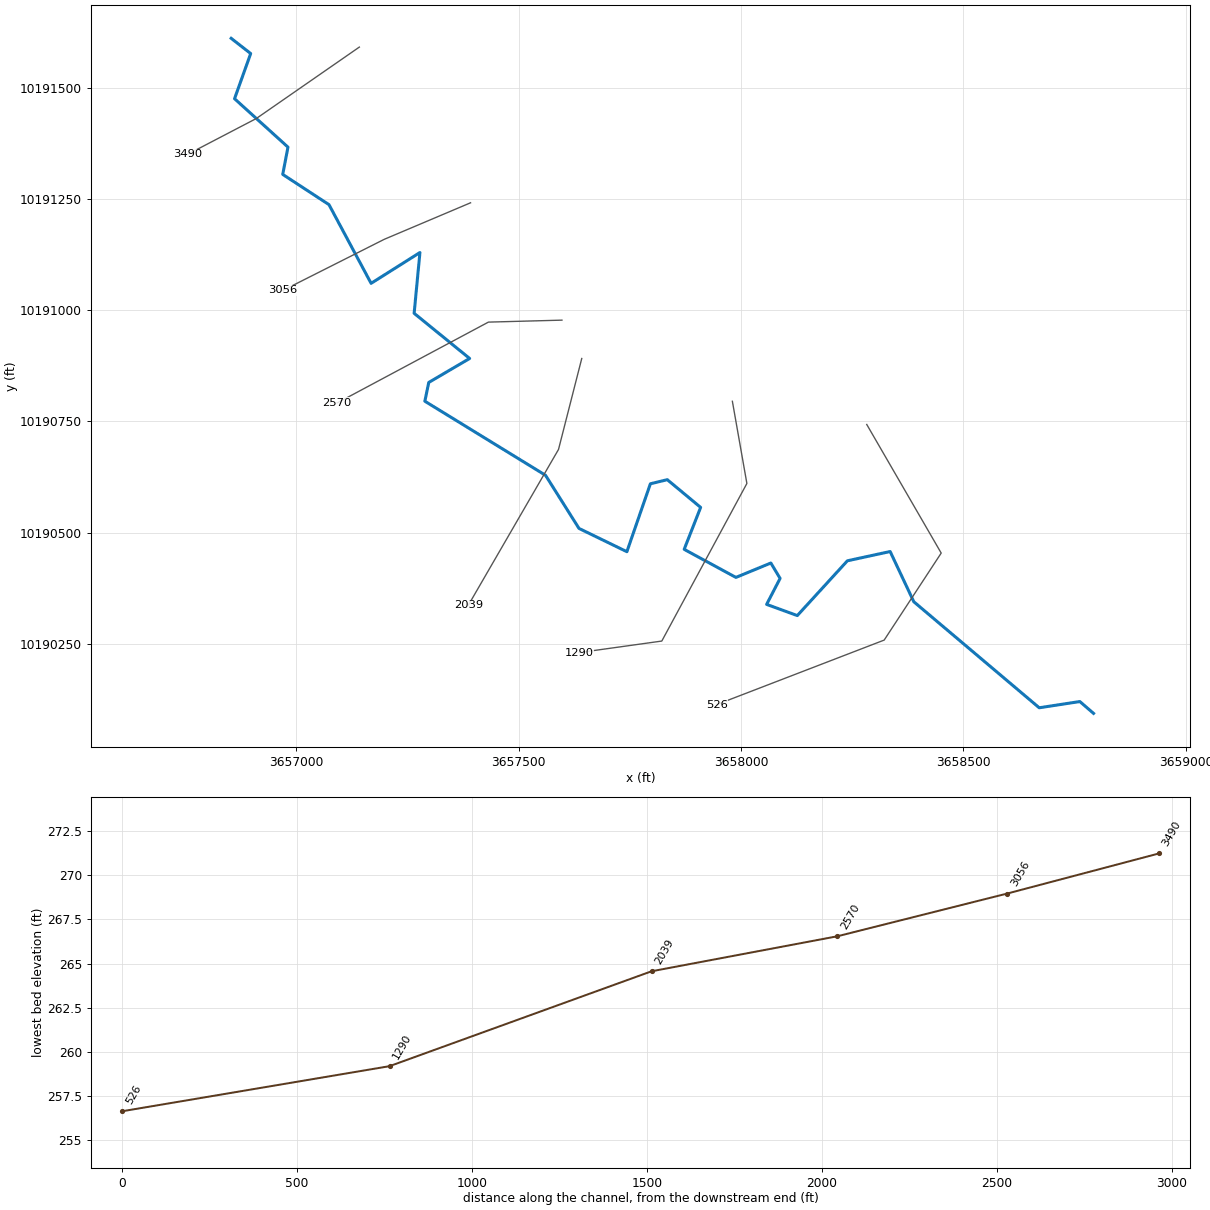
--- UNT007 IN ROCK.prj (project) ---

Proj Title=UNT007 IN ROCK Base Level Engineering
Current Plan=p01
Default Exp/Contr=0.3,0.1
English Units
Geom File=g01
Flow File=f01
Plan File=p01
Y Axis Title=Elevation
X Axis Title(PF)=Main Channel Distance
X Axis Title(XS)=Station
BEGIN DESCRIPTION:
UNT007 IN ROCK
END DESCRIPTION:
DSS Export Rating Curves= 0
DSS Export Rating Curve Sorted= 0
DSS Export Volume Flow Curves= 0
DXF OffsetX= 0
DXF OffsetY= 0
DXF ScaleX= 1
DXF ScaleY= 10

--- UNT007 IN ROCK.p01 (plan) ---

Plan Title=Multiple Run
Short Identifier=Multiple
Geom File=g01
Flow File=f01
Subcritical Flow
K Sum by GR= 0
Std Step Tol= 0.01
Critical Tol= 0.01
Num of Std Step Trials= 20
Max Error Tol= 0.3
Flow Tol Ratio= 0.001
Split Flow NTrial= 30
Split Flow Tol= 0.02
Split Flow Ratio= 0.02
Log Output Level= 0
Friction Slope Method= 1
Unsteady Friction Slope Method= 2
Unsteady Bridges Friction Slope Method= 1
Parabolic Critical Depth
Global Vel Dist=  1 , 1 , 1
Global Log Level= 0
CheckData=True
Encroach Param= -1, 0, 0, 0
BEGIN DESCRIPTION:
Multiple Run
END DESCRIPTION:

--- UNT007 IN ROCK.f01 (steady flow) ---

Flow Title=Multiple
Program Version=4.10
Number of Profiles= 7
Profile Names=10-year,25-year,50-year,1pct_min,100-year,1pct_plu,500-year
River Rch & RM=UNT007 IN ROCK,Reach-1         ,3490
     444     587     702     617     834    1128    1177
Boundary for River Rch & Prof#=UNT007 IN ROCK,Reach-1         , 1
Up Type= 0
Dn Type= 3
Dn Slope=0.0065
Boundary for River Rch & Prof#=UNT007 IN ROCK,Reach-1         , 2
Up Type= 0
Dn Type= 3
Dn Slope=0.0065
Boundary for River Rch & Prof#=UNT007 IN ROCK,Reach-1         , 3
Up Type= 0
Dn Type= 3
Dn Slope=0.0065
Boundary for River Rch & Prof#=UNT007 IN ROCK,Reach-1         , 4
Up Type= 0
Dn Type= 3
Dn Slope=0.0065
Boundary for River Rch & Prof#=UNT007 IN ROCK,Reach-1         , 5
Up Type= 0
Dn Type= 3
Dn Slope=0.0065
Boundary for River Rch & Prof#=UNT007 IN ROCK,Reach-1         , 6
Up Type= 0
Dn Type= 3
Dn Slope=0.0065
Boundary for River Rch & Prof#=UNT007 IN ROCK,Reach-1         , 7
Up Type= 0
Dn Type= 3
Dn Slope=0.0065
DSS Import GetInterval= 0
DSS Import GetPeak= 0
DSS Import FillOption= 0

--- UNT007 IN ROCK.g01 (geometry) ---

Geom Title=Existing Conditions
Program Version=4.10

River Reach=UNT007 IN ROCK  ,Reach-1
Reach XY= 30
        3656854.     10191611.33      3656897.88     10191577.14
      3656861.58      10191475.6      3656981.68     10191366.74
       3656969.9     10191305.45      3657073.89     10191237.45
      3657168.56     10191060.56      3657278.32     10191129.84
      3657265.31     10190993.19      3657390.05     10190891.68
       3657298.2     10190837.79      3657289.36     10190795.61
      3657560.62     10190629.14      3657635.88     10190509.65
      3657743.55      10190457.3      3657796.41       10190610.
      3657834.36      10190619.2      3657909.35     10190556.89
      3657872.35     10190462.59      3657988.68     10190399.51
       3658067.2     10190431.88      3658087.96     10190397.22
       3658057.7     10190338.87      3658126.65     10190313.73
      3658239.23     10190436.84      3658335.38     10190457.69
      3658388.57     10190344.76       3658670.5     10190106.45
       3658761.8     10190120.47      3658792.55     10190093.86

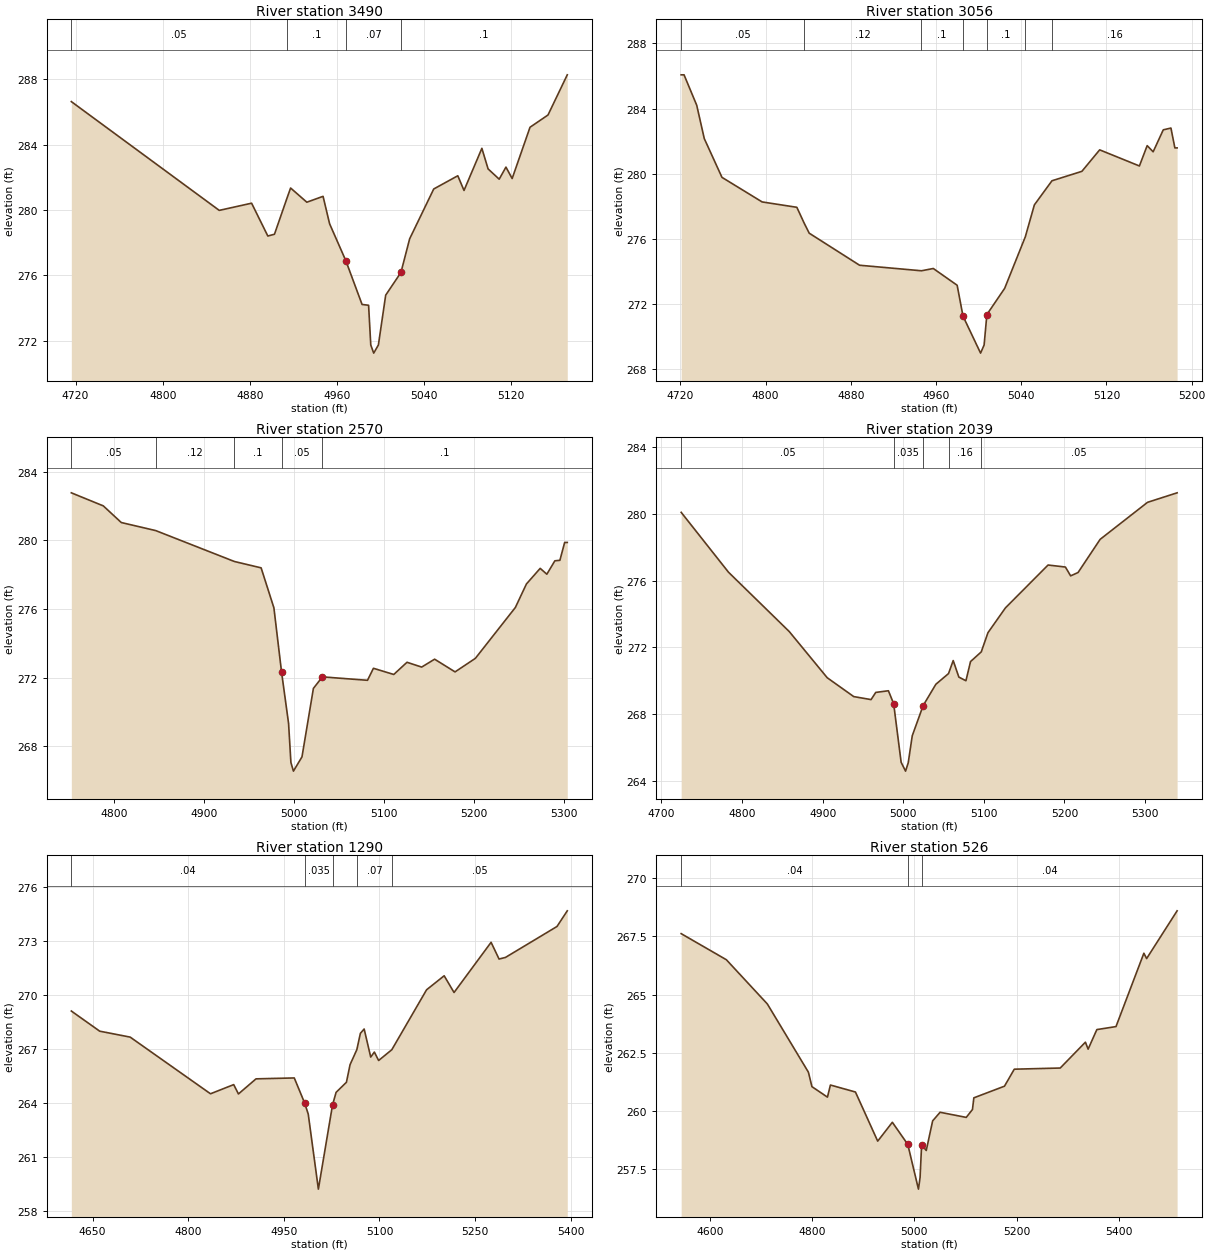
Type RM Length L Ch R = 1 ,3490    ,434,434,434
BEGIN DESCRIPTION:
UNT007 IN ROCK 5.0
END DESCRIPTION:
XS GIS Cut Line= 3
      3657142.13     10191591.66      3656910.43     10191431.02
      3656756.72     10191350.87
#Sta/Elev= 30
  4716.1  286.64  4851.9  279.98  4881.6  280.42  4896.5  278.41  4902.6  278.52
  4914.3  280.77  4917.4  281.35  4932.3  280.48  4947.2  280.84  4953.2  279.16
  4968.1   276.9    4983  274.22    4989  274.17    4991  271.74  4993.7  271.24
    4998  271.74  5004.7  274.79  5018.7  276.18  5026.7  278.24  5048.8  281.29
  5070.9   282.1  5076.6   281.2    5093  283.78  5098.7  282.52  5108.9  281.89
  5115.1  282.63  5120.8  281.93  5137.2  285.07  5153.7  285.82  5171.4  288.28
#Mann= 4 ,-1 , 0
  4716.1     .05       0  4914.3      .1       0  4968.1     .07       0
  5018.7      .1       0
Bank Sta=4968.1,5018.7
XS Rating Curve= 0 ,0
Exp/Cntr=0.3,0.1

Type RM Length L Ch R = 1 ,3056    ,486,486,486
BEGIN DESCRIPTION:
UNT007 IN ROCK 4.0
END DESCRIPTION:
XS GIS Cut Line= 3
      3657392.13     10191241.65      3657198.04     10191159.48
       3656970.5     10191044.75
#Sta/Elev= 30
  4720.7  286.07  4723.4  286.07  4735.3   284.2  4742.4  282.15    4759  279.77
  4796.7  278.26  4829.3  277.93  4836.3  276.94  4840.9  276.34  4888.2  274.37
  4946.3  274.03  4957.4  274.17  4979.8  273.14  4985.3  271.24  5001.8  268.97
  5005.1  269.47  5007.7  271.34  5024.4  272.95  5043.8  276.12  5052.3  278.08
  5068.8  279.56  5096.9  280.14  5113.6  281.46  5150.9  280.47  5158.2  281.72
  5163.8  281.34  5173.3  282.69  5180.5   282.8  5184.2  281.58  5186.3  281.58
#Mann= 7 ,-1 , 0
  4720.7     .05       0  4836.3     .12       0  4946.3      .1       0
  4985.3     .05       0  5007.7      .1       0  5043.8     .12       0
  5068.8     .16       0
Bank Sta=4985.3,5007.7
XS Rating Curve= 0 ,0
Exp/Cntr=0.3,0.1

Type RM Length L Ch R = 1 ,2570    ,531,531,531
BEGIN DESCRIPTION:
UNT007 IN ROCK 3.0
END DESCRIPTION:
XS GIS Cut Line= 3
      3657597.61     10190977.83      3657432.27     10190973.41
      3657092.09     10190791.63
#Sta/Elev= 30
  4752.4  282.76  4787.9     282  4807.9  281.03  4846.2  280.56  4933.6  278.76
  4963.3  278.39  4977.5  276.06    4986  272.32  4993.8  269.33  4996.4  267.05
  4999.2  266.55  5008.7  267.38  5021.4  271.37  5031.4  272.04  5081.5  271.84
  5088.1  272.54  5110.7  272.18  5125.4  272.89  5141.7  272.61  5156.1  273.07
  5178.8  272.33  5201.4  273.12  5245.8  276.08  5258.1  277.45  5273.4  278.36
  5280.8  278.02  5289.7   278.8  5295.3  278.83  5300.6  279.87  5303.5  279.87
#Mann= 5 ,-1 , 0
  4752.4     .05       0  4846.2     .12       0  4933.6      .1       0
    4986     .05       0  5031.4      .1       0
Bank Sta=4986,5031.4
XS Rating Curve= 0 ,0
Exp/Cntr=0.3,0.1

Type RM Length L Ch R = 1 ,2039    ,749,749,749
BEGIN DESCRIPTION:
UNT007 IN ROCK 2.0
END DESCRIPTION:
XS GIS Cut Line= 3
       3657642.1     10190891.61      3657589.87     10190687.19
      3657387.32     10190337.28
#Sta/Elev= 30
  4724.5  280.09  4783.2   276.5  4858.6  272.94  4905.7  270.17  4938.6  269.04
  4960.1  268.86  4965.9  269.29  4981.6  269.39  4988.1  268.62  4997.4   265.1
  5002.9  264.57  5006.2  265.07  5011.2  266.69  5024.7   268.5  5040.5  269.78
  5056.2  270.42    5062   271.2    5069  270.21  5077.8  269.99  5083.5  271.14
  5096.8  271.72  5105.1  272.87  5126.8  274.36  5179.7  276.93  5201.2  276.81
  5207.7  276.28  5216.9  276.48  5244.3  278.47  5303.1  280.69  5339.8  281.26
#Mann= 5 ,-1 , 0
  4724.5     .05       0  4988.1    .035       0  5024.7     .05       0
  5056.2     .16       0  5096.8     .05       0
Bank Sta=4988.1,5024.7
XS Rating Curve= 0 ,0
Exp/Cntr=0.3,0.1

Type RM Length L Ch R = 1 ,1290    ,764,764,764
BEGIN DESCRIPTION:
Mapping XS eca041b3
END DESCRIPTION:
XS GIS Cut Line= 4
      3657980.69     10190795.46       3658013.3     10190610.68
      3657822.05     10190256.43      3657636.17     10190230.49
#Sta/Elev= 30
  4616.7   269.1  4661.2  267.98    4709  267.65    4835   264.5  4871.4  265.01
  4878.8  264.49  4906.4  265.33  4966.4  265.38  4982.6  263.99  4988.3  263.37
  5004.2   259.2  5026.4  263.88    5032  264.58  5048.2  265.14  5053.9  266.12
  5064.5  266.95  5070.1  267.86    5076   268.1  5086.3  266.54    5092  266.82
  5098.7  266.35  5119.4  266.95  5173.9  270.28  5201.5  271.06    5217  270.13
  5275.1  272.92  5287.6  271.99  5297.7  272.08  5378.5   273.8  5394.6  274.67
#Mann= 5 ,-1 , 0
  4616.7     .04       0  4982.6    .035       0  5026.4     .04       0
  5064.5     .07       0  5119.4     .05       0
Bank Sta=4982.6,5026.4
XS Rating Curve= 0 ,0
Exp/Cntr=0.3,0.1

Type RM Length L Ch R = 1 ,526     ,0,0,0
BEGIN DESCRIPTION:
UNT007 IN ROCK 1.0
END DESCRIPTION:
XS GIS Cut Line= 4
       3658282.8     10190743.25      3658450.14      10190454.2
      3658321.92      10190258.6      3657945.44     10190113.63
#Sta/Elev= 30
  4543.2  267.62  4631.7   266.5    4712   264.6  4792.4  261.67  4799.3  261.05
  4829.7   260.6  4835.5  261.12  4884.5  260.82  4928.1  258.71  4956.8  259.52
    4987  258.57  5007.9  256.65  5011.1  257.15  5014.1  258.55  5023.2  258.31
  5035.7  259.58  5050.3  259.95  5101.5  259.73  5113.7  260.07  5116.4  260.57
  5176.4  261.07  5195.6   261.8  5285.6  261.85  5334.9  262.96  5340.2  262.66
  5357.3   263.5  5394.8  263.63  5449.4  266.78  5454.8  266.55  5514.5   268.6
#Mann= 3 , 0 , 0
  4543.2     .04       0    4987    .035       0  5014.1     .04       0
Bank Sta=4987,5014.1
XS Rating Curve= 0 ,0
Exp/Cntr=0.3,0.1

Chan Stop Cuts=-1
Use User Specified Reach Order=0
Composite Channel Slope=5