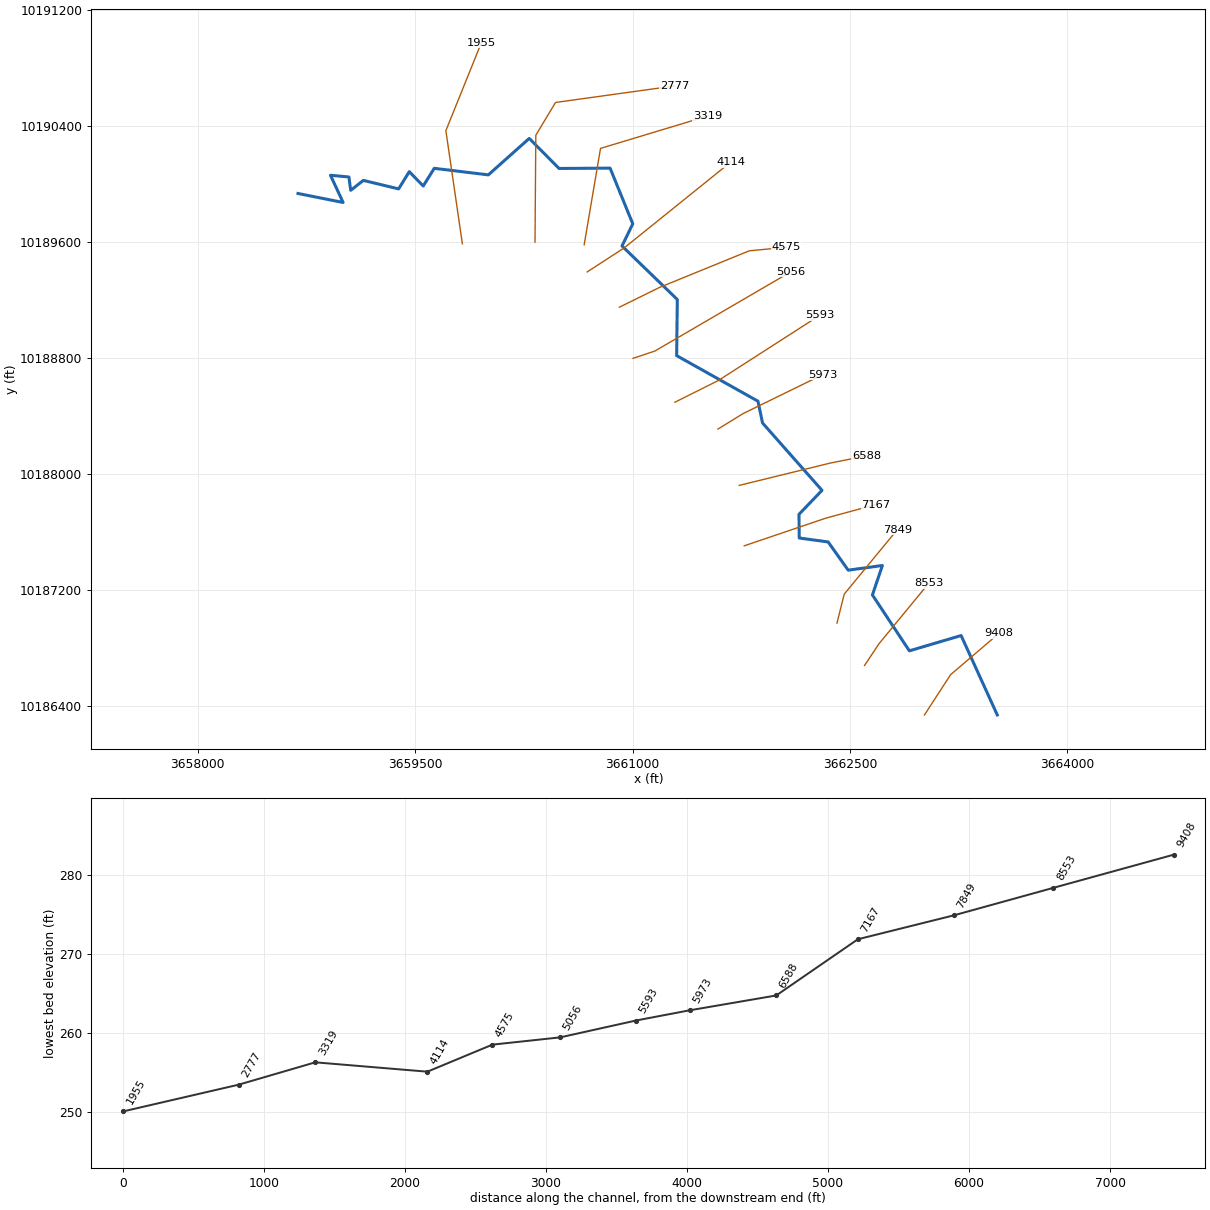
--- UNT008 IN ROCK.prj (project) ---

Proj Title=UNT008 IN ROCK Base Level Engineering
Current Plan=p01
Default Exp/Contr=0.3,0.1
English Units
Geom File=g01
Flow File=f01
Plan File=p01
Y Axis Title=Elevation
X Axis Title(PF)=Main Channel Distance
X Axis Title(XS)=Station
BEGIN DESCRIPTION:
UNT008 IN ROCK
END DESCRIPTION:
DSS Export Rating Curves= 0
DSS Export Rating Curve Sorted= 0
DSS Export Volume Flow Curves= 0
DXF OffsetX= 0
DXF OffsetY= 0
DXF ScaleX= 1
DXF ScaleY= 10

--- UNT008 IN ROCK.p01 (plan) ---

Plan Title=Multiple Run
Short Identifier=Multiple
Geom File=g01
Flow File=f01
Subcritical Flow
K Sum by GR= 0
Std Step Tol= 0.01
Critical Tol= 0.01
Num of Std Step Trials= 20
Max Error Tol= 0.3
Flow Tol Ratio= 0.001
Split Flow NTrial= 30
Split Flow Tol= 0.02
Split Flow Ratio= 0.02
Log Output Level= 0
Friction Slope Method= 1
Unsteady Friction Slope Method= 2
Unsteady Bridges Friction Slope Method= 1
Parabolic Critical Depth
Global Vel Dist=  1 , 1 , 1
Global Log Level= 0
CheckData=True
Encroach Param= -1, 0, 0, 0
BEGIN DESCRIPTION:
Multiple Run
END DESCRIPTION:

--- UNT008 IN ROCK.f01 (steady flow) ---

Flow Title=Multiple
Number of Profiles=7
Profile Names=10-year,25-year,50-year,1pct_min,100-year,1pct_plu,500-year
River Rch & RM= UNT008 IN ROCK,Reach-1,9408
     877    1202    1472    1320    1786    2415    2626
River Rch & RM= UNT008 IN ROCK,Reach-1,4114
    1052    1451    1784    1605    2170    2935    3212
Boundary for River Rch & Prof#=UNT008 IN ROCK,Reach-1,1
Up Type=0
Dn Type=3
Dn Slope=0.005
Boundary for River Rch & Prof#=UNT008 IN ROCK,Reach-1,2
Up Type=0
Dn Type=3
Dn Slope=0.005
Boundary for River Rch & Prof#=UNT008 IN ROCK,Reach-1,3
Up Type=0
Dn Type=3
Dn Slope=0.005
Boundary for River Rch & Prof#=UNT008 IN ROCK,Reach-1,4
Up Type=0
Dn Type=3
Dn Slope=0.005
Boundary for River Rch & Prof#=UNT008 IN ROCK,Reach-1,5
Up Type=0
Dn Type=3
Dn Slope=0.005
Boundary for River Rch & Prof#=UNT008 IN ROCK,Reach-1,6
Up Type=0
Dn Type=3
Dn Slope=0.005
Boundary for River Rch & Prof#=UNT008 IN ROCK,Reach-1,7
Up Type=0
Dn Type=3
Dn Slope=0.005

--- UNT008 IN ROCK.g01 (geometry) ---

Geom Title=Existing Conditions
Program Version=4.10

River Reach=UNT008 IN ROCK  ,Reach-1
Reach XY= 30
        3663516.     10186334.92      3663266.63     10186882.58
       3662909.5     10186777.12      3662654.76     10187162.41
      3662723.47     10187365.56      3662487.66     10187333.38
      3662349.48     10187528.02      3662149.95     10187555.35
      3662148.21     10187718.79       3662307.1     10187884.09
       3661896.8     10188348.52      3661865.38     10188498.66
      3661304.28     10188813.37      3661308.88     10189200.41
      3660927.37     10189569.44      3661001.55      10189722.2
      3660845.19     10190106.43      3660493.17      10190104.1
      3660287.47      10190311.4      3660005.32     10190059.94
      3659632.22     10190105.14      3659556.16     10189983.04
      3659459.91     10190081.93      3659386.33     10189963.22
      3659143.11     10190021.84      3659055.89     10189953.39
      3659043.37     10190045.44       3658916.3      10190057.2
      3659003.36     10189869.67      3658692.11     10189931.64

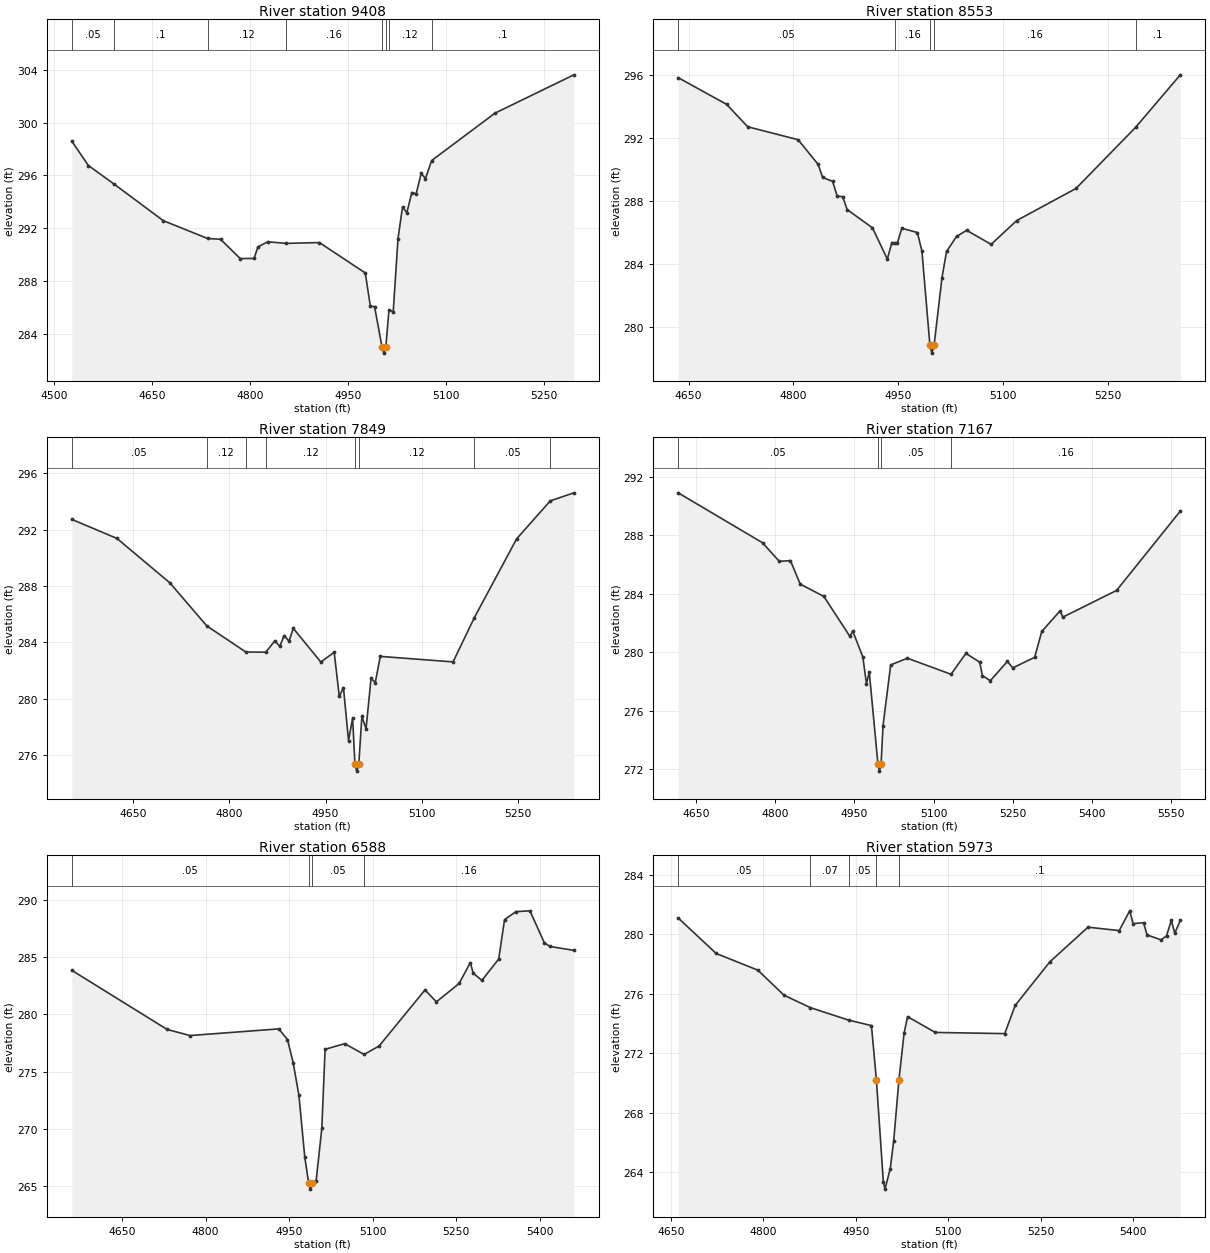
Type RM Length L Ch R = 1 ,9408    ,855,855,855
BEGIN DESCRIPTION:
UNT008 IN ROCK 13.0
END DESCRIPTION:
XS GIS Cut Line= 3
      3663013.57     10186334.79      3663194.14      10186612.6
      3663526.93     10186896.85
#Sta/Elev= 30
  4526.8   298.6  4552.3  296.75  4591.3  295.36  4666.9  292.58  4734.8  291.23
  4754.6  291.17  4784.8  289.71  4805.9  289.72  4811.9  290.59    4827  290.98
    4855  290.86    4906  290.92  4976.3  288.62    4984  286.12  4990.5  286.07
  5001.8  283.05  5004.6  282.55  5007.8  283.05  5012.6  285.83  5019.1  285.69
  5026.4  291.22  5033.4  293.63  5039.9  293.18  5047.6  294.71  5054.2  294.61
  5061.9  296.15  5068.5  295.77  5077.9  297.13    5175  300.72  5295.8  303.62
#Mann= 8 ,-1 , 0
  4526.8     .05       0  4591.3      .1       0  4734.8     .12       0
    4855     .16       0  5001.8     .07       0  5007.8     .16       0
  5012.6     .12       0  5077.9      .1       0
Bank Sta=5001.8,5007.8
XS Rating Curve= 0 ,0
Exp/Cntr=0.3,0.1

Type RM Length L Ch R = 1 ,8553    ,704,704,704
BEGIN DESCRIPTION:
UNT008 IN ROCK 12.0
END DESCRIPTION:
XS GIS Cut Line= 3
      3662600.41     10186676.33      3662700.44     10186826.36
      3663042.11     10187241.65
#Sta/Elev= 30
  4635.2   295.8  4704.5  294.11  4734.6  292.69  4806.7  291.87  4835.3  290.31
  4841.8  289.48  4856.1  289.23  4862.6   288.3  4870.5  288.26  4876.9  287.44
    4913  286.29  4934.3  284.31  4940.8  285.35  4945.3  285.34  4948.7  285.34
  4955.1  286.26  4977.3  285.99  4983.8  284.81  4995.2  278.85  4997.9  278.35
  5001.2  278.85  5012.5  283.14    5019  284.79  5033.3  285.74  5047.7  286.13
  5082.8  285.24  5119.4  286.75  5204.1  288.78  5289.3  292.65  5353.3  295.98
#Mann= 5 ,-1 , 0
  4635.2     .05       0  4945.3     .16       0  4995.2     .07       0
  5001.2     .16       0  5289.3      .1       0
Bank Sta=4995.2,5001.2
XS Rating Curve= 0 ,0
Exp/Cntr=0.3,0.1

Type RM Length L Ch R = 1 ,7849    ,682,682,682
BEGIN DESCRIPTION:
UNT008 IN ROCK 11.0
END DESCRIPTION:
XS GIS Cut Line= 3
      3662410.16     10186968.03      3662460.16     10187168.03
      3662826.12     10187612.63
#Sta/Elev= 30
  4554.8  292.72  4625.1  291.37  4707.6  288.22  4765.1  285.17  4825.9  283.32
    4857  283.31    4871  284.11  4878.9  283.72  4885.4  284.49  4893.2  284.09
  4899.7     285  4942.7  282.61  4963.5   283.3  4971.4  280.17  4977.9   280.8
  4985.8  277.05  4992.2  278.63  4995.8  275.38  4998.5  274.88  5001.8  275.38
  5006.6  278.76  5013.1  277.89  5020.9  281.46  5027.4  281.15  5035.3  283.01
  5148.6  282.62  5181.8  285.76  5247.6  291.34    5300  294.03  5336.8   294.6
#Mann= 8 ,-1 , 0
  4554.8     .05       0  4765.1     .12       0  4825.9     .16       0
    4857     .12       0  4995.8     .07       0  5001.8     .12       0
  5181.8     .05       0    5300      .1       0
Bank Sta=4995.8,5001.8
XS Rating Curve= 0 ,0
Exp/Cntr=0.3,0.1

Type RM Length L Ch R = 1 ,7167    ,579,579,579
BEGIN DESCRIPTION:
UNT008 IN ROCK 10.0
END DESCRIPTION:
XS GIS Cut Line= 3
      3661770.57      10187501.5      3662334.94      10187692.8
      3662678.67     10187785.78
#Sta/Elev= 30
  4615.8   290.9  4775.8  287.48  4807.5  286.21  4828.6  286.26  4847.2  284.65
    4892  283.81  4941.4  281.07  4946.7  281.44  4965.9  279.67  4972.8  277.83
  4978.1  278.63  4994.5  272.35  4997.3  271.85  5000.5  272.35  5004.2  274.97
  5018.7  279.12  5050.3  279.58  5133.1  278.48  5161.3  279.91  5187.4  279.31
  5192.7  278.39  5207.6  278.04  5239.9  279.36  5250.2  278.92  5291.7  279.64
  5305.1  281.41  5339.8  282.82    5345  282.39    5447  284.22  5567.8  289.65
#Mann= 4 ,-1 , 0
  4615.8     .05       0  4994.5     .03       0  5000.5     .05       0
  5133.1     .16       0
Bank Sta=4994.5,5000.5
XS Rating Curve= 0 ,0
Exp/Cntr=0.3,0.1

Type RM Length L Ch R = 1 ,6588    ,615,615,615
BEGIN DESCRIPTION:
UNT008 IN ROCK 9.0
END DESCRIPTION:
XS GIS Cut Line= 3
      3661735.78     10187918.14      3662364.33      10188072.2
      3662614.32      10188122.2
#Sta/Elev= 30
  4559.5  283.83  4730.8  278.67  4771.9  278.14  4931.4  278.72    4947  277.79
  4957.3  275.76  4967.6  272.91  4978.1  267.53  4985.2  265.24  4987.9  264.74
  4991.2  265.24  4998.4  265.42  5008.7  270.03  5014.6  276.94  5049.9  277.43
  5084.7  276.49  5111.7  277.23  5194.1  282.12  5214.6  281.08  5255.4  282.68
  5275.5  284.51  5280.6  283.59  5296.2  282.95  5326.5  284.81    5337  288.25
  5357.4  288.95  5382.6  289.02  5408.3  286.25  5418.5  285.91  5461.6  285.57
#Mann= 4 ,-1 , 0
  4559.5     .05       0  4985.2     .03       0  4991.2     .05       0
  5084.7     .16       0
Bank Sta=4985.2,4991.2
XS Rating Curve= 0 ,0
Exp/Cntr=0.3,0.1

Type RM Length L Ch R = 1 ,5973    ,380,380,380
BEGIN DESCRIPTION:
UNT008 IN ROCK 8.0
END DESCRIPTION:
XS GIS Cut Line= 3
      3661589.99     10188307.05       3661762.6     10188413.49
      3662312.21     10188682.05
#Sta/Elev= 30
  4661.9   281.1  4723.6  278.71  4791.1  277.59  4833.7   275.9  4876.3  275.07
  4938.3  274.23  4975.4  273.86  4983.4  270.23  4994.7  263.36  4997.4  262.86
  5005.9  264.24  5011.5  266.11    5020  270.22  5028.4  273.36    5034  274.46
    5079   273.4  5191.6  273.32  5208.6  275.22  5264.8  278.15  5326.7  280.48
  5377.3  280.25  5394.3  281.58  5399.8  280.72  5416.8  280.78  5422.4  279.96
  5444.9  279.63    5454  279.89  5461.8  280.94  5467.4  280.08  5476.4  280.93
#Mann= 5 ,-1 , 0
  4661.9     .05       0  4876.3     .07       0  4938.3     .05       0
  4983.4     .07       0    5020      .1       0
Bank Sta=4983.4,5020
XS Rating Curve= 0 ,0
Exp/Cntr=0.3,0.1

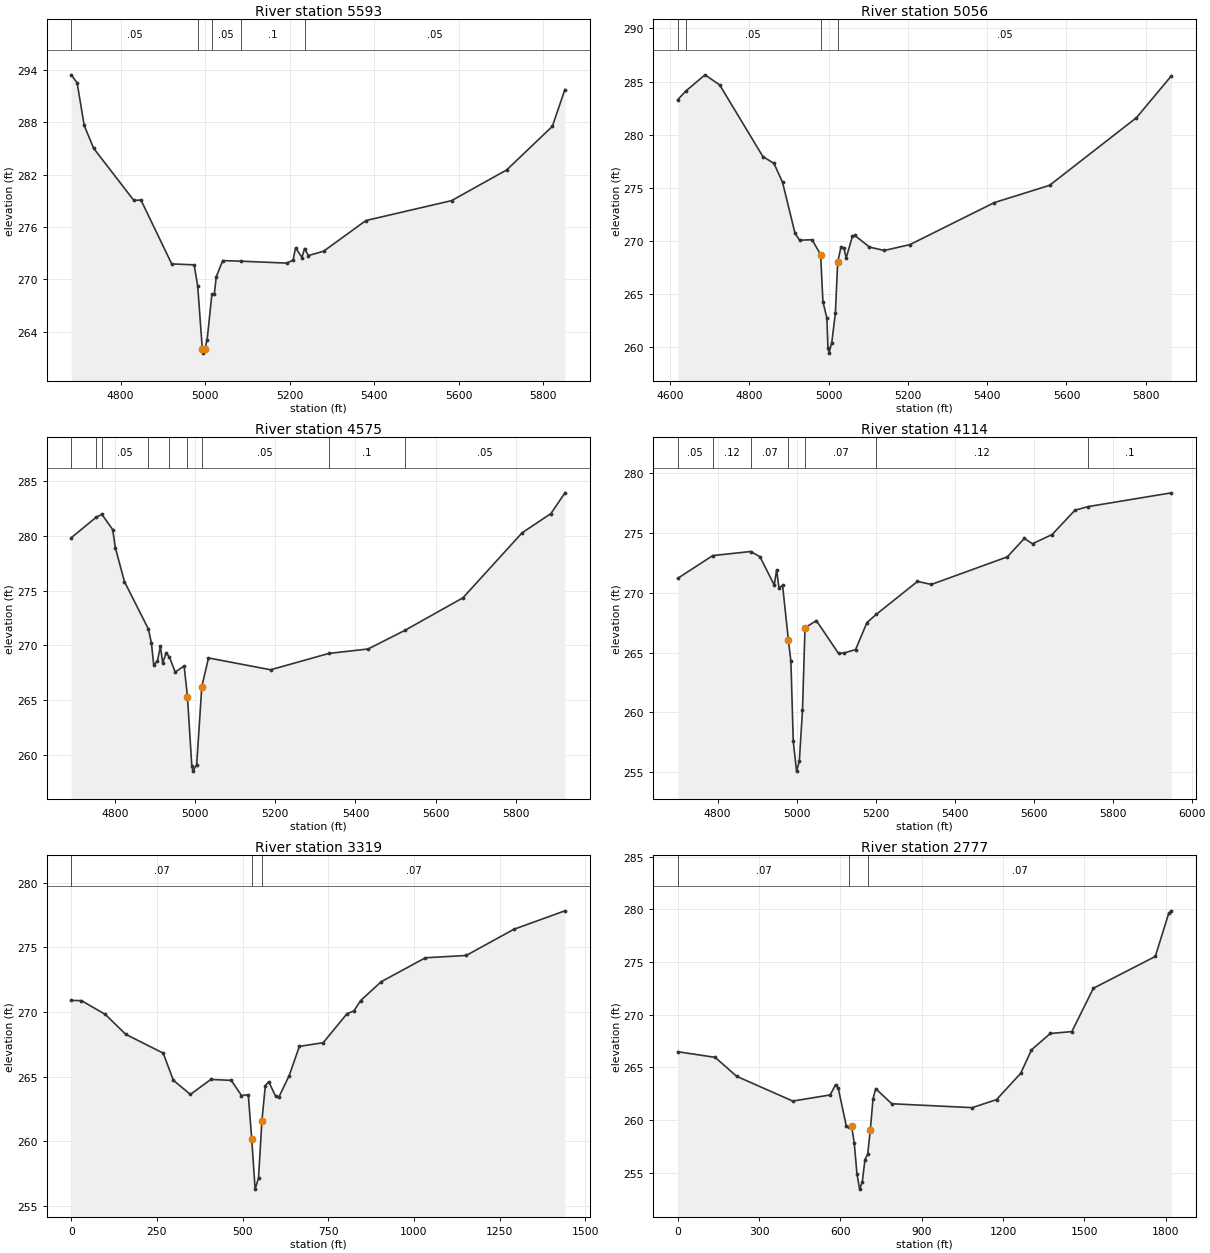
Type RM Length L Ch R = 1 ,5593    ,537,537,537
BEGIN DESCRIPTION:
UNT008 IN ROCK 7.0
END DESCRIPTION:
XS GIS Cut Line= 3
      3661292.12     10188491.65      3661592.11     10188641.64
      3662292.14     10189091.66
#Sta/Elev= 30
  4683.3  293.41  4697.3  292.49    4714  287.62  4736.4     285  4831.4  279.04
  4848.2  279.09  4920.9  271.78    4974  271.67  4982.4  269.27  4993.3  262.07
  4996.1  261.57  4999.3  262.07  5004.7  263.09  5015.9  268.28  5021.7  268.28
  5026.3   270.3  5041.5  272.16  5083.7  272.09  5192.7  271.87  5207.9   272.2
  5213.9  273.62    5229  272.51  5235.1  273.54  5244.2  272.73  5280.2  273.23
  5380.3  276.74    5583  279.02  5713.2  282.53  5821.1  287.51  5850.9  291.73
#Mann= 5 ,-1 , 0
  4683.3     .05       0  4982.4    .035       0  5015.9     .05       0
  5083.7      .1       0  5235.1     .05       0
Bank Sta=4993.3,4999.3
XS Rating Curve= 0 ,0
Exp/Cntr=0.3,0.1

Type RM Length L Ch R = 1 ,5056    ,481,481,481
BEGIN DESCRIPTION:
UNT008 IN ROCK 6.0
END DESCRIPTION:
XS GIS Cut Line= 3
      3661003.19     10188794.41      3661153.22     10188844.42
      3662092.13     10189391.66
#Sta/Elev= 30
  4619.8  283.29  4640.6  284.12  4688.6  285.63  4725.5  284.68  4834.5  277.94
  4862.6  277.29  4884.1  275.51  4915.6  270.71  4927.1  270.07  4958.6  270.11
  4980.1  268.71  4985.9  264.29  4995.8  262.75  4998.6  259.94  5001.3  259.44
  5008.2  260.44  5017.3  263.21  5023.1  267.98  5031.3  269.41  5038.8  269.31
  5044.6  268.41  5060.3  270.44  5066.1  270.52  5103.3  269.42  5140.5   269.1
  5205.1  269.65  5418.4  273.61  5557.4  275.23  5776.6   281.6  5864.7  285.54
#Mann= 4 ,-1 , 0
  4619.8     .16       0  4640.6     .05       0  4980.1    .035       0
  5023.1     .05       0
Bank Sta=4980.1,5023.1
XS Rating Curve= 0 ,0
Exp/Cntr=0.3,0.1

Type RM Length L Ch R = 1 ,4575    ,461,461,461
BEGIN DESCRIPTION:
UNT008 IN ROCK 5.0
END DESCRIPTION:
XS GIS Cut Line= 4
      3660909.45     10189147.33      3661186.64     10189283.87
      3661805.26     10189536.21      3662058.42     10189560.24
#Sta/Elev= 30
    4691  279.82  4753.2  281.69  4767.5  281.95  4794.3  280.57  4801.2  278.89
  4823.7  275.82  4883.5  271.49  4891.1  270.19  4896.7  268.23  4905.8  268.53
  4913.5   269.9  4919.1  268.41  4928.1  269.32    4936  268.92  4950.4  267.56
  4972.6  268.12  4980.9  265.33  4991.7  259.02  4994.4  258.52  5003.9   259.1
  5016.7  266.23  5033.4  268.85  5188.4  267.77  5333.4  269.26  5431.7  269.67
  5523.4  271.37  5668.1  274.34  5815.6  280.27  5887.6  282.03  5922.4  283.92
#Mann= 9 ,-1 , 0
    4691     .05       0  4753.2     .16       0  4767.5     .05       0
  4883.5      .1       0    4936     .05       0  4980.9    .035       0
  5016.7     .05       0  5333.4      .1       0  5523.4     .05       0
Bank Sta=4980.9,5016.7
XS Rating Curve= 0 ,0
Exp/Cntr=0.3,0.1

Type RM Length L Ch R = 1 ,4114    ,795,795,795
BEGIN DESCRIPTION:
UNT008 IN ROCK 4.0
END DESCRIPTION:
XS GIS Cut Line= 3
      3660687.21     10189390.38      3660942.11     10189556.01
      3661678.54     10190149.03
#Sta/Elev= 30
  4699.3   271.2  4787.9   273.1    4884  273.44  4907.3  273.01  4943.5  270.64
  4949.5  271.89  4955.6  270.38  4964.6  270.62  4979.4  266.03  4985.7  264.27
  4991.7  257.58    5000   255.1    5007  255.91    5015  260.18  5021.4  267.07
  5050.2  267.67  5106.2  264.93  5120.6  264.97  5149.4  265.25  5178.1   267.5
  5201.3  268.18  5306.1  270.94  5341.3  270.69  5533.3  272.99  5576.4  274.53
  5597.3  274.09  5646.9  274.86  5704.4  276.88  5737.8  277.19  5948.8  278.34
#Mann= 7 ,-1 , 0
  4699.3     .05       0  4787.9     .12       0    4884     .07       0
  4979.4     .05       0  5021.4     .07       0  5201.3     .12       0
  5737.8      .1       0
Bank Sta=4979.4,5021.4
XS Rating Curve= 0 ,0
Exp/Cntr=0.3,0.1

Type RM Length L Ch R = 1 ,3319    ,542,542,542
BEGIN DESCRIPTION:
UNT008 IN ROCK 3.0
END DESCRIPTION:
XS GIS Cut Line= 3
     3660666.366    10189577.875     3660779.098    10190242.595
     3661516.266    10190465.146
#Sta/Elev= 30
       0270.898129.81127270.8833 99.3709269.8186158.9935268.2757268.3015266.8176
298.1127264.7103347.7982263.6192407.4207264.7788467.0432264.7084496.8545263.5345
516.7287263.5995526.6658260.1744536.6029256.2834  546.54257.1373556.4771261.5845
566.4142264.2888576.3513264.6048596.2254263.4845606.1625263.4217635.9738265.0756
 665.785267.3376735.3276267.6251804.8672 269.874824.7357270.0819844.6042270.8897
904.2096272.34111033.355274.20031152.566274.38111291.645276.40881440.658277.8382
#Mann= 3 , 0 , 0
       0     .07       0526.6658     .05       0556.4771     .07       0
Bank Sta=526.6658,556.4771
XS Rating Curve= 0 ,0
Exp/Cntr=0.3,0.1

Type RM Length L Ch R = 1 ,2777    ,822,822,822
BEGIN DESCRIPTION:
UNT008 IN ROCK 2.0
END DESCRIPTION:
XS GIS Cut Line= 4
     3660327.214    10189595.698     3660332.775    10190333.252
     3660468.718    10190559.301     3661289.704    10190673.479
#Sta/Elev= 30
       0266.4964138.1419265.9612217.0802264.1674 424.293261.8159562.4349262.3974
582.1695 263.369592.0368263.0461621.6386259.4781631.5059259.3451641.3732259.4512
651.2405257.8273661.1078254.9253 670.975 253.463680.8423254.1455690.7096256.2722
700.5769 256.751710.4442259.0793720.3115262.0043730.1787262.9918789.5049261.5611
1086.586261.1913 1175.94261.95331265.293264.45121305.006266.67571374.503268.2254
1453.929 268.4061533.354 272.5181761.702275.53131811.343279.63091821.271279.8604
#Mann= 3 ,-1 , 0
       0     .07       0631.5059     .05       0700.5769     .07       0
Bank Sta=641.3732,710.4442
XS Rating Curve= 0 ,0
Exp/Cntr=0.3,0.1

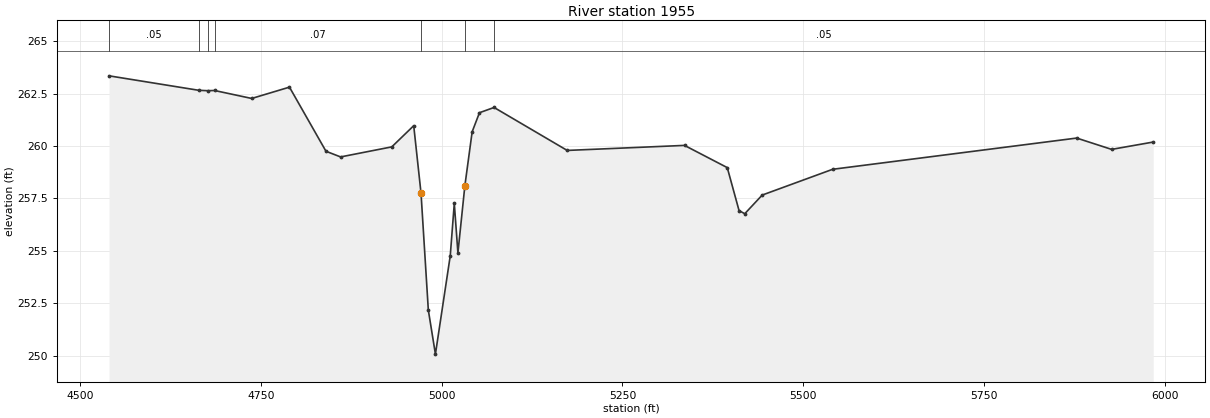
Type RM Length L Ch R = 1 ,1955    ,0,0,0
BEGIN DESCRIPTION:
UNT008 IN ROCK 1.0
END DESCRIPTION:
XS GIS Cut Line= 3
      3659826.09     10189584.78      3659712.27      10190364.9
      3659957.58     10190972.58
#Sta/Elev= 30
  4540.1  263.35  4664.1  262.66  4676.5  262.64    4686  262.65  4737.4  262.27
  4789.6  262.81  4840.1  259.75  4860.3  259.48  4931.1  259.96  4961.4  260.97
  4971.5  257.75  4981.6  252.17  4991.4  250.07  5011.9  254.76  5017.5  257.26
  5022.5   254.9  5032.1   258.1  5042.2  260.68  5052.3  261.59  5072.5  261.84
  5173.6  259.79  5335.8  260.03  5394.9  258.97  5411.2  256.92  5419.1  256.77
  5443.2  257.66  5540.6  258.89    5878  260.38  5926.3  259.84  5983.8  260.19
#Mann= 7 ,-1 , 0
  4540.1     .05       0  4664.1     .12       0  4676.5     .05       0
    4686     .07       0  4971.5     .05       0  5032.1     .07       0
  5072.5     .05       0
Bank Sta=4971.5,5032.1
XS Rating Curve= 0 ,0
Exp/Cntr=0.3,0.1

Chan Stop Cuts=-1
Use User Specified Reach Order=0
Composite Channel Slope=5