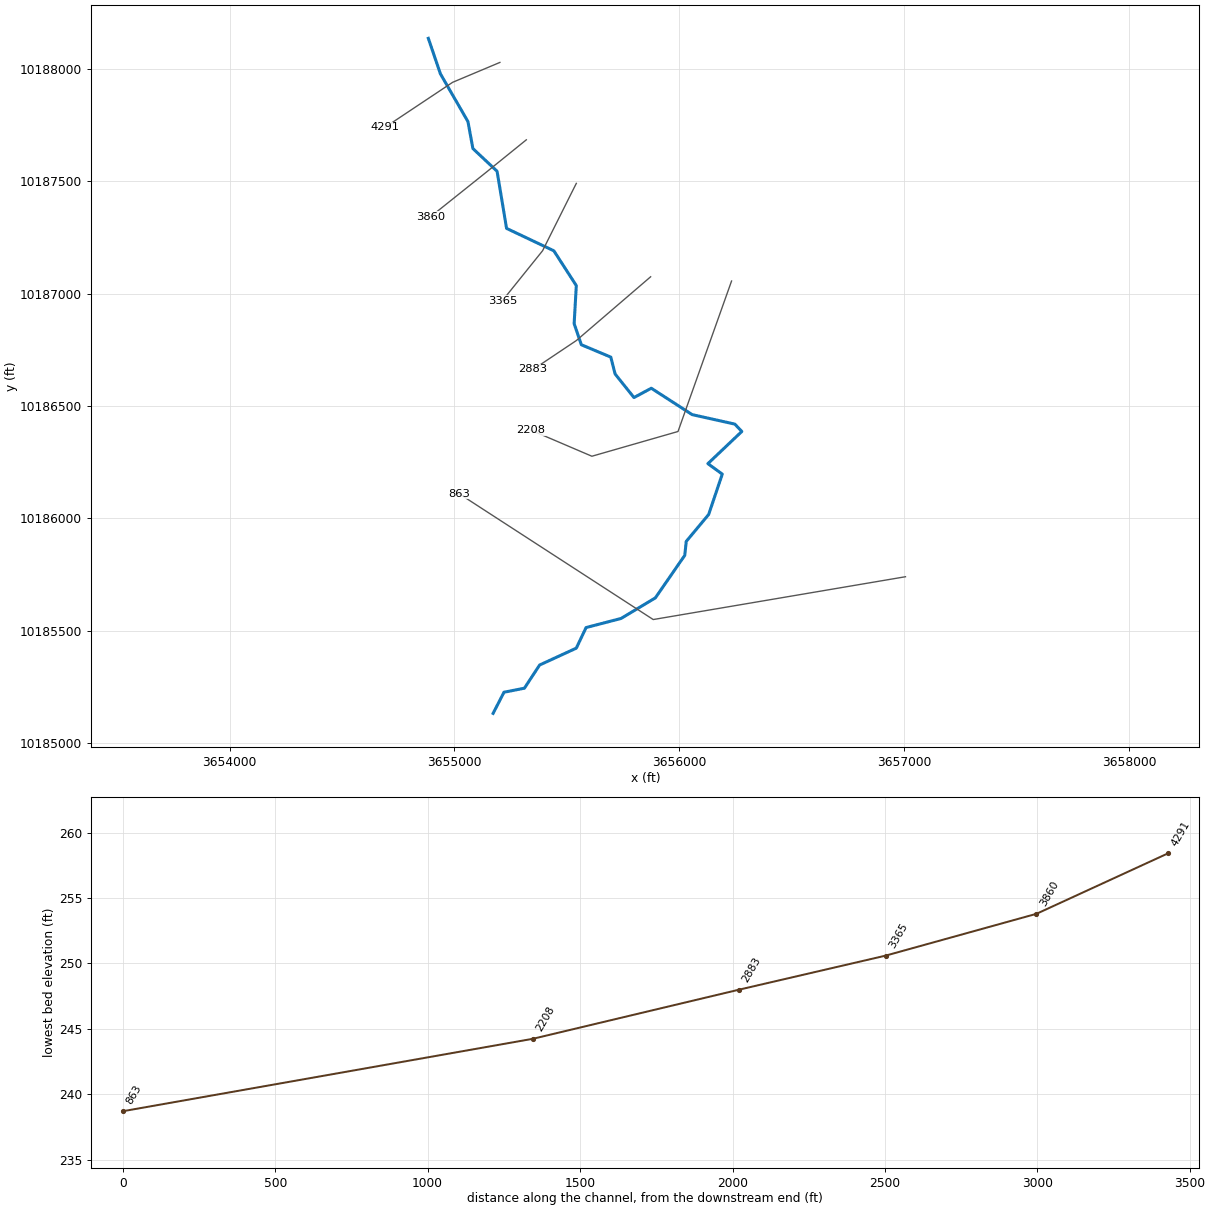
--- UNT009 IN ROCK.prj (project) ---

Proj Title=UNT009 IN ROCK Base Level Engineering
Current Plan=p01
Default Exp/Contr=0.3,0.1
English Units
Geom File=g01
Flow File=f01
Plan File=p01
Y Axis Title=Elevation
X Axis Title(PF)=Main Channel Distance
X Axis Title(XS)=Station
BEGIN DESCRIPTION:
UNT009 IN ROCK
END DESCRIPTION:
DSS Export Rating Curves= 0
DSS Export Rating Curve Sorted= 0
DSS Export Volume Flow Curves= 0
DXF OffsetX= 0
DXF OffsetY= 0
DXF ScaleX= 1
DXF ScaleY= 10

--- UNT009 IN ROCK.p01 (plan) ---

Plan Title=Multiple Run
Short Identifier=Multiple
Geom File=g01
Flow File=f01
Subcritical Flow
K Sum by GR= 0
Std Step Tol= 0.01
Critical Tol= 0.01
Num of Std Step Trials= 20
Max Error Tol= 0.3
Flow Tol Ratio= 0.001
Split Flow NTrial= 30
Split Flow Tol= 0.02
Split Flow Ratio= 0.02
Log Output Level= 0
Friction Slope Method= 1
Unsteady Friction Slope Method= 2
Unsteady Bridges Friction Slope Method= 1
Parabolic Critical Depth
Global Vel Dist=  1 , 1 , 1
Global Log Level= 0
CheckData=True
Encroach Param= -1, 0, 0, 0
BEGIN DESCRIPTION:
Multiple Run
END DESCRIPTION:

--- UNT009 IN ROCK.f01 (steady flow) ---

Flow Title=Multiple
Number of Profiles=7
Profile Names=10-year,25-year,50-year,1pct_min,100-year,1pct_plu,500-year
River Rch & RM= UNT009 IN ROCK,Reach-1,4291
     547     733     883     782    1058    1431    1517
Boundary for River Rch & Prof#=UNT009 IN ROCK,Reach-1,1
Up Type=0
Dn Type=3
Dn Slope=0.005
Boundary for River Rch & Prof#=UNT009 IN ROCK,Reach-1,2
Up Type=0
Dn Type=3
Dn Slope=0.005
Boundary for River Rch & Prof#=UNT009 IN ROCK,Reach-1,3
Up Type=0
Dn Type=3
Dn Slope=0.005
Boundary for River Rch & Prof#=UNT009 IN ROCK,Reach-1,4
Up Type=0
Dn Type=3
Dn Slope=0.005
Boundary for River Rch & Prof#=UNT009 IN ROCK,Reach-1,5
Up Type=0
Dn Type=3
Dn Slope=0.005
Boundary for River Rch & Prof#=UNT009 IN ROCK,Reach-1,6
Up Type=0
Dn Type=3
Dn Slope=0.005
Boundary for River Rch & Prof#=UNT009 IN ROCK,Reach-1,7
Up Type=0
Dn Type=3
Dn Slope=0.005

--- UNT009 IN ROCK.g01 (geometry) ---

Geom Title=Existing Conditions
Program Version=4.10

River Reach=UNT009 IN ROCK  ,Reach-1
Reach XY= 30
      3654884.08     10188137.46       3654937.8     10187979.29
      3655060.21     10187766.86      3655082.25     10187646.67
      3655189.77      10187545.5      3655231.95     10187291.21
      3655442.26     10187191.39      3655542.06     10187036.53
      3655532.53      10186866.9       3655564.5     10186773.06
      3655695.45     10186718.01      3655714.73     10186642.76
       3655798.6     10186537.97      3655875.55     10186579.43
      3656057.23     10186461.94      3656247.14     10186419.65
      3656278.17     10186386.94      3656127.29     10186243.63
      3656191.22       10186197.      3656130.72     10186017.15
      3656030.98     10185897.42      3656024.52     10185835.39
       3655893.7     10185645.96       3655741.1     10185554.26
      3655585.67     10185513.78      3655542.11     10185422.04
      3655379.04     10185347.04      3655311.35     10185243.74
      3655220.54     10185225.76      3655172.11     10185131.64

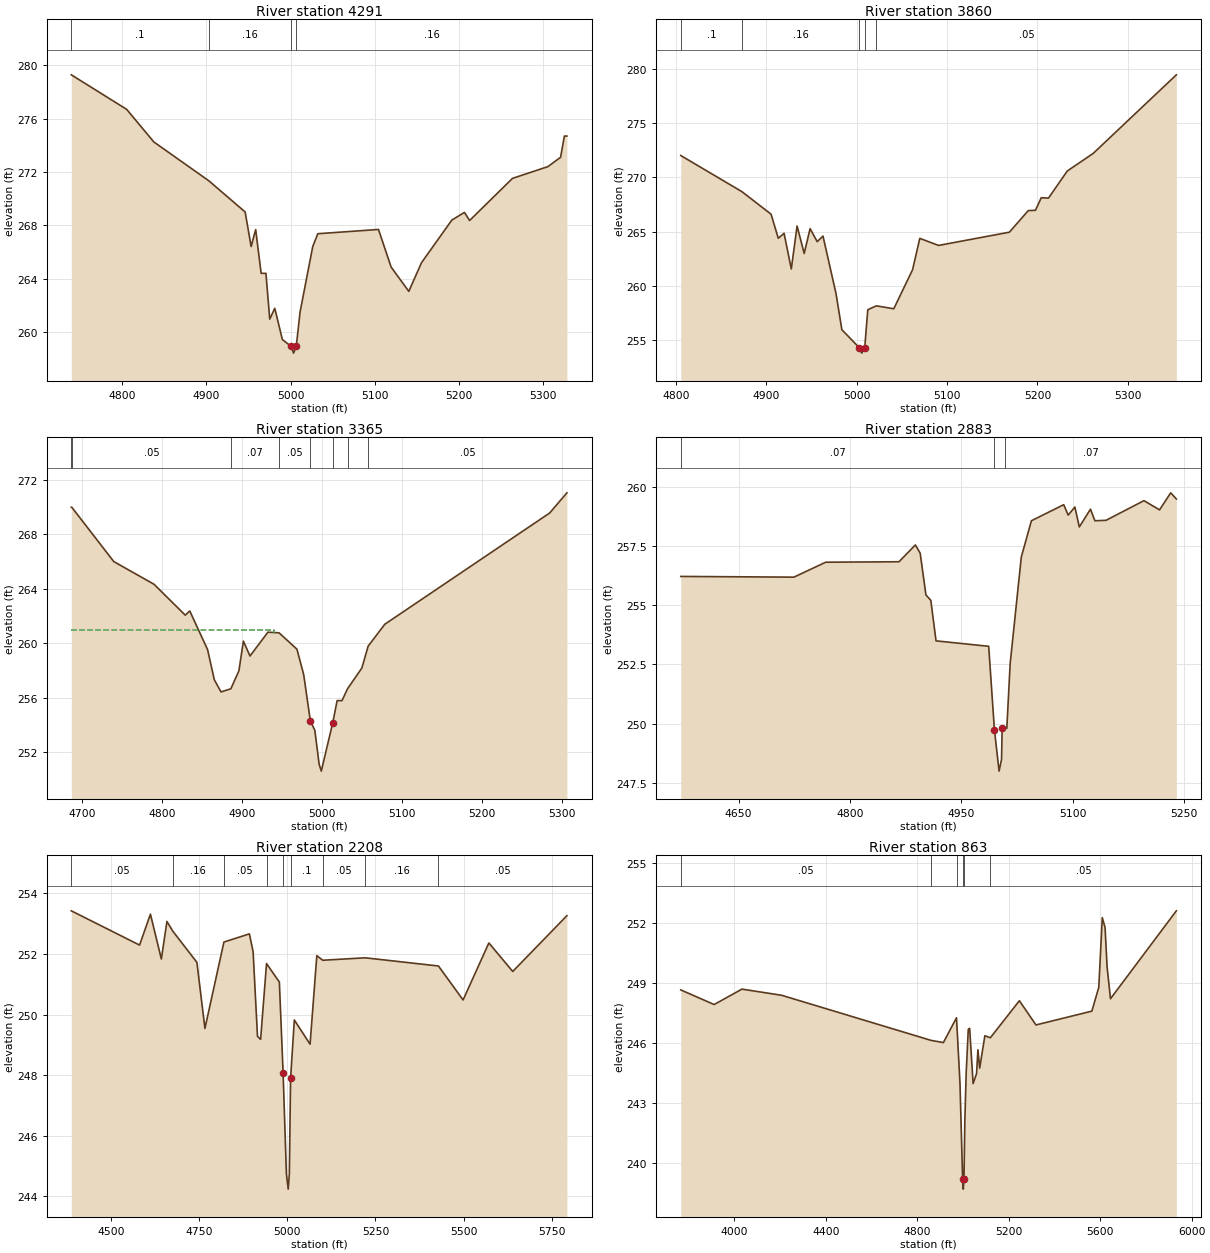
Type RM Length L Ch R = 1 ,4291    ,431,431,431
BEGIN DESCRIPTION:
UNT009 IN ROCK 6.0
END DESCRIPTION:
XS GIS Cut Line= 3
      3655202.39     10188030.21      3654992.11     10187941.64
      3654692.13     10187741.66
#Sta/Elev= 30
  4739.5  279.28  4805.3  276.69  4837.5  274.25  4902.8  271.34    4946     269
  4953.1  266.41  4958.5  267.68    4965   264.4  4970.7   264.4  4975.2  260.97
  4981.2  261.78  4990.2  259.44  5000.7  258.92  5003.5  258.42  5006.7  258.92
  5011.2  261.49  5026.3  266.41  5032.3  267.37  5104.4  267.69  5119.4  264.87
  5140.4  263.05  5155.5   265.2  5191.5  268.39  5206.5  268.97  5212.6  268.36
  5263.6  271.52  5305.7   272.4  5320.7   273.1  5325.2  274.69  5328.2  274.69
#Mann= 4 ,-1 , 0
  4739.5      .1       0  4902.8     .16       0  5000.7     .07       0
  5006.7     .16       0
Bank Sta=5000.7,5006.7
XS Rating Curve= 0 ,0
Exp/Cntr=0.3,0.1

Type RM Length L Ch R = 1 ,3860    ,495,495,495
BEGIN DESCRIPTION:
UNT009 IN ROCK 5.0
END DESCRIPTION:
XS GIS Cut Line= 3
      3655319.81     10187685.57      3655142.11     10187541.64
      3654892.14     10187341.67
#Sta/Elev= 30
  4805.1  272.02  4872.8  268.69  4905.1  266.61  4913.1  264.39  4919.5  264.85
  4927.5  261.56  4933.9  265.52  4941.8  262.99  4948.3  265.28  4956.2  264.08
  4962.6  264.59    4977   259.3  4983.5  255.96  5002.8   254.3  5005.5   253.8
  5008.8   254.3  5012.2   257.8  5021.7  258.16    5041  257.89  5061.8  261.49
  5069.8  264.38  5090.6  263.73    5169  264.95  5189.9  266.94  5197.9  266.97
  5204.3  268.13  5212.3  268.09  5233.1  270.59  5261.9  272.22  5353.9  279.46
#Mann= 5 ,-1 , 0
  4805.1      .1       0  4872.8     .16       0  5002.8     .07       0
  5008.8     .16       0  5021.7     .05       0
Bank Sta=5002.8,5008.8
XS Rating Curve= 0 ,0
Exp/Cntr=0.3,0.1

Type RM Length L Ch R = 1 ,3365    ,482,482,482
BEGIN DESCRIPTION:
UNT009 IN ROCK 4.0
END DESCRIPTION:
XS GIS Cut Line= 3
      3655542.12     10187491.67      3655392.11     10187191.64
      3655213.77     10186969.77
#Sta/Elev= 30
  4686.3  269.99  4686.9  269.99  4739.4     266  4789.8  264.33  4828.9  262.06
  4834.5  262.37  4856.8  259.53  4865.2  257.32  4873.6  256.42  4885.9  256.65
    4896  257.97  4901.6  260.15  4909.9  259.06  4932.3  260.81  4946.3  260.76
  4968.6  259.56    4977  257.71  4985.4  254.29    4991   253.6  4996.4   251.1
  4999.1   250.6  5013.4  254.15  5018.9  255.78    5025  255.78  5031.9  256.65
  5049.8  258.17  5057.7  259.78  5078.5  261.39  5284.9  269.57  5306.4  271.05
#Mann= 8 ,-1 , 0
  4686.3      .1       0  4686.9     .05       0  4885.9     .07       0
  4946.3     .05       0  4985.4    .035       0  5013.4     .05       0
  5031.9     .07       0  5057.7     .05       0
#XS Ineff= 2 , 0
            4940  260.95
Permanent Ineff=
       F       F
Bank Sta=4985.4,5013.4
XS Rating Curve= 0 ,0
Exp/Cntr=0.3,0.1

Type RM Length L Ch R = 1 ,2883    ,675,675,675
BEGIN DESCRIPTION:
UNT009 IN ROCK 3.0
END DESCRIPTION:
XS GIS Cut Line= 3
      3655872.72     10187075.76      3655542.11     10186791.64
      3655350.07     10186662.94
#Sta/Elev= 30
  4572.2  256.21  4724.5  256.18  4767.3  256.81    4866  256.83    4888  257.54
  4894.5  257.19  4902.2  255.43  4908.8   255.2  4915.8  253.49  4986.7  253.26
  4994.4  249.74  5000.7  247.99    5004  248.49  5004.8   249.8  5008.1   249.8
  5011.1   249.8  5015.6  252.53  5030.6  257.03  5044.2  258.56  5087.7  259.24
  5093.7   258.8  5102.7  259.14  5108.7   258.3  5123.7  259.05  5129.7  258.56
  5144.7  258.58  5195.7  259.41  5216.7  259.02  5231.7  259.74  5239.3  259.48
#Mann= 3 ,-1 , 0
  4572.2     .07       0  4994.4     .05       0  5008.1     .07       0
Bank Sta=4994.4,5004.8
XS Rating Curve= 0 ,0
Exp/Cntr=0.3,0.1

Type RM Length L Ch R = 1 ,2208    ,1345,1345,1345
BEGIN DESCRIPTION:
UNT009 IN ROCK 2.0
END DESCRIPTION:
XS GIS Cut Line= 4
      3656232.54      10187056.8      3655994.39     10186386.81
      3655611.42     10186276.64      3655341.13     10186392.42
#Sta/Elev= 30
  4388.5  253.42  4581.8  252.29  4612.6  253.31  4643.5  251.83  4659.3  253.07
  4675.9  252.75  4744.2  251.72  4766.9  249.54  4820.7  252.39  4892.8  252.66
  4903.4  252.07  4915.8  249.28  4924.6  249.18  4941.4  251.68  4977.7  251.07
  4988.3  248.08  4997.7  244.74  5002.8  244.24    5006  244.74  5009.5  247.89
  5020.1  249.82  5064.7  249.02  5083.8  251.94  5100.7  251.79    5221  251.87
  5428.3   251.6  5498.1  250.48  5571.1  252.36  5638.7  251.42  5792.1  253.26
#Mann= 9 ,-1 , 0
  4388.5     .05       0  4675.9     .16       0  4820.7     .05       0
  4941.4      .1       0  4988.3     .05       0  5009.5      .1       0
  5100.7     .05       0    5221     .16       0  5428.3     .05       0
Bank Sta=4988.3,5009.5
XS Rating Curve= 0 ,0
Exp/Cntr=0.3,0.1

Type RM Length L Ch R = 1 ,863     ,0,0,0
BEGIN DESCRIPTION:
UNT009 IN ROCK 1.0
END DESCRIPTION:
XS GIS Cut Line= 3
      3657006.01      10185740.1      3655884.12     10185549.46
      3655020.57     10186110.01
#Sta/Elev= 30
  3765.6  248.65  3911.6  247.92  4033.3  248.69  4207.4  248.38  4860.1  246.13
  4914.3  246.02  4971.6  247.26  4986.8  243.98  4998.3   239.2  5001.1   238.7
  5004.3   239.2    5008  242.09  5013.9   244.5  5023.1  246.68  5029.1  246.73
  5044.2  243.97  5059.3  244.47  5065.3  245.66  5072.9  244.74  5095.6  246.36
  5119.6  246.26  5246.6  248.11  5319.1   246.9  5563.6  247.59  5593.9  248.78
  5609.1  252.26  5621.3  251.77  5630.2   249.8  5645.1  248.21  5933.1   252.6
#Mann= 6 ,-1 , 0
  3765.6     .05       0  4860.1     .12       0  4971.6     .16       0
  4998.3     .07       0  5004.3     .16       0  5119.6     .05       0
Bank Sta=4998.3,5004.3
XS Rating Curve= 0 ,0
Exp/Cntr=0.3,0.1

Chan Stop Cuts=-1
Use User Specified Reach Order=0
Composite Channel Slope=5