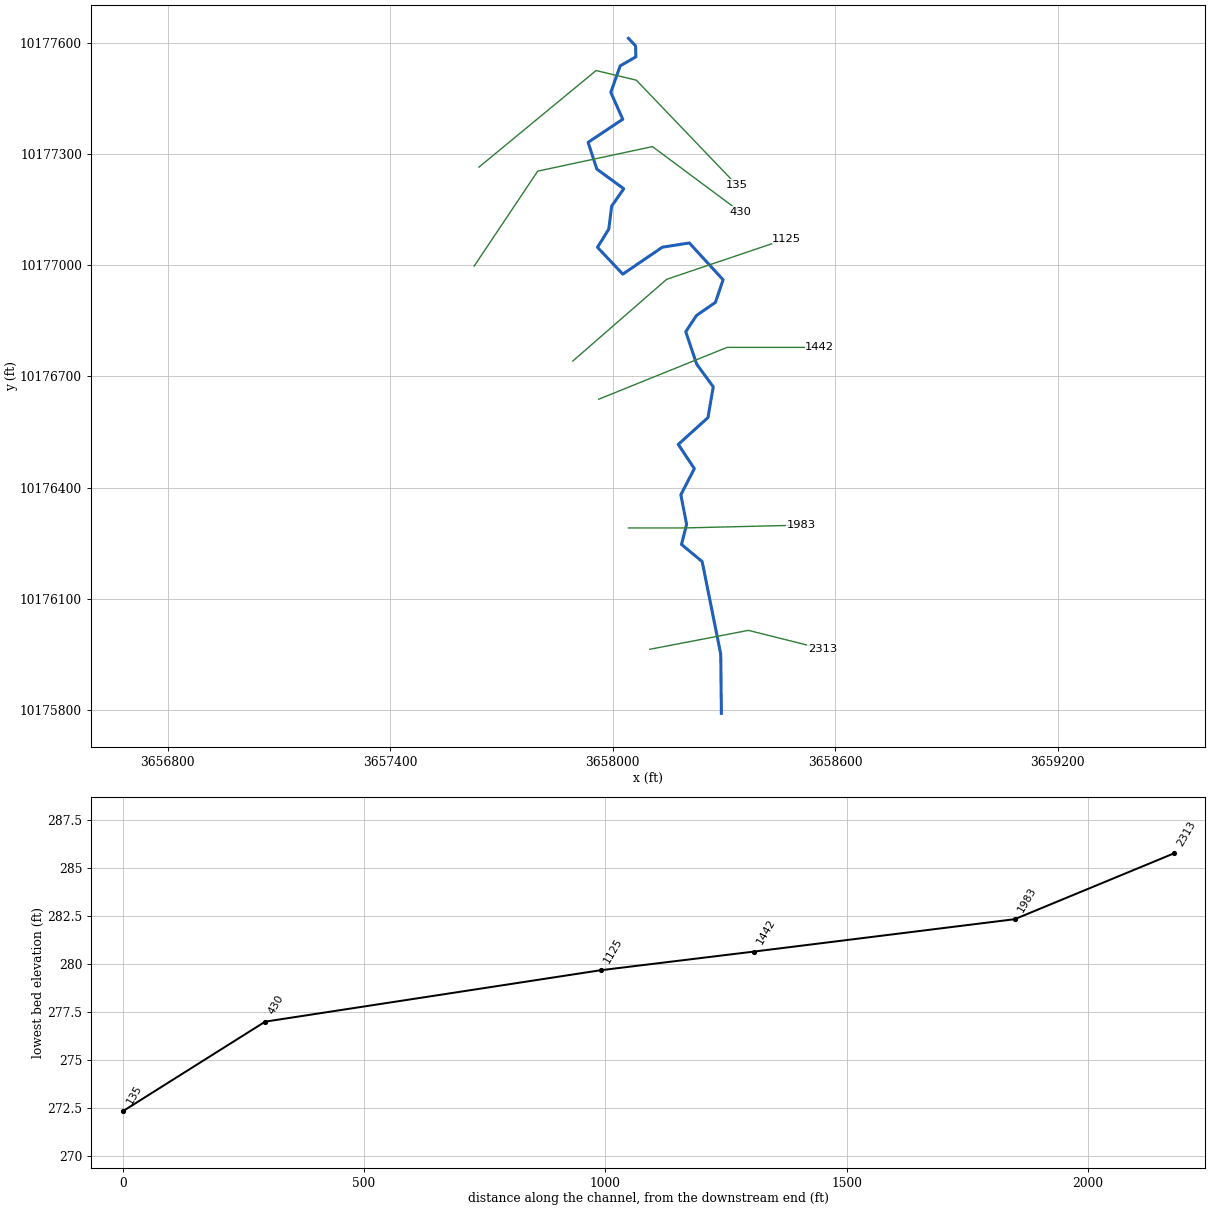
--- UNT012 IN ROCK.prj (project) ---

Proj Title=UNT012 IN ROCK Base Level Engineering
Current Plan=p01
Default Exp/Contr=0.3,0.1
English Units
Geom File=g01
Flow File=f01
Plan File=p01
BEGIN DESCRIPTION:
UNT012 IN ROCK
END DESCRIPTION:

--- UNT012 IN ROCK.p01 (plan) ---

Plan Title=Multiple Run
Short Identifier=Multiple
Geom File=g01
Flow File=f01
Subcritical Flow
K Sum by GR= 0
Std Step Tol= 0.01
Critical Tol= 0.01
Num of Std Step Trials= 20
Max Error Tol= 0.3
Flow Tol Ratio= 0.001
Split Flow NTrial= 30
Split Flow Tol= 0.02
Split Flow Ratio= 0.02
Log Output Level= 0
Friction Slope Method= 1
Unsteady Friction Slope Method= 2
Unsteady Bridges Friction Slope Method= 1
Parabolic Critical Depth
Global Vel Dist=  1 , 1 , 1
Global Log Level= 0
CheckData=True
Encroach Param= -1, 0, 0, 0
BEGIN DESCRIPTION:
Multiple Run
END DESCRIPTION:

--- UNT012 IN ROCK.f01 (steady flow) ---

Flow Title=Multiple
Number of Profiles=7
Profile Names=10-year,25-year,50-year,1pct_min,100-year,1pct_plu,500-year
River Rch & RM= UNT012 IN ROCK,Reach-1,2313
     351     456     539     469     634     857     875
Boundary for River Rch & Prof#=UNT012 IN ROCK,Reach-1,1
Up Type=0
Dn Type=3
Dn Slope=0.005
Boundary for River Rch & Prof#=UNT012 IN ROCK,Reach-1,2
Up Type=0
Dn Type=3
Dn Slope=0.005
Boundary for River Rch & Prof#=UNT012 IN ROCK,Reach-1,3
Up Type=0
Dn Type=3
Dn Slope=0.005
Boundary for River Rch & Prof#=UNT012 IN ROCK,Reach-1,4
Up Type=0
Dn Type=3
Dn Slope=0.005
Boundary for River Rch & Prof#=UNT012 IN ROCK,Reach-1,5
Up Type=0
Dn Type=3
Dn Slope=0.005
Boundary for River Rch & Prof#=UNT012 IN ROCK,Reach-1,6
Up Type=0
Dn Type=3
Dn Slope=0.005
Boundary for River Rch & Prof#=UNT012 IN ROCK,Reach-1,7
Up Type=0
Dn Type=3
Dn Slope=0.005

--- UNT012 IN ROCK.g01 (geometry) ---

Geom Title=Existing Conditions

River Reach=UNT012 IN ROCK,Reach-1
Reach XY= 30
      3658292.64     10175791.68      3658290.92     10175951.41
      3658240.80     10176201.02      3658185.12     10176247.17
      3658198.92     10176301.39      3658183.33     10176380.99
      3658219.73     10176451.62      3658176.45     10176516.88
      3658256.51     10176589.14      3658270.73     10176672.04
      3658226.04     10176733.22      3658196.60     10176820.75
      3658225.63     10176864.55      3658276.51     10176899.63
      3658297.26     10176960.65      3658206.24     10177059.93
      3658133.52     10177048.52      3658026.87     10176975.90
      3657958.61     10177048.15      3657989.10     10177097.32
      3657996.83     10177159.30      3658029.46     10177206.11
      3657956.91     10177259.06      3657933.34     10177331.10
      3658026.77     10177393.47      3657994.53     10177465.96
      3658019.90     10177537.55      3658062.11     10177561.64
      3658061.32     10177591.32      3658042.11     10177611.64

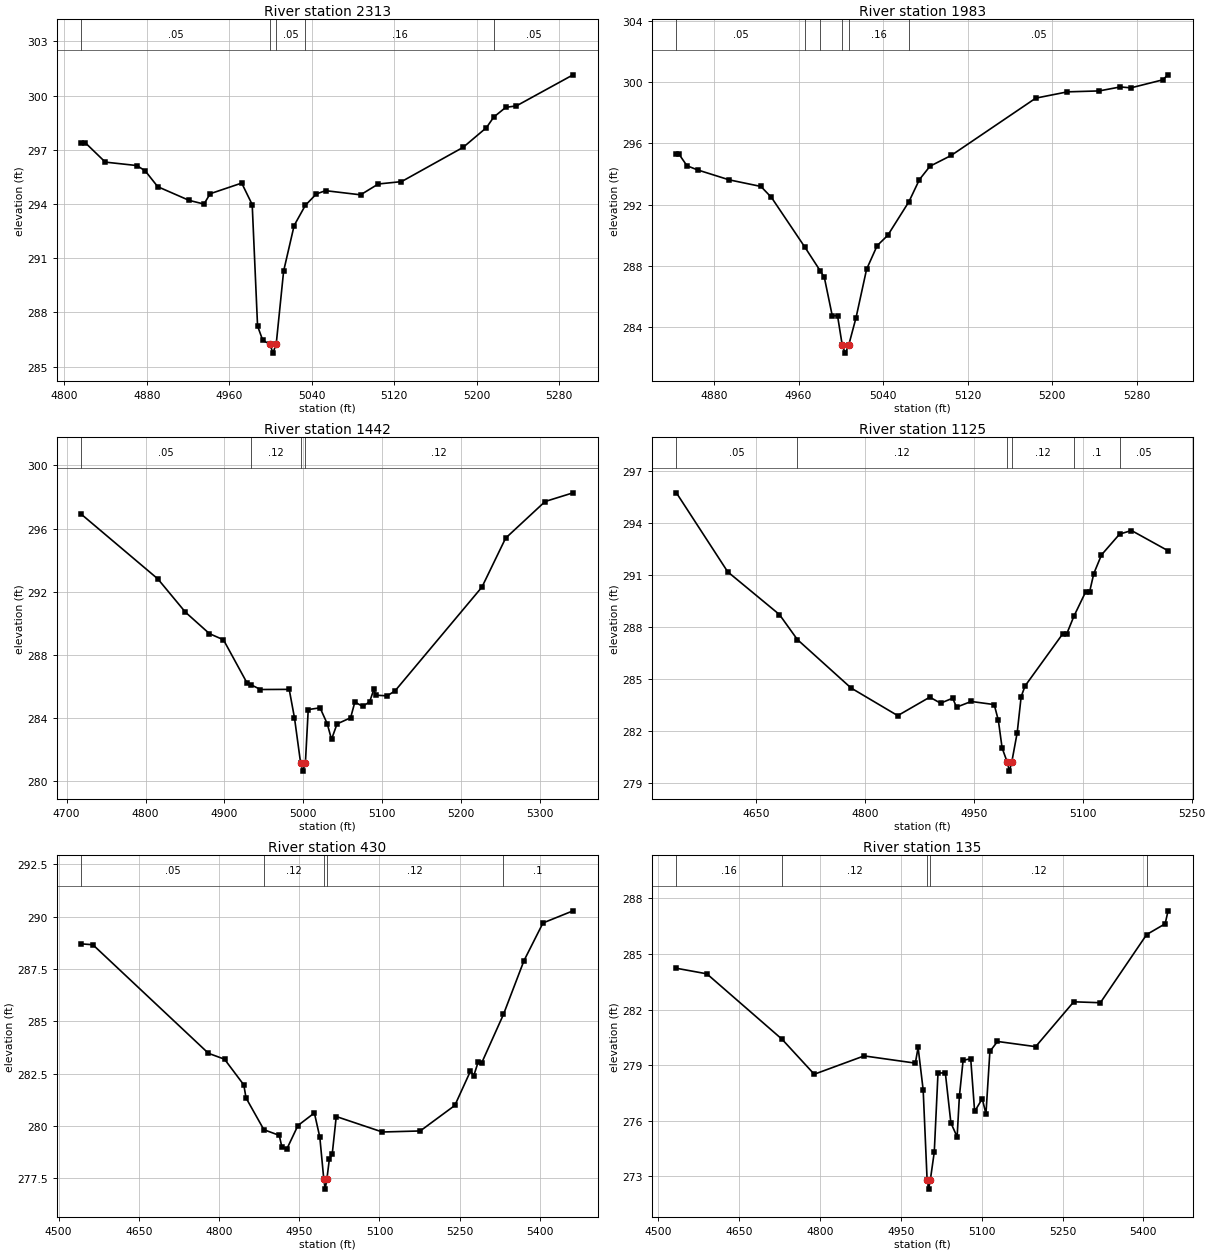
Type RM Length L Ch R = 1,2313,330,330,330
BEGIN DESCRIPTION:
UNT012 IN ROCK 5.0
END DESCRIPTION:
XS GIS Cut Line= 3
      3658099.30     10175964.40      3658365.49     10176015.47
      3658565.49     10175965.47
#Sta/Elev= 30
  4816.4  297.38  4820.4  297.38  4839.6  296.32  4870.2  296.13  4878.3  295.84
  4890.5  294.96  4921.1  294.20  4935.4  294.00  4941.4  294.57  4972.0  295.16
  4982.2  293.97  4987.4  287.25  4992.5  286.45  4999.5  286.25  5002.3  285.75
  5005.5  286.25  5012.7  290.29  5022.9  292.81  5033.8  293.93  5044.5  294.56
  5053.4  294.74  5087.4  294.51  5104.6  295.11  5127.1  295.24  5187.0  297.14
  5209.6  298.23  5216.6  298.81  5228.3  299.35  5238.6  299.43  5293.6  301.15
#Mann=5,-1,0
  4816.4    0.05       0  4999.5    0.03       0  5005.5    0.05       0
  5033.8    0.16       0  5216.6    0.05       0
Bank Sta=4999.5,5005.5
Exp/Cntr=0.3,0.1

Type RM Length L Ch R = 1,1983,541,541,541
BEGIN DESCRIPTION:
UNT012 IN ROCK 4.0
END DESCRIPTION:
XS GIS Cut Line= 3
      3658042.10     10176291.64      3658192.11     10176291.64
      3658507.31     10176299.20
#Sta/Elev= 30
  4844.4  295.29  4846.9  295.29  4854.4  294.54  4864.4  294.27  4894.4  293.62
  4924.4  293.19  4934.4  292.47  4965.9  289.24  4980.5  287.69  4984.4  287.26
  4991.9  284.76  4996.9  284.76  5001.4  282.82  5004.2  282.32  5007.4  282.82
  5014.4  284.63  5024.4  287.79  5034.4  289.33  5044.4  290.00  5064.5  292.20
  5074.4  293.64  5084.4  294.51  5104.4  295.21  5184.5  298.95  5214.5  299.36
  5244.5  299.42  5264.5  299.68  5274.5  299.62  5304.5  300.14  5309.7  300.47
#Mann=6,-1,0
  4844.4    0.05       0  4965.9    0.12       0  4980.5    0.16       0
  5001.4    0.07       0  5007.4    0.16       0  5064.5    0.05       0
Bank Sta=5001.4,5007.4
Exp/Cntr=0.3,0.1

Type RM Length L Ch R = 1,1442,317,317,317
BEGIN DESCRIPTION:
UNT012 IN ROCK 3.0
END DESCRIPTION:
XS GIS Cut Line= 3
      3657961.73     10176638.60      3658307.95     10176778.37
      3658557.48     10176778.37
#Sta/Elev= 30
  4718.7  296.90  4815.5  292.81  4850.5  290.70  4880.9  289.34  4898.7  288.95
  4928.3  286.24  4933.3  286.11  4945.6  285.80  4982.0  285.81  4988.7  284.00
  4996.5  281.13  4999.2  280.63  5002.5  281.13  5006.1  284.53  5021.1  284.64
  5030.2  283.63  5035.6  282.64  5042.6  283.62  5059.8  284.01  5065.2  285.01
  5075.0  284.73  5083.9  285.02  5089.3  285.82  5091.6  285.44  5106.2  285.40
  5116.2  285.72  5226.2  292.29  5256.2  295.39  5306.2  297.71  5341.6  298.26
#Mann=4,-1,0
  4718.7    0.05       0  4933.3    0.12       0  4996.5    0.07       0
  5002.5    0.12       0
Bank Sta=4996.5,5002.5
Exp/Cntr=0.3,0.1

Type RM Length L Ch R = 1,1125,695,695,695
BEGIN DESCRIPTION:
UNT012 IN ROCK 2.0
END DESCRIPTION:
XS GIS Cut Line= 3
      3657892.13     10176741.67      3658145.18     10176961.94
      3658468.99     10177071.40
#Sta/Elev= 30
  4540.1  295.76  4610.8  291.19  4682.0  288.72  4706.8  287.27  4780.7  284.47
  4845.0  282.87  4889.2  283.94  4904.0  283.59  4920.7  283.88  4926.0  283.36
  4946.2  283.69  4977.9  283.51  4983.6  282.60  4988.8  281.00  4996.0  280.16
  4998.8  279.66  5002.0  280.16  5009.6  281.89  5015.0  283.96  5020.3  284.58
  5072.6  287.62  5077.9  287.61  5087.8  288.63  5104.1  290.05  5109.4  290.05
  5115.1  291.09  5125.7  292.17  5150.6  293.37  5167.0  293.58  5217.4  292.41
#Mann=6,-1,0
  4540.1    0.05       0  4706.8    0.12       0  4996.0    0.07       0
  5002.0    0.12       0  5087.8     0.1       0  5150.6    0.05       0
Bank Sta=4996,5002
Exp/Cntr=0.3,0.1

Type RM Length L Ch R = 1,430,295,295,295
BEGIN DESCRIPTION:
Mapping XS 4db2ce20
END DESCRIPTION:
XS GIS Cut Line= 4
      3657626.05     10176997.45      3657797.51     10177253.55
      3658106.76     10177319.74      3658343.34     10177143.93
#Sta/Elev= 30
  4542.7  288.70  4564.2  288.66  4780.3  283.47  4810.3  283.19  4846.4  281.96
  4850.5  281.34  4883.9  279.82  4912.6  279.55  4917.8  278.97  4927.2  278.92
  4947.6  280.02  4978.3  280.62  4988.5  279.46  4995.8  277.48  4998.5  276.98
  5001.8  277.48  5006.4  278.43  5011.6  278.64  5019.2  280.45  5105.4  279.71
  5176.2  279.76  5240.9  280.98  5270.1  282.62  5276.3  282.40  5284.7  283.07
  5290.9  283.00  5331.8  285.33  5370.2  287.90  5405.7  289.70  5461.9  290.28
#Mann=5,-1,0
  4542.7    0.05       0  4883.9    0.12       0  4995.8    0.07       0
  5001.8    0.12       0  5331.8     0.1       0
Bank Sta=4995.8,5001.8
Exp/Cntr=0.3,0.1

Type RM Length L Ch R = 1,135,0,0,0
BEGIN DESCRIPTION:
UNT012 IN ROCK 1.0
END DESCRIPTION:
XS GIS Cut Line= 4
      3657639.09     10177264.40      3657954.85     10177524.82
      3658063.35     10177498.78      3658334.11     10177216.11
#Sta/Elev= 30
  4533.5  284.23  4590.0  283.93  4729.5  280.40  4789.3  278.51  4881.8  279.50
  4976.9  279.11  4982.0  279.96  4991.4  277.66  4998.7  272.81  5001.4  272.31
  5004.7  272.81  5012.0  274.31  5018.9  278.57  5032.5  278.59  5042.8  275.89
  5054.4  275.13  5058.6  277.32  5065.5  279.26  5079.6  279.35  5086.9  276.50
  5101.0  277.19  5107.9  276.37  5115.2  279.74  5129.3  280.28  5200.1  280.00
  5270.8  282.42  5320.2  282.37  5406.1  286.05  5440.4  286.63  5445.8  287.33
#Mann=5,-1,0
  4533.5    0.16       0  4729.5    0.12       0  4998.7    0.07       0
  5004.7    0.12       0  5406.1     0.1       0
Bank Sta=4998.7,5004.7
Exp/Cntr=0.3,0.1

Chan Stop Cuts=-1