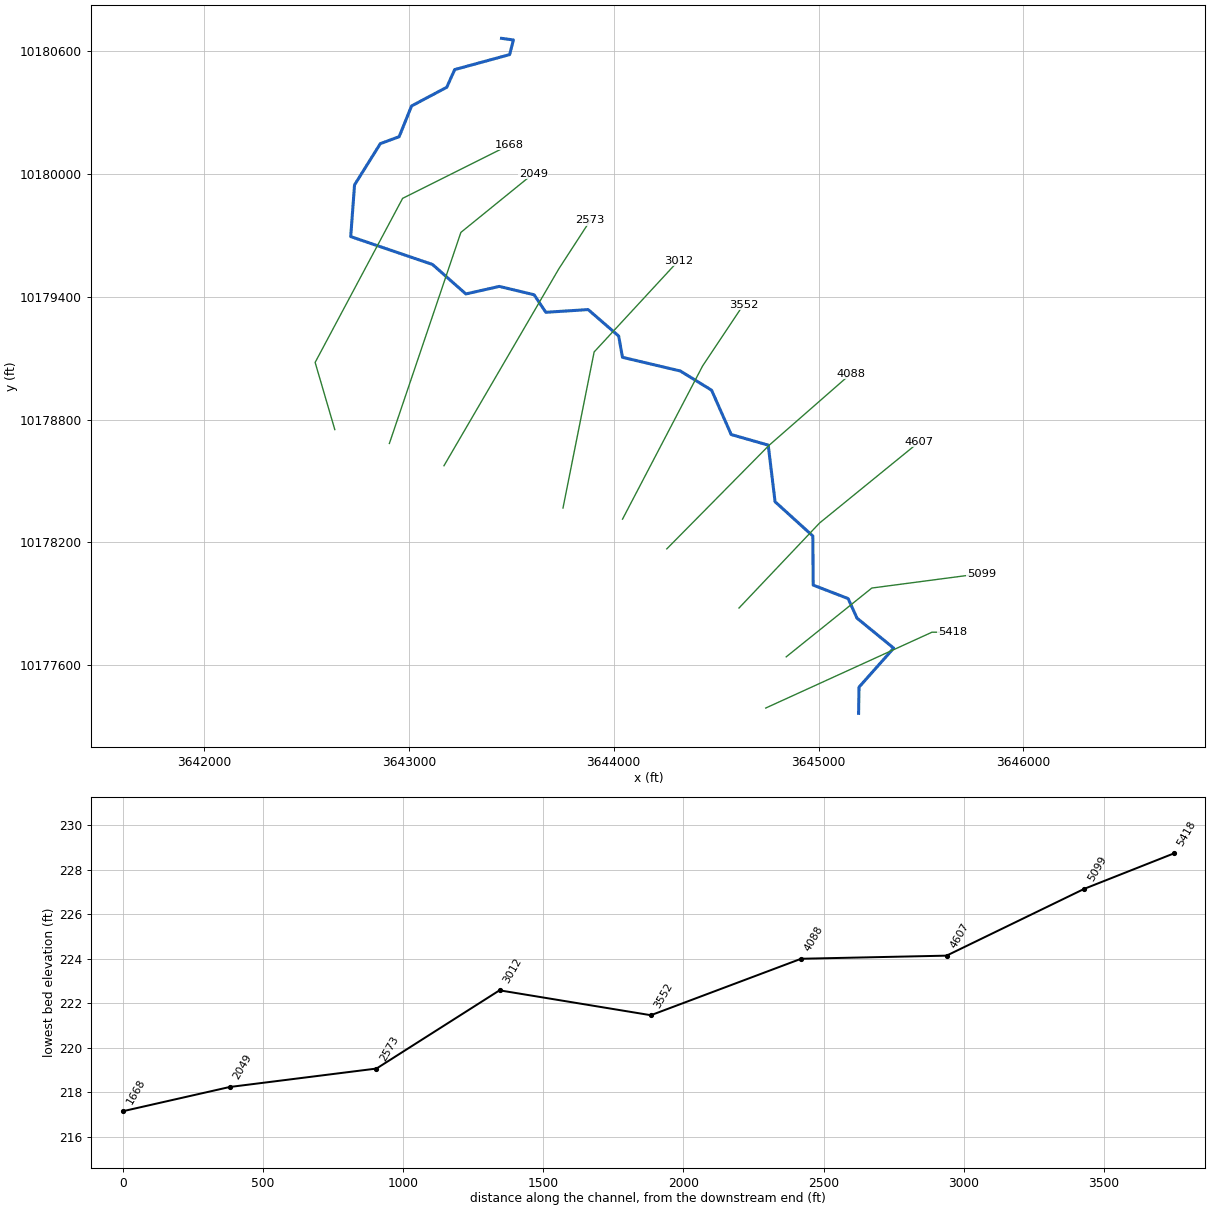
--- UNT016 IN ROCK.prj (project) ---

Proj Title=UNT016 IN ROCK Base Level Engineering
Current Plan=p01
Default Exp/Contr=0.3,0.1
English Units
Geom File=g01
Flow File=f01
Plan File=p01
BEGIN DESCRIPTION:
UNT016 IN ROCK
END DESCRIPTION:

--- UNT016 IN ROCK.p01 (plan) ---

Plan Title=Multiple Run
Short Identifier=Multiple
Geom File=g01
Flow File=f01
Subcritical Flow
K Sum by GR= 0
Std Step Tol= 0.01
Critical Tol= 0.01
Num of Std Step Trials= 20
Max Error Tol= 0.3
Flow Tol Ratio= 0.001
Split Flow NTrial= 30
Split Flow Tol= 0.02
Split Flow Ratio= 0.02
Log Output Level= 0
Friction Slope Method= 1
Unsteady Friction Slope Method= 2
Unsteady Bridges Friction Slope Method= 1
Parabolic Critical Depth
Global Vel Dist=  1 , 1 , 1
Global Log Level= 0
CheckData=True
Encroach Param= -1, 0, 0, 0
BEGIN DESCRIPTION:
Multiple Run
END DESCRIPTION:

--- UNT016 IN ROCK.f01 (steady flow) ---

Flow Title=Multiple
Number of Profiles=7
Profile Names=10-year,25-year,50-year,1pct_min,100-year,1pct_plu,500-year
River Rch & RM= UNT016 IN ROCK,Reach-1,5418
     827    1138    1398    1259    1702    2302    2528
River Rch & RM= UNT016 IN ROCK,Reach-1,4088
     836    1147    1406    1263    1708    2310    2524
Boundary for River Rch & Prof#=UNT016 IN ROCK,Reach-1,1
Up Type=0
Dn Type=3
Dn Slope=0.005
Boundary for River Rch & Prof#=UNT016 IN ROCK,Reach-1,2
Up Type=0
Dn Type=3
Dn Slope=0.005
Boundary for River Rch & Prof#=UNT016 IN ROCK,Reach-1,3
Up Type=0
Dn Type=3
Dn Slope=0.005
Boundary for River Rch & Prof#=UNT016 IN ROCK,Reach-1,4
Up Type=0
Dn Type=3
Dn Slope=0.005
Boundary for River Rch & Prof#=UNT016 IN ROCK,Reach-1,5
Up Type=0
Dn Type=3
Dn Slope=0.005
Boundary for River Rch & Prof#=UNT016 IN ROCK,Reach-1,6
Up Type=0
Dn Type=3
Dn Slope=0.005
Boundary for River Rch & Prof#=UNT016 IN ROCK,Reach-1,7
Up Type=0
Dn Type=3
Dn Slope=0.005

--- UNT016 IN ROCK.g01 (geometry) ---

Geom Title=Existing Conditions

River Reach=UNT016 IN ROCK,Reach-1
Reach XY= 30
      3645195.57     10177365.60      3645197.66     10177493.85
      3645366.93     10177684.15      3645187.77     10177830.65
      3645144.53     10177926.10      3644973.93     10177991.90
      3644972.11     10178231.64      3644787.74     10178399.03
      3644754.35     10178675.45      3644573.43     10178727.12
      3644477.88     10178943.57      3644325.00     10179037.38
      3644042.71     10179104.19      3644024.12     10179208.02
      3643875.07     10179337.23      3643668.31     10179323.95
      3643611.45     10179409.46      3643441.43     10179450.34
      3643277.95     10179413.57      3643115.18     10179557.50
      3642715.76     10179693.57      3642734.45     10179945.96
      3642860.36     10180147.50      3642952.25     10180181.30
      3643012.79     10180331.36      3643184.73     10180422.76
      3643223.54     10180509.06      3643491.74     10180582.27
      3643510.05     10180653.59      3643452.11     10180661.64

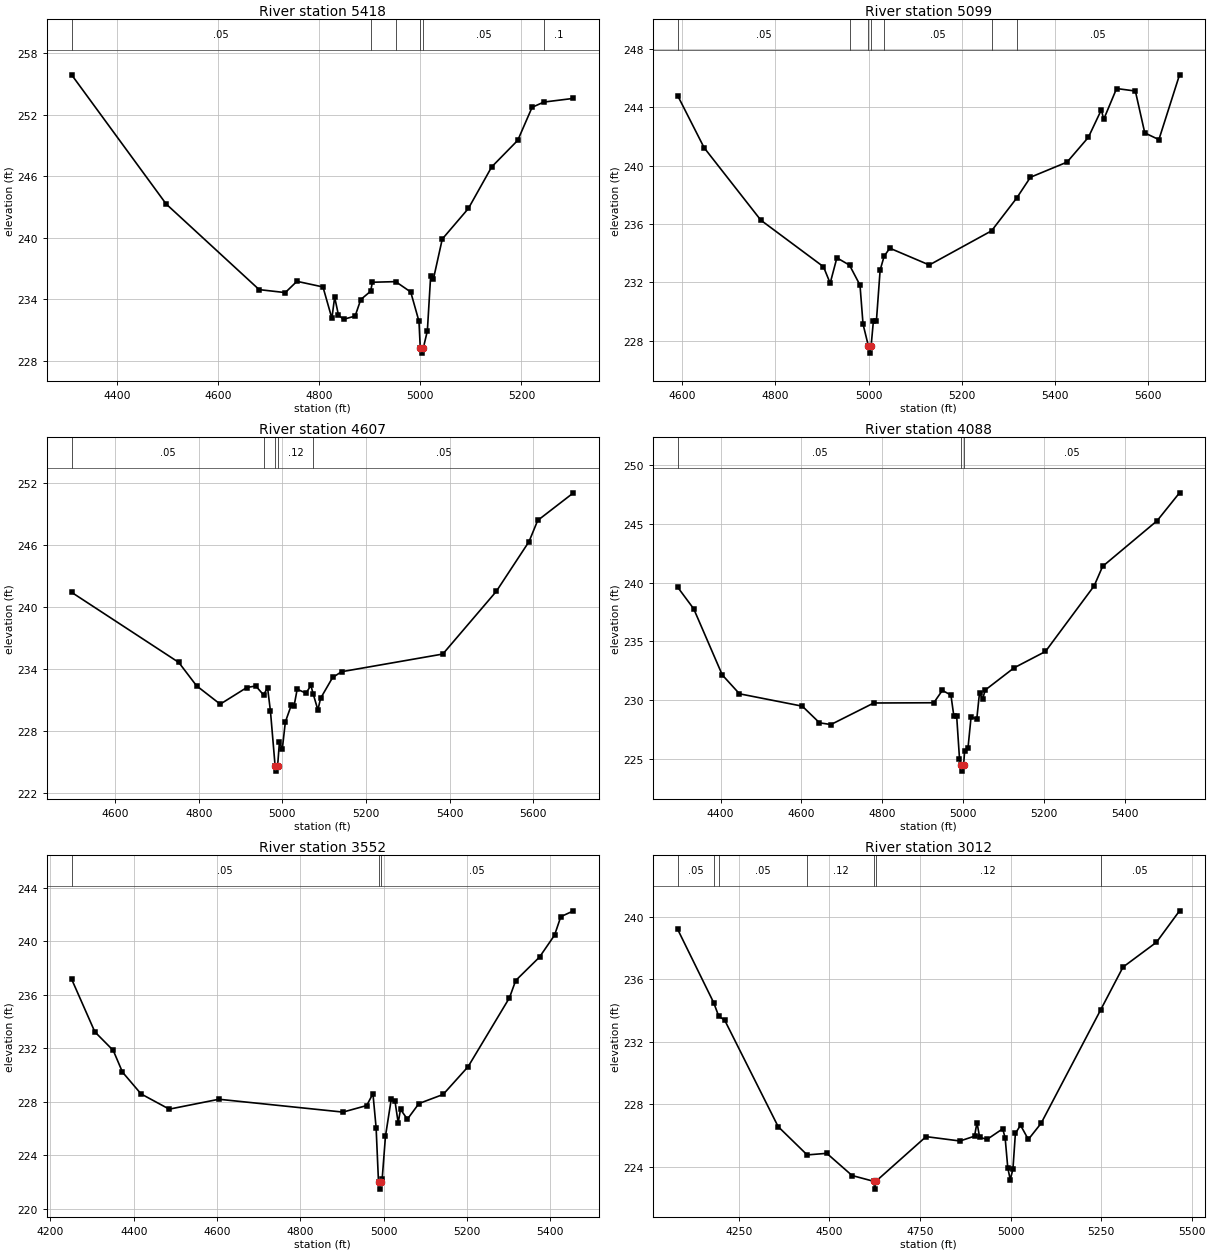
Type RM Length L Ch R = 1,5418,319,319,319
BEGIN DESCRIPTION:
UNT016 IN ROCK 10.0
END DESCRIPTION:
XS GIS Cut Line= 3
      3644742.10     10177391.64      3645553.97     10177761.96
      3645653.93     10177761.96
#Sta/Elev= 30
  4310.6  255.91  4497.5  243.30  4681.4  234.94  4733.0  234.65  4756.1  235.75
  4807.6  235.20  4825.2  232.14  4830.7  234.20  4838.2  232.46  4848.2  232.04
  4871.2  232.36  4882.3  233.97  4901.8  234.78  4905.3  235.66  4951.3  235.72
  4981.1  234.71  4997.4  231.85  5000.0  229.24  5002.8  228.74  5006.0  229.24
  5014.0  230.91  5020.5  236.26  5026.0  235.98  5043.5  239.88  5095.1  242.86
  5141.2  246.92  5192.8  249.52  5221.1  252.74  5244.4  253.25  5302.9  253.61
#Mann=6,-1,0
  4310.6    0.05       0  4901.8    0.12       0  4951.3    0.05       0
  5000.0    0.03       0  5006.0    0.05       0  5244.4     0.1       0
Bank Sta=5000,5006
Exp/Cntr=0.3,0.1

Type RM Length L Ch R = 1,5099,492,492,492
BEGIN DESCRIPTION:
UNT016 IN ROCK 9.0
END DESCRIPTION:
XS GIS Cut Line= 3
      3644842.07     10177641.62      3645260.15     10177977.59
      3645796.07     10178048.21
#Sta/Elev= 30
  4590.4  244.79  4647.2  241.22  4768.8  236.26  4903.2  233.07  4917.6  231.94
  4932.0  233.68  4959.1  233.18  4981.6  231.81  4988.1  229.14  4999.5  227.65
  5002.2  227.15  5005.5  227.65  5010.4  229.37  5016.8  229.35  5024.8  232.84
  5033.5  233.80  5045.6  234.34  5130.3  233.19  5263.9  235.53  5317.5  237.76
  5347.3  239.20  5426.0  240.24  5471.7  241.94  5499.5  243.82  5504.6  243.17
  5532.2  245.28  5572.5  245.11  5592.7  242.24  5623.0  241.78  5667.3  246.22
#Mann=7,-1,0
  4590.4    0.05       0  4959.1    0.12       0  4999.5    0.07       0
  5005.5    0.12       0  5033.5    0.05       0  5263.9    0.12       0
  5317.5    0.05       0
Bank Sta=4999.5,5005.5
Exp/Cntr=0.3,0.1

Type RM Length L Ch R = 1,4607,519,519,519
BEGIN DESCRIPTION:
UNT016 IN ROCK 8.0
END DESCRIPTION:
XS GIS Cut Line= 3
      3644611.57     10177879.89      3645005.12     10178295.15
      3645492.11     10178691.64
#Sta/Elev= 30
  4496.1  241.44  4752.3  234.66  4794.8  232.40  4851.4  230.62  4915.0  232.23
  4936.4  232.38  4955.0  231.52  4964.7  232.20  4971.6  229.93  4982.7  224.64
  4985.5  224.14  4988.7  224.64  4993.0  226.94  4999.9  226.28  5007.2  228.90
  5021.3  230.51  5028.2  230.48  5035.5  232.07  5056.5  231.68  5068.2  232.43
  5074.1  231.57  5085.0  230.06  5091.5  231.19  5120.2  233.20  5141.7  233.76
  5383.8  235.47  5511.6  241.53  5589.9  246.35  5610.7  248.40  5696.2  251.07
#Mann=5,-1,0
  4496.1    0.05       0  4955.0    0.12       0  4982.7    0.07       0
  4988.7    0.12       0  5074.1    0.05       0
Bank Sta=4982.7,4988.7
Exp/Cntr=0.3,0.1

Type RM Length L Ch R = 1,4088,536,536,536
BEGIN DESCRIPTION:
UNT016 IN ROCK 7.0
END DESCRIPTION:
XS GIS Cut Line= 3
      3644259.02     10178168.71      3644758.72     10178674.73
      3645157.92     10179024.02
#Sta/Elev= 30
  4294.1  239.60  4333.7  237.77  4404.4  232.16  4446.9  230.56  4602.4  229.51
  4644.9  228.10  4673.1  227.95  4779.2  229.78  4927.7  229.80  4948.9  230.85
  4970.1  230.45  4977.2  228.70  4984.3  228.67  4991.3  225.06  4995.4  224.50
  4998.2  224.00  5001.4  224.50  5004.1  225.74  5012.3  225.96  5019.9  228.58
  5034.1  228.44  5040.8  230.64  5048.4  230.11  5055.0  230.88  5126.2  232.76
  5204.0  234.15  5324.5  239.72  5345.4  241.37  5480.2  245.24  5535.7  247.61
#Mann=3,-1,0
  4294.1    0.05       0  4995.4    0.03       0  5001.4    0.05       0
Bank Sta=4995.4,5001.4
Exp/Cntr=0.3,0.1

Type RM Length L Ch R = 1,3552,540,540,540
BEGIN DESCRIPTION:
UNT016 IN ROCK 6.0
END DESCRIPTION:
XS GIS Cut Line= 3
      3644042.95     10178314.04      3644433.95     10179061.96
      3644633.94     10179361.95
#Sta/Elev= 30
  4251.0  237.16  4306.7  233.22  4350.9  231.83  4373.0  230.21  4417.6  228.58
  4485.3  227.44  4604.5  228.18  4902.3  227.22  4959.2  227.71  4974.2  228.60
  4981.8  226.06  4987.6  221.96  4990.4  221.46  4993.6  221.96  4996.3  222.19
  5004.3  225.43  5018.3  228.21  5026.9  228.08  5034.8  226.42  5040.4  227.42
  5056.9  226.69  5084.6  227.86  5142.7  228.54  5202.7  230.62  5301.9  235.77
  5316.9  237.06  5374.0  238.81  5410.1  240.45  5425.1  241.83  5455.5  242.27
#Mann=3,-1,0
  4251.0    0.05       0  4987.6    0.03       0  4993.6    0.05       0
Bank Sta=4987.6,4993.6
Exp/Cntr=0.3,0.1

Type RM Length L Ch R = 1,3012,439,439,439
BEGIN DESCRIPTION:
UNT016 IN ROCK 5.0
END DESCRIPTION:
XS GIS Cut Line= 3
      3643752.17     10178368.05      3643904.30     10179130.25
      3644317.01     10179576.81
#Sta/Elev= 30
  4081.3  239.20  4180.7  234.51  4194.8  233.63  4210.6  233.41  4358.6  226.58
  4438.7  224.77  4492.9  224.87  4562.7  223.45  4622.4  223.08  4625.2  222.58
  4628.4  223.08  4766.9  225.94  4860.6  225.66  4900.7  225.97  4907.5  226.84
  4914.8  225.89  4935.8  225.77  4978.4  226.44  4985.2  225.86  4992.5  223.94
  4999.3  223.19  5006.7  223.86  5013.5  226.15  5027.7  226.67  5049.2  225.76
  5084.4  226.79  5248.6  234.04  5310.6  236.79  5403.0  238.38  5466.6  240.39
#Mann=7,-1,0
  4081.3    0.05       0  4180.7    0.16       0  4194.8    0.05       0
  4438.7    0.12       0  4622.4    0.07       0  4628.4    0.12       0
  5248.6    0.05       0
Bank Sta=4622.4,4628.4
Exp/Cntr=0.3,0.1

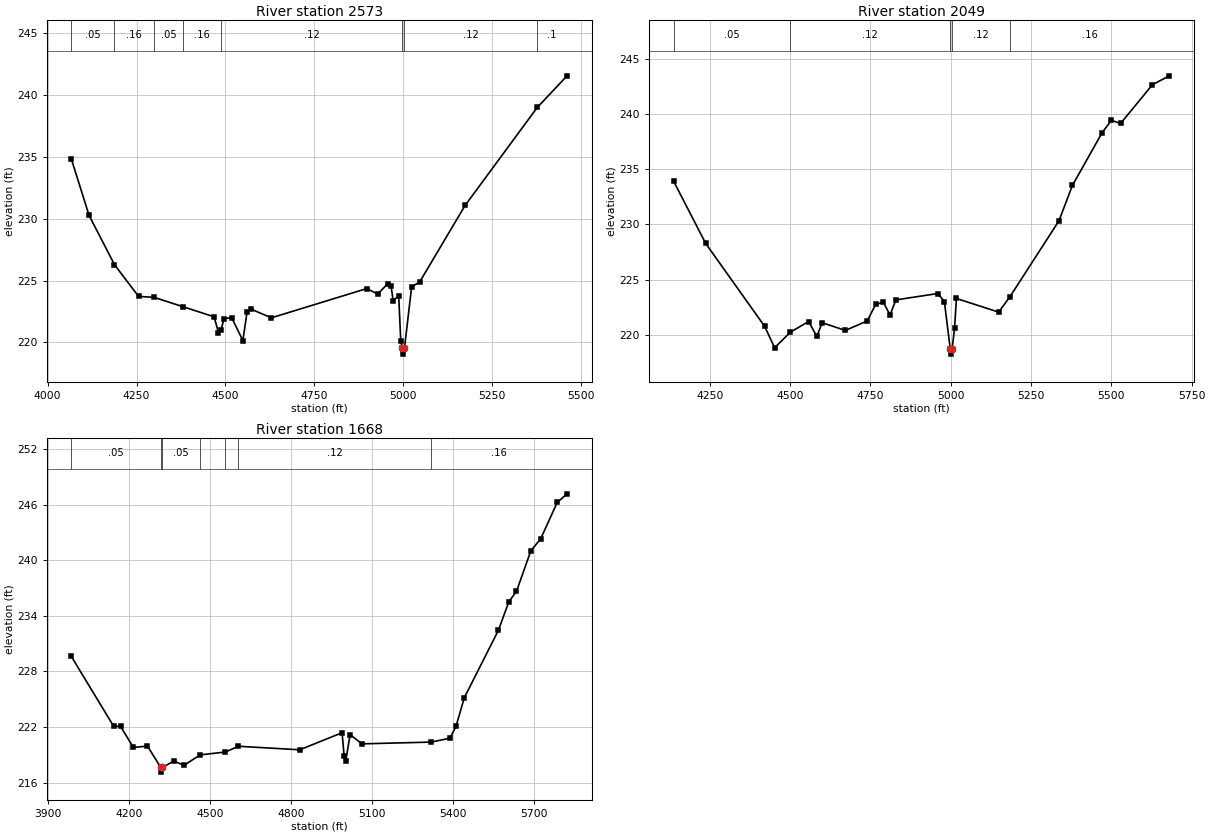
Type RM Length L Ch R = 1,2573,524,524,524
BEGIN DESCRIPTION:
UNT016 IN ROCK 4.0
END DESCRIPTION:
XS GIS Cut Line= 3
      3643171.10     10178574.76      3643731.41     10179535.41
      3643885.10     10179772.19
#Sta/Elev= 30
  4066.5  234.81  4116.5  230.25  4187.9  226.28  4255.5  223.72  4299.4  223.64
  4380.3  222.89  4468.1  222.07  4480.4  220.80  4487.3  221.00  4496.1  221.93
  4517.6  222.00  4549.0  220.15  4560.7  222.45  4570.5  222.71  4629.3  221.99
  4897.2  224.35  4928.6  223.91  4955.9  224.73  4965.8  224.58  4971.6  223.38
  4987.3  223.76  4993.1  220.13  4997.6  219.56  5000.3  219.06  5003.6  219.56
  5023.7  224.50  5046.0  224.87  5174.3  231.07  5377.1  238.97  5460.9  241.52
#Mann=8,-1,0
  4066.5    0.05       0  4187.9    0.16       0  4299.4    0.05       0
  4380.3    0.16       0  4487.3    0.12       0  4997.6    0.07       0
  5003.6    0.12       0  5377.1     0.1       0
Bank Sta=4997.6,5003.6
Exp/Cntr=0.3,0.1

Type RM Length L Ch R = 1,2049,381,381,381
BEGIN DESCRIPTION:
UNT016 IN ROCK 2.0
END DESCRIPTION:
XS GIS Cut Line= 3
      3642904.56     10178683.55      3643253.67     10179714.04
      3643606.76     10180000.67
#Sta/Elev= 30
  4137.8  233.92  4237.7  228.27  4420.9  220.76  4452.3  218.81  4501.1  220.22
  4558.1  221.19  4583.3  219.84  4600.3  221.08  4672.3  220.38  4740.4  221.24
  4766.5  222.74  4790.4  222.94  4811.5  221.78  4829.4  223.15  4960.3  223.73
  4980.4  223.00  4998.6  218.73  5001.3  218.23  5004.6  218.73  5012.1  220.56
  5017.9  223.28  5149.4  222.04  5184.8  223.45  5337.1  230.33  5378.8  233.53
  5471.5  238.33  5500.2  239.44  5528.9  239.16  5628.1  242.68  5680.6  243.48
#Mann=5,-1,0
  4137.8    0.05       0  4501.1    0.12       0  4998.6    0.07       0
  5004.6    0.12       0  5184.8    0.16       0
Bank Sta=4998.6,5004.6
Exp/Cntr=0.3,0.1

Type RM Length L Ch R = 1,1668,0,0,0
BEGIN DESCRIPTION:
UNT016 IN ROCK 1.0
END DESCRIPTION:
XS GIS Cut Line= 4
      3642638.06     10178751.23      3642542.02     10179079.16
      3642969.14     10179880.16      3643492.14     10180141.66
#Sta/Elev= 30
  3987.0  229.62  4143.7  222.08  4169.0  222.08  4216.7  219.80  4268.8  219.95
  4317.9  217.64  4320.6  217.14  4323.9  217.64  4366.0  218.33  4404.2  217.88
  4463.8  219.00  4557.3  219.31  4605.1  219.93  4832.1  219.55  4988.8  221.39
  4996.4  218.86  5002.1  218.31  5018.4  221.18  5062.3  220.19  5318.4  220.38
  5387.9  220.80  5410.3  222.09  5441.0  225.17  5566.8  232.42  5605.9  235.53
  5633.9  236.63  5687.0  241.01  5723.3  242.30  5784.8  246.23  5821.2  247.16
#Mann=7,-1,0
  3987.0    0.05       0  4317.9    0.07       0  4323.9    0.05       0
  4463.8    0.16       0  4557.3    0.05       0  4605.1    0.12       0
  5318.4    0.16       0
Bank Sta=4317.9,4323.9
Exp/Cntr=0.3,0.1

Chan Stop Cuts=-1