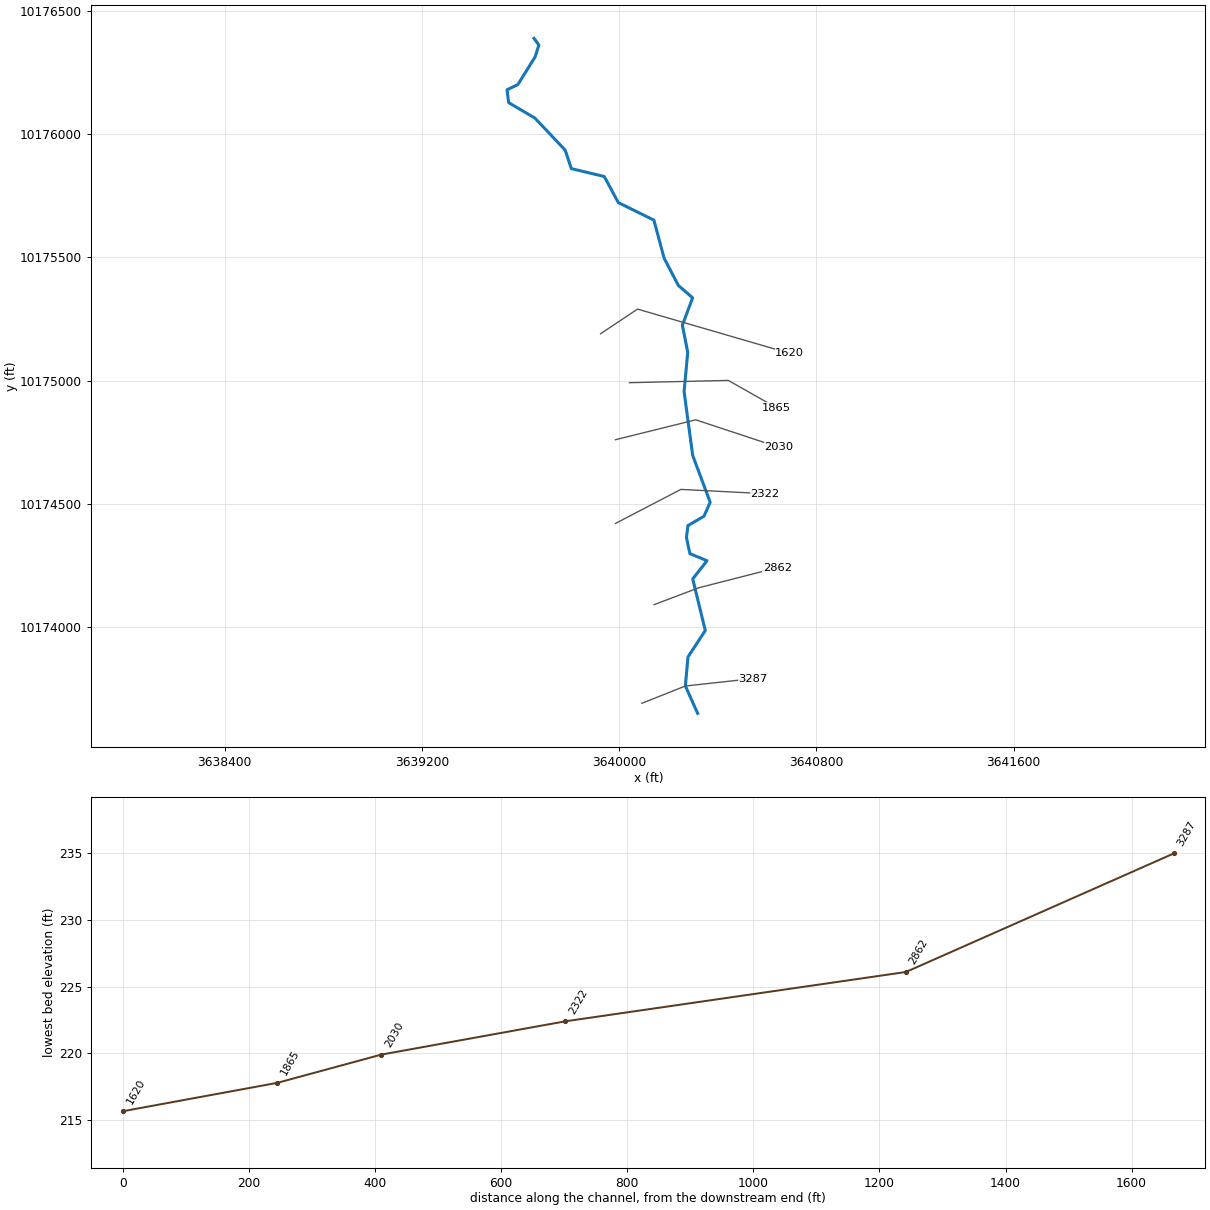
--- UNT017 IN ROCK.prj (project) ---

Proj Title=UNT017 IN ROCK Base Level Engineering
Current Plan=p01
Default Exp/Contr=0.3,0.1
English Units
Geom File=g01
Flow File=f01
Plan File=p01
BEGIN DESCRIPTION:
UNT017 IN ROCK
END DESCRIPTION:

--- UNT017 IN ROCK.p01 (plan) ---

Plan Title=Multiple Run
Short Identifier=Multiple
Geom File=g01
Flow File=f01
Subcritical Flow
K Sum by GR= 0
Std Step Tol= 0.01
Critical Tol= 0.01
Num of Std Step Trials= 20
Max Error Tol= 0.3
Flow Tol Ratio= 0.001
Split Flow NTrial= 30
Split Flow Tol= 0.02
Split Flow Ratio= 0.02
Log Output Level= 0
Friction Slope Method= 1
Unsteady Friction Slope Method= 2
Unsteady Bridges Friction Slope Method= 1
Parabolic Critical Depth
Global Vel Dist=  1 , 1 , 1
Global Log Level= 0
CheckData=True
Encroach Param= -1, 0, 0, 0
BEGIN DESCRIPTION:
Multiple Run
END DESCRIPTION:

--- UNT017 IN ROCK.f01 (steady flow) ---

Flow Title=Multiple
Number of Profiles=7
Profile Names=10-year,25-year,50-year,1pct_min,100-year,1pct_plu,500-year
River Rch & RM= UNT017 IN ROCK,Reach-1,3287
     163     201     230     194     263     356     341
Boundary for River Rch & Prof#=UNT017 IN ROCK,Reach-1,1
Up Type=0
Dn Type=3
Dn Slope=0.005
Boundary for River Rch & Prof#=UNT017 IN ROCK,Reach-1,2
Up Type=0
Dn Type=3
Dn Slope=0.005
Boundary for River Rch & Prof#=UNT017 IN ROCK,Reach-1,3
Up Type=0
Dn Type=3
Dn Slope=0.005
Boundary for River Rch & Prof#=UNT017 IN ROCK,Reach-1,4
Up Type=0
Dn Type=3
Dn Slope=0.005
Boundary for River Rch & Prof#=UNT017 IN ROCK,Reach-1,5
Up Type=0
Dn Type=3
Dn Slope=0.005
Boundary for River Rch & Prof#=UNT017 IN ROCK,Reach-1,6
Up Type=0
Dn Type=3
Dn Slope=0.005
Boundary for River Rch & Prof#=UNT017 IN ROCK,Reach-1,7
Up Type=0
Dn Type=3
Dn Slope=0.005

--- UNT017 IN ROCK.g01 (geometry) ---

Geom Title=Existing Conditions

River Reach=UNT017 IN ROCK,Reach-1
Reach XY= 30
      3640318.56     10173650.81      3640268.91     10173761.75
      3640279.20     10173879.15      3640349.51     10173986.79
      3640298.59     10174195.99      3640356.45     10174269.78
      3640287.01     10174298.42      3640273.12     10174364.40
      3640279.20     10174412.14      3640344.30     10174450.33
      3640369.48     10174506.76      3640298.41     10174696.86
      3640263.57     10174955.54      3640278.33     10175115.26
      3640256.63     10175224.64      3640298.18     10175335.66
      3640240.31     10175386.07      3640182.42     10175496.73
      3640141.19     10175650.78      3639996.97     10175721.80
      3639939.77     10175827.66      3639806.33     10175859.68
      3639781.12     10175934.81      3639658.34     10176064.71
      3639551.90     10176127.30      3639545.63     10176179.30
      3639589.41     10176200.62      3639659.50     10176313.07
      3639674.51     10176361.05      3639654.79     10176387.94

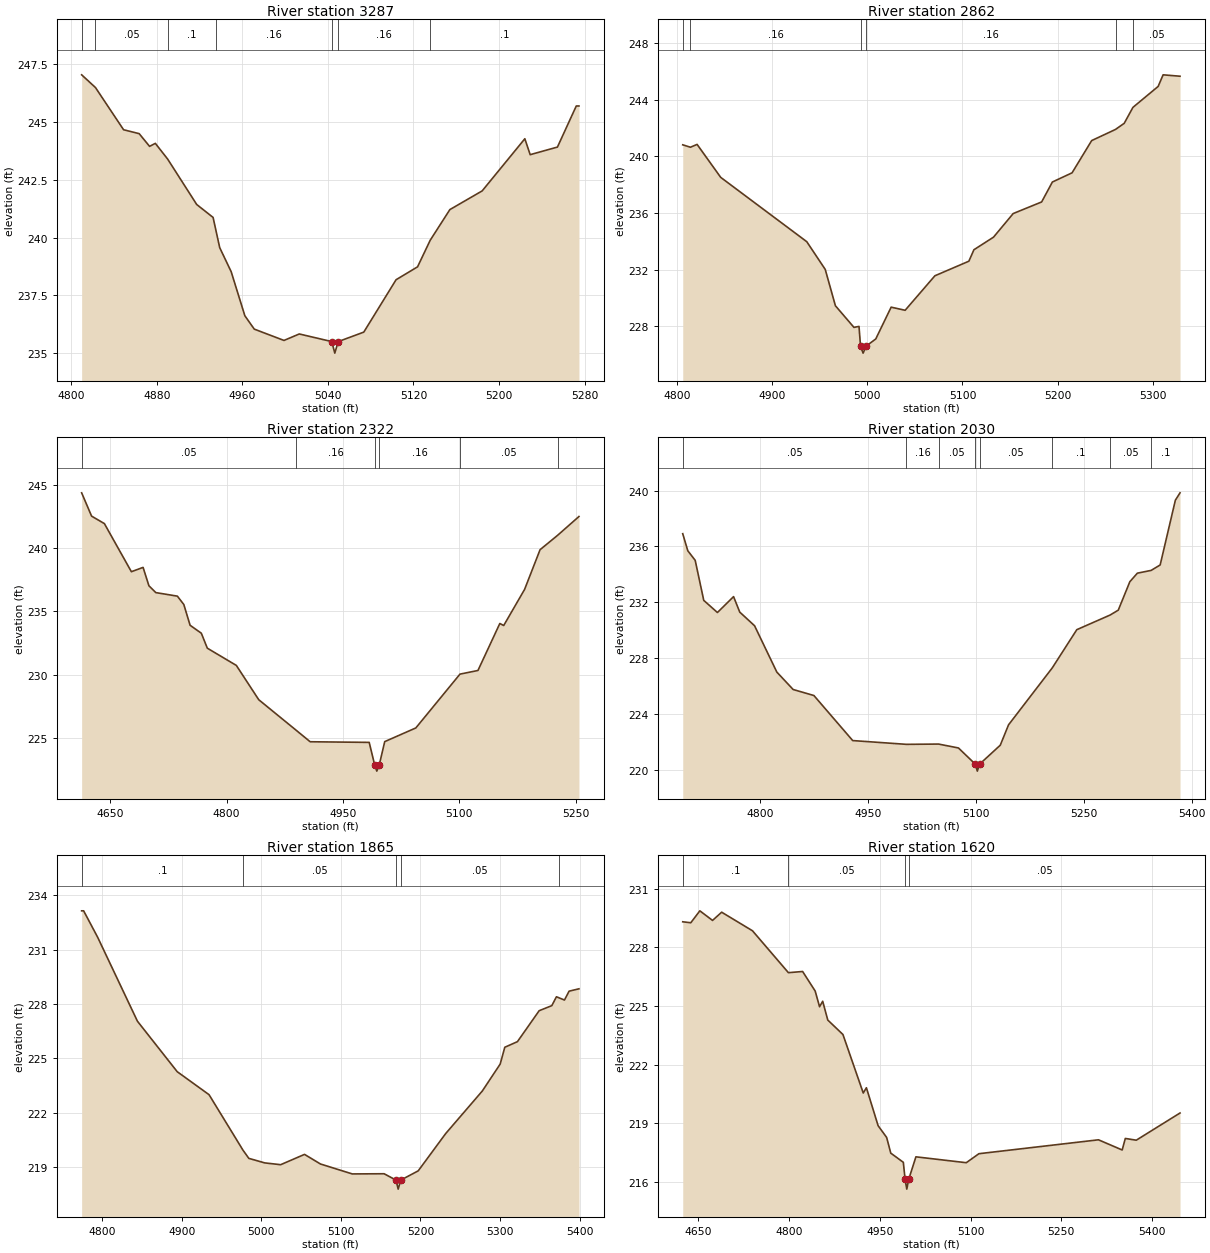
Type RM Length L Ch R = 1,3287,425,425,425
BEGIN DESCRIPTION:
UNT017 IN ROCK 5.0
END DESCRIPTION:
XS GIS Cut Line= 3
      3640092.10     10173691.64      3640268.91     10173761.75
      3640542.08     10173791.64
#Sta/Elev= 30
  4809.8  247.05  4822.7  246.50  4849.0  244.67  4863.6  244.50  4873.3  243.95
  4878.7  244.08  4890.2  243.40  4917.4  241.43  4932.7  240.87  4935.2  240.34
  4938.9  239.56  4949.6  238.52  4962.4  236.61  4971.2  236.03  4999.0  235.54
  5013.3  235.82  5043.7  235.49  5046.5  234.99  5049.7  235.49  5073.6  235.90
  5103.8  238.17  5123.9  238.73  5135.7  239.88  5154.1  241.21  5184.3  242.02
  5224.2  244.28  5229.2  243.59  5254.7  243.92  5272.3  245.70  5274.8  245.70
#Mann=7,-1,0
  4809.8     0.1       0  4822.7    0.05       0  4890.2     0.1       0
  4935.2    0.16       0  5043.7    0.07       0  5049.7    0.16       0
  5135.7     0.1       0
Bank Sta=5043.7,5049.7
Exp/Cntr=0.3,0.1

Type RM Length L Ch R = 1,2862,540,540,540
BEGIN DESCRIPTION:
UNT017 IN ROCK 4.0
END DESCRIPTION:
XS GIS Cut Line= 3
      3640142.06     10174091.63      3640322.11     10174159.87
      3640642.08     10174241.64
#Sta/Elev= 30
  4805.9  240.82  4814.0  240.65  4821.0  240.85  4845.8  238.52  4936.3  233.97
  4955.7  232.01  4966.4  229.44  4985.9  227.91  4991.2  227.98  4992.8  226.59
  4995.5  226.09  4998.8  226.59  5008.8  227.09  5025.0  229.34  5039.7  229.12
  5071.0  231.56  5106.7  232.59  5112.0  233.40  5132.6  234.29  5153.3  235.96
  5183.2  236.78  5194.5  238.19  5215.2  238.84  5235.8  241.12  5260.9  241.91
  5270.0  242.34  5279.2  243.47  5305.7  244.95  5310.9  245.77  5328.7  245.67
#Mann=6,-1,0
  4805.9     0.1       0  4814.0    0.16       0  4992.8    0.07       0
  4998.8    0.16       0  5260.9     0.1       0  5279.2    0.05       0
Bank Sta=4992.8,4998.8
Exp/Cntr=0.3,0.1

Type RM Length L Ch R = 1,2322,292,292,292
BEGIN DESCRIPTION:
UNT017 IN ROCK 3.0
END DESCRIPTION:
XS GIS Cut Line= 3
      3639985.23     10174420.98      3640250.54     10174558.96
      3640592.16     10174541.64
#Sta/Elev= 30
  4613.2  244.37  4626.0  242.53  4642.5  241.94  4677.3  238.14  4692.4  238.48
  4699.9  237.03  4708.8  236.49  4736.6  236.21  4744.9  235.55  4753.0  233.91
  4767.5  233.28  4775.2  232.10  4812.6  230.74  4841.5  228.03  4890.1  225.60
  4907.8  224.71  4983.9  224.66  4990.9  222.89  4993.7  222.39  4996.9  222.89
  5003.9  224.72  5044.0  225.80  5100.9  230.05  5124.1  230.34  5152.3  234.05
  5157.3  233.89  5184.2  236.74  5204.2  239.88  5226.7  241.01  5254.3  242.50
#Mann=6,-1,0
  4613.2    0.05       0  4890.1    0.16       0  4990.9    0.07       0
  4996.9    0.16       0  5100.9    0.05       0  5226.7     0.1       0
Bank Sta=4990.9,4996.9
Exp/Cntr=0.3,0.1

Type RM Length L Ch R = 1,2030,165,165,165
BEGIN DESCRIPTION:
Mapping XS 7f8792b3
END DESCRIPTION:
XS GIS Cut Line= 3
      3639985.28     10174760.46      3640310.84     10174841.19
      3640648.24     10174729.59
#Sta/Elev= 30
  4693.1  236.91  4700.1  235.69  4710.4  235.00  4722.3  232.13  4741.3  231.26
  4763.7  232.40  4772.3  231.29  4792.9  230.31  4823.8  226.99  4846.5  225.74
  4875.3  225.31  4929.2  222.08  5003.9  221.81  5048.5  221.83  5076.1  221.55
  5099.5  220.39  5102.3  219.89  5105.5  220.39  5134.2  221.75  5145.7  223.21
  5206.4  227.29  5240.5  230.03  5286.8  231.08  5298.1  231.43  5314.2  233.47
  5324.6  234.08  5343.8  234.28  5356.3  234.67  5377.4  239.31  5383.9  239.84
#Mann=8,-1,0
  4693.1    0.05       0  5003.9    0.16       0  5048.5    0.05       0
  5099.5    0.03       0  5105.5    0.05       0  5206.4     0.1       0
  5286.8    0.05       0  5343.8     0.1       0
Bank Sta=5099.5,5105.5
Exp/Cntr=0.3,0.1

Type RM Length L Ch R = 1,1865,245,245,245
BEGIN DESCRIPTION:
UNT017 IN ROCK 2.0
END DESCRIPTION:
XS GIS Cut Line= 3
      3640042.06     10174991.64      3640442.95     10175000.90
      3640637.84     10174890.47
#Sta/Elev= 30
  4774.2  233.15  4776.7  233.15  4794.3  231.69  4844.3  227.05  4894.3  224.26
  4934.3  222.99  4977.0  219.92  4984.3  219.47  5004.3  219.22  5024.3  219.12
  5054.3  219.69  5074.3  219.16  5114.3  218.61  5154.3  218.62  5169.3  218.27
  5172.0  217.77  5175.3  218.27  5197.2  218.78  5231.7  220.84  5277.7  223.19
  5300.2  224.68  5306.0  225.61  5321.9  225.92  5349.2  227.63  5365.1  227.91
  5370.9  228.40  5373.7  228.35  5381.0  228.22  5386.8  228.71  5399.2  228.84
#Mann=5,-1,0
  4774.2     0.1       0  4977.0    0.05       0  5169.3    0.03       0
  5175.3    0.05       0  5373.7     0.1       0
Bank Sta=5169.3,5175.3
Exp/Cntr=0.3,0.1

Type RM Length L Ch R = 1,1620,0,0,0
BEGIN DESCRIPTION:
UNT017 IN ROCK 1.0
END DESCRIPTION:
XS GIS Cut Line= 3
      3639924.83     10175190.09      3640074.79     10175290.06
      3640691.62     10175110.71
#Sta/Elev= 30
  4624.0  229.30  4637.3  229.25  4652.3  229.86  4673.3  229.37  4688.4  229.79
  4739.4  228.84  4798.8  226.70  4822.3  226.76  4843.1  225.76  4850.3  224.96
  4855.5  225.24  4863.9  224.28  4889.0  223.54  4922.6  220.55  4927.8  220.82
  4947.2  218.88  4961.3  218.28  4968.1  217.48  4988.9  217.01  4991.8  216.14
  4994.6  215.64  4997.8  216.14  5009.7  217.29  5093.0  216.99  5113.9  217.45
  5311.7  218.16  5350.9  217.64  5356.1  218.23  5374.2  218.14  5446.6  219.53
#Mann=4,-1,0
  4624.0     0.1       0  4798.8    0.05       0  4991.8    0.03       0
  4997.8    0.05       0
Bank Sta=4991.8,4997.8
Exp/Cntr=0.3,0.1

Chan Stop Cuts=-1