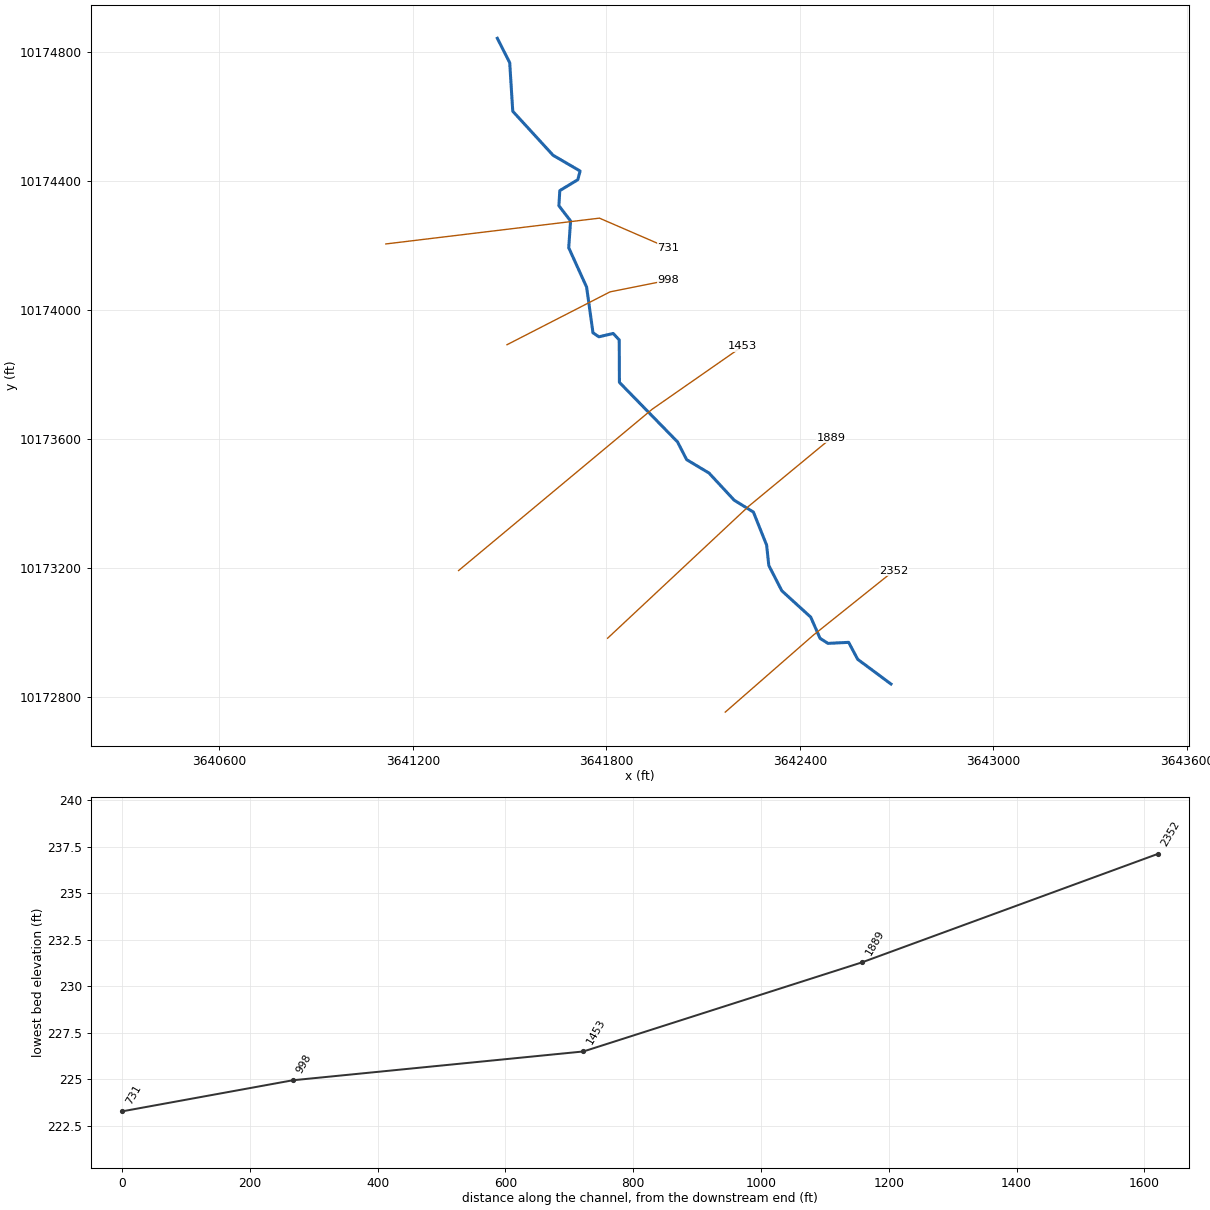
--- UNT018 IN ROCK.prj (project) ---

Proj Title=UNT018 IN ROCK Base Level Engineering
Current Plan=p01
Default Exp/Contr=0.3,0.1
English Units
Geom File=g01
Flow File=f01
Plan File=p01
BEGIN DESCRIPTION:
UNT018 IN ROCK
END DESCRIPTION:

--- UNT018 IN ROCK.p01 (plan) ---

Plan Title=Multiple Run
Short Identifier=Multiple
Geom File=g01
Flow File=f01
Subcritical Flow
K Sum by GR= 0
Std Step Tol= 0.01
Critical Tol= 0.01
Num of Std Step Trials= 20
Max Error Tol= 0.3
Flow Tol Ratio= 0.001
Split Flow NTrial= 30
Split Flow Tol= 0.02
Split Flow Ratio= 0.02
Log Output Level= 0
Friction Slope Method= 1
Unsteady Friction Slope Method= 2
Unsteady Bridges Friction Slope Method= 1
Parabolic Critical Depth
Global Vel Dist=  1 , 1 , 1
Global Log Level= 0
CheckData=True
Encroach Param= -1, 0, 0, 0
BEGIN DESCRIPTION:
Multiple Run
END DESCRIPTION:

--- UNT018 IN ROCK.f01 (steady flow) ---

Flow Title=Multiple
Number of Profiles=7
Profile Names=10-year,25-year,50-year,1pct_min,100-year,1pct_plu,500-year
River Rch & RM= UNT018 IN ROCK,Reach-1,2352
     284     366     431     374     505     683     693
Boundary for River Rch & Prof#=UNT018 IN ROCK,Reach-1,1
Up Type=0
Dn Type=3
Dn Slope=0.005
Boundary for River Rch & Prof#=UNT018 IN ROCK,Reach-1,2
Up Type=0
Dn Type=3
Dn Slope=0.005
Boundary for River Rch & Prof#=UNT018 IN ROCK,Reach-1,3
Up Type=0
Dn Type=3
Dn Slope=0.005
Boundary for River Rch & Prof#=UNT018 IN ROCK,Reach-1,4
Up Type=0
Dn Type=3
Dn Slope=0.005
Boundary for River Rch & Prof#=UNT018 IN ROCK,Reach-1,5
Up Type=0
Dn Type=3
Dn Slope=0.005
Boundary for River Rch & Prof#=UNT018 IN ROCK,Reach-1,6
Up Type=0
Dn Type=3
Dn Slope=0.005
Boundary for River Rch & Prof#=UNT018 IN ROCK,Reach-1,7
Up Type=0
Dn Type=3
Dn Slope=0.005

--- UNT018 IN ROCK.g01 (geometry) ---

Geom Title=Existing Conditions

River Reach=UNT018 IN ROCK,Reach-1
Reach XY= 30
      3642682.50     10172839.84      3642579.21     10172916.47
      3642551.23     10172969.05      3642487.09     10172965.88
      3642462.59     10172981.43      3642433.68     10173047.21
      3642344.06     10173128.88      3642303.73     10173207.30
      3642296.86     10173270.55      3642255.93     10173372.92
      3642196.42     10173409.67      3642118.36     10173493.85
      3642049.07     10173535.38      3642020.71     10173590.40
      3641840.61     10173774.93      3641840.02     10173906.55
      3641821.25     10173926.59      3641776.92     10173916.18
      3641758.66     10173928.72      3641738.89     10174070.30
      3641683.45     10174192.33      3641689.19     10174275.29
      3641653.02     10174322.48      3641655.78     10174369.39
      3641711.58     10174403.18      3641718.71     10174430.09
      3641634.77     10174479.07      3641509.94     10174615.46
      3641500.51     10174765.96      3641462.11     10174841.64

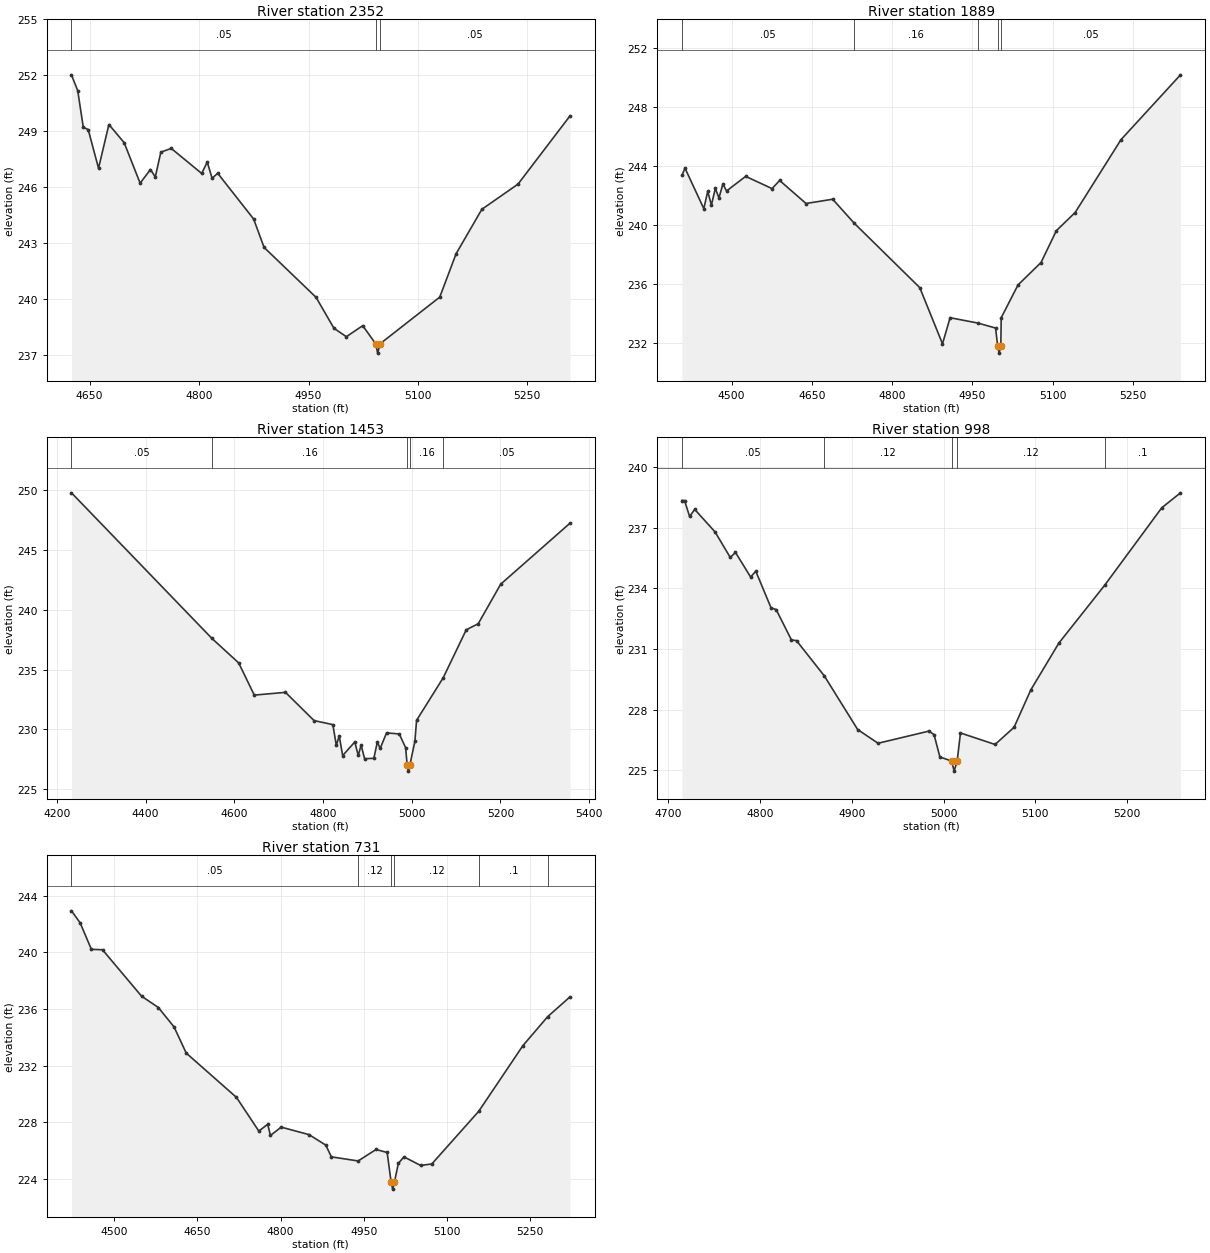
Type RM Length L Ch R = 1,2352,463,463,463
BEGIN DESCRIPTION:
UNT018 IN ROCK 5.0
END DESCRIPTION:
XS GIS Cut Line= 3
      3642168.62     10172752.70      3642442.11     10172991.64
      3642692.09     10173191.63
#Sta/Elev= 30
  4625.1  252.02  4633.7  251.17  4641.3  249.21  4648.0  249.09  4662.2  247.02
  4676.4  249.36  4697.3  248.39  4719.2  246.22  4733.4  246.95  4740.0  246.55
  4747.6  247.88  4761.9  248.08  4803.6  246.74  4811.2  247.35  4817.9  246.48
  4825.5  246.75  4874.8  244.30  4889.1  242.78  4960.3  240.11  4984.9  238.45
  5001.9  238.00  5024.3  238.59  5042.1  237.62  5044.8  237.12  5048.1  237.62
  5129.9  240.12  5152.3  242.44  5187.6  244.82  5237.2  246.17  5308.4  249.82
#Mann=3,-1,0
  4625.1    0.05       0  5042.1    0.04       0  5048.1    0.05       0
Bank Sta=5042.1,5048.1
Exp/Cntr=0.3,0.1

Type RM Length L Ch R = 1,1889,436,436,436
BEGIN DESCRIPTION:
UNT018 IN ROCK 4.0
END DESCRIPTION:
XS GIS Cut Line= 3
      3641804.01     10172981.84      3642242.11     10173391.64
      3642497.78     10173602.82
#Sta/Elev= 30
  4407.2  243.33  4412.8  243.83  4448.0  241.08  4455.3  242.25  4462.2  241.32
  4469.5  242.45  4476.3  241.81  4483.7  242.75  4490.5  242.28  4526.2  243.27
  4575.5  242.44  4589.7  242.99  4639.0  241.43  4688.8  241.72  4728.9  240.10
  4851.5  235.73  4894.0  231.92  4908.2  233.69  4959.8  233.33  4993.2  232.99
  4997.0  231.79  4999.8  231.29  5003.0  231.79  5003.7  233.69  5035.1  235.91
  5078.1  237.43  5106.8  239.59  5141.9  240.82  5227.6  245.76  5338.7  250.15
#Mann=5,-1,0
  4407.2    0.05       0  4728.9    0.16       0  4959.8    0.05       0
  4997.0    0.03       0  5003.0    0.05       0
Bank Sta=4997,5003
Exp/Cntr=0.3,0.1

Type RM Length L Ch R = 1,1453,455,455,455
BEGIN DESCRIPTION:
UNT018 IN ROCK 3.0
END DESCRIPTION:
XS GIS Cut Line= 3
      3641342.08     10173191.62      3641942.11     10173691.64
      3642223.10     10173887.37
#Sta/Elev= 30
  4233.1  249.78  4549.4  237.61  4610.0  235.55  4645.1  232.86  4715.4  233.09
  4779.8  230.73  4822.2  230.39  4830.0  228.65  4836.5  229.45  4844.3  227.80
  4871.6  228.94  4879.4  227.81  4885.9  228.68  4893.7  227.54  4914.6  227.57
  4922.4  228.93  4928.9  228.40  4943.2  229.70  4971.9  229.61  4986.2  228.46
  4989.7  227.00  4992.4  226.50  4995.7  227.00  5007.0  228.98  5010.9  230.75
  5070.9  234.31  5122.8  238.32  5149.8  238.83  5200.5  242.14  5356.6  247.24
#Mann=5,-1,0
  4233.1    0.05       0  4549.4    0.16       0  4989.7    0.07       0
  4995.7    0.16       0  5070.9    0.05       0
Bank Sta=4989.7,4995.7
Exp/Cntr=0.3,0.1

Type RM Length L Ch R = 1,998,267,267,267
BEGIN DESCRIPTION:
UNT018 IN ROCK 2.0
END DESCRIPTION:
XS GIS Cut Line= 3
      3641492.13     10173891.66      3641811.50     10174055.52
      3641992.07     10174091.64
#Sta/Elev= 30
  4715.0  238.35  4717.8  238.35  4723.3  237.56  4728.9  237.91  4751.1  236.79
  4767.6  235.53  4773.3  235.78  4789.8  234.56  4795.4  234.85  4812.0  233.04
  4817.6  232.95  4834.2  231.45  4839.8  231.41  4870.0  229.67  4906.4  227.01
  4928.6  226.33  4983.9  226.93  4989.6  226.76  4996.0  225.65  5008.8  225.45
  5011.5  224.95  5014.8  225.45  5018.4  226.84  5056.1  226.27  5076.8  227.12
  5095.0  228.97  5125.6  231.29  5175.6  234.16  5237.7  237.99  5258.1  238.73
#Mann=5,-1,0
  4715.0    0.05       0  4870.0    0.12       0  5008.8    0.07       0
  5014.8    0.12       0  5175.6     0.1       0
Bank Sta=5008.8,5014.8
Exp/Cntr=0.3,0.1

Type RM Length L Ch R = 1,731,0,0,0
BEGIN DESCRIPTION:
UNT018 IN ROCK 1.0
END DESCRIPTION:
XS GIS Cut Line= 3
      3641116.48     10174204.07      3641778.67     10174284.06
      3641992.12     10174191.64
#Sta/Elev= 30
  4422.7  242.94  4438.4  242.09  4458.6  240.22  4478.7  240.19  4549.2  236.91
  4579.5  236.11  4607.8  234.74  4629.8  232.89  4720.5  229.76  4760.8  227.38
  4776.8  227.86  4781.8  227.07  4801.1  227.66  4851.4  227.13  4881.6  226.39
  4891.7  225.56  4940.0  225.27  4972.3  226.08  4992.4  225.87  4999.5  223.78
  5002.3  223.28  5005.5  223.78  5012.6  225.10  5022.7  225.56  5052.9  224.95
  5073.0  225.06  5157.7  228.78  5237.4  233.42  5282.2  235.47  5322.3  236.86
#Mann=6,-1,0
  4422.7    0.05       0  4940.0    0.12       0  4999.5    0.07       0
  5005.5    0.12       0  5157.7     0.1       0  5282.2    0.12       0
Bank Sta=4999.5,5005.5
Exp/Cntr=0.3,0.1

Chan Stop Cuts=-1