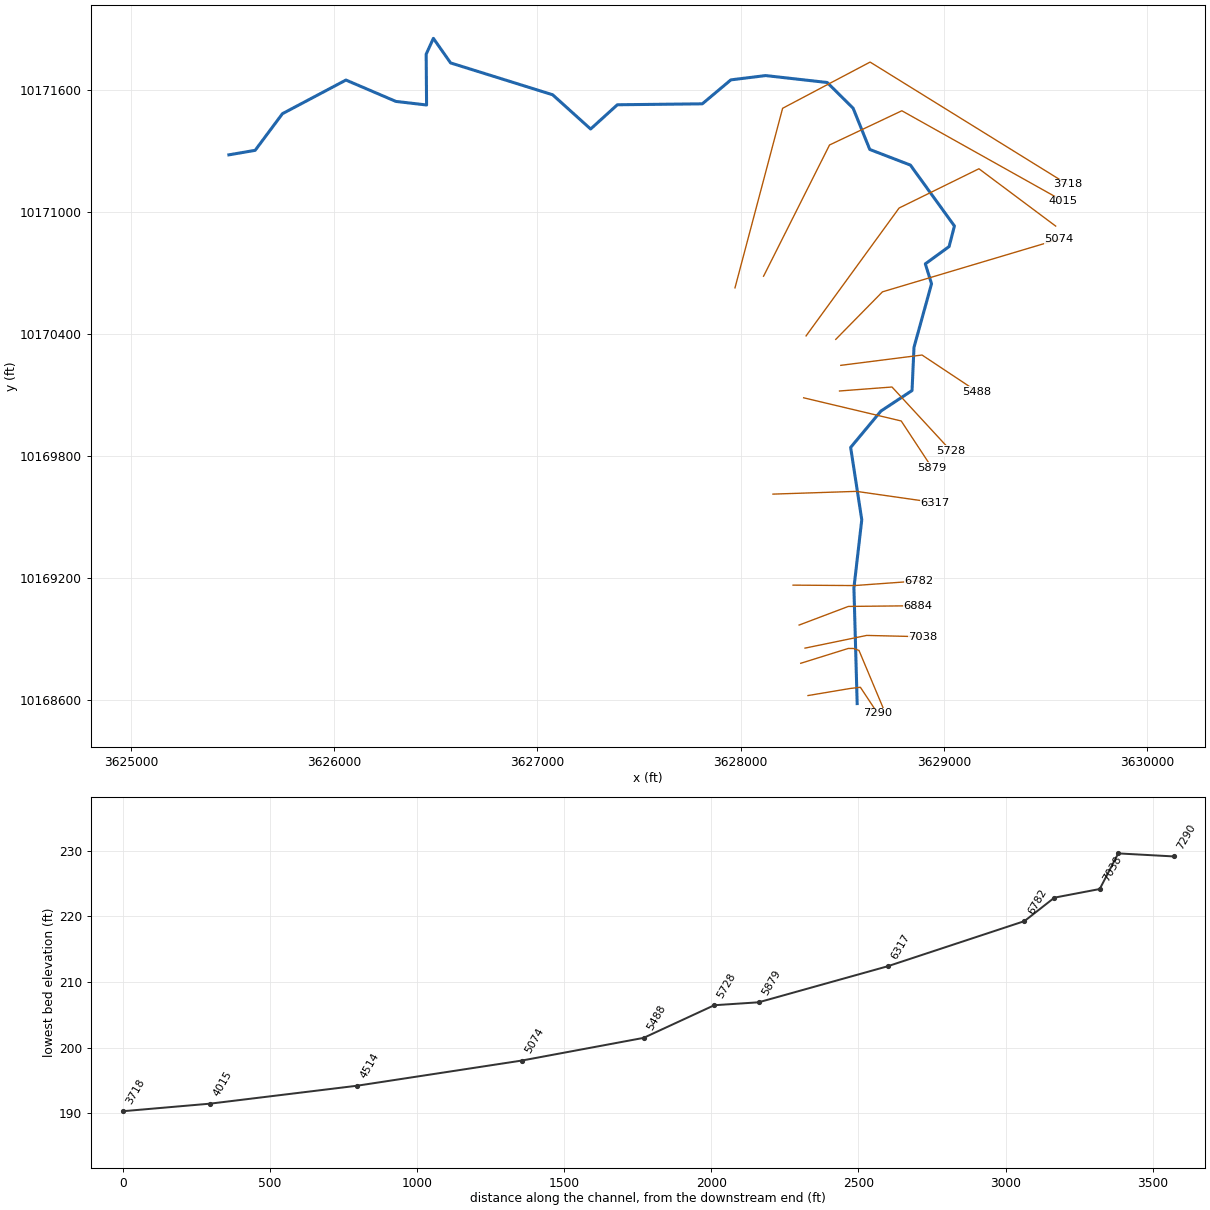
--- UNT021 IN ROCK.prj (project) ---

Proj Title=UNT021 IN ROCK Base Level Engineering
Current Plan=p01
Default Exp/Contr=0.3,0.1
English Units
Geom File=g01
Flow File=f01
Plan File=p01
Y Axis Title=Elevation
X Axis Title(PF)=Main Channel Distance
X Axis Title(XS)=Station
BEGIN DESCRIPTION:
UNT021 IN ROCK
END DESCRIPTION:
DSS Export Rating Curves= 0
DSS Export Rating Curve Sorted= 0
DSS Export Volume Flow Curves= 0
DXF OffsetX= 0
DXF OffsetY= 0
DXF ScaleX= 1
DXF ScaleY= 10

--- UNT021 IN ROCK.p01 (plan) ---

Plan Title=Multiple Run
Short Identifier=Multiple
Geom File=g01
Flow File=f01
Subcritical Flow
K Sum by GR= 0
Std Step Tol= 0.01
Critical Tol= 0.01
Num of Std Step Trials= 20
Max Error Tol= 0.3
Flow Tol Ratio= 0.001
Split Flow NTrial= 30
Split Flow Tol= 0.02
Split Flow Ratio= 0.02
Log Output Level= 0
Friction Slope Method= 1
Unsteady Friction Slope Method= 2
Unsteady Bridges Friction Slope Method= 1
Parabolic Critical Depth
Global Vel Dist=  1 , 1 , 1
Global Log Level= 0
CheckData=True
Encroach Param= -1, 0, 0, 0
BEGIN DESCRIPTION:
Multiple Run
END DESCRIPTION:

--- UNT021 IN ROCK.f01 (steady flow) ---

Flow Title=Multiple
Program Version=4.10
Number of Profiles= 7
Profile Names=10-year,25-year,50-year,1pct_min,100-year,1pct_plu,500-year
River Rch & RM=UNT021 IN ROCK,Reach-1         ,7290
     109     131     146     121     164     221     203
River Rch & RM=UNT021 IN ROCK,Reach-1         ,5074
     625     838    1011     894    1209    1635    1732
Boundary for River Rch & Prof#=UNT021 IN ROCK,Reach-1         , 1
Up Type= 0
Dn Type= 3
Dn Slope=0.003
Boundary for River Rch & Prof#=UNT021 IN ROCK,Reach-1         , 2
Up Type= 0
Dn Type= 3
Dn Slope=0.003
Boundary for River Rch & Prof#=UNT021 IN ROCK,Reach-1         , 3
Up Type= 0
Dn Type= 3
Dn Slope=0.003
Boundary for River Rch & Prof#=UNT021 IN ROCK,Reach-1         , 4
Up Type= 0
Dn Type= 3
Dn Slope=0.003
Boundary for River Rch & Prof#=UNT021 IN ROCK,Reach-1         , 5
Up Type= 0
Dn Type= 3
Dn Slope=0.003
Boundary for River Rch & Prof#=UNT021 IN ROCK,Reach-1         , 6
Up Type= 0
Dn Type= 3
Dn Slope=0.003
Boundary for River Rch & Prof#=UNT021 IN ROCK,Reach-1         , 7
Up Type= 0
Dn Type= 3
Dn Slope=0.003
DSS Import GetInterval= 0
DSS Import GetPeak= 0
DSS Import FillOption= 0

--- UNT021 IN ROCK.g01 (geometry) ---

Geom Title=Existing Conditions
Program Version=4.10

River Reach=UNT021 IN ROCK  ,Reach-1
Reach XY= 30
      3628573.75     10168581.36      3628557.74     10169150.61
       3628596.4     10169486.01      3628541.65     10169841.83
       3628690.8     10170020.95       3628843.8     10170121.86
      3628853.36     10170334.38       3628939.7     10170647.05
       3628909.1      10170745.2      3629026.13      10170830.1
      3629052.31     10170931.51      3628835.69     10171231.25
      3628635.75     10171308.14      3628553.87     10171511.02
      3628426.12     10171637.67      3628123.11     10171671.78
      3627952.25     10171650.55      3627811.78     10171532.71
      3627393.57      10171528.1       3627262.1     10171408.71
      3627075.05     10171577.38      3626573.03     10171734.03
      3626488.21     10171854.99      3626452.87     10171776.96
      3626454.82     10171526.96      3626303.37     10171544.67
      3626058.09     10171649.71      3625745.55     10171484.19
      3625611.29     10171303.85      3625482.11     10171281.64

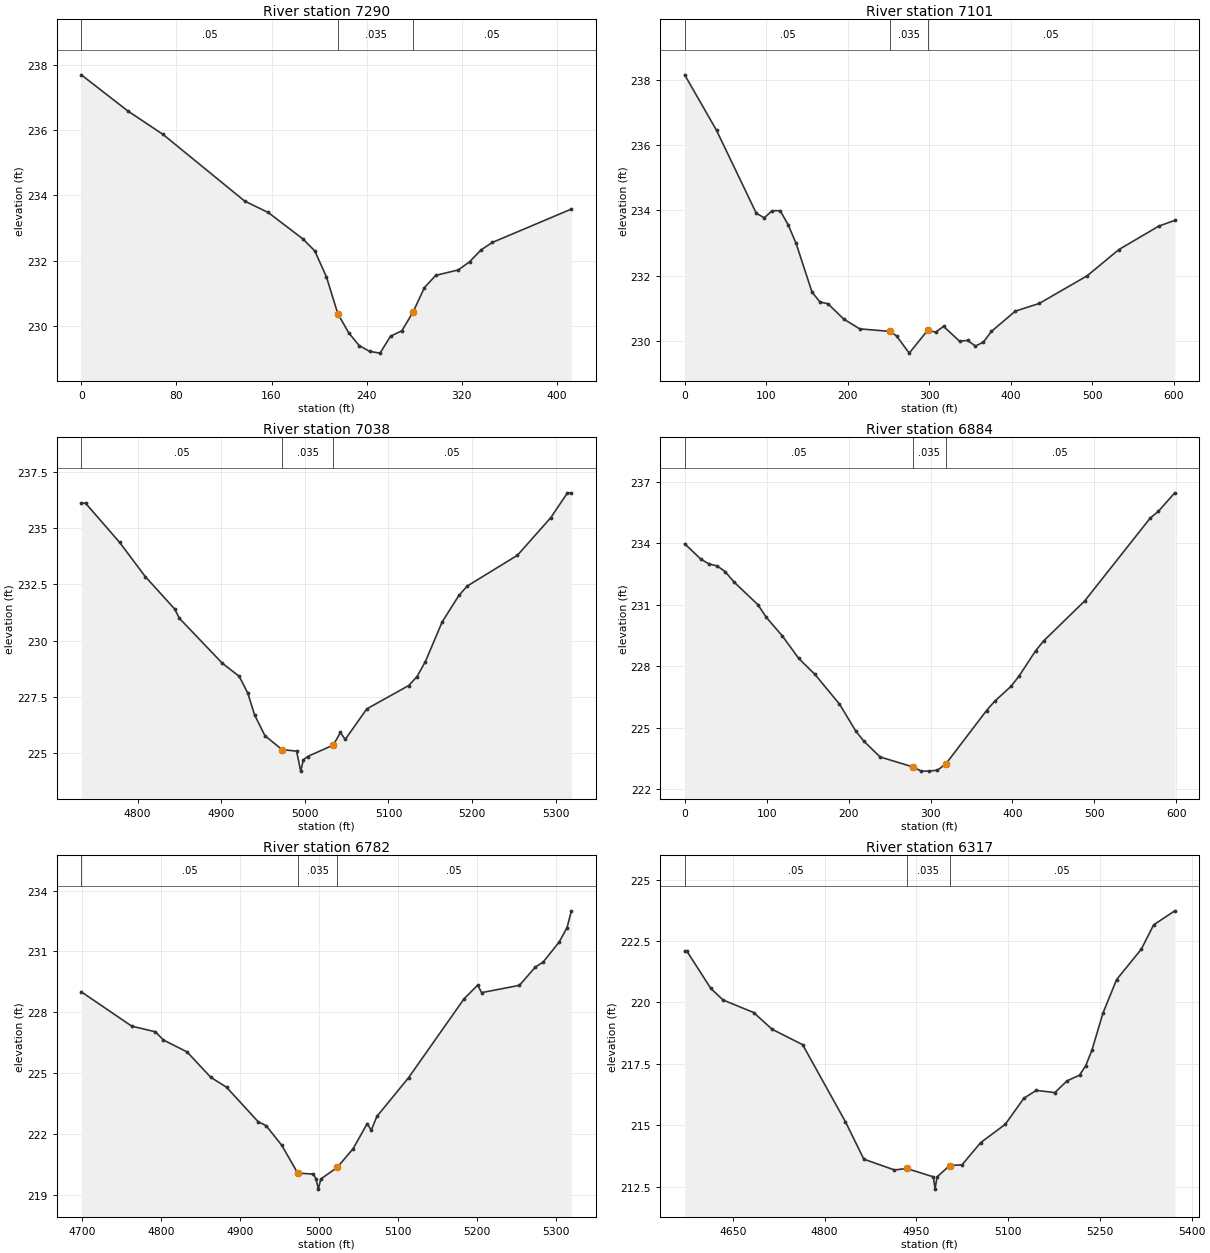
Type RM Length L Ch R = 1 ,7290    ,189,189,189
XS GIS Cut Line= 4
     3628331.755    10168620.831     3628538.352    10168655.553
     3628589.567    10168661.629     3628674.636    10168533.157
#Sta/Elev= 23
       0237.702239.27836236.589468.73713235.8733137.4743233.8259157.1134233.4796
186.5722232.6608196.3918232.2979206.2114231.4987  215.77  230.37224.8428229.7897
233.6545229.3949242.4663229.2151251.2781229.1611260.0899229.6806269.5967229.8466
279.1035 230.426288.6104231.1725298.1172231.5477317.1309231.7155326.6377231.9664
336.1445232.3271345.6513232.5567412.1991233.5826
#Mann= 3 , 0 , 0
       0     .05       0  215.77    .035       0279.1035     .05       0
Bank Sta=215.77,279.1035
XS Rating Curve= 0 ,0
Exp/Cntr=0.3,0.1

Type RM Length L Ch R = 1 ,7101    ,63,63,63
XS GIS Cut Line= 5
     3628296.164    10168779.685     3628529.671    10168852.601
     3628554.845    10168852.601     3628582.623    10168843.053
     3628700.678    10168561.803
#Sta/Elev= 30
       0 238.15139.03426236.450787.82709233.911197.58566233.7689107.3442233.9877
117.1028233.9876126.8614233.5625136.6199232.9882156.1371231.4982165.8956231.1904
175.6542231.1378195.1713230.6659214.6884 230.367251.9502230.2891259.9364230.1503
275.4577229.6233298.0634230.3214307.8431 230.267317.6227230.4421337.1821229.9898
346.9618230.0117356.7415229.8406366.5212229.9633376.3008 230.289405.6399230.9096
434.9789231.1458 493.657231.9916532.7758232.7983581.6742233.5165601.2336233.6897
#Mann= 3 , 0 , 0
       0     .05       0251.9502    .035       0298.0634     .05       0
Bank Sta=251.9502,298.0634
XS Rating Curve= 0 ,0
Exp/Cntr=0.3,0.1

Type RM Length L Ch R = 1 ,7038    ,154,154,154
BEGIN DESCRIPTION:
Mapping XS 66532c3f
END DESCRIPTION:
XS GIS Cut Line= 3
      3628317.14     10168854.25      3628620.56     10168916.76
      3628896.59     10168910.25
#Sta/Elev= 30
  4732.8  236.12  4737.9  236.12  4778.7  234.37  4809.3  232.85  4844.4  231.41
  4850.2  230.99  4901.2     229  4921.6  228.41  4931.9  227.66  4939.9   226.7
  4952.3  225.77  4972.7  225.15  4990.2  225.08  4995.1  224.19  4998.3  224.69
  5003.3  224.84    5034  225.35  5042.6  225.91  5048.3   225.6  5074.1  226.96
  5124.2     228  5134.2   228.4  5144.2  229.07  5164.2  230.83  5184.2  232.01
  5194.2  232.43  5254.2   233.8  5294.2  235.48    5314  236.58  5318.7  236.58
#Mann= 3 ,-1 , 0
  4732.8     .05       0  4972.7    .035       0    5034     .05       0
Bank Sta=4972.7,5034
XS Rating Curve= 0 ,0
Exp/Cntr=0.3,0.1

Type RM Length L Ch R = 1 ,6884    ,102,102,102
XS GIS Cut Line= 3
      3628288.07    10168967.766     3628530.431    10169059.432
     3628872.792    10169062.905
#Sta/Elev= 30
       0233.967919.88213233.2109 29.8232232.982839.76426 232.88549.70533232.5973
59.64639232.123689.46959 230.99199.41066 230.387119.2928229.4636139.1749228.3727
159.0571227.5891188.8802226.1473208.7624224.8306218.7034224.3314238.5856 223.563
278.4443223.0805288.4327222.8773 298.421222.8735308.4093222.9209318.3976223.2085
368.3392 225.829378.3275226.2854398.3042227.0141408.2925227.5257428.2692228.7487
438.2575229.2361488.1991231.1804568.1057235.2221 578.094235.5531598.0706236.4538
#Mann= 3 , 0 , 0
       0     .05       0278.4443    .035       0318.3976     .05       0
Bank Sta=278.4443,318.3976
XS Rating Curve= 0 ,0
Exp/Cntr=0.3,0.1

Type RM Length L Ch R = 1 ,6782    ,465,465,465
BEGIN DESCRIPTION:
UNT021 IN ROCK 11.0
END DESCRIPTION:
XS GIS Cut Line= 3
      3628258.35     10169164.22      3628559.86     10169162.09
      3628877.61     10169185.02
#Sta/Elev= 30
  4699.2  229.01    4763  227.32    4793  227.04    4803  226.64    4833  226.05
    4863   224.8    4883  224.31    4923  222.61    4933  222.42    4953  221.44
    4973  220.08    4993  220.03  4996.3  219.79  4999.1  219.29  5002.3  219.79
    5023  220.36  5043.1  221.28    5061  222.52    5066  222.19  5073.2  222.87
  5113.3  224.78  5183.4  228.66  5200.7  229.34  5205.7  228.97  5253.6  229.33
  5273.7  230.23  5283.7  230.48  5303.8  231.46  5313.8  232.17  5319.3     233
#Mann= 3 ,-1 , 0
  4699.2     .05       0    4973    .035       0    5023     .05       0
Bank Sta=4973,5023
XS Rating Curve= 0 ,0
Exp/Cntr=0.3,0.1

Type RM Length L Ch R = 1 ,6317    ,438,438,438
BEGIN DESCRIPTION:
UNT021 IN ROCK 10.0
END DESCRIPTION:
XS GIS Cut Line= 3
      3628159.42     10169612.14      3628570.28     10169625.63
      3628956.27     10169570.47
#Sta/Elev= 30
  4571.4  222.08  4575.2  222.08  4614.1  220.57  4634.1   220.1  4684.1  219.59
  4714.2  218.91  4764.2  218.28  4834.2  215.14  4864.2  213.62  4914.3  213.18
  4934.3  213.24  4977.9   212.9  4980.6   212.4  4983.9   212.9  5004.5  213.36
  5024.7  213.39    5055  214.29  5095.4  215.04  5125.8   216.1    5146  216.42
  5176.3  216.33  5196.5  216.81  5216.7  217.04  5226.8  217.42  5236.9  218.05
  5255.1  219.57  5277.3  220.93  5317.7  222.17  5337.9  223.16  5372.4  223.73
#Mann= 3 , 0 , 0
  4571.4     .05       0  4934.3    .035       0  5004.5     .05       0
Bank Sta=4934.3,5004.5
XS Rating Curve= 0 ,0
Exp/Cntr=0.3,0.1

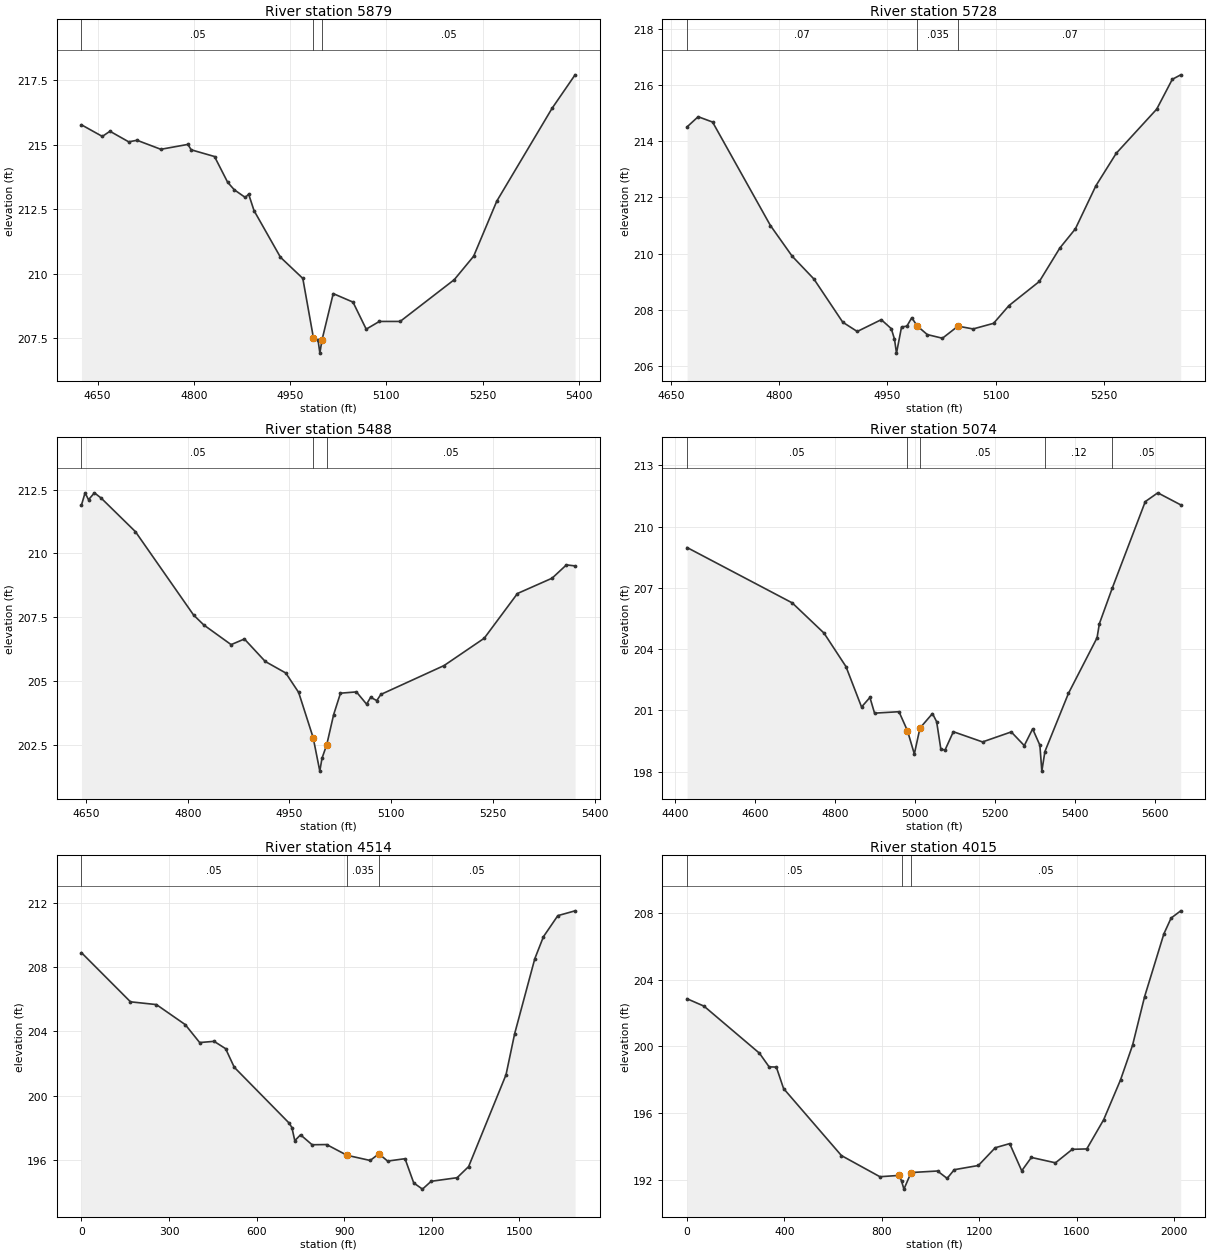
Type RM Length L Ch R = 1 ,5879    ,151,151,151
BEGIN DESCRIPTION:
UNT021 IN ROCK 9.0
END DESCRIPTION:
XS GIS Cut Line= 3
      3628310.45     10170086.09      3628790.51     10169972.03
       3628942.1     10169741.65
#Sta/Elev= 30
  4624.9  215.77  4657.4  215.32  4669.3  215.52  4698.5  215.11  4711.5  215.17
  4748.6  214.82  4790.7  215.01  4795.9   214.8  4832.2  214.54  4852.7  213.54
    4863  213.25  4880.2  212.95  4885.4  213.08  4893.8  212.44    4935  210.63
  4969.8  209.81  4986.3  207.51  4993.6  207.41  4996.4  206.91  4999.6  207.41
  5017.2  209.22    5048  208.89  5068.6  207.84  5089.1  208.14  5121.5  208.14
  5205.8  209.76    5236  210.67  5272.1  212.81  5358.2  216.41  5394.1  217.71
#Mann= 3 , 0 , 0
  4624.9     .05       0  4986.3    .035       0  4999.6     .05       0
Bank Sta=4986.3,4999.6
XS Rating Curve= 0 ,0
Exp/Cntr=0.3,0.1

Type RM Length L Ch R = 1 ,5728    ,240,240,240
BEGIN DESCRIPTION:
Mapping XS 40862f3f
END DESCRIPTION:
XS GIS Cut Line= 3
      3628486.89     10170119.64      3628745.14     10170139.18
      3629033.78     10169826.66
#Sta/Elev= 30
  4672.4  214.51  4687.7  214.87  4707.7  214.68  4787.9     211    4818  209.91
  4848.1   209.1  4888.2  207.56  4908.3  207.23  4941.6  207.65  4955.5  207.33
  4959.9  206.96  4962.7  206.46  4969.7  207.39  4977.1  207.42  4983.9  207.72
  4991.3  207.43  5005.4  207.12  5026.4  206.99    5048  207.42  5068.9  207.32
  5097.3  207.52  5118.6  208.15  5160.8  209.01  5189.2   210.2  5210.7  210.88
  5239.1  212.41  5267.4  213.57  5323.5  215.14  5345.1   216.2  5356.8  216.36
#Mann= 3 , 0 , 0
  4672.4     .07       0  4991.3    .035       0    5048     .07       0
Bank Sta=4991.3,5048
XS Rating Curve= 0 ,0
Exp/Cntr=0.3,0.1

Type RM Length L Ch R = 1 ,5488    ,414,414,414
BEGIN DESCRIPTION:
Mapping XS c70ced70
END DESCRIPTION:
XS GIS Cut Line= 3
      3628493.16      10170245.8      3628892.91     10170296.58
      3629163.76     10170116.88
#Sta/Elev= 30
  4643.2  211.89  4648.5  212.37  4653.6   212.1  4662.3  212.37  4672.4  212.16
  4722.8  210.85  4808.5  207.59  4823.6   207.2  4863.9  206.43  4883.5  206.65
  4914.3  205.77  4944.5  205.32  4963.5  204.56  4984.9  202.79  4994.7  201.48
  4997.9  201.98    5005  202.52  5015.1  203.69  5025.2  204.53  5048.7  204.58
  5063.7   204.1  5069.7  204.37  5078.7  204.24  5084.7  204.48  5177.9  205.61
  5237.2  206.68  5286.2  208.43  5337.3  209.03  5358.4  209.55  5371.2  209.51
#Mann= 3 , 0 , 0
  4643.2     .05       0  4984.9    .035       0    5005     .05       0
Bank Sta=4984.9,5005
XS Rating Curve= 0 ,0
Exp/Cntr=0.3,0.1

Type RM Length L Ch R = 1 ,5074    ,560,560,560
BEGIN DESCRIPTION:
UNT021 IN ROCK 8.0
END DESCRIPTION:
XS GIS Cut Line= 3
      3628468.38     10170373.65       3628698.2     10170607.51
       3629567.1     10170866.64
#Sta/Elev= 30
  4430.8  208.97  4693.7  206.26  4773.2  204.78  4828.1  203.14  4867.1  201.16
    4888  201.63  4899.6  200.86  4960.7  200.93  4981.9     200  4999.1  198.86
  5013.2  200.13  5044.5  200.84  5054.9  200.44  5065.4   199.1  5075.8  199.05
  5096.7  199.95  5169.7  199.45  5241.5  199.94  5274.1  199.27    5295  200.09
  5313.1  199.29    5318  198.02  5325.7  198.98  5384.6  201.83  5456.1  204.55
  5461.9  205.24  5493.9  206.97  5576.7  211.22    5608  211.65  5665.4  211.06
#Mann= 5 ,-1 , 0
  4430.8     .05       0  4981.9    .035       0  5013.2     .05       0
  5325.7     .12       0  5493.9     .05       0
Bank Sta=4981.9,5013.2
XS Rating Curve= 0 ,0
Exp/Cntr=0.3,0.1

Type RM Length L Ch R = 1 ,4514    ,499,499,499
XS GIS Cut Line= 5
     3628322.271    10170390.674      3628780.17    10171020.015
     3629172.965    10171213.157     3629550.569    10170931.039
3629550.5690977910170931.0389269
#Sta/Elev= 30
       0208.8819167.8587205.8273256.7251205.6542355.4656204.4095404.8358203.2939
 454.206203.3692493.7022 202.914523.3243 201.758710.9312198.2926720.8052198.0097
730.6793197.1919750.4274197.5558789.9975196.9384839.7375196.9506909.3735 196.284
988.9576195.96051018.802196.37531048.646195.92291108.334196.07041138.178194.5623
1168.022194.17861197.866194.66551286.755194.88941326.179195.58121454.309201.2942
1483.878203.84851552.871208.50891582.439209.8764 1631.72211.18551690.857 211.485
#Mann= 3 , 0 , 0
       0     .05       0909.3735    .035       01018.802     .05       0
Bank Sta=909.3735,1018.802
XS Rating Curve= 0 ,0
Exp/Cntr=0.3,0.1

Type RM Length L Ch R = 1 ,4015    ,297,297,297
XS GIS Cut Line= 4
     3628113.098    10170684.367     3628437.751      10171330.2
     3628793.654    10171498.603 3629587.055893510171054.1580597
#Sta/Elev= 30
       0 202.86169.33204 202.419297.1373199.5965336.7556198.7795366.4694198.7654
396.1831197.4783633.8929193.4577792.0026192.1893870.8238192.2693880.6765191.9336
890.5291191.4459 920.087192.44081028.466192.53251067.877  192.091097.435 192.611
1196.303192.86361265.571193.92761324.943194.1751 1374.42192.54471414.001193.3468
1512.955193.02381582.223193.83361641.595193.85661710.863195.60581780.131197.9936
1829.608 200.0741879.084202.98731958.247206.75331987.934207.70112027.515208.1348
#Mann= 3 ,-1 , 0
       0     .05       0880.6765    .035       0 920.087     .05       0
Bank Sta=870.8238,920.087
XS Rating Curve= 0 ,0
Exp/Cntr=0.3,0.1

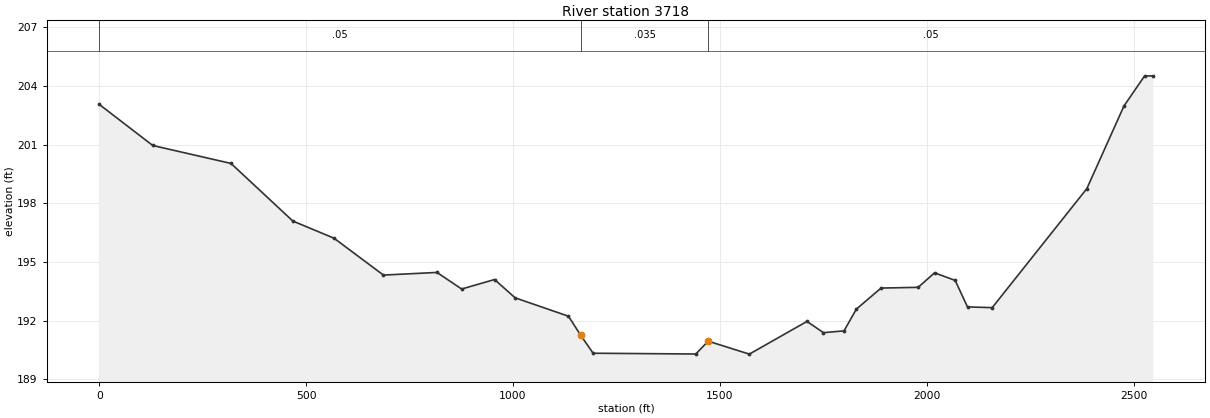
Type RM Length L Ch R = 1 ,3718    ,0,0,0
XS GIS Cut Line= 5
     3627972.473    10170627.075     3628206.848    10171510.755
     3628637.404    10171738.186     3629609.626    10171135.755
3629609.6262075310171135.7548714
#Sta/Elev= 30
       0203.0537129.4223200.9514 318.578200.0341467.9114197.0913 567.467196.2147
686.9338194.3295816.3561194.4645876.0895193.6171955.6152194.10281005.245193.1675
1134.281192.22611164.059191.24571193.836190.33531442.078190.29571471.926190.9525
1571.422190.28981710.715191.96141750.513 191.3861800.261191.47911830.109192.5889
1889.807193.66641979.352 193.7032019.151194.44392068.898 194.0572098.747192.7023
2158.444192.66552387.283198.75022476.829202.96572526.577204.49982546.476204.5117
#Mann= 3 , 0 , 0
       0     .05       01164.059    .035       01471.926     .05       0
Bank Sta=1164.059,1471.926
XS Rating Curve= 0 ,0
Exp/Cntr=0.3,0.1

Chan Stop Cuts=-1
Use User Specified Reach Order=0
Composite Channel Slope=5