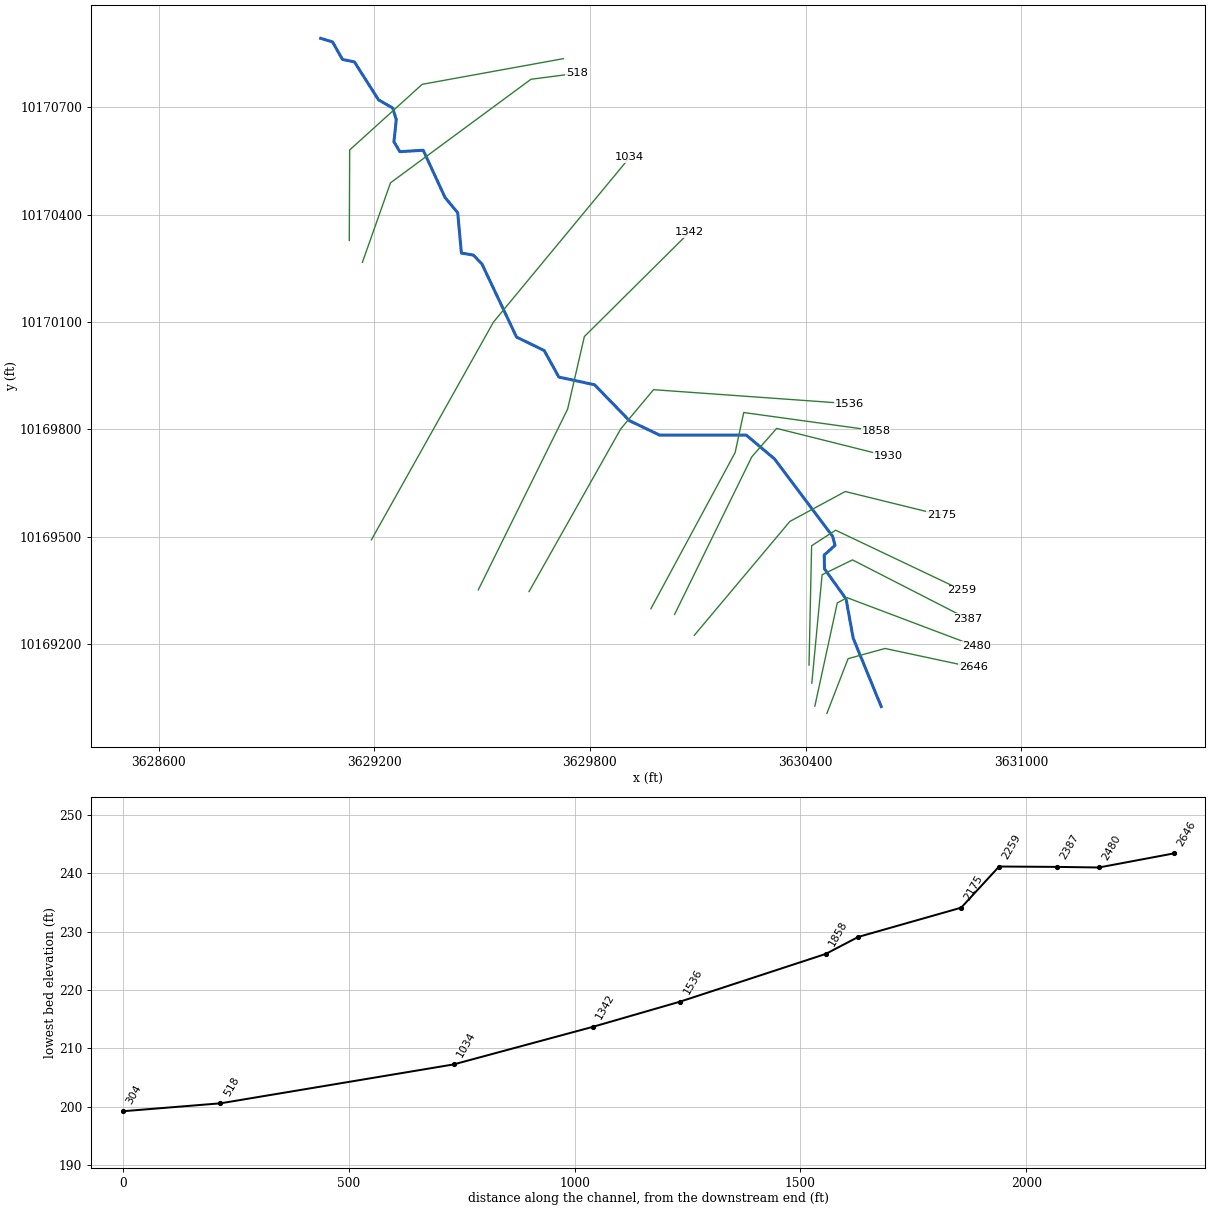
--- UNT022 IN ROCK.prj (project) ---

Proj Title=UNT022 IN ROCK Base Level Engineering
Current Plan=p01
Default Exp/Contr=0.3,0.1
English Units
Geom File=g01
Flow File=f01
Plan File=p01
Y Axis Title=Elevation
X Axis Title(PF)=Main Channel Distance
X Axis Title(XS)=Station
BEGIN DESCRIPTION:
UNT022 IN ROCK
END DESCRIPTION:
DSS Export Rating Curves= 0
DSS Export Rating Curve Sorted= 0
DSS Export Volume Flow Curves= 0
DXF OffsetX= 0
DXF OffsetY= 0
DXF ScaleX= 1
DXF ScaleY= 10

--- UNT022 IN ROCK.p01 (plan) ---

Plan Title=Multiple Run
Short Identifier=Multiple
Geom File=g01
Flow File=f01
Subcritical Flow
K Sum by GR= 0
Std Step Tol= 0.01
Critical Tol= 0.01
Num of Std Step Trials= 20
Max Error Tol= 0.3
Flow Tol Ratio= 0.001
Split Flow NTrial= 30
Split Flow Tol= 0.02
Split Flow Ratio= 0.02
Log Output Level= 0
Friction Slope Method= 1
Unsteady Friction Slope Method= 2
Unsteady Bridges Friction Slope Method= 1
Parabolic Critical Depth
Global Vel Dist=  1 , 1 , 1
Global Log Level= 0
CheckData=True
Encroach Param= -1, 0, 0, 0
BEGIN DESCRIPTION:
Multiple Run
END DESCRIPTION:

--- UNT022 IN ROCK.f01 (steady flow) ---

Flow Title=Multiple
Program Version=4.10
Number of Profiles= 7
Profile Names=10-year,25-year,50-year,1pct_min,100-year,1pct_plu,500-year
River Rch & RM=UNT022 IN ROCK,Reach-1         ,2646
     114     137     154     128     173     235     218
River Rch & RM=UNT022 IN ROCK,Reach-1         ,2480
     114     137     154     128     173     235     218
Boundary for River Rch & Prof#=UNT022 IN ROCK,Reach-1         , 1
Up Type= 0
Dn Type= 3
Dn Slope=0.005
Boundary for River Rch & Prof#=UNT022 IN ROCK,Reach-1         , 2
Up Type= 0
Dn Type= 3
Dn Slope=0.005
Boundary for River Rch & Prof#=UNT022 IN ROCK,Reach-1         , 3
Up Type= 0
Dn Type= 3
Dn Slope=0.005
Boundary for River Rch & Prof#=UNT022 IN ROCK,Reach-1         , 4
Up Type= 0
Dn Type= 3
Dn Slope=0.005
Boundary for River Rch & Prof#=UNT022 IN ROCK,Reach-1         , 5
Up Type= 0
Dn Type= 3
Dn Slope=0.005
Boundary for River Rch & Prof#=UNT022 IN ROCK,Reach-1         , 6
Up Type= 0
Dn Type= 3
Dn Slope=0.005
Boundary for River Rch & Prof#=UNT022 IN ROCK,Reach-1         , 7
Up Type= 0
Dn Type= 3
Dn Slope=0.005
DSS Import GetInterval= 0
DSS Import GetPeak= 0
DSS Import FillOption= 0

--- UNT022 IN ROCK.g01 (geometry) ---

Geom Title=Existing Conditions
Program Version=4.10

River Reach=UNT022 IN ROCK  ,Reach-1
Reach XY= 30
      3630610.61     10169025.99       3630532.7     10169216.79
      3630512.76      10169326.7      3630452.87     10169410.47
        3630452.     10169449.09      3630482.12     10169476.28
      3630475.34     10169501.72      3630313.24     10169718.11
      3630235.12     10169784.09      3629994.06     10169784.09
      3629910.07     10169824.45        3629813.     10169924.68
      3629713.69     10169946.21      3629672.81     10170020.43
      3629595.99     10170057.84       3629499.4     10170262.72
      3629475.44     10170286.94      3629442.62     10170292.41
      3629432.21     10170405.17      3629396.79     10170448.13
      3629336.37     10170579.64      3629271.27     10170575.74
      3629254.86     10170603.34      3629261.37     10170665.32
       3629251.2     10170697.73       3629211.9     10170720.53
      3629144.88     10170826.44      3629111.55     10170833.38
      3629083.92     10170882.36      3629051.04      10170892.2

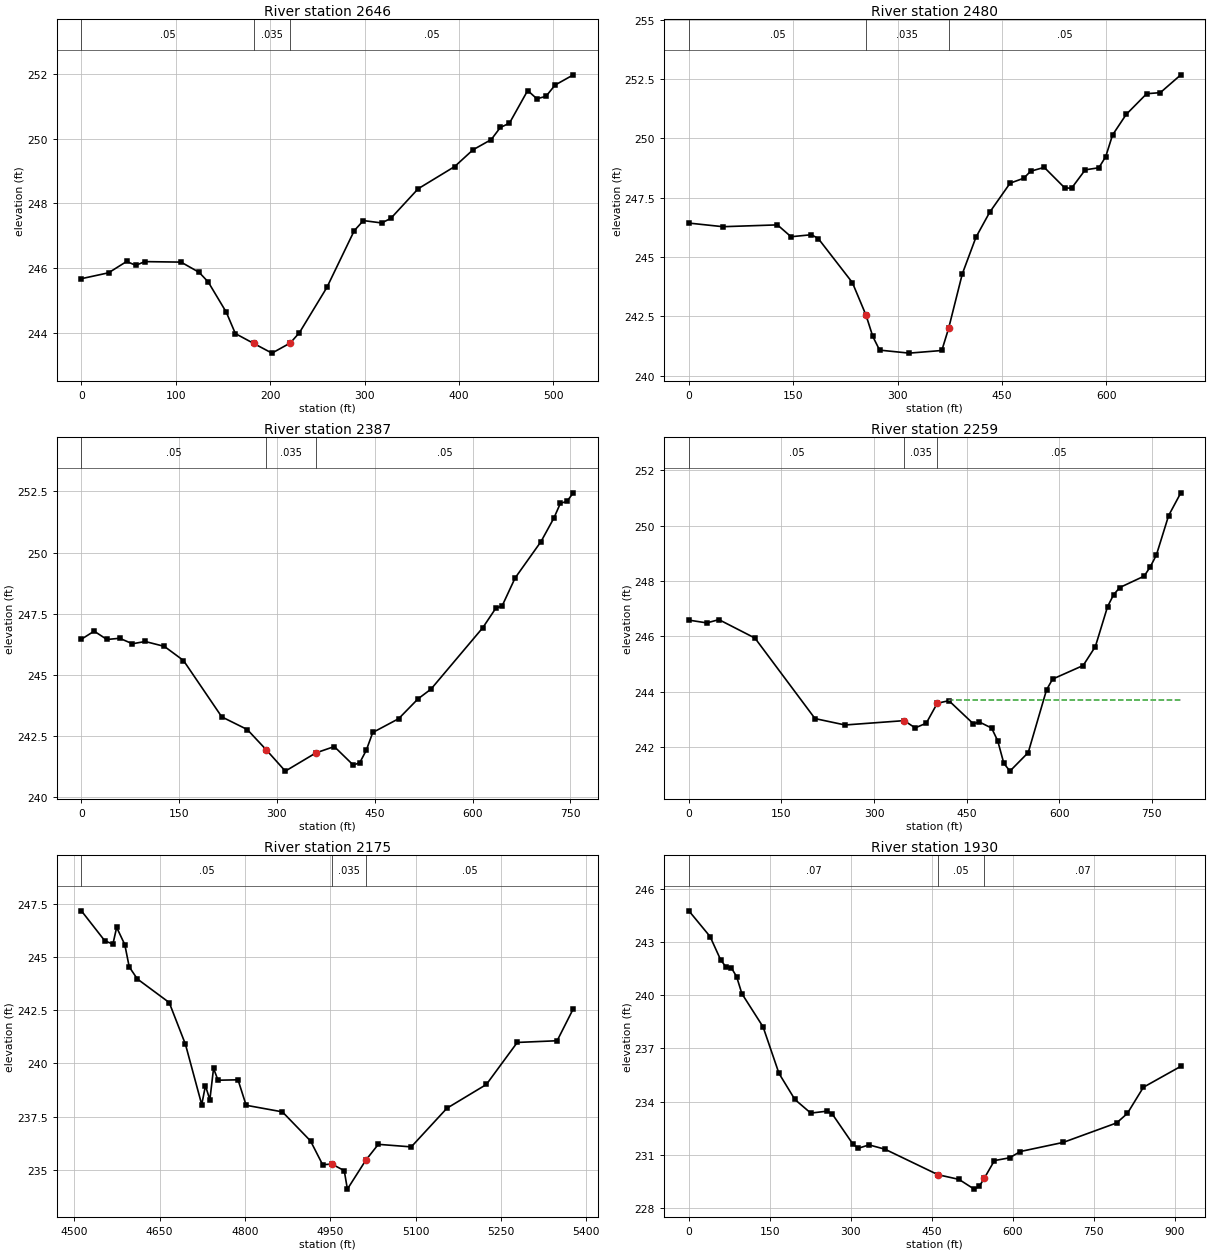
Type RM Length L Ch R = 1 ,2646    ,166,166,166
XS GIS Cut Line= 4
     3630459.445    10169006.998     3630518.473    10169159.776
     3630621.251    10169188.248     3630867.084    10169135.471
#Sta/Elev= 30
       0245.667128.78885245.849347.98141246.2002 57.5777246.079267.17398 246.195
105.5591246.1798124.7517245.8634 134.348 245.566153.5405244.6296163.1368243.9694
182.5275243.6647201.9182243.3647221.3088243.6778231.0042243.9973260.0901245.3958
289.1266247.1532298.7972247.4642318.1384247.3909327.8089247.5316356.8206248.4489
395.5029249.1353414.8441249.6521434.1852249.9685443.8558250.3432453.5264 250.477
472.8675251.4873482.5381 251.232492.2087251.3066501.8793251.6556521.2204251.9723
#Mann= 3 , 0 , 0
       0     .05       0182.5275    .035       0221.3088     .05       0
Bank Sta=182.5275,221.3088
XS Rating Curve= 0 ,0
Exp/Cntr=0.3,0.1

Type RM Length L Ch R = 1 ,2480    ,93,93,93
BEGIN DESCRIPTION:
UNT022 IN ROCK 5.0
END DESCRIPTION:
XS GIS Cut Line= 4
     3630425.975    10169027.319     3630488.355    10169315.437
     3630515.649    10169330.111     3630874.759    10169193.986
#Sta/Elev= 30
       0246.434148.95102246.2819127.2727246.3582146.8531245.8592176.2237245.9439
186.0139245.7811234.9649243.9285254.5453242.5591264.3355241.6587274.1257241.0841
316.6235240.9574363.5206241.0683373.3351242.0035 392.964244.2938 412.593245.8368
432.2219 246.885461.6654248.1153481.2943248.3227491.1088248.6165510.7378248.7808
540.1812247.9159549.9957247.9022569.6246248.6759589.2536 248.764599.0681249.2295
608.8826250.1432628.5115251.0095 657.955251.8819677.5839251.9277707.0273252.6776
#Mann= 3 , 0 , 0
       0     .05       0254.5453    .035       0373.3351     .05       0
Bank Sta=254.5453,373.3351
XS Rating Curve= 0 ,0
Exp/Cntr=0.3,0.1

Type RM Length L Ch R = 1 ,2387    ,128,128,128
BEGIN DESCRIPTION:
Mapping XS ea9b1af3
END DESCRIPTION:
XS GIS Cut Line= 4
     3630417.555    10169091.555     3630446.152     10169394.09
     3630530.642    10169435.619     3630850.454    10169271.243
#Sta/Elev= 30
       0246.453119.57668246.783439.15335246.442558.73003246.491978.30671246.2671
97.88338246.3604127.2484246.1604156.6134245.5827215.3435243.2766254.4968242.7582
283.8618241.9207312.8258241.0573359.7622241.8036387.9241242.0616417.1631241.3029
427.0889241.4054437.0147  241.91446.9405242.6379486.6438243.2016516.4213244.0142
536.2729244.4111615.6795246.9221635.5311247.7147 645.457247.8187665.3086248.9581
705.0119250.4463724.8635251.4122734.7894252.0152744.7152252.0902 754.641 252.442
#Mann= 3 , 0 , 0
       0     .05       0283.8618    .035       0359.7622     .05       0
Bank Sta=283.8618,359.7622
XS Rating Curve= 0 ,0
Exp/Cntr=0.3,0.1

Type RM Length L Ch R = 1 ,2259    ,84,84,84
BEGIN DESCRIPTION:
Mapping XS 89f9d184
END DESCRIPTION:
XS GIS Cut Line= 4
     3630409.742    10169141.902     3630416.949    10169475.145
     3630483.789    10169518.547     3630834.829    10169351.104
#Sta/Elev= 30
       0246.5845 29.1881246.484348.64683246.6032 107.023 245.935204.3167243.0228
252.9635242.7916348.6788242.9488366.5592242.6873384.4395242.8547402.3199 243.576
 421.146243.6708460.6898 242.836470.5758242.8988490.3477242.6802500.2336242.2199
510.1196241.4062520.0056241.1222549.6634241.7943579.3212244.0639589.2072244.4525
 638.637244.9432658.4089245.6289678.1808247.0743688.0667247.5088697.9526 247.764
737.4965248.1777747.3824248.5141757.2684 248.943777.0403250.3662796.8122251.1899
#Mann= 3 , 0 , 0
       0     .05       0348.6788    .035       0402.3199     .05       0
#XS Ineff= 2 , 0
                          420.91          243.68
Permanent Ineff=
       F       F
Bank Sta=348.6788,402.3199
XS Rating Curve= 0 ,0
Exp/Cntr=0.3,0.1

Type RM Length L Ch R = 1 ,2175    ,228,228,228
BEGIN DESCRIPTION:
Mapping XS a478b2ce
END DESCRIPTION:
XS GIS Cut Line= 4
      3630090.67     10169225.15      3630356.49     10169543.04
      3630510.57     10169626.59     3630778.591    10169560.374
#Sta/Elev= 30
  4512.4  247.19  4553.5  245.78  4567.8  245.62  4574.4  246.41  4588.7   245.6
  4596.5  244.55  4610.8  243.98  4666.8  242.87  4695.4   240.9    4724  238.06
  4730.5  238.95  4738.3  238.29  4744.8  239.77  4752.6  239.21  4787.8  239.23
  4802.1  238.03  4865.8  237.72  4915.3  236.35  4936.6  235.23  4952.8  235.26
  4974.6  234.95  4980.1  234.08  5012.7  235.45  5034.5  236.19  5092.4  236.07
  5155.1  237.89  5224.5  239.01  5278.8  240.99  5348.9  241.07  5377.4  242.58
#Mann= 3 , 0 , 0
  4512.4     .05       0  4952.8    .035       0  5012.7     .05       0
Bank Sta=4952.8,5012.7
XS Rating Curve= 0 ,0
Exp/Cntr=0.3,0.1

Type RM Length L Ch R = 1 ,1930    ,72,72,72
XS GIS Cut Line= 4
     3630035.737    10169283.365      3630250.58    10169723.469
     3630319.591    10169802.896     3630630.789    10169724.771
#Sta/Elev= 30
       0244.749239.28159243.301158.92238241.986168.74278241.588778.56318241.5414
88.38358241.048898.20397240.0857137.4856238.2141166.9467235.5945196.4079 234.125
225.8691233.3579255.3303233.4652265.1507233.3312304.4323231.5911314.2527231.3811
333.8935 231.567363.3547231.3247461.5587229.8882500.4152229.6254528.6012229.0763
537.9965229.2282547.3918229.6896566.1825230.6844594.3685230.8403614.1903231.1947
693.4776231.7062792.5867232.8043812.4084233.3371842.1412234.8124911.5176235.9923
#Mann= 3 , 0 , 0
       0     .07       0461.5587     .05       0547.3918     .07       0
Bank Sta=461.5587,547.3918
XS Rating Curve= 0 ,0
Exp/Cntr=0.3,0.1

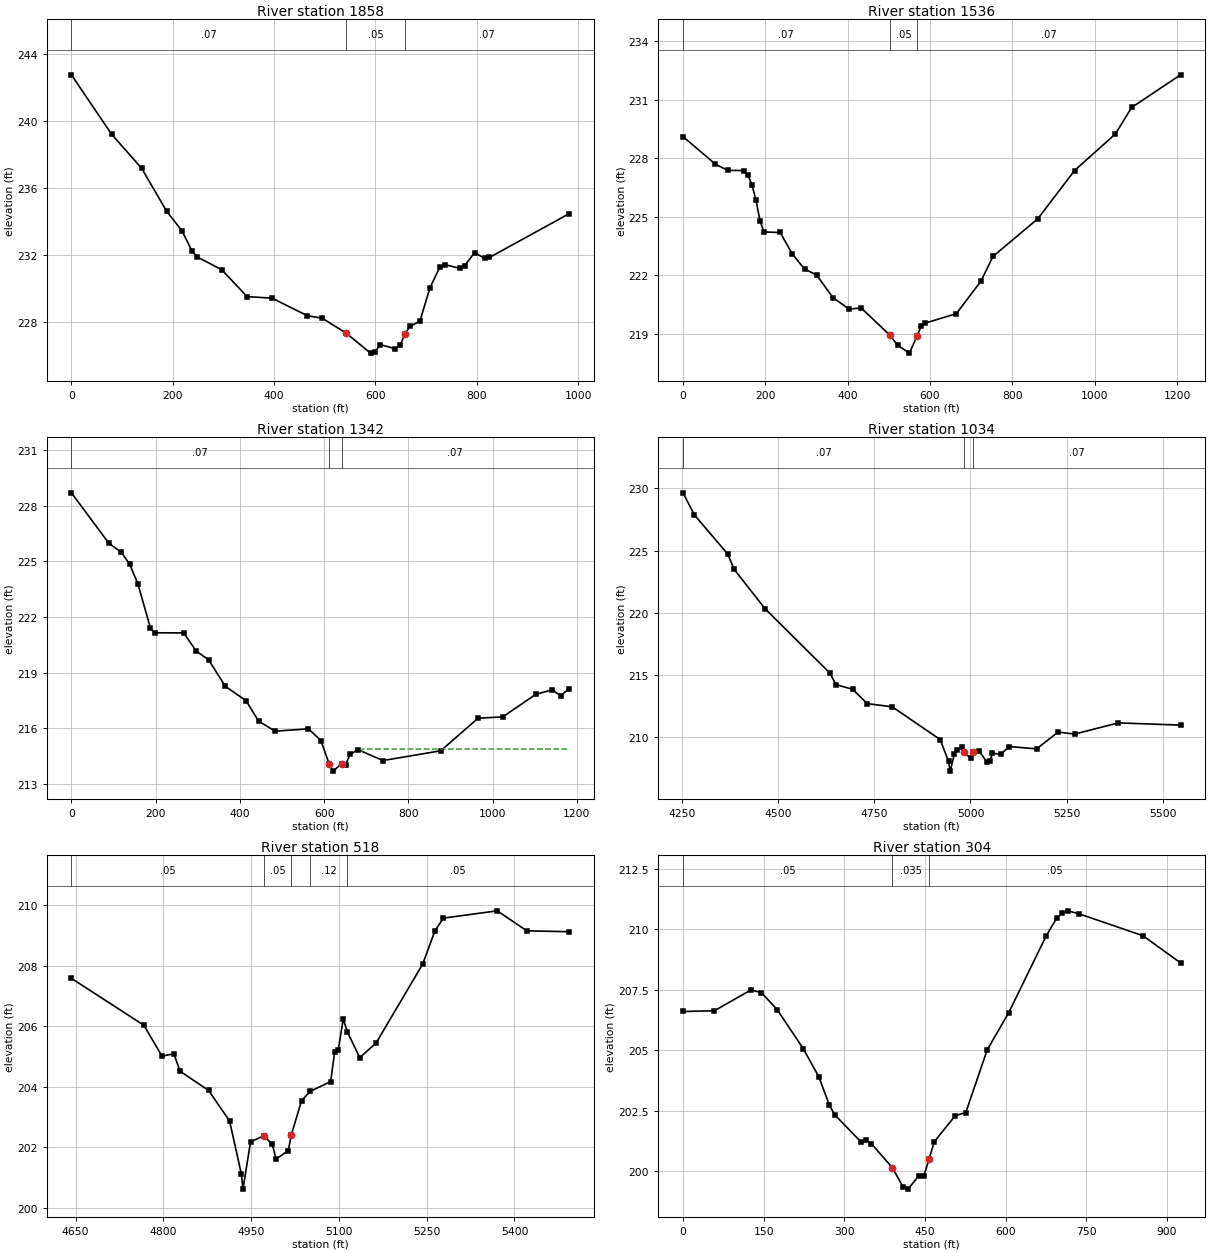
Type RM Length L Ch R = 1 ,1858    ,322,322,322
XS GIS Cut Line= 5
     3629969.825    10169299.237       3630204.2    10169735.434
     3630228.072    10169847.197      3630595.91    10169796.198
3630595.9100604610169796.1979916
#Sta/Elev= 30
       0242.755179.22832239.2156138.6496237.1844188.1673 234.614217.8779233.4721
 237.685232.2722247.5885 231.915297.1062231.1271346.6239229.5373396.1416229.4411
465.4664228.4007 495.177228.2449 542.795227.3486590.4129 226.167599.9365226.2628
609.4601226.6731638.8745226.4344648.6793226.6241658.4841227.3184668.2888227.7637
687.8984228.0757 707.508230.0472727.1176231.2871736.9224231.4436766.3367231.2219
776.1415231.3785795.7511232.1584815.3607231.8177825.1655231.8686982.0421234.4724
#Mann= 3 , 0 , 0
       0     .07       0 542.795     .05       0658.4841     .07       0
Bank Sta=542.795,658.4841
XS Rating Curve= 0 ,0
Exp/Cntr=0.3,0.1

Type RM Length L Ch R = 1 ,1536    ,194,194,194
XS GIS Cut Line= 4
     3629630.789    10169347.167     3629885.997    10169801.594
     3629977.143    10169910.969     3630521.414    10169871.906
#Sta/Elev= 30
       0229.119778.70114227.7093108.2141227.3919147.5646 227.378157.4023227.1667
167.2399226.6618177.0776225.8849186.9152224.8147196.7529 224.232236.1034 224.205
265.6164223.1008295.1293222.3332324.6422222.0209363.9928220.8715403.3434220.2764
432.8563220.3341501.7198218.9533521.3951218.4226549.9011218.0196568.9052218.9178
578.4072219.3857587.9092219.5567663.9255220.0443723.3306221.6983753.0332222.9801
861.9426224.9118951.0504227.38241050.059 229.2511089.662230.61411208.473232.2884
#Mann= 3 ,-1 , 0
       0     .07       0501.7198     .05       0568.9052     .07       0
Bank Sta=501.7198,568.9052
XS Rating Curve= 0 ,0
Exp/Cntr=0.3,0.1

Type RM Length L Ch R = 1 ,1342    ,308,308,308
XS GIS Cut Line= 4
     3629489.556    10169351.898     3629738.037    10169856.455
     3629784.695    10170059.363     3630077.664    10170351.247
#Sta/Elev= 30
       0228.699888.85592225.9816118.4746225.4928138.2203224.8553157.9661223.7783
187.5847221.4057197.4576221.1511266.5677221.1435296.1864220.1683 325.805219.6908
365.2965218.2633414.6609217.4863444.2796216.3877483.7711215.8434562.7542215.9705
592.2378215.3408611.8936214.0833621.7214213.6892641.3772214.0969651.2051214.0361
 661.033214.5894680.6888214.8435739.6561214.2599 877.042214.7887965.3257216.5446
1024.182216.61481102.656217.83721141.893218.07151161.512217.7448 1181.13218.1361
#Mann= 3 ,-1 , 0
       0     .07       0611.8936     .05       0641.3772     .07       0
#XS Ineff= 2 , 0
                          690.53          214.87
Permanent Ineff=
       F       F
Bank Sta=611.8936,641.3772
XS Rating Curve= 0 ,0
Exp/Cntr=0.3,0.1

Type RM Length L Ch R = 1 ,1034    ,516,516,516
BEGIN DESCRIPTION:
UNT022 IN ROCK 2.0
END DESCRIPTION:
XS GIS Cut Line= 3
       3629192.1     10169491.63      3629531.62     10170099.56
       3629911.1     10170560.03
#Sta/Elev= 30
    4253  229.65  4282.7  227.87  4369.5  224.72  4385.5  223.51  4466.6  220.32
  4634.6  215.16  4650.5  214.23    4694  213.85  4731.7   212.7  4796.8  212.44
  4921.3  209.81    4943  208.06  4947.4  207.27  4958.2  208.64    4965  208.97
    4979  209.18 4983.51  208.77  5001.2  208.29  5007.7   208.8  5022.1   208.9
  5042.9  207.99  5050.7  208.08  5057.2   208.7  5079.4  208.63  5100.2  209.25
  5171.9  209.06  5227.9  210.41  5270.9  210.25  5384.3  211.15    5546  210.97
#Mann= 3 , 0 , 0
    4253     .07       0 4983.51     .05       0  5007.7     .07       0
#Block Obstruct= 2 , 0
         4980.13  208.28 5015.68           208.2
Bank Sta=4983.51,5007.7
XS Rating Curve= 0 ,0
Exp/Cntr=0.3,0.1

Type RM Length L Ch R = 1 ,518     ,216,216,216
BEGIN DESCRIPTION:
UNT022 IN ROCK 1.0
END DESCRIPTION:
XS GIS Cut Line= 4
      3629167.09      10170266.6      3629245.28     10170488.65
       3629636.1     10170777.91      3629763.59     10170794.44
#Sta/Elev= 30
  4642.9  207.58  4766.8  206.03  4797.7  205.01  4817.9  205.09  4828.7  204.51
  4877.3  203.88  4913.2  202.87  4933.3  201.12    4936  200.62    4949  202.18
  4971.7  202.38  4986.3   202.1  4992.6  201.61  5013.4  201.89  5018.7  202.41
  5036.1  203.54    5051  203.85  5085.9  204.17  5092.8  205.16    5099  205.23
  5107.4  206.24  5114.3  205.82  5135.6  204.96  5163.7  205.45  5243.1  208.05
  5263.9  209.14  5278.5  209.57  5370.6  209.81    5421  209.15  5493.1  209.12
#Mann= 5 ,-1 , 0
  4642.9     .05       0  4971.7     .05       0  5018.7     .05       0
    5051     .12       0  5114.3     .05       0
#Block Obstruct= 2 , 0
         4966.48  201.59
Bank Sta=4971.7,5018.7
XS Rating Curve= 0 ,0
Exp/Cntr=0.3,0.1

Type RM Length L Ch R = 1 ,304     ,0,0,0
XS GIS Cut Line= 4
     3629130.624    10170327.623     3629131.709    10170580.444
     3629333.532    10170763.821     3629726.327    10170835.435
#Sta/Elev= 30
       0206.600258.34389206.6317126.4118207.4893145.8597207.3792175.0317206.6806
223.6516205.0654252.8235203.8929272.3295202.7289282.0825202.3375330.8474201.2194
340.6004201.2852350.3534201.1414389.3653 200.152408.8712199.3706418.6242199.2654
438.1302199.8068447.8832199.8084457.6362200.5091467.3892201.2263506.4011202.3007
 525.907202.4264565.8519205.0193605.7968 206.552675.7004209.7335695.6728210.4761
 705.659210.6594715.6453210.7572735.6177210.6419855.4523209.7286925.3558208.6081
#Mann= 3 , 0 , 0
       0     .05       0389.3653    .035       0457.6362     .05       0
Bank Sta=389.3653,457.6362
XS Rating Curve= 0 ,0
Exp/Cntr=0.3,0.1
Stream Node=UNT022 IN ROCK  ,Reach-1         , 0 , 0 ,Upstream end
Stream Node=UNT022 IN ROCK  ,Reach-1         , 0 , 1 ,Downstream end

Chan Stop Cuts=-1
Use User Specified Reach Order=0
Composite Channel Slope=5