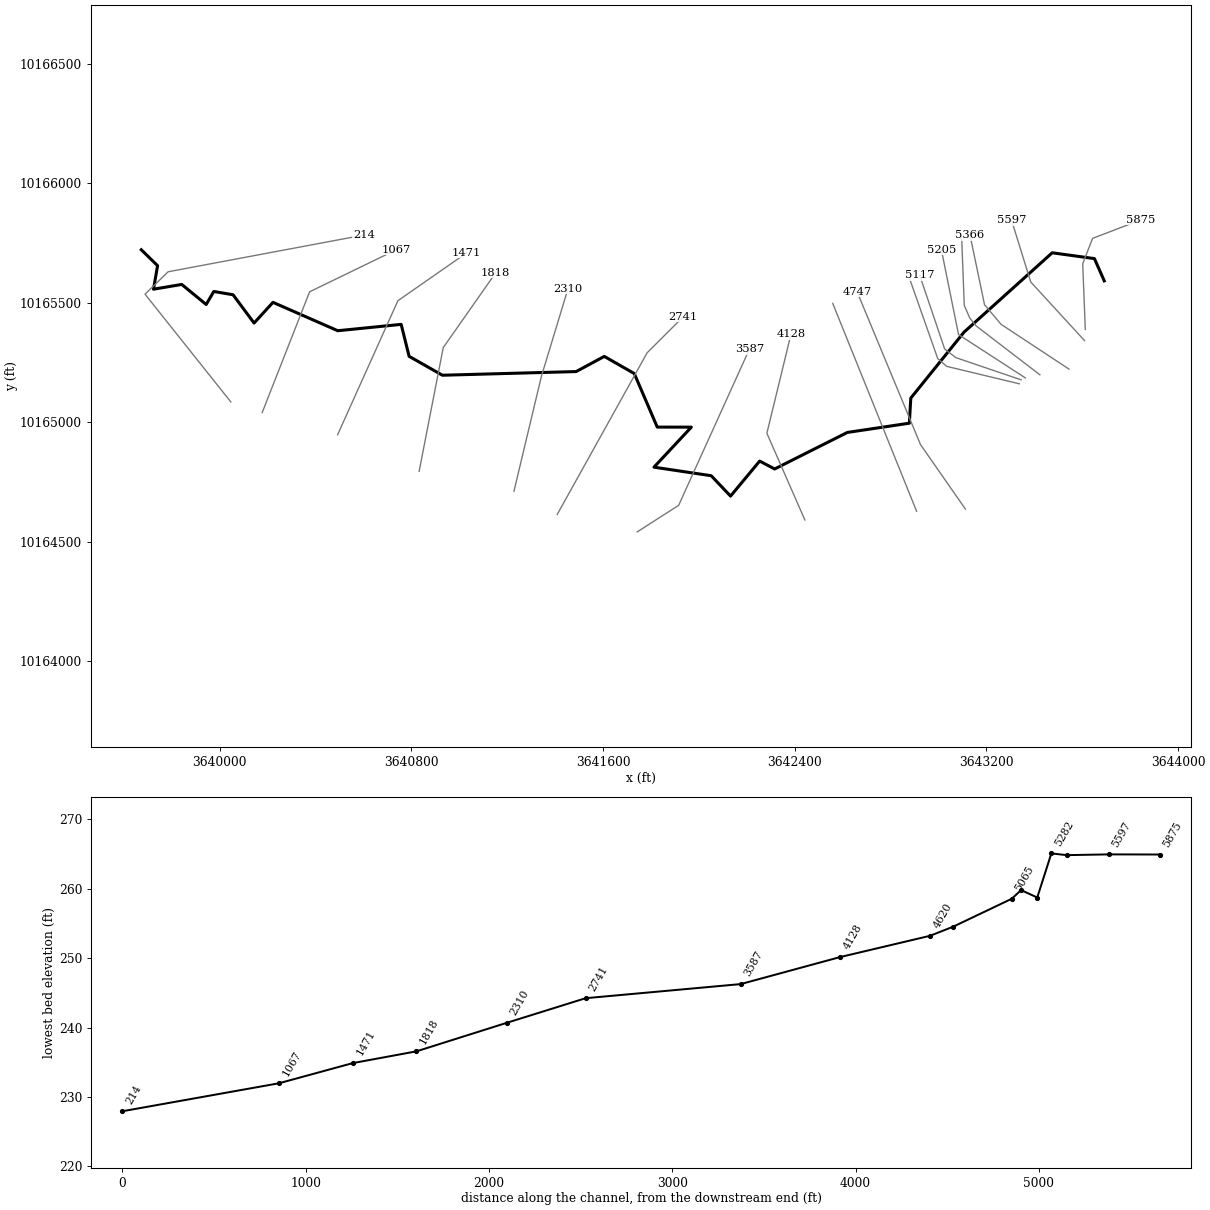
--- UNT024 IN ROCK.prj (project) ---

Proj Title=UNT024 IN ROCK Base Level Engineering
Current Plan=p01
Default Exp/Contr=0.3,0.1
English Units
Geom File=g01
Flow File=f01
Plan File=p01
Y Axis Title=Elevation
X Axis Title(PF)=Main Channel Distance
X Axis Title(XS)=Station
BEGIN DESCRIPTION:
UNT024 IN ROCK
END DESCRIPTION:
DSS Export Rating Curves= 0
DSS Export Rating Curve Sorted= 0
DSS Export Volume Flow Curves= 0
DXF OffsetX= 0
DXF OffsetY= 0
DXF ScaleX= 1
DXF ScaleY= 10

--- UNT024 IN ROCK.p01 (plan) ---

Plan Title=Multiple Run
Short Identifier=Multiple
Geom File=g01
Flow File=f01
Subcritical Flow
K Sum by GR= 0
Std Step Tol= 0.01
Critical Tol= 0.01
Num of Std Step Trials= 20
Max Error Tol= 0.3
Flow Tol Ratio= 0.001
Split Flow NTrial= 30
Split Flow Tol= 0.02
Split Flow Ratio= 0.02
Log Output Level= 0
Friction Slope Method= 1
Unsteady Friction Slope Method= 2
Unsteady Bridges Friction Slope Method= 1
Parabolic Critical Depth
Global Vel Dist=  1 , 1 , 1
Global Log Level= 0
CheckData=True
Encroach Param= -1, 0, 0, 0
BEGIN DESCRIPTION:
Multiple Run
END DESCRIPTION:

--- UNT024 IN ROCK.f01 (steady flow) ---

Flow Title=Multiple
Number of Profiles=7
Profile Names=10-year,25-year,50-year,1pct_min,100-year,1pct_plu,500-year
River Rch & RM= UNT024 IN ROCK,Reach-1,5875
     306     397     468     407     551     745     760
River Rch & RM= UNT024 IN ROCK,Reach-1,3587
     486     646     775     683     923    1249    1310
Boundary for River Rch & Prof#=UNT024 IN ROCK,Reach-1,1
Up Type=0
Dn Type=3
Dn Slope=0.005
Boundary for River Rch & Prof#=UNT024 IN ROCK,Reach-1,2
Up Type=0
Dn Type=3
Dn Slope=0.005
Boundary for River Rch & Prof#=UNT024 IN ROCK,Reach-1,3
Up Type=0
Dn Type=3
Dn Slope=0.005
Boundary for River Rch & Prof#=UNT024 IN ROCK,Reach-1,4
Up Type=0
Dn Type=3
Dn Slope=0.005
Boundary for River Rch & Prof#=UNT024 IN ROCK,Reach-1,5
Up Type=0
Dn Type=3
Dn Slope=0.005
Boundary for River Rch & Prof#=UNT024 IN ROCK,Reach-1,6
Up Type=0
Dn Type=3
Dn Slope=0.005
Boundary for River Rch & Prof#=UNT024 IN ROCK,Reach-1,7
Up Type=0
Dn Type=3
Dn Slope=0.005

--- UNT024 IN ROCK.g01 (geometry) ---

Geom Title=Existing Conditions
Program Version=4.10

River Reach=UNT024 IN ROCK  ,Reach-1
Reach XY= 30
      3643691.92     10165591.51      3643650.79     10165684.71
      3643474.57     10165709.02       3643106.4     10165377.02
       3642884.3     10165101.38      3642878.22     10164996.34
      3642619.23     10164957.66      3642316.03     10164804.89
      3642253.38      10164837.9      3642131.86     10164691.45
      3642051.14     10164776.69      3641812.15     10164812.43
      3641968.24     10164979.83      3641825.96     10164980.06
      3641729.97     10165203.99      3641604.81     10165275.71
       3641487.4     10165212.28      3640929.05     10165196.95
      3640790.16     10165275.97      3640756.95     10165409.61
       3640492.2     10165383.07      3640221.89     10165501.73
      3640142.89     10165415.15       3640055.2     10165533.51
      3639974.72      10165547.2      3639942.97     10165492.79
        3639841.     10165576.67      3639723.06      10165556.7
       3639740.1     10165655.15      3639672.11     10165721.64

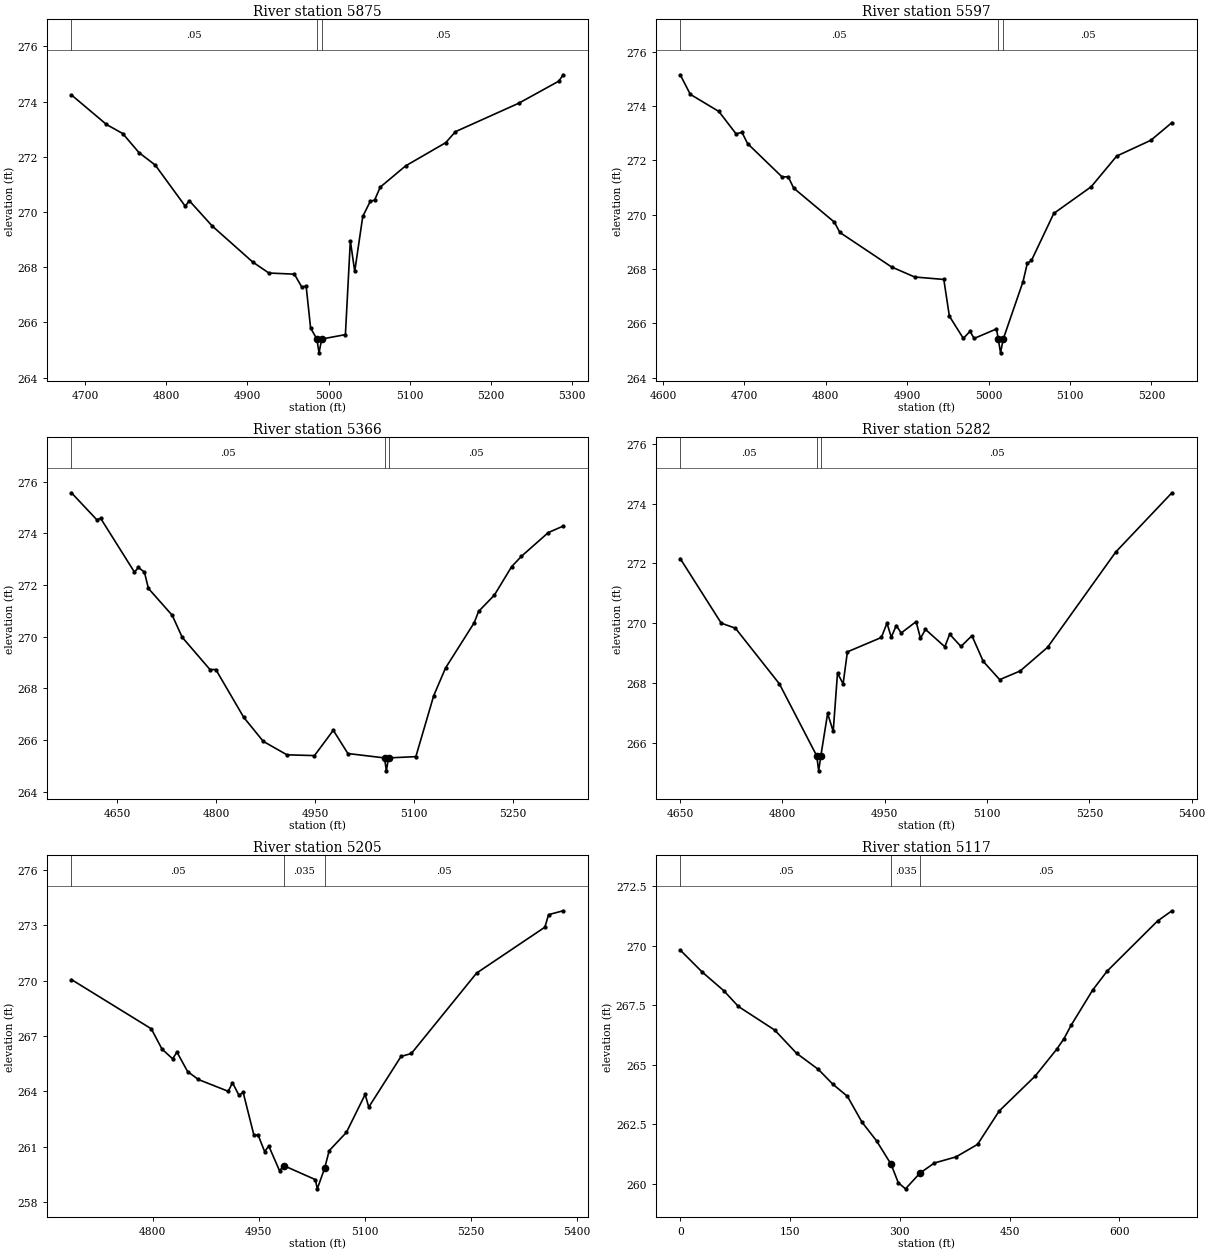
Type RM Length L Ch R = 1 ,5875    ,278,278,278
BEGIN DESCRIPTION:
UNT024 IN ROCK 11.0
END DESCRIPTION:
XS GIS Cut Line= 4
      3643612.73     10165388.44      3643601.87       10165663.
      3643643.11     10165769.34        3643846.     10165847.04
#Sta/Elev= 30
    4683  274.24  4726.2  273.17  4746.3  272.84  4766.3  272.15  4786.3   271.7
  4823.3  270.21  4828.3  270.41  4856.3   269.5  4906.4  268.19  4926.4  267.79
  4957.8  267.75    4967  267.28  4972.3  267.32  4977.8   265.8  4985.5   265.4
  4988.2   264.9  4991.5   265.4  5020.7  265.56  5026.8  268.96  5032.2  267.85
  5042.1  269.84  5051.4  270.39  5056.7  270.43  5063.6   270.9  5094.9  271.67
  5144.3  272.51  5156.4  272.91  5234.4  273.94  5283.8  274.74  5289.1  274.97
#Mann= 3 ,-1 , 0
    4683     .05       0  4985.5     .03       0  4991.5     .05       0
Bank Sta=4985.5,4991.5
XS Rating Curve= 0 ,0
Exp/Cntr=0.3,0.1

Type RM Length L Ch R = 1 ,5597    ,231,231,231
BEGIN DESCRIPTION:
Mapping XS a6496be3
END DESCRIPTION:
XS GIS Cut Line= 3
      3643609.44     10165341.86      3643384.86     10165587.05
      3643304.56      10165846.4
#Sta/Elev= 30
  4621.3  275.15  4633.7  274.43  4668.8   273.8  4689.8  272.98  4697.2  273.03
    4704  272.62  4746.5  271.39  4753.9   271.4  4760.7  270.98  4810.6  269.73
  4817.4  269.35  4880.9  268.08  4909.3  267.71  4945.1  267.62  4951.9  266.27
  4969.1  265.45  4977.2  265.71  4982.4  265.45  5009.8   265.8    5012  265.42
  5014.8  264.92    5018  265.42  5042.4  267.54  5047.6  268.21  5052.8  268.32
  5080.2  270.05  5126.1  271.03  5157.5  272.16  5199.4  272.74  5225.3  273.39
#Mann= 3 ,-1 , 0
  4621.3     .05       0    5012     .03       0    5018     .05       0
Bank Sta=5012,5018
XS Rating Curve= 0 ,0
Exp/Cntr=0.3,0.1

Type RM Length L Ch R = 1 ,5366    ,84,84,84
BEGIN DESCRIPTION:
UNT024 IN ROCK 10.0
END DESCRIPTION:
XS GIS Cut Line= 4
      3643544.71     10165222.62      3643261.13     10165409.82
      3643192.11     10165491.64      3643131.31     10165783.64
#Sta/Elev= 30
  4580.5  275.57  4618.8  274.53  4624.8  274.58    4676   272.5    4682  272.68
  4691.1   272.5  4697.1  271.87  4733.2  270.83  4748.3  269.98  4790.4  268.73
  4799.3  268.73  4841.6  266.88  4871.2  265.95  4907.1  265.43  4948.8   265.4
  4977.3  266.38  4999.4  265.48    5055  265.31  5057.7  264.81    5061  265.31
  5102.4  265.36  5129.5  267.72  5147.4  268.79  5190.8  270.54  5197.5  270.98
  5221.4  271.61  5247.5  272.71  5262.3  273.11  5303.1  274.03  5325.6  274.28
#Mann= 3 ,-1 , 0
  4580.5     .05       0    5055     .03       0    5061     .05       0
Bank Sta=5055,5061
XS Rating Curve= 0 ,0
Exp/Cntr=0.3,0.1

Type RM Length L Ch R = 1 ,5282    ,77,77,77
BEGIN DESCRIPTION:
Mapping XS 56e3829c
END DESCRIPTION:
XS GIS Cut Line= 5
      3643423.17     10165198.77      3643156.28     10165403.82
      3643130.23     10165436.37      3643107.45     10165489.54
       3643096.6     10165773.83
#Sta/Elev= 30
  4650.4  272.16  4710.5     270  4731.3  269.83  4795.7  267.97  4850.5  265.56
  4853.3  265.06  4856.5  265.56  4866.4  266.98  4874.6  266.38  4880.9  268.33
  4889.1  267.97  4895.4  269.04  4945.2  269.52  4953.4     270  4959.7  269.53
    4967  269.92  4974.2  269.67  4996.1  270.05  5002.5  269.49  5009.8  269.79
  5038.2  269.21  5045.3  269.63  5061.8  269.22  5077.9  269.58  5094.5  268.72
  5118.6  268.11  5148.6   268.4  5188.7  269.19  5288.7  272.38    5371  274.36
#Mann= 3 ,-1 , 0
  4650.4     .05       0  4850.5     .03       0  4856.5     .05       0
Bank Sta=4850.5,4856.5
XS Rating Curve= 0 ,0
Exp/Cntr=0.3,0.1

Type RM Length L Ch R = 1 ,5205    ,88,88,88
BEGIN DESCRIPTION:
Mapping XS 42221b68
END DESCRIPTION:
XS GIS Cut Line= 3
      3643362.45     10165185.71      3643083.58     10165366.92
      3643011.95     10165721.79
#Sta/Elev= 30
  4685.4  270.06  4798.2  267.39  4813.3  266.29  4828.4  265.76  4834.4  266.13
  4849.5  265.07  4864.7  264.64  4906.9     264  4912.9  264.46    4922  263.79
    4928  263.94  4943.1  261.63  4949.1  261.63  4958.3  260.73  4964.2  261.03
  4979.4  259.69  4985.3  259.97    5030  259.21  5032.7  258.71  5043.2  259.84
  5049.5  260.78  5073.8  261.77  5100.3  263.83  5105.4  263.14    5151  265.89
  5165.6  266.05  5257.7  270.41  5354.2   272.9  5359.4  273.58    5380  273.79
#Mann= 3 , 0 , 0
  4685.4     .05       0  4985.3    .035       0  5043.2     .05       0
Bank Sta=4985.3,5043.2
XS Rating Curve= 0 ,0
Exp/Cntr=0.3,0.1

Type RM Length L Ch R = 1 ,5117    ,52,52,52
XS GIS Cut Line= 4
     3643344.977    10165177.613     3643072.407    10165270.495
     3643025.532    10165306.953     3642921.366    10165615.113
#Sta/Elev= 27
       0269.816429.79171268.897659.58343268.104479.44457267.4438129.0974266.4506
158.8891265.4757188.6809264.7977 208.542264.1735228.4031263.6652248.2643262.5805
268.1254261.7958287.9866260.8097297.8497 260.034307.7128259.7758327.4391260.4363
347.1654260.8624376.6624261.1183406.1594261.6456435.6564 263.048484.8181264.5165
514.3151 265.648524.1474266.0868533.9797266.6552563.4767268.1388583.1414268.9307
651.9677271.0368671.6324271.4671
#Mann= 3 , 0 , 0
       0     .05       0287.9866    .035       0327.4391     .05       0
Bank Sta=287.9866,327.4391
XS Rating Curve= 0 ,0
Exp/Cntr=0.3,0.1

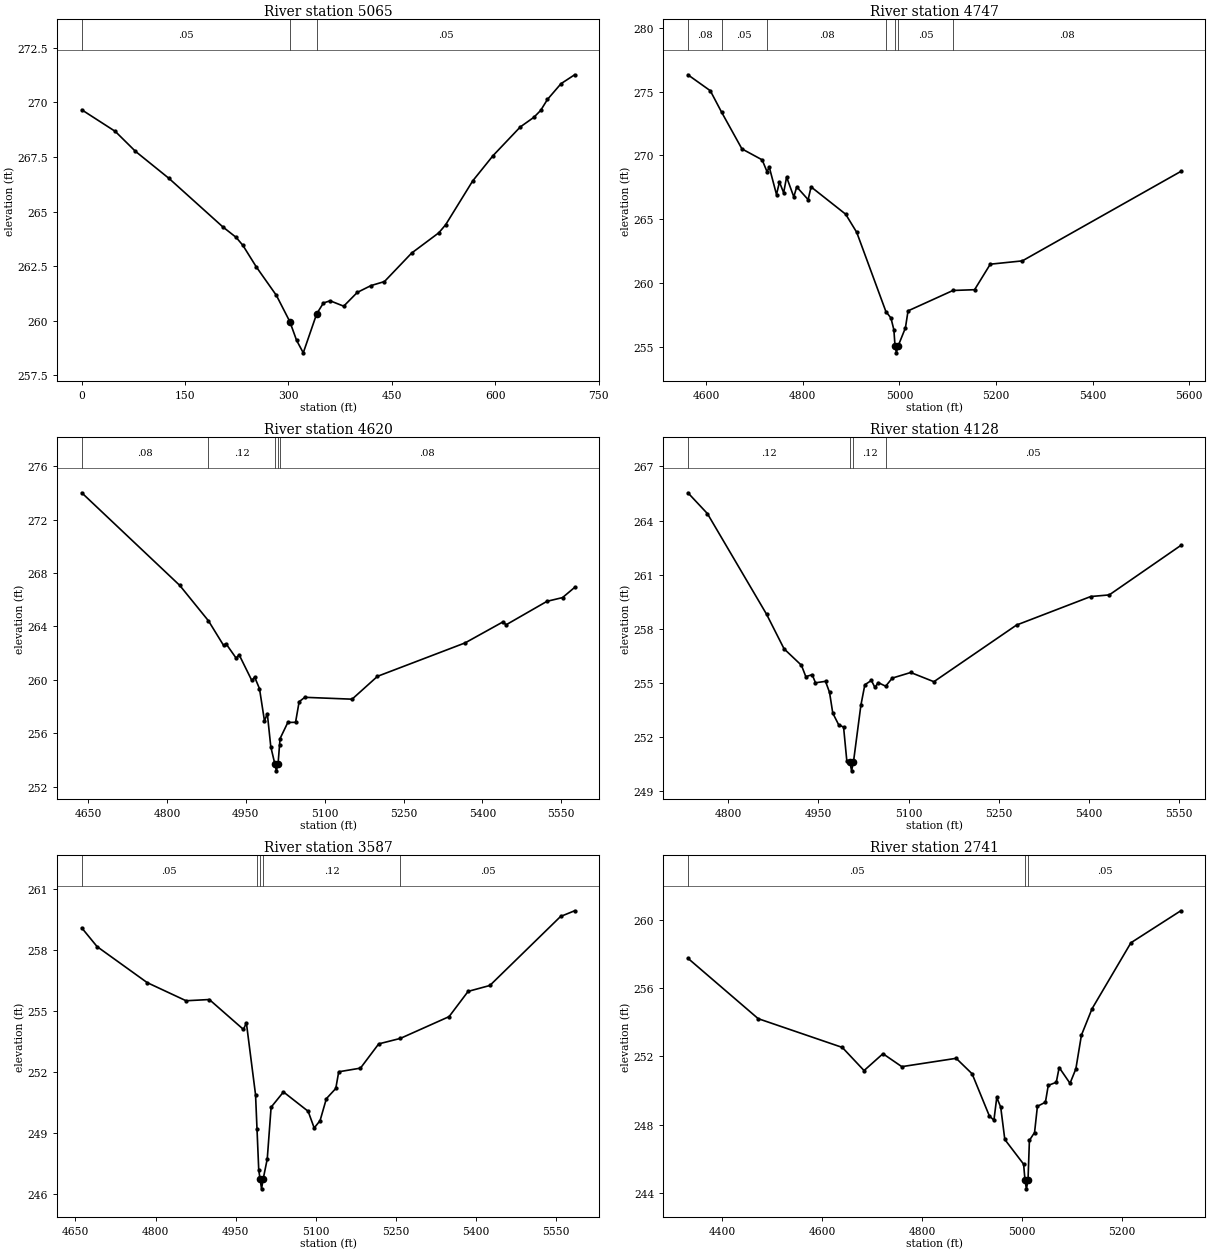
Type RM Length L Ch R = 1 ,5065    ,318,318,318
XS GIS Cut Line= 4
     3643337.164     10165161.12     3643034.213    10165234.037
     3642996.886    10165266.155     3642878.831    10165602.092
#Sta/Elev= 30
       0269.664948.70483268.673377.92773267.7606126.6326266.5183204.5603264.3007
224.0422263.8147233.7832263.4515253.2651262.4631 282.488261.1536301.9699259.9513
311.7109259.0971321.4562258.5199340.9468260.3091350.6921 260.805360.4374 260.907
380.1496260.6596399.8618261.2911419.5741261.6018439.2863261.7887478.7108263.0942
518.1353264.0237527.9915264.3895567.4159266.4072596.9843 267.567636.4088268.8791
 656.121269.3208665.9771269.6366675.8333270.1408695.5455270.8639715.2578 271.271
#Mann= 3 , 0 , 0
       0     .05       0301.9699    .035       0340.9468     .05       0
Bank Sta=301.9699,340.9468
XS Rating Curve= 0 ,0
Exp/Cntr=0.3,0.1

Type RM Length L Ch R = 1 ,4747    ,127,127,127
BEGIN DESCRIPTION:
UNT024 IN ROCK 9.0
END DESCRIPTION:
XS GIS Cut Line= 3
      3643112.44     10164636.88      3642924.75     10164907.03
        3642660.     10165546.11
#Sta/Elev= 30
    4562  276.32  4608.4  275.07  4631.6   273.4  4673.9  270.51  4715.8  269.65
  4725.8  268.73  4730.6  269.07  4745.5  266.93  4751.6  267.91  4760.3  267.07
  4766.4   268.3  4781.3  266.75  4787.4  267.53    4811  266.53  4817.1  267.53
  4888.7  265.39  4911.6  263.97    4972  257.76  4982.5  257.25  4988.6  256.32
    4991  255.02  4993.8  254.52    4997  255.02  5012.5  256.48  5017.9  257.81
    5111  259.41  5155.7  259.47  5188.2  261.47  5254.6  261.73  5582.7  268.74
#Mann= 7 ,-1 , 0
    4562     .08       0  4631.6     .05       0  4725.8     .08       0
    4972     .05       0    4991     .03       0    4997     .05       0
    5111     .08       0
Bank Sta=4991,4997
XS Rating Curve= 0 ,0
Exp/Cntr=0.3,0.1

Type RM Length L Ch R = 1 ,4620    ,492,492,492
BEGIN DESCRIPTION:
UNT024 IN ROCK 8.0
END DESCRIPTION:
XS GIS Cut Line= 2
      3642908.49     10164628.13      3642558.33     10165497.56
#Sta/Elev= 30
  4638.1     274  4824.5  267.07  4879.1  264.42  4907.7  262.59  4913.1  262.67
  4931.9  261.62  4937.3  261.89  4961.5  259.96  4966.9  260.21  4976.1  259.35
  4985.6  256.93    4991  257.48  4997.6     255  5005.4   253.7  5008.2   253.2
  5011.4   253.7  5014.2  255.11  5015.2  255.61    5030  256.82  5044.7  256.83
  5051.5  258.37  5062.3   258.7  5152.2  258.56  5200.5  260.27  5367.1  262.77
  5439.5  264.35  5444.9  264.12  5522.8  265.88  5552.4  266.16  5575.4  266.92
#Mann= 5 ,-1 , 0
  4638.1     .08       0  4879.1     .12       0  5005.4     .07       0
  5011.4     .12       0  5014.2     .08       0
Bank Sta=5005.4,5011.4
XS Rating Curve= 0 ,0
Exp/Cntr=0.3,0.1

Type RM Length L Ch R = 1 ,4128    ,541,541,541
BEGIN DESCRIPTION:
UNT024 IN ROCK 7.0
END DESCRIPTION:
XS GIS Cut Line= 3
       3642442.1     10164591.65      3642283.53     10164954.34
      3642383.83      10165367.4
#Sta/Elev= 30
  4732.5  265.54  4764.9  264.39  4863.5  258.81  4892.7  256.89  4921.6  255.98
  4928.9  255.35  4939.5  255.46    4945  255.01  4961.7  255.09  4968.4  254.48
  4973.8  253.33  4983.5  252.69  4991.8  252.55  4997.2  250.68  5002.3  250.63
  5005.1  250.13  5008.3  250.63  5020.6  253.76  5027.2   254.9  5038.1  255.14
    5044  254.75  5049.5  255.02  5061.9  254.82  5072.9  255.27  5103.6  255.58
  5142.2  255.07  5279.9  258.21  5403.4  259.79  5434.3  259.88  5553.4  262.62
#Mann= 4 ,-1 , 0
  4732.5     .12       0  5002.3     .07       0  5008.3     .12       0
  5061.9     .05       0
Bank Sta=5002.3,5008.3
XS Rating Curve= 0 ,0
Exp/Cntr=0.3,0.1

Type RM Length L Ch R = 1 ,3587    ,846,846,846
BEGIN DESCRIPTION:
UNT024 IN ROCK 6.0
END DESCRIPTION:
XS GIS Cut Line= 3
       3641742.1     10164541.64      3641915.27     10164652.89
       3642210.4     10165305.64
#Sta/Elev= 30
    4662  259.07  4690.7  258.15  4784.5  256.38  4857.2  255.49  4900.7  255.55
  4964.6  254.08    4970  254.41  4987.2  250.87  4989.9   249.2  4993.2  247.16
  4995.6  246.75  4998.4  246.25  5001.6  246.75  5009.1  247.72  5016.3  250.26
  5039.4  251.01  5085.6  250.06  5096.9  249.24  5107.9   249.6  5119.7  250.68
  5137.3  251.18  5142.8     252  5183.5  252.18  5217.6  253.37  5258.1  253.64
  5349.3  254.71  5384.9  255.95  5425.6  256.24  5557.9  259.63  5584.2  259.91
#Mann= 5 ,-1 , 0
    4662     .05       0  4989.9     .12       0  4995.6     .07       0
  5001.6     .12       0  5258.1     .05       0
Bank Sta=4995.6,5001.6
XS Rating Curve= 0 ,0
Exp/Cntr=0.3,0.1

Type RM Length L Ch R = 1 ,2741    ,431,431,431
BEGIN DESCRIPTION:
UNT024 IN ROCK 5.0
END DESCRIPTION:
XS GIS Cut Line= 3
      3641408.31     10164614.66      3641783.77     10165290.95
       3641933.8     10165440.98
#Sta/Elev= 30
  4331.6  257.77  4472.2  254.22  4640.4  252.53  4683.9  251.17  4721.7  252.16
  4759.4   251.4  4868.1  251.89    4900  250.98  4934.4  248.51  4943.6  248.25
  4949.3  249.59  4957.2  249.02  4965.4  247.12    5003  245.67  5005.8  244.72
  5008.6  244.22  5011.8  244.72  5014.6  247.07  5024.9  247.53  5030.6  249.07
  5046.6  249.31  5052.3   250.3  5068.3  250.48  5074.1  251.35  5095.8  250.42
  5107.5  251.27  5118.6  253.25  5139.8   254.8  5217.6  258.68  5317.3  260.56
#Mann= 3 ,-1 , 0
  4331.6     .05       0  5005.8     .03       0  5011.8     .05       0
Bank Sta=5005.8,5011.8
XS Rating Curve= 0 ,0
Exp/Cntr=0.3,0.1

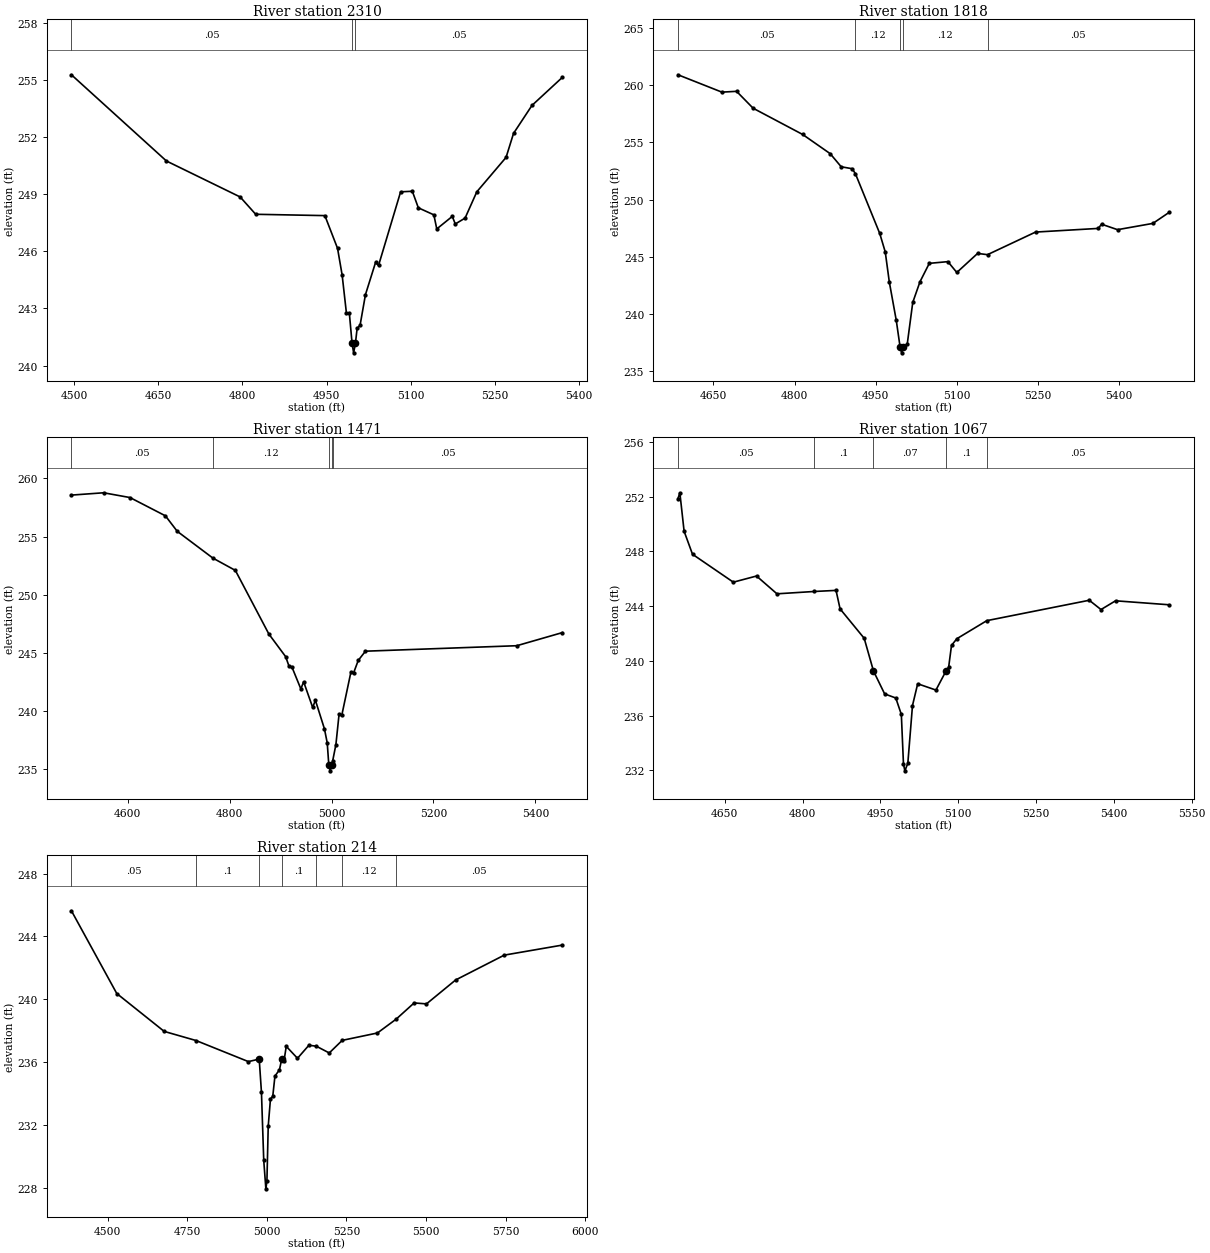
Type RM Length L Ch R = 1 ,2310    ,492,492,492
BEGIN DESCRIPTION:
UNT024 IN ROCK 4.0
END DESCRIPTION:
XS GIS Cut Line= 3
      3641227.77      10164711.9      3641342.11     10165191.64
      3641453.09     10165557.92
#Sta/Elev= 30
  4494.9  255.28  4664.4  250.75  4795.9  248.86  4823.6  247.95    4947  247.88
  4969.6  246.16  4977.8  244.76  4985.5  242.74  4990.7  242.74  4995.5  241.17
  4998.3  240.67  5001.5  241.17  5004.5  241.95  5009.8  242.12  5019.4  243.73
  5037.4  245.42  5042.7  245.26  5082.1  249.13    5103  249.16  5113.7  248.29
  5141.4  247.92  5146.6  247.18  5174.3  247.84  5179.6  247.44  5197.1  247.75
    5218  249.13  5270.2  250.94  5283.5   252.2  5316.4  253.67  5370.8  255.15
#Mann= 3 ,-1 , 0
  4494.9     .05       0  4995.5     .03       0  5001.5     .05       0
Bank Sta=4995.5,5001.5
XS Rating Curve= 0 ,0
Exp/Cntr=0.3,0.1

Type RM Length L Ch R = 1 ,1818    ,347,347,347
BEGIN DESCRIPTION:
UNT024 IN ROCK 3.0
END DESCRIPTION:
XS GIS Cut Line= 3
      3640831.93     10164795.22      3640932.63     10165312.61
      3641151.41     10165625.15
#Sta/Elev= 30
  4584.3  260.93  4665.5  259.41  4692.7  259.48  4723.3     258    4815   255.7
  4865.9  254.02  4886.3  252.87  4906.7   252.7  4912.7  252.25  4957.6  247.03
  4967.8  245.41  4975.3  242.78  4988.2  239.41  4995.3  237.07  4998.1  236.57
  5001.3  237.07  5008.5  237.34  5018.7  240.99  5032.1   242.8  5049.3  244.41
  5083.7  244.56  5100.2  243.61  5138.7  245.28    5157  245.17  5245.9  247.15
  5361.9  247.47    5368  247.84  5397.6  247.36    5463  247.91  5492.9  248.87
#Mann= 5 ,-1 , 0
  4584.3     .05       0  4912.7     .12       0  4995.3     .07       0
  5001.3     .12       0    5157     .05       0
Bank Sta=4995.3,5001.3
XS Rating Curve= 0 ,0
Exp/Cntr=0.3,0.1

Type RM Length L Ch R = 1 ,1471    ,404,404,404
BEGIN DESCRIPTION:
UNT024 IN ROCK 2.0
END DESCRIPTION:
XS GIS Cut Line= 3
      3640491.67     10164948.06      3640743.33     10165508.54
      3641029.89     10165708.47
#Sta/Elev= 30
  4489.4  258.57  4552.6  258.77  4604.4  258.36  4673.9  256.79  4697.1  255.46
    4767  253.16  4811.2   252.1    4877  246.63  4909.9  244.69  4916.5  243.87
    4922  243.82  4939.7  241.92  4945.2  242.53  4962.9  240.33  4968.3  240.94
    4986  238.49  4991.5  237.28  4994.6  235.38  4997.3  234.88  5000.6  235.38
  5002.3  235.76  5008.5  237.13  5014.7  239.73  5020.2  239.68  5037.9  243.35
  5043.3   243.3  5052.4  244.37  5066.5  245.16  5363.5  245.63  5453.2  246.76
#Mann= 5 ,-1 , 0
  4489.4     .05       0    4767     .12       0  4994.6     .07       0
  5000.6     .12       0  5002.3     .05       0
Bank Sta=4994.6,5000.6
XS Rating Curve= 0 ,0
Exp/Cntr=0.3,0.1

Type RM Length L Ch R = 1 ,1067    ,853,853,853
BEGIN DESCRIPTION:
Mapping XS ec9dd91a
END DESCRIPTION:
XS GIS Cut Line= 3
      3640176.83     10165040.69      3640374.74     10165545.89
      3640738.26     10165722.45
#Sta/Elev= 30
  4559.7  251.86  4563.3  252.28  4571.5  249.47  4587.7  247.79  4666.4  245.75
  4711.1   246.2  4750.5   244.9  4822.1  245.07  4864.4  245.15  4872.2   243.8
  4918.7  241.65  4936.6  239.26  4958.1  237.59  4979.6  237.29  4990.3  236.09
  4994.4  232.47  4997.1  231.97  5002.8  232.52  5011.8  236.74  5021.8  238.33
    5057  237.87  5076.1  239.24  5081.5  239.54    5087  241.13  5097.3  241.62
  5155.1  242.94  5352.6  244.43  5375.2  243.75  5403.3  244.39  5506.4   244.1
#Mann= 5 ,-1 , 0
  4559.7     .05       0  4822.1      .1       0  4936.6     .07       0
  5076.1      .1       0  5155.1     .05       0
Bank Sta=4936.6,5076.1
XS Rating Curve= 0 ,0
Exp/Cntr=0.3,0.1

Type RM Length L Ch R = 1 ,214     ,0,0,0
BEGIN DESCRIPTION:
UNT024 IN ROCK 1.0
END DESCRIPTION:
XS GIS Cut Line= 4
      3640045.83     10165085.34      3639687.76     10165535.86
      3639784.12     10165629.61      3640601.79     10165783.25
#Sta/Elev= 30
  4386.4  245.63  4528.8  240.37  4677.8  237.96  4777.7  237.38  4942.1  236.04
  4976.1   236.2  4983.1   234.1  4990.3  229.76    4997  227.95  5000.3  228.45
  5004.4  231.94  5011.4  233.66  5018.6  233.83  5025.5  235.12  5039.7  235.52
  5046.9  236.22  5053.8  236.07    5061  237.01  5096.3  236.25  5132.1  237.08
  5155.3  237.02    5196  236.59  5236.7  237.39  5347.3  237.86  5406.1  238.74
  5462.5  239.77  5501.3  239.71  5592.8  241.23  5745.5  242.81  5928.3  243.45
#Mann= 7 ,-1 , 0
  4386.4     .05       0  4777.7      .1       0  4976.1     .05       0
  5046.9      .1       0  5155.3     .07       0  5236.7     .12       0
  5406.1     .05       0
Bank Sta=4976.1,5046.9
XS Rating Curve= 0 ,0
Exp/Cntr=0.3,0.1

Chan Stop Cuts=-1
Use User Specified Reach Order=0
Composite Channel Slope=5