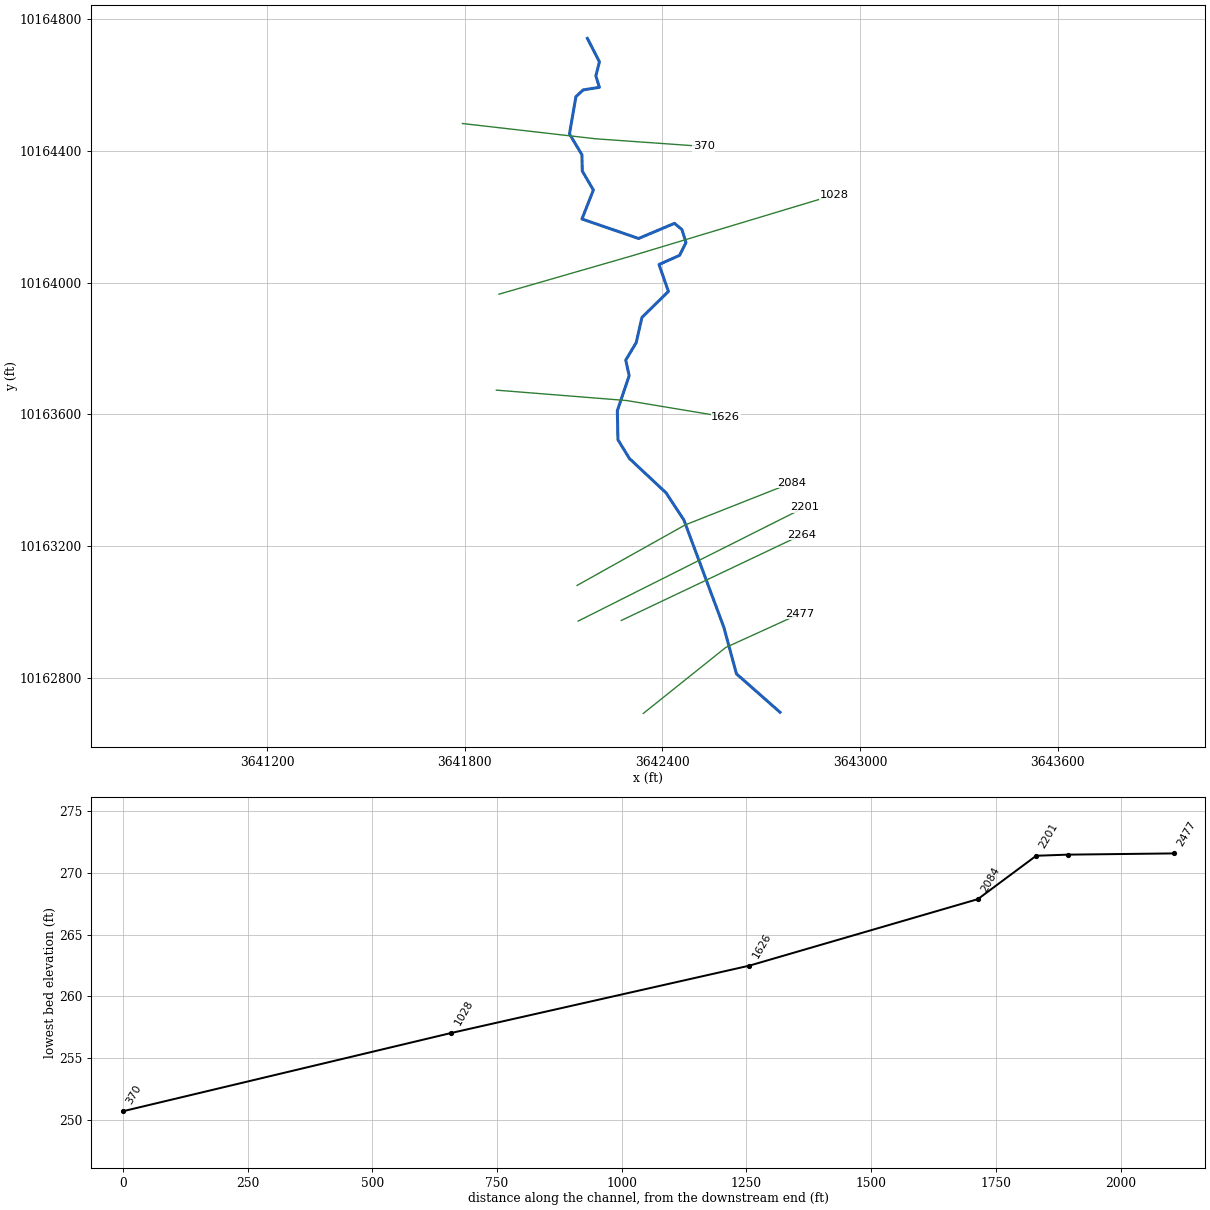
--- UNT025 IN ROCK.prj (project) ---

Proj Title=UNT025 IN ROCK Base Level Engineering
Current Plan=p01
Default Exp/Contr=0.3,0.1
English Units
Geom File=g01
Flow File=f01
Plan File=p01
BEGIN DESCRIPTION:
UNT025 IN ROCK
END DESCRIPTION:

--- UNT025 IN ROCK.p01 (plan) ---

Plan Title=Multiple Run
Short Identifier=Multiple
Geom File=g01
Flow File=f01
Subcritical Flow
K Sum by GR= 0
Std Step Tol= 0.01
Critical Tol= 0.01
Num of Std Step Trials= 20
Max Error Tol= 0.3
Flow Tol Ratio= 0.001
Split Flow NTrial= 30
Split Flow Tol= 0.02
Split Flow Ratio= 0.02
Log Output Level= 0
Friction Slope Method= 1
Unsteady Friction Slope Method= 2
Unsteady Bridges Friction Slope Method= 1
Parabolic Critical Depth
Global Vel Dist=  1 , 1 , 1
Global Log Level= 0
CheckData=True
Encroach Param= -1, 0, 0, 0
BEGIN DESCRIPTION:
Multiple Run
END DESCRIPTION:

--- UNT025 IN ROCK.f01 (steady flow) ---

Flow Title=Multiple
Number of Profiles=7
Profile Names=10-year,25-year,50-year,1pct_min,100-year,1pct_plu,500-year
River Rch & RM= UNT025 IN ROCK,Reach-1,2477
     248     315     367     315     426     576     573
Boundary for River Rch & Prof#=UNT025 IN ROCK,Reach-1,1
Up Type=0
Dn Type=3
Dn Slope=0.005
Boundary for River Rch & Prof#=UNT025 IN ROCK,Reach-1,2
Up Type=0
Dn Type=3
Dn Slope=0.005
Boundary for River Rch & Prof#=UNT025 IN ROCK,Reach-1,3
Up Type=0
Dn Type=3
Dn Slope=0.005
Boundary for River Rch & Prof#=UNT025 IN ROCK,Reach-1,4
Up Type=0
Dn Type=3
Dn Slope=0.005
Boundary for River Rch & Prof#=UNT025 IN ROCK,Reach-1,5
Up Type=0
Dn Type=3
Dn Slope=0.005
Boundary for River Rch & Prof#=UNT025 IN ROCK,Reach-1,6
Up Type=0
Dn Type=3
Dn Slope=0.005
Boundary for River Rch & Prof#=UNT025 IN ROCK,Reach-1,7
Up Type=0
Dn Type=3
Dn Slope=0.005

--- UNT025 IN ROCK.g01 (geometry) ---

Geom Title=Existing Conditions

River Reach=UNT025 IN ROCK,Reach-1
Reach XY= 30
      3642757.12     10162695.14      3642624.83     10162811.80
      3642586.81     10162952.43      3642465.45     10163278.47
      3642411.28     10163361.22      3642299.77     10163465.68
      3642264.93     10163522.82      3642263.16     10163611.14
      3642299.09     10163717.17      3642288.64     10163764.40
      3642320.33     10163817.29      3642337.81     10163894.08
      3642418.27     10163972.99      3642389.67     10164054.77
      3642452.12     10164082.51      3642471.46     10164121.33
      3642459.37     10164160.90      3642436.63     10164179.81
      3642327.65     10164133.86      3642155.63     10164192.95
      3642190.37     10164280.89      3642156.63     10164338.78
      3642155.60     10164388.00      3642117.78     10164451.46
      3642137.39     10164564.66      3642159.55     10164585.07
      3642208.69     10164592.82      3642197.91     10164627.51
      3642208.72     10164670.34      3642172.11     10164741.64

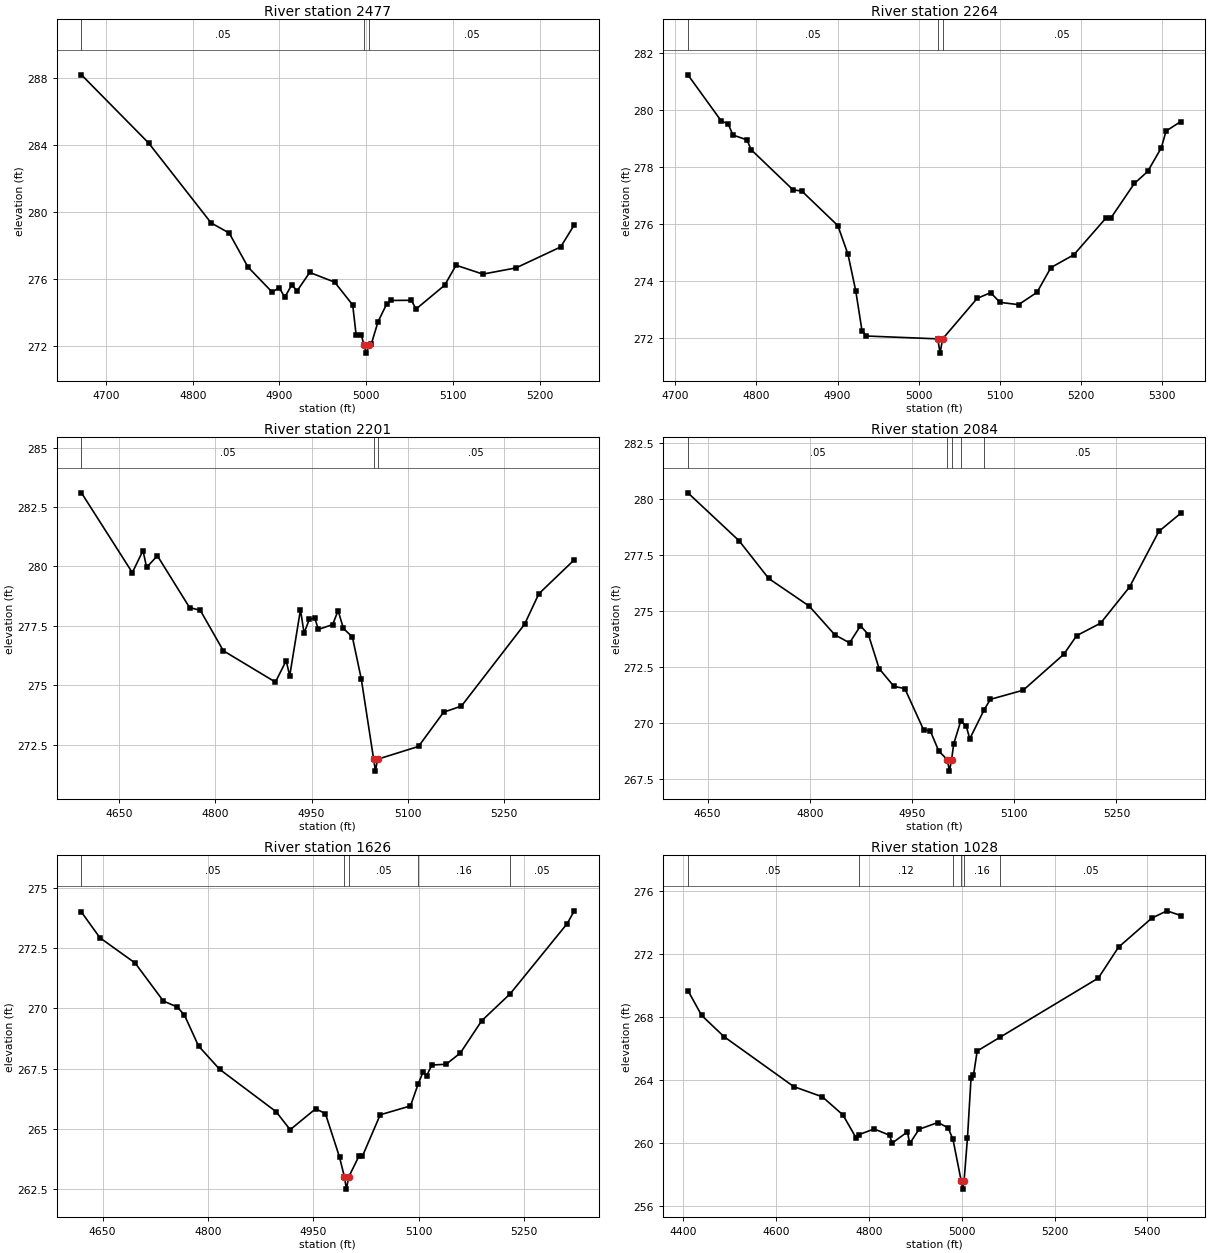
Type RM Length L Ch R = 1,2477,213,213,213
BEGIN DESCRIPTION:
UNT025 IN ROCK 5.0
END DESCRIPTION:
XS GIS Cut Line= 3
      3642342.14     10162691.67      3642592.11     10162891.64
      3642818.13     10162994.64
#Sta/Elev= 30
  4671.6  288.16  4749.2  284.09  4821.2  279.33  4842.0  278.73  4863.6  276.71
  4891.7  275.20  4899.7  275.48  4906.1  274.90  4914.1  275.63  4920.5  275.29
  4934.9  276.38  4963.7  275.80  4984.5  274.44  4988.5  272.63  4994.5  272.63
  4997.5  272.07  5000.2  271.57  5003.5  272.07  5006.0  272.12  5013.7  273.44
  5023.5  274.48  5029.0  274.71  5052.1  274.72  5057.6  274.20  5090.6  275.62
  5103.7  276.81  5134.6  276.28  5172.8  276.65  5224.4  277.90  5240.1  279.22
#Mann=3,-1,0
  4671.6    0.05       0  4997.5    0.03       0  5003.5    0.05       0
Bank Sta=4997.5,5003.5
Exp/Cntr=0.3,0.1

Type RM Length L Ch R = 1,2264,63,63,63
BEGIN DESCRIPTION:
Mapping XS 047c0011
END DESCRIPTION:
XS GIS Cut Line= 2
      3642275.17     10162973.82      3642823.80     10163234.24
#Sta/Elev= 30
  4715.6  281.23  4756.5  279.62  4765.4  279.50  4771.0  279.12  4788.2  278.95
  4793.7  278.60  4845.0  277.20  4856.1  277.15  4900.4  275.94  4912.9  274.93
  4922.5  273.64  4930.1  272.26  4935.6  272.07  5023.5  271.97  5026.3  271.47
  5029.5  271.97  5072.0  273.39  5088.6  273.59  5100.2  273.25  5123.0  273.17
  5145.7  273.60  5162.9  274.47  5191.2  274.92  5231.1  276.22  5236.6  276.20
  5265.7  277.42  5282.1  277.84  5298.9  278.67  5304.8  279.26  5322.9  279.59
#Mann=3,-1,0
  4715.6    0.05       0  5023.5    0.03       0  5029.5    0.05       0
Bank Sta=5023.5,5029.5
Exp/Cntr=0.3,0.1

Type RM Length L Ch R = 1,2201,117,117,117
BEGIN DESCRIPTION:
Mapping XS 009f3bf6
END DESCRIPTION:
XS GIS Cut Line= 2
      3642144.23     10162971.99      3642831.54     10163317.11
#Sta/Elev= 30
  4590.9  283.10  4670.3  279.74  4687.0  280.67  4692.6  279.96  4709.4  280.45
  4759.6  278.27  4776.4  278.15  4812.3  276.45  4893.6  275.13  4910.4  276.03
  4915.9  275.39  4932.7  278.18  4938.3  277.19  4946.6  277.78  4955.0  277.83
  4960.6  277.35  4982.9  277.55  4991.4  278.14  4999.7  277.39  5013.7  277.03
  5027.6  275.26  5046.9  271.88  5049.7  271.38  5052.9  271.88  5116.9  272.42
  5156.0  273.86  5183.9  274.12  5282.3  277.56  5304.7  278.85  5360.0  280.28
#Mann=3,-1,0
  4590.9    0.05       0  5046.9    0.03       0  5052.9    0.05       0
Bank Sta=5046.9,5052.9
Exp/Cntr=0.3,0.1

Type RM Length L Ch R = 1,2084,458,458,458
BEGIN DESCRIPTION:
UNT025 IN ROCK 4.0
END DESCRIPTION:
XS GIS Cut Line= 3
      3642140.94     10163080.20      3642469.56     10163264.19
      3642792.08     10163391.63
#Sta/Elev= 30
  4621.0  280.28  4696.2  278.14  4739.6  276.46  4799.0  275.23  4836.6  273.95
  4858.3  273.59  4874.3  274.35  4885.9  273.96  4901.7  272.44  4923.4  271.65
  4939.4  271.55  4966.8  269.72  4977.0  269.65  4989.1  268.77  5002.0  268.37
  5004.8  267.87  5008.0  268.37  5011.1  269.08  5021.4  270.10  5029.4  269.89
  5034.7  269.31  5055.9  270.61  5064.9  271.07  5113.2  271.48  5172.7  273.08
  5191.6  273.91  5226.8  274.47  5269.2  276.08  5312.2  278.56  5344.4  279.37
#Mann=5,-1,0
  4621.0    0.05       0  5002.0    0.03       0  5008.0    0.05       0
  5021.4    0.16       0  5055.9    0.05       0
Bank Sta=5002,5008
Exp/Cntr=0.3,0.1

Type RM Length L Ch R = 1,1626,598,598,598
BEGIN DESCRIPTION:
UNT025 IN ROCK 3.0
END DESCRIPTION:
XS GIS Cut Line= 3
      3641895.90     10163673.27      3642292.11     10163641.64
      3642592.10     10163591.64
#Sta/Elev= 30
  4620.0  274.01  4646.3  272.94  4696.4  271.89  4736.6  270.31  4756.6  270.06
  4766.7  269.72  4786.7  268.44  4816.8  267.47  4897.1  265.71  4917.1  264.96
  4953.4  265.83  4967.3  265.63  4987.4  263.82  4994.4  262.99  4997.2  262.49
  5000.4  262.99  5015.0  263.86  5020.0  263.86  5045.3  265.58  5088.4  265.95
  5099.2  266.85  5106.2  267.35  5111.2  267.19  5118.8  267.65  5139.1  267.68
  5159.4  268.15  5189.8  269.49  5230.3  270.61  5311.5  273.53  5321.6  274.06
#Mann=5,-1,0
  4620.0    0.05       0  4994.4    0.07       0  5000.4    0.05       0
  5099.2    0.16       0  5230.3    0.05       0
Bank Sta=4994.4,5000.4
Exp/Cntr=0.3,0.1

Type RM Length L Ch R = 1,1028,658,658,658
BEGIN DESCRIPTION:
UNT025 IN ROCK 2.0
END DESCRIPTION:
XS GIS Cut Line= 3
      3641903.69     10163964.66      3642305.94     10164080.69
      3642922.23     10164266.35
#Sta/Elev= 30
  4409.8  269.65  4439.4  268.07  4487.7  266.72  4637.9  263.55  4699.6  262.90
  4744.0  261.75  4772.4  260.29  4777.5  260.49  4811.3  260.86  4844.6  260.46
  4849.8  259.96  4882.8  260.67  4888.0  259.94  4908.0  260.84  4948.8  261.27
  4970.7  260.93  4981.1  260.20  4999.0  257.54  5001.7  257.04  5005.0  257.54
  5012.4  260.31  5020.0  264.07  5025.3  264.26  5033.3  265.81  5082.9  266.69
  5294.4  270.44  5337.9  272.40  5409.3  274.24  5442.2  274.71  5472.1  274.41
#Mann=6,-1,0
  4409.8    0.05       0  4777.5    0.12       0  4981.1    0.16       0
  4999.0    0.07       0  5005.0    0.16       0  5082.9    0.05       0
Bank Sta=4999,5005
Exp/Cntr=0.3,0.1

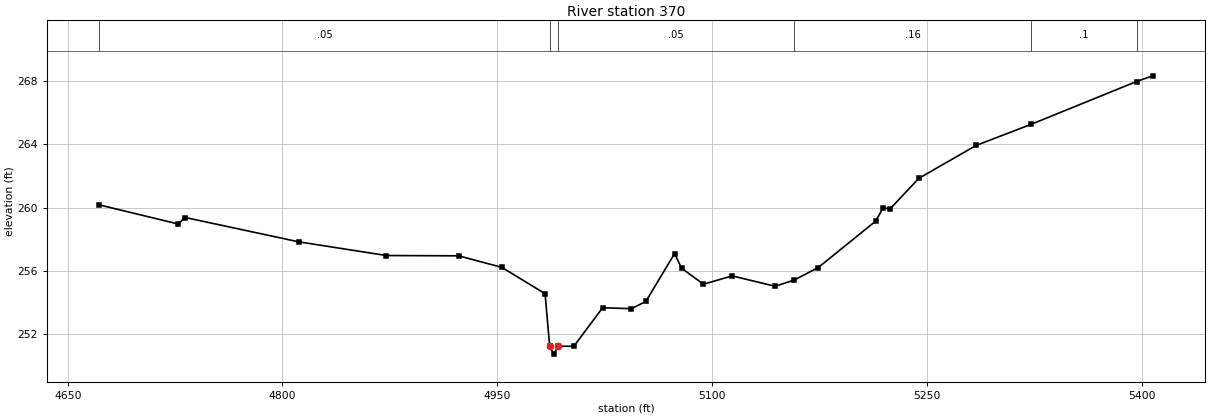
Type RM Length L Ch R = 1,370,0,0,0
BEGIN DESCRIPTION:
UNT025 IN ROCK 1.0
END DESCRIPTION:
XS GIS Cut Line= 3
      3641792.78     10164482.96      3642197.64     10164436.54
      3642525.10     10164413.34
#Sta/Elev= 30
  4672.0  260.17  4727.1  258.96  4732.1  259.37  4811.2  257.83  4872.6  256.96
  4923.0  256.94  4953.2  256.21  4983.4  254.54  4986.6  251.21  4989.4  250.71
  4992.6  251.21  5003.5  251.21  5023.6  253.65  5043.7  253.59  5053.8  254.05
  5073.8  257.08  5078.8  256.15  5094.0  255.14  5114.1  255.67  5144.1  255.01
  5157.5  255.41  5174.2  256.20  5214.3  259.14  5219.4  259.97  5224.5  259.93
  5244.4  261.85  5284.5  263.94  5323.0  265.28  5396.5  267.99  5407.8  268.35
#Mann=6,-1,0
  4672.0    0.05       0  4986.6    0.07       0  4992.6    0.05       0
  5157.5    0.16       0  5323.0     0.1       0  5396.5    0.05       0
Bank Sta=4986.6,4992.6
Exp/Cntr=0.3,0.1

Chan Stop Cuts=-1