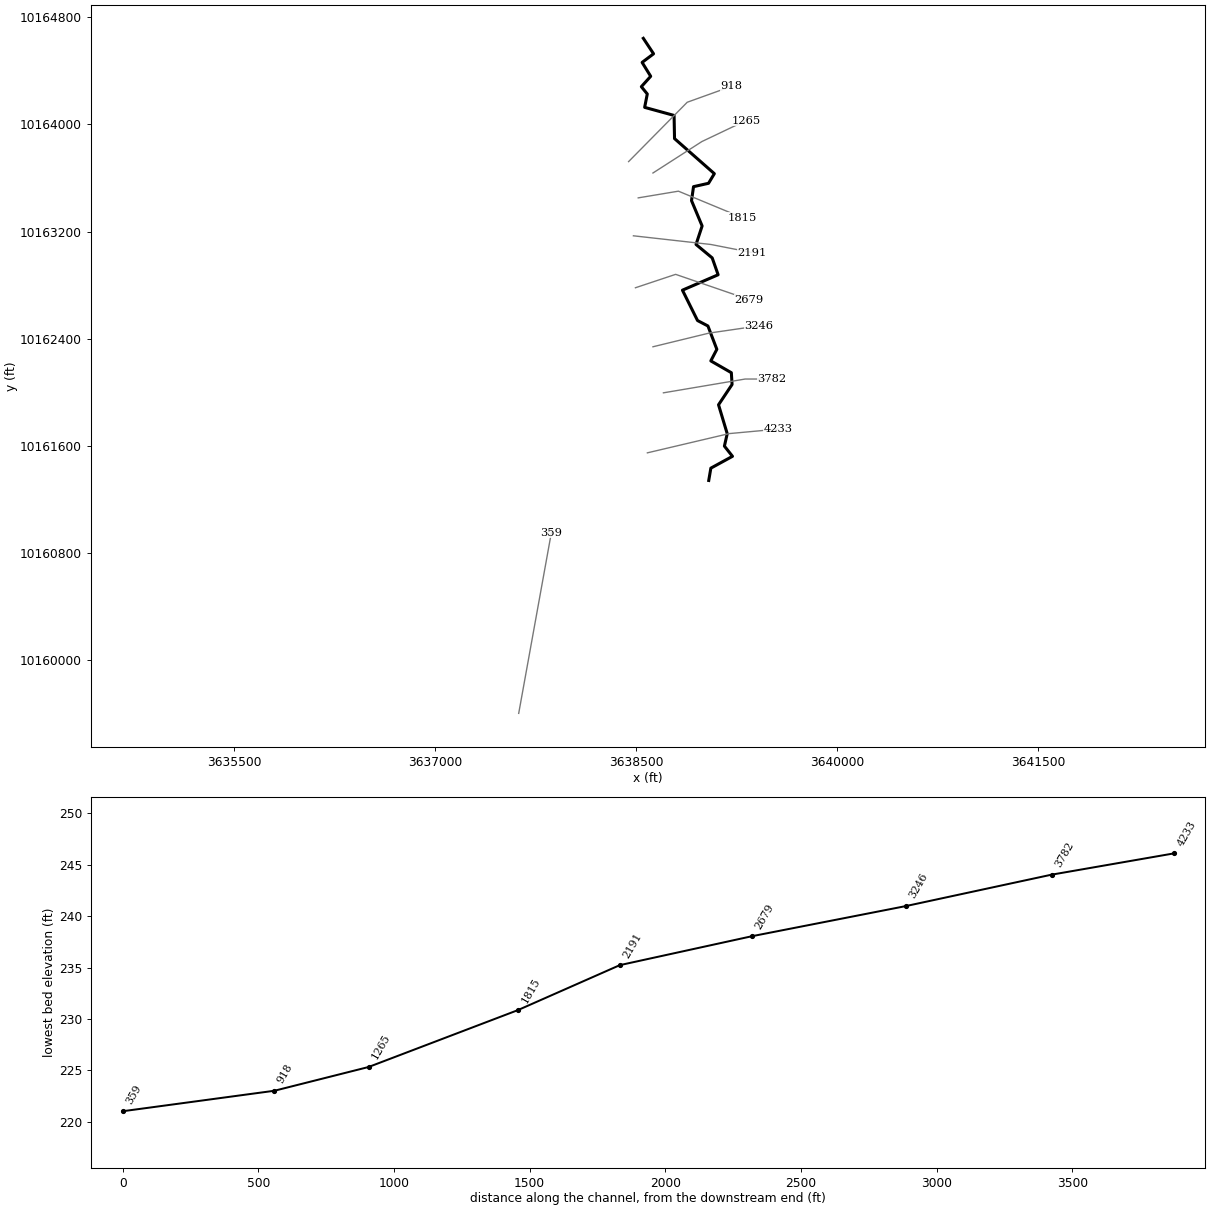
--- UNT026 IN ROCK.prj (project) ---

Proj Title=UNT026 IN ROCK Base Level Engineering
Current Plan=p01
Default Exp/Contr=0.3,0.1
English Units
Geom File=g01
Flow File=f01
Plan File=p01
Y Axis Title=Elevation
X Axis Title(PF)=Main Channel Distance
X Axis Title(XS)=Station
BEGIN DESCRIPTION:
UNT026 IN ROCK
END DESCRIPTION:
DSS Export Rating Curves= 0
DSS Export Rating Curve Sorted= 0
DSS Export Volume Flow Curves= 0
DXF OffsetX= 0
DXF OffsetY= 0
DXF ScaleX= 1
DXF ScaleY= 10

--- UNT026 IN ROCK.p01 (plan) ---

Plan Title=Multiple Run
Short Identifier=Multiple
Geom File=g01
Flow File=f01
Subcritical Flow
K Sum by GR= 0
Std Step Tol= 0.01
Critical Tol= 0.01
Num of Std Step Trials= 20
Max Error Tol= 0.3
Flow Tol Ratio= 0.001
Split Flow NTrial= 30
Split Flow Tol= 0.02
Split Flow Ratio= 0.02
Log Output Level= 0
Friction Slope Method= 1
Unsteady Friction Slope Method= 2
Unsteady Bridges Friction Slope Method= 1
Parabolic Critical Depth
Global Vel Dist=  1 , 1 , 1
Global Log Level= 0
CheckData=True
Encroach Param= -1, 0, 0, 0
BEGIN DESCRIPTION:
Multiple Run
END DESCRIPTION:

--- UNT026 IN ROCK.f01 (steady flow) ---

Flow Title=Multiple
Number of Profiles=7
Profile Names=10-year,25-year,50-year,1pct_min,100-year,1pct_plu,500-year
River Rch & RM= UNT026 IN ROCK,Reach-1,4233
     315     408     480     416     563     762     773
River Rch & RM= UNT026 IN ROCK,Reach-1,1265
     448     592     707     621     840    1136    1184
Boundary for River Rch & Prof#=UNT026 IN ROCK,Reach-1,1
Up Type=0
Dn Type=3
Dn Slope=0.005
Boundary for River Rch & Prof#=UNT026 IN ROCK,Reach-1,2
Up Type=0
Dn Type=3
Dn Slope=0.005
Boundary for River Rch & Prof#=UNT026 IN ROCK,Reach-1,3
Up Type=0
Dn Type=3
Dn Slope=0.005
Boundary for River Rch & Prof#=UNT026 IN ROCK,Reach-1,4
Up Type=0
Dn Type=3
Dn Slope=0.005
Boundary for River Rch & Prof#=UNT026 IN ROCK,Reach-1,5
Up Type=0
Dn Type=3
Dn Slope=0.005
Boundary for River Rch & Prof#=UNT026 IN ROCK,Reach-1,6
Up Type=0
Dn Type=3
Dn Slope=0.005
Boundary for River Rch & Prof#=UNT026 IN ROCK,Reach-1,7
Up Type=0
Dn Type=3
Dn Slope=0.005

--- UNT026 IN ROCK.g01 (geometry) ---

Geom Title=Existing Conditions
Program Version=4.10

River Reach=UNT026 IN ROCK  ,Reach-1
Reach XY= 30
      3639040.28     10161341.92      3639056.04     10161433.87
      3639217.45     10161522.14      3639157.23     10161598.39
      3639178.23     10161690.95      3639113.37     10161906.74
      3639214.38      10162058.2      3639208.99     10162146.17
      3639055.71     10162234.29      3639100.77     10162320.76
       3639034.2     10162494.92      3638956.54     10162535.56
      3638844.03     10162762.13      3639110.37     10162877.16
      3639066.02     10163003.07      3638945.41     10163103.26
      3638990.93     10163241.27      3638911.76     10163430.32
       3638926.7     10163534.59      3639038.69      10163559.8
      3639082.11     10163631.64      3638784.93     10163893.37
      3638781.62     10164066.17       3638561.9      10164126.5
      3638581.59     10164226.35      3638537.22     10164280.72
      3638607.05     10164358.27      3638543.01       10164462.
      3638628.56     10164526.19      3638552.11     10164641.64

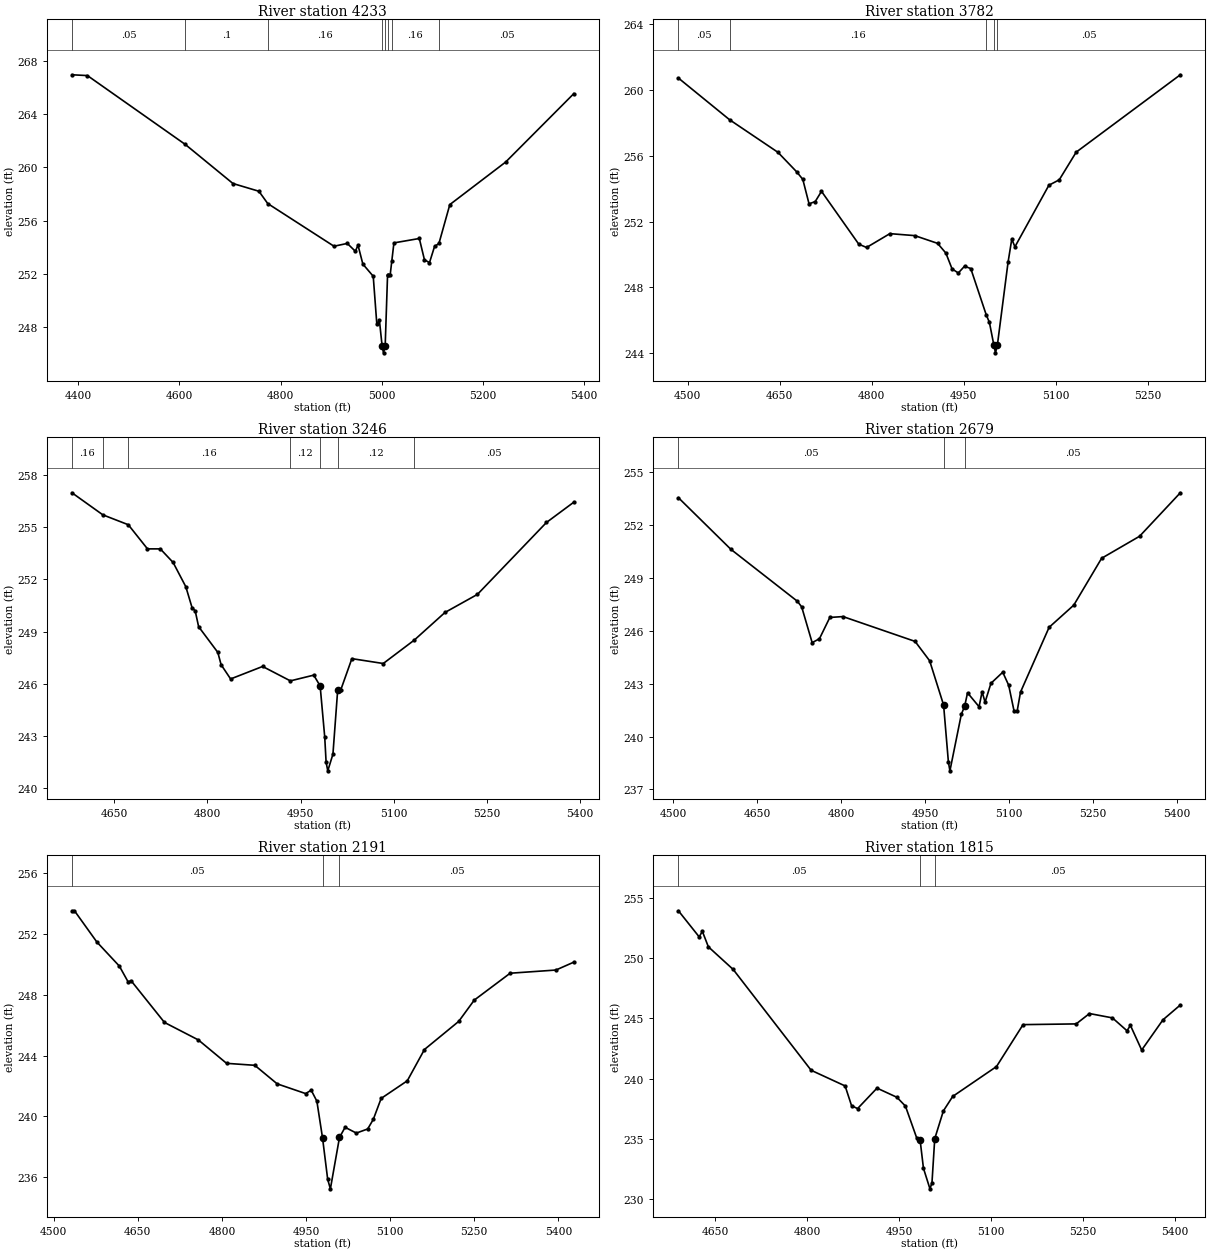
Type RM Length L Ch R = 1 ,4233    ,451,451,451
BEGIN DESCRIPTION:
UNT026 IN ROCK 9.0
END DESCRIPTION:
XS GIS Cut Line= 3
      3638582.32     10161548.09      3639192.11     10161691.64
      3639556.31     10161725.18
#Sta/Elev= 30
  4387.6  266.94  4418.2  266.88  4611.6  261.72  4705.9  258.79  4757.2  258.21
  4774.6  257.29  4905.6  254.09  4931.9   254.3  4947.9  253.71  4953.1  254.17
  4962.7  252.75  4983.2  251.84  4990.3  248.25  4995.4  248.54  5000.8   246.6
  5003.5   246.1  5006.8   246.6  5011.5  251.91  5013.3  251.91  5016.6  251.91
  5019.9  252.98  5024.1  254.34  5074.3  254.67  5084.4  253.08  5094.4  252.86
  5104.4  254.07  5113.1   254.3  5134.6  257.21    5245   260.4  5379.8  265.53
#Mann= 8 ,-1 , 0
  4387.6     .05       0  4611.6      .1       0  4774.6     .16       0
  5000.8     .07       0  5006.8     .16       0  5013.3      .1       0
  5019.9     .16       0  5113.1     .05       0
Bank Sta=5000.8,5006.8
XS Rating Curve= 0 ,0
Exp/Cntr=0.3,0.1

Type RM Length L Ch R = 1 ,3782    ,536,536,536
BEGIN DESCRIPTION:
UNT026 IN ROCK 8.0
END DESCRIPTION:
XS GIS Cut Line= 3
      3638702.09     10161996.01       3639311.9     10162098.93
      3639511.86     10162098.93
#Sta/Elev= 30
    4485  260.72  4568.4  258.19  4647.3  256.21  4677.7  255.03  4687.8  254.57
    4698  253.08  4708.1  253.22  4718.3  253.84  4779.1  250.63  4791.8  250.43
  4829.8  251.27  4870.4  251.15  4907.6  250.68  4921.1  250.09  4931.2  249.13
  4941.4  248.88  4951.5  249.29  4961.7  249.15    4987  246.33  4992.1  245.88
  4999.2  244.53    5002  244.03  5005.2  244.53  5022.5  249.53  5028.6  250.94
  5033.7  250.47  5089.1  254.21    5106  254.54  5133.6  256.22  5303.4  260.92
#Mann= 5 ,-1 , 0
    4485     .05       0  4568.4     .16       0    4987     .05       0
  4999.2     .03       0  5005.2     .05       0
Bank Sta=4999.2,5005.2
XS Rating Curve= 0 ,0
Exp/Cntr=0.3,0.1

Type RM Length L Ch R = 1 ,3246    ,567,567,567
BEGIN DESCRIPTION:
UNT026 IN ROCK 7.0
END DESCRIPTION:
XS GIS Cut Line= 3
      3638623.97     10162339.76      3639042.11     10162441.64
       3639415.7     10162496.02
#Sta/Elev= 30
  4582.1  256.99  4631.8  255.72  4672.8  255.15  4703.7  253.76  4724.3  253.76
  4744.9  252.98  4765.4  251.58  4775.4  250.38  4780.5  250.19    4786  249.28
  4816.9   247.8  4822.2  247.09  4837.5  246.27    4889  246.99  4933.7  246.16
  4971.3  246.49  4981.6  245.87    4989  242.92  4991.2  241.48  4993.9  240.98
  5002.2  241.94  5009.9  245.66    5015  245.66  5032.7  247.44  5083.2  247.16
  5133.2  248.51  5182.6   250.1  5234.8  251.14  5345.9  255.28    5390  256.45
#Mann= 7 ,-1 , 0
  4582.1     .16       0  4631.8      .1       0  4672.8     .16       0
  4933.7     .12       0  4981.6     .07       0  5009.9     .12       0
  5133.2     .05       0
Bank Sta=4981.6,5009.9
XS Rating Curve= 0 ,0
Exp/Cntr=0.3,0.1

Type RM Length L Ch R = 1 ,2679    ,488,488,488
BEGIN DESCRIPTION:
UNT026 IN ROCK 6.0
END DESCRIPTION:
XS GIS Cut Line= 3
      3638493.18     10162780.19      3638793.15     10162880.18
      3639342.08     10162691.65
#Sta/Elev= 30
  4509.5  253.56  4603.2  250.63    4722  247.68  4729.7  247.36  4748.4  245.33
  4761.4  245.55    4780  246.76  4803.5  246.81  4932.3   245.4  4958.3   244.3
  4983.2  241.79  4991.8  238.55  4994.5  238.05  5014.9  241.26  5020.8  241.72
    5026  242.48  5046.6  241.69    5052  242.54  5057.3  241.95  5067.8  243.02
  5088.9  243.65  5099.5  242.91  5109.2  241.43  5114.5  241.42  5120.6  242.52
  5171.7   246.2  5215.8  247.46  5265.5  250.12  5333.3  251.37  5406.1  253.84
#Mann= 3 , 0 , 0
  4509.5     .05       0  4983.2    .035       0  5020.8     .05       0
Bank Sta=4983.2,5020.8
XS Rating Curve= 0 ,0
Exp/Cntr=0.3,0.1

Type RM Length L Ch R = 1 ,2191    ,376,376,376
BEGIN DESCRIPTION:
UNT026 IN ROCK 5.0
END DESCRIPTION:
XS GIS Cut Line= 3
      3638478.12     10163167.89      3639056.57     10163103.08
      3639363.55     10163042.89
#Sta/Elev= 30
  4532.6  253.53  4537.1  253.53  4576.9  251.48  4617.1  249.89  4632.9  248.84
    4638  248.93  4697.6  246.18    4758  245.03  4808.3  243.49  4858.6  243.36
  4898.5  242.14  4949.2   241.5  4959.2  241.72  4969.3     241  4979.4  238.58
  4988.6  235.85  4993.4  235.23  5009.6  238.61  5019.6  239.28  5039.7   238.9
  5059.9  239.17  5069.9   239.8  5083.9  241.18  5130.5  242.34  5161.1   244.4
  5222.2  246.25  5249.9  247.65  5313.9  249.42  5395.5  249.63  5427.5  250.15
#Mann= 3 , 0 , 0
  4532.6     .05       0  4979.4    .035       0  5009.6     .05       0
Bank Sta=4979.4,5009.6
XS Rating Curve= 0 ,0
Exp/Cntr=0.3,0.1

Type RM Length L Ch R = 1 ,1815    ,550,550,550
BEGIN DESCRIPTION:
UNT026 IN ROCK 4.0
END DESCRIPTION:
XS GIS Cut Line= 3
      3638513.99     10163451.02      3638813.98     10163501.02
      3639288.92     10163304.02
#Sta/Elev= 30
  4590.3  253.93  4624.2  251.76  4629.3  252.23  4639.1  250.94  4679.6  249.06
  4806.7  240.69  4862.1  239.39  4872.6  237.75  4882.4  237.51  4914.1  239.21
  4946.5  238.45  4960.4  237.72  4978.9  235.06  4984.3  234.92  4989.8  232.56
  5000.4  230.85  5003.7  231.35  5008.2  235.01  5022.3  237.32  5037.5  238.52
  5108.9     241  5152.2  244.48  5238.8  244.54  5260.5   245.4  5297.9  245.04
  5321.7  243.97  5327.2  244.42  5345.6  242.37  5380.3  244.88  5408.6  246.11
#Mann= 3 , 0 , 0
  4590.3     .05       0  4984.3    .035       0  5008.2     .05       0
Bank Sta=4984.3,5008.2
XS Rating Curve= 0 ,0
Exp/Cntr=0.3,0.1

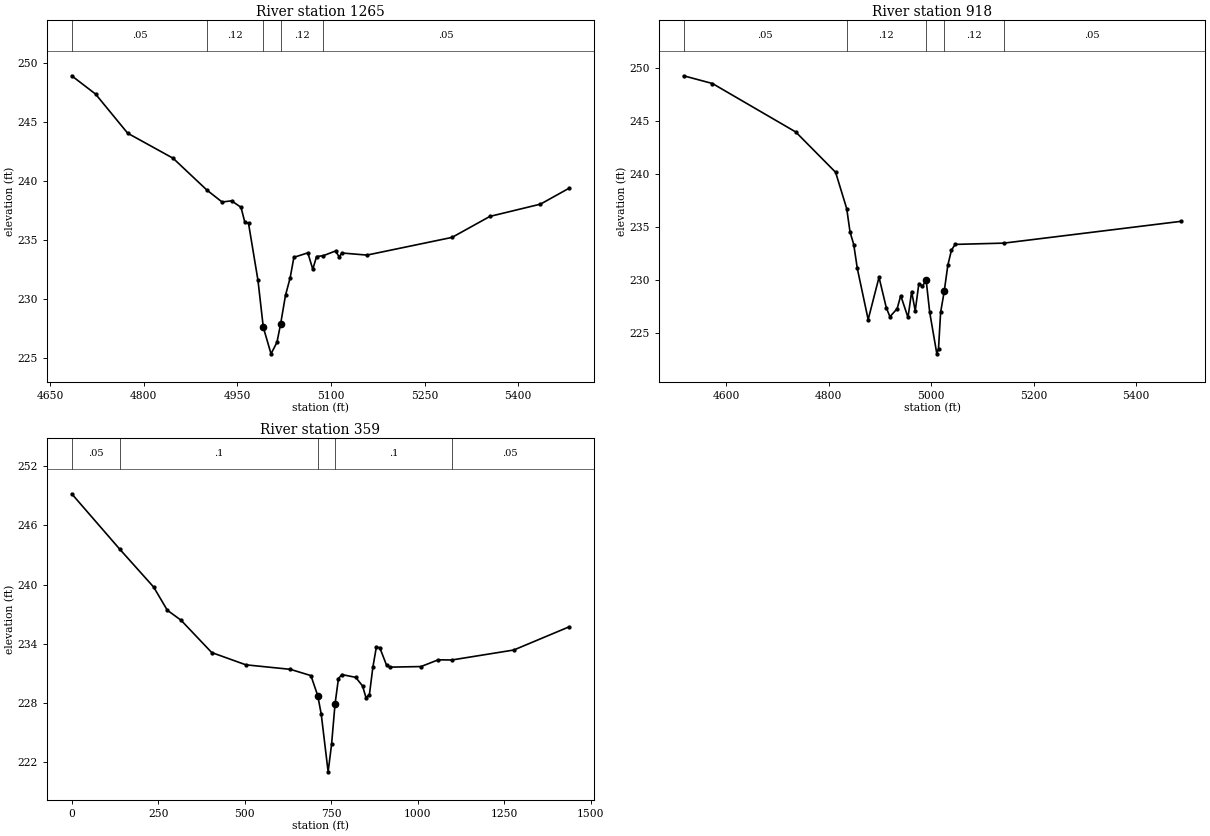
Type RM Length L Ch R = 1 ,1265    ,347,347,347
BEGIN DESCRIPTION:
UNT026 IN ROCK 3.0
END DESCRIPTION:
XS GIS Cut Line= 3
      3638623.98     10163636.63      3638988.57     10163871.01
      3639316.02     10164026.94
#Sta/Elev= 30
  4684.8  248.89    4723  247.34  4774.5  244.02  4847.2   241.9  4901.6  239.19
  4925.7  238.19  4940.9  238.29    4956  237.74  4962.1  236.48    4968  236.39
  4983.2  231.54  4991.7  227.57  5004.1  225.32  5013.6   226.3  5019.5  227.87
  5027.3  230.29  5034.7  231.76  5040.7   233.5    5063  233.88    5071  232.49
    5077  233.57  5087.9  233.64  5107.4  234.04  5113.3  233.53  5117.4  233.87
  5157.7  233.69    5294  235.19  5354.7  236.97  5435.7  238.01  5480.9  239.34
#Mann= 5 ,-1 , 0
  4684.8     .05       0  4901.6     .12       0  4991.7     .07       0
  5019.5     .12       0  5087.9     .05       0
Bank Sta=4991.7,5019.5
XS Rating Curve= 0 ,0
Exp/Cntr=0.3,0.1

Type RM Length L Ch R = 1 ,918     ,559,559,559
BEGIN DESCRIPTION:
UNT026 IN ROCK 2.0
END DESCRIPTION:
XS GIS Cut Line= 3
      3638442.21     10163721.68       3638879.7     10164164.61
      3639207.18     10164282.42
#Sta/Elev= 30
  4516.5  249.23  4572.9   248.5  4735.6  243.93  4813.4  240.13  4835.1   236.7
  4841.6   234.5  4848.8  233.32  4855.8  231.06    4877  226.24  4898.2  230.23
  4912.4  227.36  4919.5  226.51  4933.6  227.27  4940.6   228.5  4954.8  226.44
  4961.9  228.88  4968.9  227.06    4976  229.64  4983.1  229.38  4990.2  229.98
  4997.2  226.92  5011.1  223.01  5014.4  223.51  5018.5  226.92  5025.5  228.89
  5032.6  231.37  5039.6  232.78  5046.8  233.33  5142.1  233.45  5487.1   235.5
#Mann= 5 ,-1 , 0
  4516.5     .05       0  4835.1     .12       0  4990.2     .07       0
  5025.5     .12       0  5142.1     .05       0
Bank Sta=4990.2,5025.5
XS Rating Curve= 0 ,0
Exp/Cntr=0.3,0.1

Type RM Length L Ch R = 1 ,359     ,0,0,0
BEGIN DESCRIPTION:
UNT026 IN ROCK 1.0
END DESCRIPTION:
XS GIS Cut Line= 2
3637621.9573358810159603.68130263637866.0025625610160953.5914389
#Sta/Elev= 30
       0249.2135138.2015243.6221236.9168239.7543 276.403 237.403315.8891236.3984
404.7329233.1139503.4483231.8693631.8535231.4127691.5342230.7776711.4279228.7148
721.3746226.8555741.2682221.0178 751.215223.8065761.1618227.8756771.1086230.4823
781.0554230.8797820.8426230.6003840.7362229.7319 850.683228.5415860.6298228.8543
870.5766231.6252880.5234233.6395890.4702233.6157910.3638231.8091920.3106 231.636
1009.696231.69321059.345232.37471099.064232.36161277.801233.37051436.678235.7035
#Mann= 5 ,-1 , 0
       0     .05       0138.2015      .1       0711.4279     .07       0
761.1618      .1       01099.064     .05       0
Bank Sta=711.4279,761.1618
XS Rating Curve= 0 ,0
Exp/Cntr=0.3,0.1

Chan Stop Cuts=-1
Use User Specified Reach Order=0
Composite Channel Slope=5