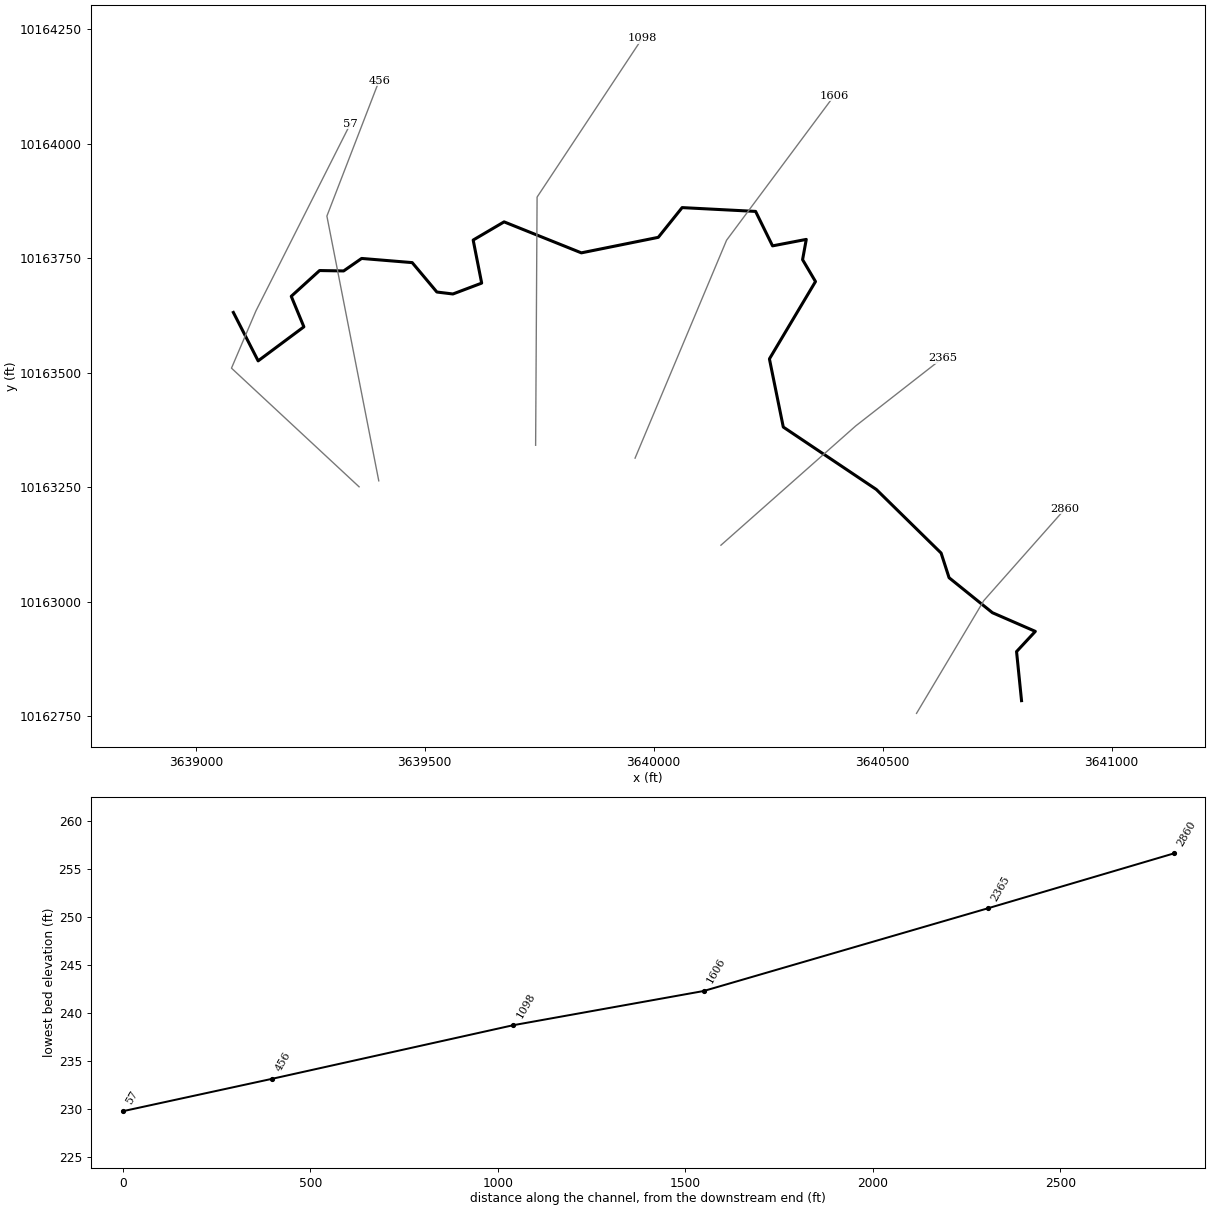
--- UNT027 IN ROCK.prj (project) ---

Proj Title=UNT027 IN ROCK Base Level Engineering
Current Plan=p01
Default Exp/Contr=0.3,0.1
English Units
Geom File=g01
Flow File=f01
Plan File=p01
Y Axis Title=Elevation
X Axis Title(PF)=Main Channel Distance
X Axis Title(XS)=Station
BEGIN DESCRIPTION:
UNT027 IN ROCK
END DESCRIPTION:
DSS Export Rating Curves= 0
DSS Export Rating Curve Sorted= 0
DSS Export Volume Flow Curves= 0
DXF OffsetX= 0
DXF OffsetY= 0
DXF ScaleX= 1
DXF ScaleY= 10

--- UNT027 IN ROCK.p01 (plan) ---

Plan Title=Multiple Run
Short Identifier=Multiple
Geom File=g01
Flow File=f01
Subcritical Flow
K Sum by GR= 0
Std Step Tol= 0.01
Critical Tol= 0.01
Num of Std Step Trials= 20
Max Error Tol= 0.3
Flow Tol Ratio= 0.001
Split Flow NTrial= 30
Split Flow Tol= 0.02
Split Flow Ratio= 0.02
Log Output Level= 0
Friction Slope Method= 1
Unsteady Friction Slope Method= 2
Unsteady Bridges Friction Slope Method= 1
Parabolic Critical Depth
Global Vel Dist=  1 , 1 , 1
Global Log Level= 0
CheckData=True
Encroach Param= -1, 0, 0, 0
BEGIN DESCRIPTION:
Multiple Run
END DESCRIPTION:

--- UNT027 IN ROCK.f01 (steady flow) ---

Flow Title=Multiple
Program Version=4.10
Number of Profiles= 7
Profile Names=10-year,25-year,50-year,1pct_min,100-year,1pct_plu,500-year
River Rch & RM=UNT027 IN ROCK,Reach-1         ,2860
     184     228     261     221     299     404     389
Boundary for River Rch & Prof#=UNT027 IN ROCK,Reach-1         , 1
Up Type= 0
Dn Type= 3
Dn Slope=0.015
Boundary for River Rch & Prof#=UNT027 IN ROCK,Reach-1         , 2
Up Type= 0
Dn Type= 3
Dn Slope=0.015
Boundary for River Rch & Prof#=UNT027 IN ROCK,Reach-1         , 3
Up Type= 0
Dn Type= 3
Dn Slope=0.015
Boundary for River Rch & Prof#=UNT027 IN ROCK,Reach-1         , 4
Up Type= 0
Dn Type= 3
Dn Slope=0.015
Boundary for River Rch & Prof#=UNT027 IN ROCK,Reach-1         , 5
Up Type= 0
Dn Type= 3
Dn Slope=0.015
Boundary for River Rch & Prof#=UNT027 IN ROCK,Reach-1         , 6
Up Type= 0
Dn Type= 3
Dn Slope=0.015
Boundary for River Rch & Prof#=UNT027 IN ROCK,Reach-1         , 7
Up Type= 0
Dn Type= 3
Dn Slope=0.015
DSS Import GetInterval= 0
DSS Import GetPeak= 0
DSS Import FillOption= 0

--- UNT027 IN ROCK.g01 (geometry) ---

Geom Title=Existing Conditions
Program Version=4.10

River Reach=UNT027 IN ROCK  ,Reach-1
Reach XY= 30
      3640803.13     10162783.96      3640792.26      10162891.1
      3640833.26     10162935.21      3640739.51     10162976.01
      3640644.89      10163052.4      3640627.53     10163106.22
      3640486.04     10163245.11       3640282.9     10163381.35
      3640252.62     10163530.19      3640353.22      10163699.1
      3640325.02     10163746.86      3640333.09     10163791.13
      3640259.43     10163777.01      3640222.42     10163852.25
      3640062.01     10163860.55      3640009.96     10163795.63
      3639841.95     10163761.74      3639673.27     10163829.41
      3639605.74     10163789.68      3639624.31     10163695.67
      3639561.53     10163671.94      3639526.47      10163676.2
       3639472.6     10163740.45      3639362.16     10163749.54
      3639322.89     10163722.25      3639270.37     10163723.12
       3639208.5     10163666.87      3639236.08     10163600.23
      3639136.21     10163525.89      3639082.11     10163631.64

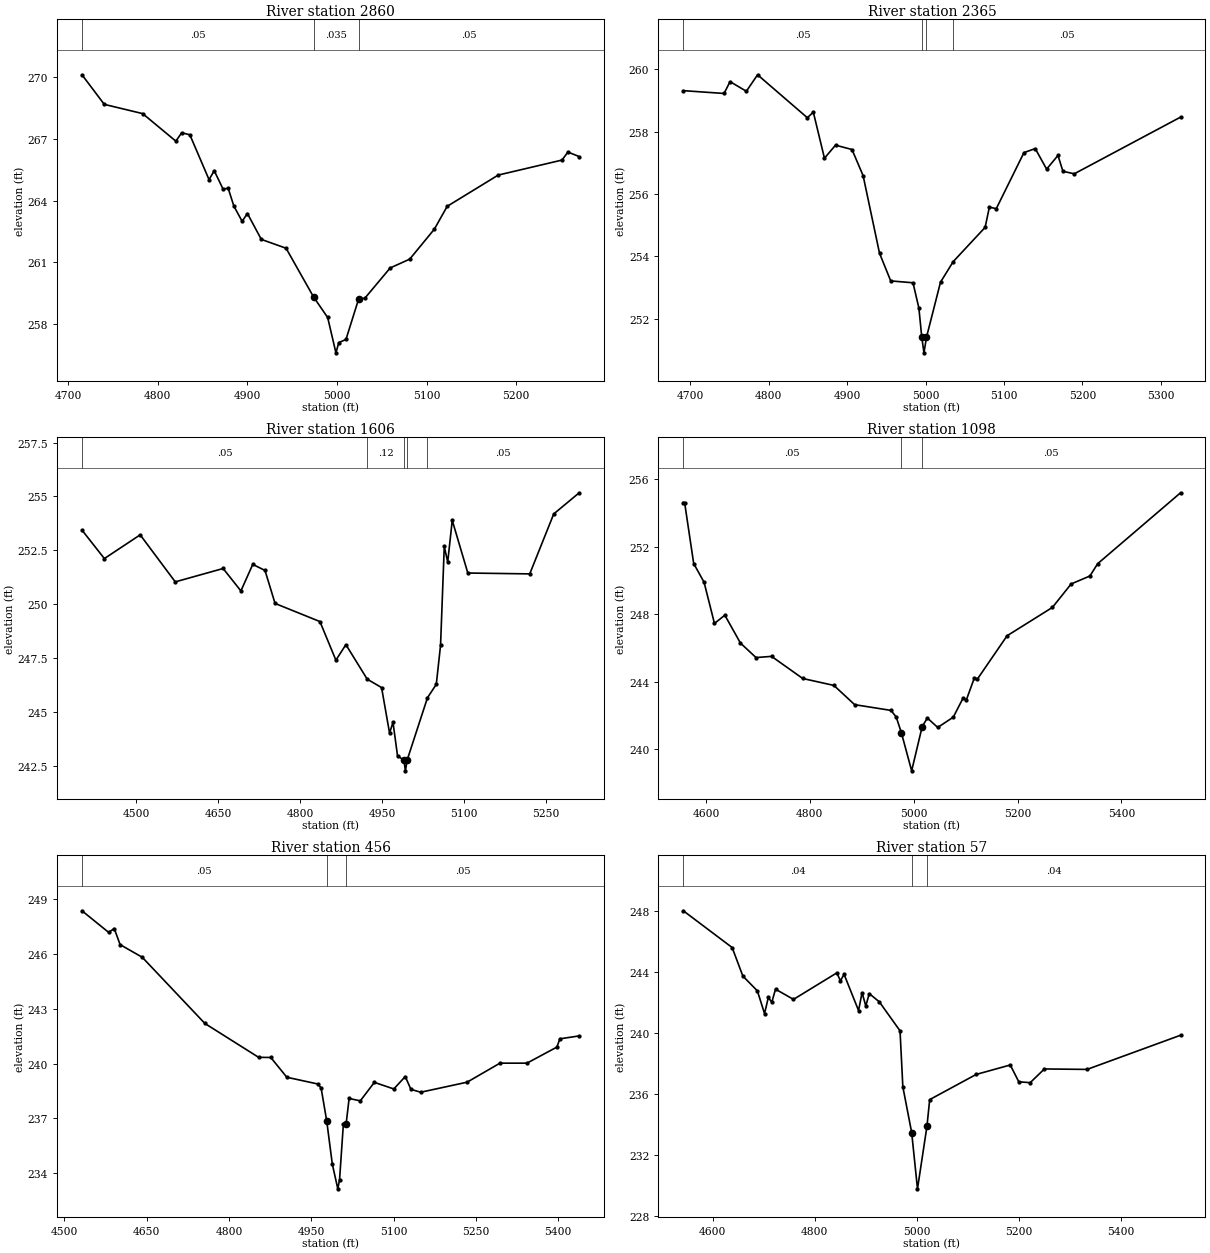
Type RM Length L Ch R = 1 ,2860    ,495,495,495
BEGIN DESCRIPTION:
UNT027 IN ROCK 5.0
END DESCRIPTION:
XS GIS Cut Line= 3
      3640573.82     10162756.17       3640720.8      10163002.5
      3640898.25     10163202.87
#Sta/Elev= 30
  4715.7  270.13  4740.6  268.69  4783.4  268.24  4820.4   266.9  4826.9  267.31
    4836  267.21  4857.4  265.03  4863.2  265.46  4872.9  264.58  4878.8   264.6
  4885.1  263.74  4894.3     263  4900.2  263.38  4915.7  262.12  4943.3  261.69
  4974.1  259.31  4989.7  258.32  4998.9   256.6  5002.1   257.1  5010.1  257.25
  5024.3  259.23    5031  259.25  5059.4  260.73  5081.2  261.16  5108.7  262.62
    5123  263.73  5179.9  265.25    5251  265.98  5257.6  266.37  5270.2  266.15
#Mann= 3 , 0 , 0
  4715.7     .05       0  4974.1    .035       0  5024.3     .05       0
Bank Sta=4974.1,5024.3
XS Rating Curve= 0 ,0
Exp/Cntr=0.3,0.1

Type RM Length L Ch R = 1 ,2365    ,759,759,759
BEGIN DESCRIPTION:
UNT027 IN ROCK 4.0
END DESCRIPTION:
XS GIS Cut Line= 3
      3640146.77      10163123.4      3640441.02      10163383.8
      3640631.12     10163532.23
#Sta/Elev= 30
  4691.1  259.32  4743.1  259.23  4750.7  259.61  4771.5   259.3  4785.8  259.83
  4849.3  258.45  4856.9  258.63  4871.1  257.15  4885.2  257.57  4906.2  257.43
  4920.4  256.59  4941.3   254.1  4955.6  253.21    4984  253.15  4991.5  252.34
  4995.2   251.4    4998   250.9  5001.2   251.4  5019.1  253.17  5035.3  253.83
    5076  254.93  5081.4  255.58  5090.2  255.53  5125.5  257.33  5139.9  257.46
  5154.4   256.8  5168.9  257.24  5175.2  256.73  5189.7  256.65  5325.2  258.47
#Mann= 4 ,-1 , 0
  4691.1     .05       0  4995.2     .07       0  5001.2     .05       0
  5035.3     .05       0
Bank Sta=4995.2,5001.2
XS Rating Curve= 0 ,0
Exp/Cntr=0.3,0.1

Type RM Length L Ch R = 1 ,1606    ,508,508,508
BEGIN DESCRIPTION:
UNT027 IN ROCK 3.0
END DESCRIPTION:
XS GIS Cut Line= 3
      3639959.25     10163313.49      3640159.06     10163789.31
      3640394.14     10164105.15
#Sta/Elev= 30
  4401.1  253.44  4442.1  252.12  4507.6  253.22  4571.8  251.04  4659.4  251.66
  4691.9  250.62  4713.6  251.85    4736  251.57  4754.4  250.04  4836.5   249.2
  4865.7  247.41    4884  248.13    4923  246.53  4949.3  246.14  4963.9  244.03
  4970.2  244.53  4978.5  242.97  4990.1  242.78  4992.9  242.28  4996.1  242.78
  5033.3  245.67  5049.4  246.29  5057.2   248.1    5064  252.68  5070.3  251.96
  5078.6  253.89  5107.1  251.45  5220.4  251.41  5264.3  254.19  5310.9  255.17
#Mann= 5 ,-1 , 0
  4401.1     .05       0    4923     .12       0  4990.1     .07       0
  4996.1     .12       0  5033.3     .05       0
Bank Sta=4990.1,4996.1
XS Rating Curve= 0 ,0
Exp/Cntr=0.3,0.1

Type RM Length L Ch R = 1 ,1098    ,642,642,642
BEGIN DESCRIPTION:
UNT027 IN ROCK 2.0
END DESCRIPTION:
XS GIS Cut Line= 3
      3639742.11     10163341.61       3639745.3     10163883.48
       3639974.9     10164230.16
#Sta/Elev= 30
  4556.3  254.61  4558.8  254.61  4576.3     251  4596.3  249.89  4616.3  247.45
  4636.3  247.94  4666.3  246.29  4696.3  245.43  4726.3   245.5  4786.3  244.19
  4846.3  243.78  4886.3  242.64  4956.3   242.3  4966.3  241.91  4976.3  240.98
  4996.1  238.72  5016.3  241.33  5026.3  241.85  5046.3  241.29  5076.3   241.9
  5094.8  243.01  5101.7  242.94  5116.8  244.22  5122.8  244.16  5179.9  246.72
  5267.2   248.4  5303.3  249.79  5339.4  250.26  5354.4  250.99    5514  255.19
#Mann= 3 , 0 , 0
  4556.3     .05       0  4976.3    .035       0  5016.3     .05       0
Bank Sta=4976.3,5016.3
XS Rating Curve= 0 ,0
Exp/Cntr=0.3,0.1

Type RM Length L Ch R = 1 ,456     ,399,399,399
BEGIN DESCRIPTION:
Mapping XS 2380599b
END DESCRIPTION:
XS GIS Cut Line= 3
       3639399.6     10163263.94      3639286.33     10163842.03
      3639400.48     10164137.78
#Sta/Elev= 30
  4532.2  248.35  4580.8  247.17    4591  247.38  4601.7   246.5    4642  245.81
  4756.2  242.19    4854  240.34  4876.3  240.33  4905.5  239.25  4962.1  238.88
    4968  238.66  4978.2  236.86  4988.4   234.5  4998.4  233.15  5001.6  233.65
  5008.5  236.67  5013.6  236.71    5019  238.09  5039.4  237.96    5065  238.97
  5100.5  238.61  5121.3  239.29  5131.6  238.59  5149.4  238.43    5234  238.98
  5293.9  240.02  5343.1  240.02  5397.7   240.9    5403  241.35  5438.3  241.51
#Mann= 3 , 0 , 0
  4532.2     .05       0  4978.2    .035       0  5013.6     .05       0
Bank Sta=4978.2,5013.6
XS Rating Curve= 0 ,0
Exp/Cntr=0.3,0.1

Type RM Length L Ch R = 1 ,57      ,0,0,0
BEGIN DESCRIPTION:
UNT027 IN ROCK 1.0
END DESCRIPTION:
XS GIS Cut Line= 4
      3639356.61     10163250.91        3639078.       10163510.
      3639131.38       10163635.      3639337.77     10164043.88
#Sta/Elev= 30
  4542.7     248  4638.4  245.59  4659.4  243.72  4687.8  242.75  4701.9  241.26
  4709.3  242.32  4716.1     242  4723.4  242.86  4758.6  242.19  4843.6  243.93
  4850.5  243.41  4857.8  243.83  4886.1  241.46    4893  242.63  4900.3  241.76
  4907.1  242.57  4926.8  242.03  4967.4  240.13  4972.9  236.46  4990.2  233.46
  5001.6  229.77  5020.1  233.86  5025.5  235.62  5116.6  237.27  5183.4  237.89
  5200.1  236.79  5222.4  236.73  5250.3  237.63  5333.9   237.6  5517.1  239.84
#Mann= 3 , 0 , 0
  4542.7     .04       0  4990.2    .035       0  5020.1     .04       0
Bank Sta=4990.2,5020.1
XS Rating Curve= 0 ,0
Exp/Cntr=0.3,0.1

Chan Stop Cuts=-1
Use User Specified Reach Order=0
Composite Channel Slope=5