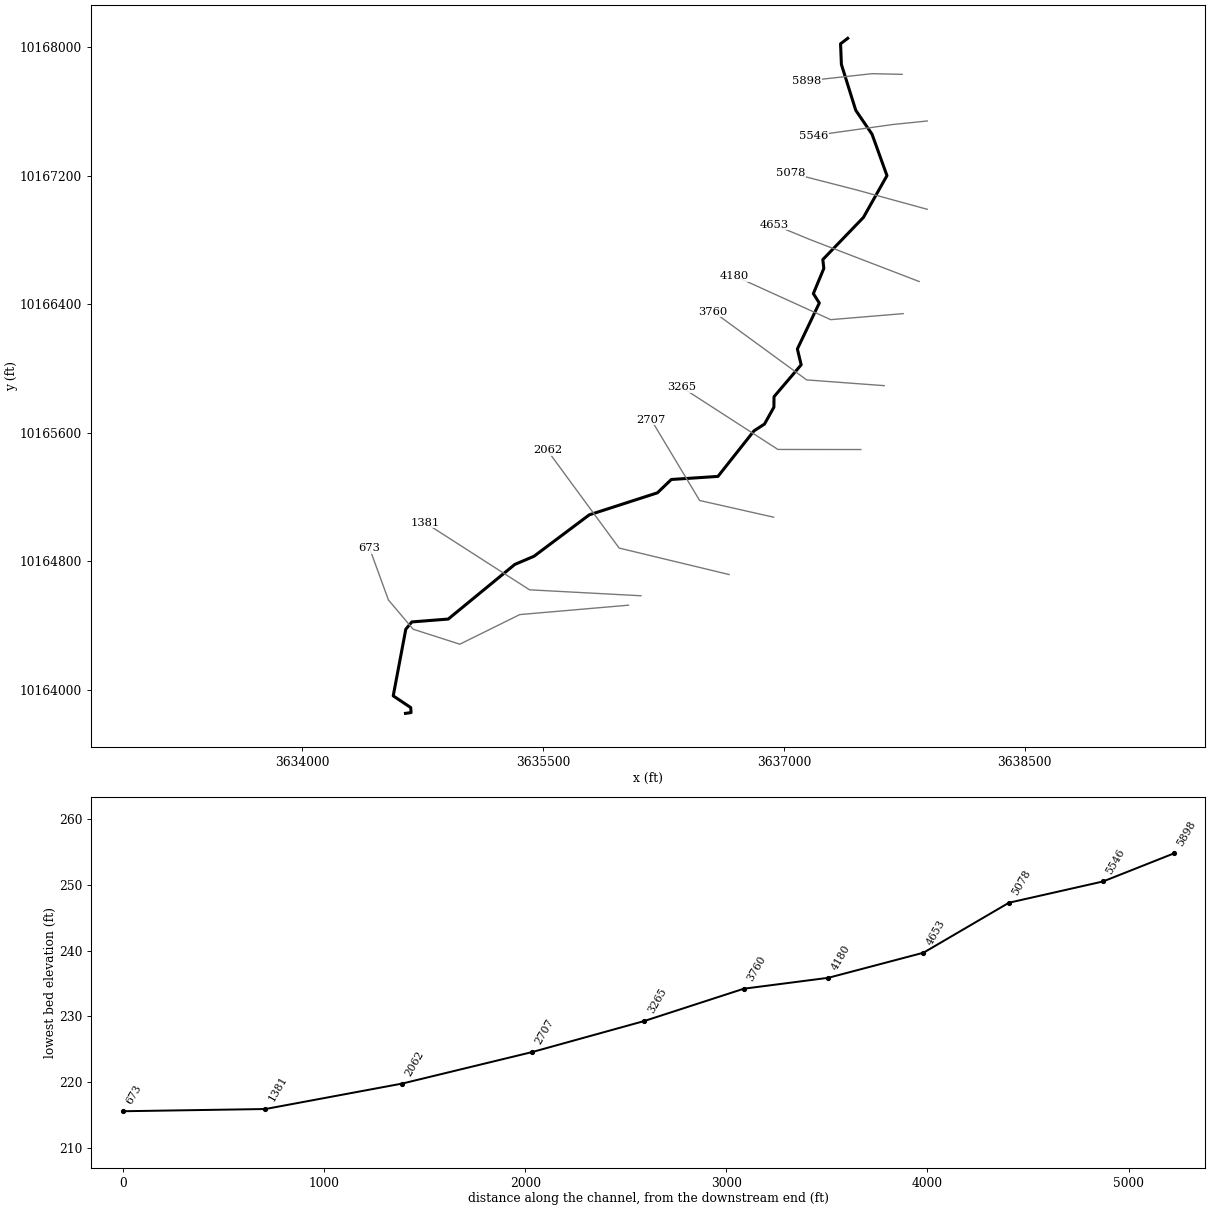
--- UNT028 IN ROCK.prj (project) ---

Proj Title=UNT028 IN ROCK Base Level Engineering
Current Plan=p01
Default Exp/Contr=0.3,0.1
English Units
Geom File=g01
Flow File=f01
Plan File=p01
Y Axis Title=Elevation
X Axis Title(PF)=Main Channel Distance
X Axis Title(XS)=Station
BEGIN DESCRIPTION:
UNT028 IN ROCK
END DESCRIPTION:
DSS Export Rating Curves= 0
DSS Export Rating Curve Sorted= 0
DSS Export Volume Flow Curves= 0
DXF OffsetX= 0
DXF OffsetY= 0
DXF ScaleX= 1
DXF ScaleY= 10

--- UNT028 IN ROCK.p01 (plan) ---

Plan Title=Multiple Run
Short Identifier=Multiple
Geom File=g01
Flow File=f01
Subcritical Flow
K Sum by GR= 0
Std Step Tol= 0.01
Critical Tol= 0.01
Num of Std Step Trials= 20
Max Error Tol= 0.3
Flow Tol Ratio= 0.001
Split Flow NTrial= 30
Split Flow Tol= 0.02
Split Flow Ratio= 0.02
Log Output Level= 0
Friction Slope Method= 1
Unsteady Friction Slope Method= 2
Unsteady Bridges Friction Slope Method= 1
Parabolic Critical Depth
Global Vel Dist=  1 , 1 , 1
Global Log Level= 0
CheckData=True
Encroach Param= -1, 0, 0, 0
BEGIN DESCRIPTION:
Multiple Run
END DESCRIPTION:

--- UNT028 IN ROCK.f01 (steady flow) ---

Flow Title=Multiple
Number of Profiles=7
Profile Names=10-year,25-year,50-year,1pct_min,100-year,1pct_plu,500-year
River Rch & RM= UNT028 IN ROCK,Reach-1,5898
     318     411     484     420     568     768     779
Boundary for River Rch & Prof#=UNT028 IN ROCK,Reach-1,1
Up Type=0
Dn Type=3
Dn Slope=0.005
Boundary for River Rch & Prof#=UNT028 IN ROCK,Reach-1,2
Up Type=0
Dn Type=3
Dn Slope=0.005
Boundary for River Rch & Prof#=UNT028 IN ROCK,Reach-1,3
Up Type=0
Dn Type=3
Dn Slope=0.005
Boundary for River Rch & Prof#=UNT028 IN ROCK,Reach-1,4
Up Type=0
Dn Type=3
Dn Slope=0.005
Boundary for River Rch & Prof#=UNT028 IN ROCK,Reach-1,5
Up Type=0
Dn Type=3
Dn Slope=0.005
Boundary for River Rch & Prof#=UNT028 IN ROCK,Reach-1,6
Up Type=0
Dn Type=3
Dn Slope=0.005
Boundary for River Rch & Prof#=UNT028 IN ROCK,Reach-1,7
Up Type=0
Dn Type=3
Dn Slope=0.005

--- UNT028 IN ROCK.g01 (geometry) ---

Geom Title=Existing Conditions
Program Version=4.10

River Reach=UNT028 IN ROCK  ,Reach-1
Reach XY= 30
      3637396.84     10168056.49      3637352.31     10168022.43
      3637357.52     10167893.95      3637446.93     10167608.36
      3637548.49     10167459.06      3637641.37     10167201.24
      3637494.67     10166940.83      3637241.81     10166678.48
      3637248.14     10166623.38      3637182.88     10166466.41
       3637219.9     10166407.87      3637083.25     10166121.61
      3637106.88     10166022.68      3636937.73     10165824.09
       3636937.1     10165758.84      3636878.39     10165653.71
      3636812.92     10165611.33      3636588.53     10165327.71
      3636298.03     10165308.58      3636211.55     10165225.51
      3635787.07     10165088.36      3635442.84     10164830.39
      3635323.06     10164779.36      3634908.43     10164439.13
      3634681.94     10164421.32       3634644.2     10164375.95
      3634565.83     10163960.63      3634674.87     10163887.88
      3634676.96     10163856.64      3634642.11     10163851.64

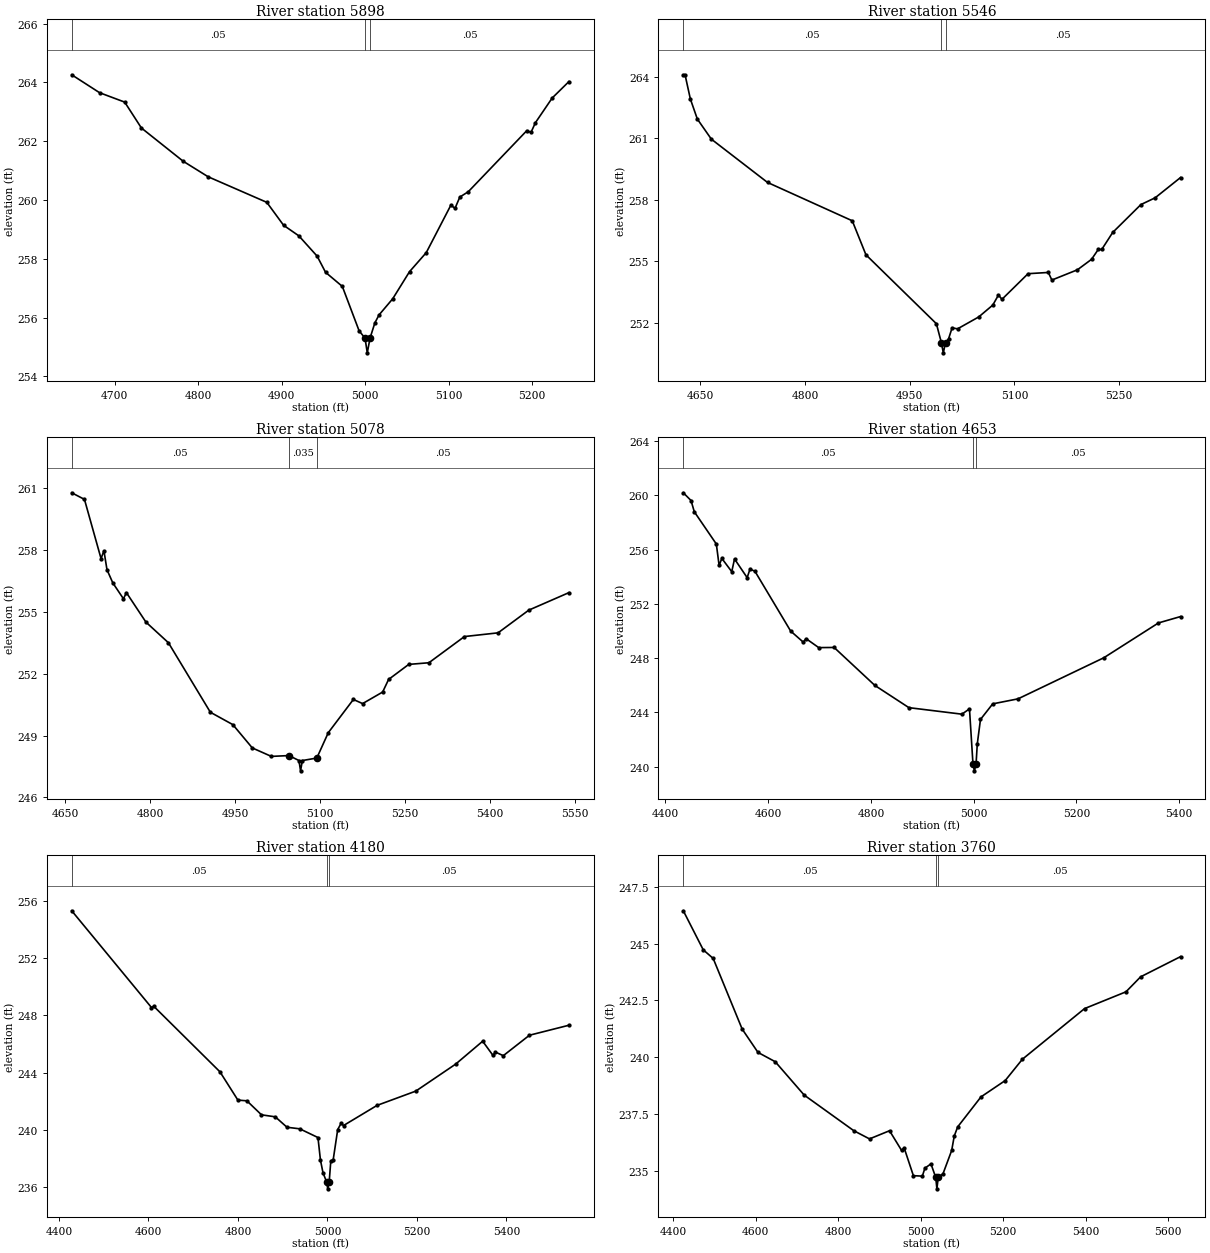
Type RM Length L Ch R = 1 ,5898    ,352,352,352
BEGIN DESCRIPTION:
UNT028 IN ROCK 10.0
END DESCRIPTION:
XS GIS Cut Line= 3
      3637735.54     10167832.26      3637548.94     10167836.35
      3637142.14     10167791.65
#Sta/Elev= 30
  4648.3  264.26  4681.7  263.65  4711.8  263.33  4731.8  262.45  4781.8  261.32
  4811.8  260.79  4882.1  259.92  4902.2  259.14  4920.5  258.78  4942.4  258.09
  4952.5  257.54  4972.6  257.06  4992.7  255.55  4999.8   255.3  5002.5   254.8
  5005.8   255.3  5011.6  255.82  5016.6  256.09    5033  256.64  5053.1  257.56
  5073.2  258.21  5102.6  259.82  5107.7  259.72  5113.4   260.1  5123.5  260.28
  5193.7  262.36  5198.7   262.3    5204  262.63  5224.1  263.47  5244.2  264.03
#Mann= 3 ,-1 , 0
  4648.3     .05       0  4999.8    .035       0  5005.8     .05       0
Bank Sta=4999.8,5005.8
XS Rating Curve= 0 ,0
Exp/Cntr=0.3,0.1

Type RM Length L Ch R = 1 ,5546    ,468,468,468
BEGIN DESCRIPTION:
UNT028 IN ROCK 9.0
END DESCRIPTION:
XS GIS Cut Line= 3
       3637892.1     10167541.64      3637677.27     10167519.65
       3637185.8     10167450.95
#Sta/Elev= 30
  4625.8  264.09  4628.3  264.09  4635.9  262.91  4645.9  261.93    4666  260.95
  4746.4  258.84  4867.8  256.97  4887.4  255.31  4988.3  251.95  4995.4  251.03
  4998.2  250.53  5001.4  251.03  5005.7  251.21  5010.8  251.75  5018.6   251.7
  5048.9  252.28  5069.1  252.86  5077.2  253.35  5082.2  253.14  5119.6  254.39
  5148.6  254.45  5153.7  254.08  5190.3  254.58  5210.5  255.09  5220.1  255.57
  5225.1  255.57  5240.8   256.4  5281.2  257.76  5301.6  258.09    5338  259.08
#Mann= 3 ,-1 , 0
  4625.8     .05       0  4995.4    .035       0  5001.4     .05       0
Bank Sta=4995.4,5001.4
XS Rating Curve= 0 ,0
Exp/Cntr=0.3,0.1

Type RM Length L Ch R = 1 ,5078    ,425,425,425
BEGIN DESCRIPTION:
UNT028 IN ROCK 8.0
END DESCRIPTION:
XS GIS Cut Line= 3
      3637892.15     10166991.63      3637453.01      10167111.9
      3637043.32     10167217.15
#Sta/Elev= 30
  4661.5  260.77    4684  260.45  4713.3  257.58  4718.4  257.96  4723.8  257.04
  4734.1   256.4  4752.9  255.63  4758.1  255.93  4792.6   254.5  4832.3   253.5
  4906.4  250.13  4946.1  249.53  4980.5   248.4  5014.1  247.99  5045.2  248.03
  5062.9  247.79  5065.7  247.29  5068.9  247.79  5094.4  247.91  5114.7  249.14
    5159  250.75  5175.3  250.55  5210.7  251.11  5221.2  251.72  5256.8  252.45
  5292.4  252.53  5355.2   253.8  5414.6  253.98  5468.8  255.08  5539.8  255.93
#Mann= 3 , 0 , 0
  4661.5     .05       0  5045.2    .035       0  5094.4     .05       0
Bank Sta=5045.2,5094.4
XS Rating Curve= 0 ,0
Exp/Cntr=0.3,0.1

Type RM Length L Ch R = 1 ,4653    ,473,473,473
BEGIN DESCRIPTION:
UNT028 IN ROCK 7.0
END DESCRIPTION:
XS GIS Cut Line= 3
       3637842.1     10166541.64      3637161.27     10166803.32
      3636940.74     10166894.43
#Sta/Elev= 30
  4434.8  260.19  4449.8  259.62  4456.2  258.79  4499.1  256.41  4504.5  254.83
  4509.8  255.35  4529.1  254.37  4534.5  255.31  4559.1  253.93  4564.5  254.55
  4574.1  254.41  4643.8  249.99  4668.4  249.17  4673.8  249.43  4698.4  248.77
  4728.4  248.78  4807.7  245.98    4874  244.34  4977.1  243.86  4991.9  244.25
  4998.7  240.18  5001.5  239.68  5004.7  240.18  5007.1  241.67  5013.3  243.47
  5037.1  244.62  5086.4  244.99  5253.4  248.02  5359.8  250.59  5402.8  251.06
#Mann= 3 ,-1 , 0
  4434.8     .05       0  4998.7     .03       0  5004.7     .05       0
Bank Sta=4998.7,5004.7
XS Rating Curve= 0 ,0
Exp/Cntr=0.3,0.1

Type RM Length L Ch R = 1 ,4180    ,420,420,420
BEGIN DESCRIPTION:
UNT028 IN ROCK 6.0
END DESCRIPTION:
XS GIS Cut Line= 3
      3637742.15     10166341.65       3637291.1     10166304.06
      3636691.73     10166576.51
#Sta/Elev= 30
  4428.6  255.32  4606.8  248.55  4611.8  248.64  4759.8  244.05  4799.9  242.07
    4820  242.02  4852.6  241.04  4883.4   240.9  4909.6  240.17  4938.2  240.06
  4978.8  239.45  4984.3  237.88    4990  236.99  4997.9  236.36  5000.7  235.86
  5003.9  236.36  5007.4  237.78  5012.9  237.91  5022.9  240.01  5030.4  240.44
  5035.9  240.29  5110.8   241.7  5197.4   242.7  5286.5  244.59  5346.8  246.19
  5369.8   245.2  5375.3  245.43  5392.9  245.18  5451.3  246.61  5539.6  247.31
#Mann= 3 ,-1 , 0
  4428.6     .05       0  4997.9     .03       0  5003.9     .05       0
Bank Sta=4997.9,5003.9
XS Rating Curve= 0 ,0
Exp/Cntr=0.3,0.1

Type RM Length L Ch R = 1 ,3760    ,495,495,495
BEGIN DESCRIPTION:
UNT028 IN ROCK 5.0
END DESCRIPTION:
XS GIS Cut Line= 3
       3637624.3     10165892.99      3637141.09     10165928.89
      3636559.27     10166353.97
#Sta/Elev= 30
  4424.5  246.45  4472.8  244.73  4496.9  244.35  4567.1  241.24  4605.5  240.21
  4647.3   239.8  4717.5  238.33  4837.8  236.76  4875.8   236.4  4924.3  236.76
  4953.6  235.89  4959.8     236  4982.1  234.78  5003.8  234.76    5010  235.11
  5024.7   235.3  5036.3   234.7  5039.1   234.2  5042.3   234.7    5054  234.87
  5074.9  235.89  5081.2  236.53  5089.5  236.93  5145.9  238.25  5204.6  238.97
  5246.3  239.91  5396.9  242.14  5497.3  242.88  5532.8  243.54  5629.6  244.43
#Mann= 3 ,-1 , 0
  4424.5     .05       0  5036.3    .035       0  5042.3     .05       0
Bank Sta=5036.3,5042.3
XS Rating Curve= 0 ,0
Exp/Cntr=0.3,0.1

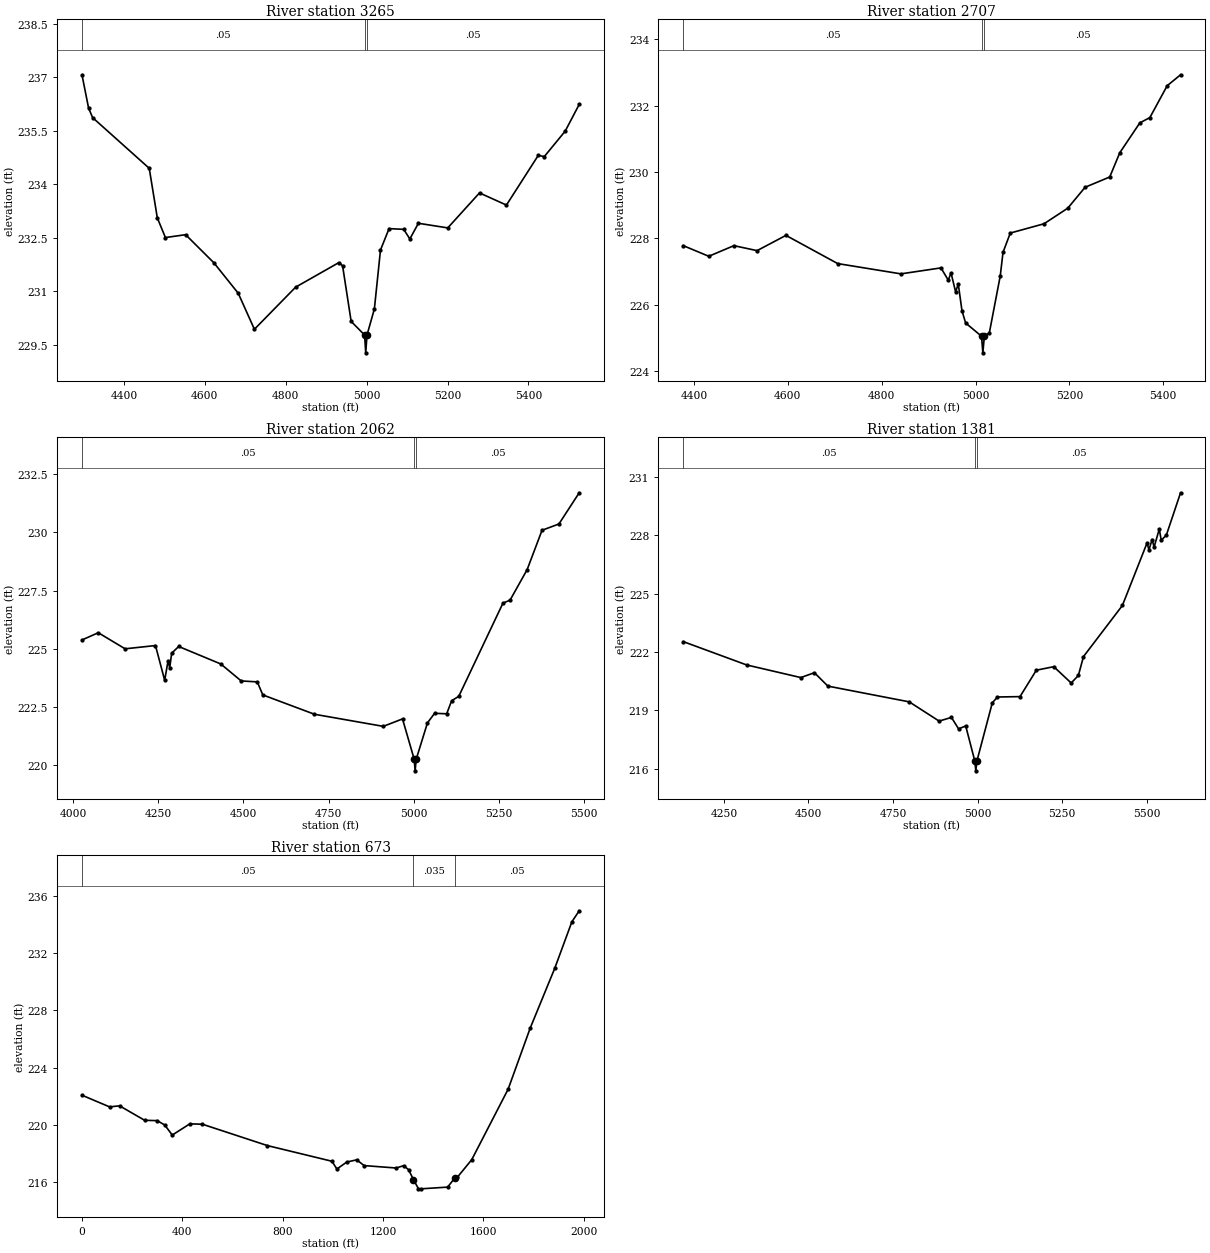
Type RM Length L Ch R = 1 ,3265    ,558,558,558
BEGIN DESCRIPTION:
UNT028 IN ROCK 4.0
END DESCRIPTION:
XS GIS Cut Line= 3
      3637478.43     10165495.12      3636961.97      10165495.6
      3636363.21     10165882.41
#Sta/Elev= 30
  4296.2  237.07  4312.5  236.14  4322.5  235.87  4462.5  234.45  4482.5  233.06
  4502.5  232.51  4552.5  232.59  4622.5   231.8  4682.5  230.95  4722.5  229.94
  4824.4  231.12  4931.6  231.81  4940.5  231.72  4961.7  230.16  4994.9  229.78
  4997.7  229.28  5000.9  229.78  5019.1  230.51  5034.2  232.16  5055.4  232.76
  5091.6  232.74  5106.8  232.47  5127.9  232.91  5200.5  232.78    5279  233.76
  5345.6  233.42  5424.2  234.81  5439.3  234.78  5490.8  235.49  5525.5  236.24
#Mann= 3 ,-1 , 0
  4296.2     .05       0  4994.9    .035       0  5000.9     .05       0
Bank Sta=4994.9,5000.9
XS Rating Curve= 0 ,0
Exp/Cntr=0.3,0.1

Type RM Length L Ch R = 1 ,2707    ,645,645,645
BEGIN DESCRIPTION:
UNT028 IN ROCK 3.0
END DESCRIPTION:
XS GIS Cut Line= 3
      3636935.45     10165073.63       3636474.5     10165177.69
      3636172.47     10165681.08
#Sta/Elev= 30
  4377.3  227.78  4431.6  227.46  4485.1  227.78  4534.5  227.63    4596  228.09
  4706.3  227.24    4841  226.93  4926.4  227.11  4941.9  226.74  4947.8  226.96
  4957.5  226.39  4963.3  226.62  4971.1  225.82  4978.9  225.45  5012.8  225.05
  5015.6  224.55  5018.8  225.05  5029.4  225.15  5052.7  226.87  5058.6  227.58
  5074.1  228.16    5146  228.44  5196.6  228.91  5233.5  229.54    5286  229.85
  5307.4  230.58  5350.1  231.48  5371.5  231.64  5408.4   232.6  5436.9  232.93
#Mann= 3 ,-1 , 0
  4377.3     .05       0  5012.8     .03       0  5018.8     .05       0
Bank Sta=5012.8,5018.8
XS Rating Curve= 0 ,0
Exp/Cntr=0.3,0.1

Type RM Length L Ch R = 1 ,2062    ,681,681,681
BEGIN DESCRIPTION:
UNT028 IN ROCK 2.0
END DESCRIPTION:
XS GIS Cut Line= 3
      3636658.03     10164716.49      3635973.03     10164881.34
      3635526.56     10165489.62
#Sta/Elev= 30
  4026.1  225.38    4074  225.69  4152.7     225  4241.8  225.14  4268.8  223.65
  4278.6  224.47  4283.7  224.19  4289.3  224.81  4309.9   225.1  4433.3  224.35
  4493.4  223.62  4540.5  223.58  4556.8  223.02  4708.2  222.19  4910.3  221.67
  4966.7  221.99  5000.9  220.26  5003.7  219.76  5006.9  220.26  5039.9  221.82
  5060.8  222.23  5096.3  222.21  5110.9  222.77  5131.8  222.96  5261.4  226.96
  5282.3  227.09  5332.4   228.4  5376.1  230.09  5425.7  230.36  5485.2   231.7
#Mann= 3 ,-1 , 0
  4026.1     .05       0  5000.9     .03       0  5006.9     .05       0
Bank Sta=5000.9,5006.9
XS Rating Curve= 0 ,0
Exp/Cntr=0.3,0.1

Type RM Length L Ch R = 1 ,1381    ,708,708,708
BEGIN DESCRIPTION:
UNT028 IN ROCK 1.0
END DESCRIPTION:
XS GIS Cut Line= 3
      3636108.92     10164584.25      3635414.79     10164621.34
      3634763.06     10165039.93
#Sta/Elev= 30
  4130.2  222.53  4317.3  221.33  4477.5  220.68  4517.6  220.93  4557.6  220.24
    4798  219.43  4886.3  218.44  4922.7  218.63  4943.8  218.04  4964.9  218.19
  4991.9  216.38  4994.7  215.88  4997.9  216.38  5043.5  219.38  5058.7  219.68
  5125.4   219.7  5173.7  221.06  5225.2  221.24  5276.7   220.4  5297.9  220.79
    5313  221.76    5428  224.39  5500.7   227.6  5506.6  227.26  5515.8  227.78
  5521.8   227.4    5537  228.32  5542.9  227.74  5558.1  228.02  5599.9  230.19
#Mann= 3 ,-1 , 0
  4130.2     .05       0  4991.9     .03       0  4997.9     .05       0
Bank Sta=4991.9,4997.9
XS Rating Curve= 0 ,0
Exp/Cntr=0.3,0.1

Type RM Length L Ch R = 1 ,673     ,0,0,0
XS GIS Cut Line= 6
     3636031.121     10164525.58     3635354.038    10164466.987
     3634980.774    10164282.525     3634689.976    10164375.841
     3634535.896    10164558.1333634418.7080836810164879.3127706
#Sta/Elev= 30
       0222.0814109.9684221.2655149.9569221.3386249.9281220.3285299.9137220.3044
329.9051220.0008359.8965219.2976429.8763220.0804 479.862220.0558739.1472218.5628
996.2988217.4696 1016.08216.92691055.641217.41581095.203217.56711124.695217.1663
1252.493216.99771281.984 217.1611301.646216.88361321.307216.18981340.968 215.553
1350.798 215.5431457.573215.66391486.385216.30941495.988216.3483 1553.61217.5796
1698.654222.50131786.569226.76541884.252230.9347 1952.63234.18581981.935234.9584
#Mann= 3 , 0 , 0
       0     .05       01321.307    .035       01486.385     .05       0
Bank Sta=1321.307,1486.385
XS Rating Curve= 0 ,0
Exp/Cntr=0.3,0.1

Chan Stop Cuts=-1
Use User Specified Reach Order=0
Composite Channel Slope=5