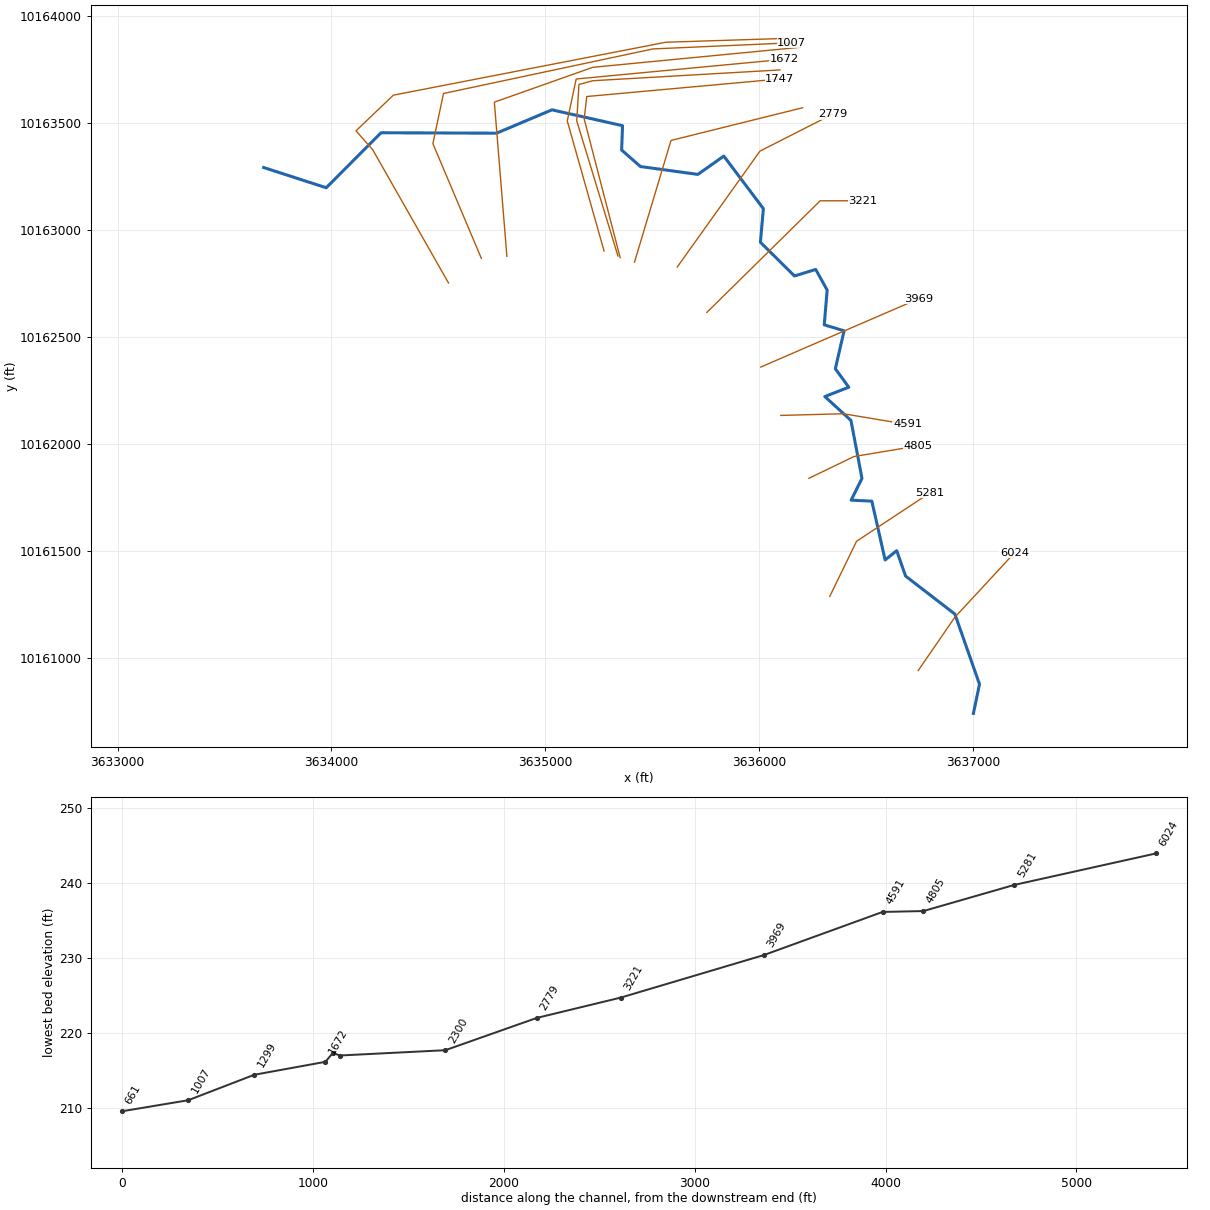
--- UNT029 IN ROCK.prj (project) ---

Proj Title=UNT029 IN ROCK Base Level Engineering
Current Plan=p01
Default Exp/Contr=0.3,0.1
English Units
Geom File=g01
Flow File=f01
Plan File=p01
Y Axis Title=Elevation
X Axis Title(PF)=Main Channel Distance
X Axis Title(XS)=Station
BEGIN DESCRIPTION:
UNT029 IN ROCK
END DESCRIPTION:
DSS Export Rating Curves= 0
DSS Export Rating Curve Sorted= 0
DSS Export Volume Flow Curves= 0
DXF OffsetX= 0
DXF OffsetY= 0
DXF ScaleX= 1
DXF ScaleY= 10

--- UNT029 IN ROCK.p01 (plan) ---

Plan Title=Multiple Run
Short Identifier=Multiple
Geom File=g01
Flow File=f01
Subcritical Flow
K Sum by GR= 0
Std Step Tol= 0.01
Critical Tol= 0.01
Num of Std Step Trials= 20
Max Error Tol= 0.3
Flow Tol Ratio= 0.001
Split Flow NTrial= 30
Split Flow Tol= 0.02
Split Flow Ratio= 0.02
Log Output Level= 0
Friction Slope Method= 1
Unsteady Friction Slope Method= 2
Unsteady Bridges Friction Slope Method= 1
Parabolic Critical Depth
Global Vel Dist=  1 , 1 , 1
Global Log Level= 0
CheckData=True
Encroach Param= -1, 0, 0, 0
BEGIN DESCRIPTION:
Multiple Run
END DESCRIPTION:

--- UNT029 IN ROCK.f01 (steady flow) ---

Flow Title=Multiple
Program Version=4.10
Number of Profiles= 7
Profile Names=10-year,25-year,50-year,1pct_min,100-year,1pct_plu,500-year
River Rch & RM=UNT029 IN ROCK,Reach-1         ,6024
     356     464     549     478     646     874     895
Boundary for River Rch & Prof#=UNT029 IN ROCK,Reach-1         , 1
Up Type= 0
Dn Type= 3
Dn Slope=0.008
Boundary for River Rch & Prof#=UNT029 IN ROCK,Reach-1         , 2
Up Type= 0
Dn Type= 3
Dn Slope=0.008
Boundary for River Rch & Prof#=UNT029 IN ROCK,Reach-1         , 3
Up Type= 0
Dn Type= 3
Dn Slope=0.008
Boundary for River Rch & Prof#=UNT029 IN ROCK,Reach-1         , 4
Up Type= 0
Dn Type= 3
Dn Slope=0.008
Boundary for River Rch & Prof#=UNT029 IN ROCK,Reach-1         , 5
Up Type= 0
Dn Type= 3
Dn Slope=0.008
Boundary for River Rch & Prof#=UNT029 IN ROCK,Reach-1         , 6
Up Type= 0
Dn Type= 3
Dn Slope=0.008
Boundary for River Rch & Prof#=UNT029 IN ROCK,Reach-1         , 7
Up Type= 0
Dn Type= 3
Dn Slope=0.008
DSS Import GetInterval= 0
DSS Import GetPeak= 0
DSS Import FillOption= 0

--- UNT029 IN ROCK.g01 (geometry) ---

Geom Title=Existing Conditions
Program Version=4.10

River Reach=UNT029 IN ROCK  ,Reach-1
Reach XY= 30
      3637000.03     10160741.28      3637028.46     10160877.67
      3636913.44     10161205.36        3636683.     10161382.91
      3636641.43     10161501.72      3636587.42     10161458.18
      3636525.26     10161733.18      3636428.57     10161737.66
      3636479.21     10161839.67      3636427.72     10162110.33
       3636305.6     10162221.99      3636417.71     10162265.59
      3636354.74     10162351.73      3636395.72     10162529.32
       3636302.9     10162557.12       3636316.5     10162719.72
      3636263.03     10162815.93      3636163.71     10162785.51
      3636004.59     10162943.06      3636018.36     10163100.05
       3635833.5     10163345.69      3635712.21     10163260.14
      3635444.15     10163296.86      3635356.06     10163373.95
      3635360.22     10163487.82      3635030.39     10163561.93
      3634771.57     10163452.79      3634231.52     10163454.68
      3633975.44     10163197.73      3633683.43     10163292.24

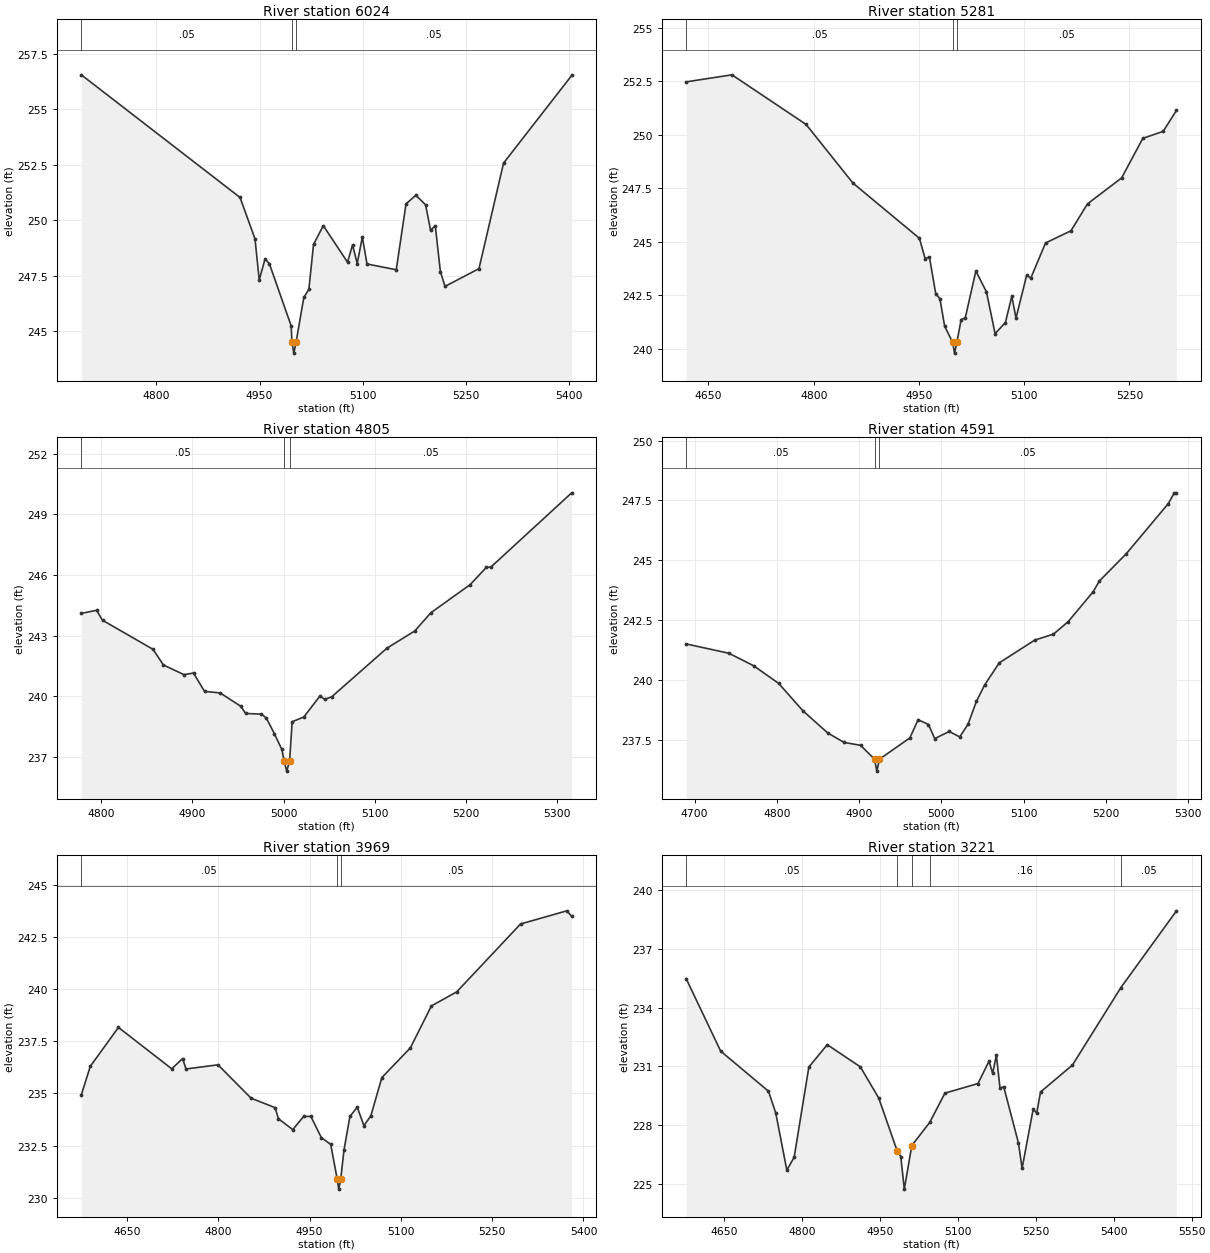
Type RM Length L Ch R = 1 ,6024    ,743,743,743
BEGIN DESCRIPTION:
UNT029 IN ROCK 9.0
END DESCRIPTION:
XS GIS Cut Line= 3
      3636742.09     10160941.61      3636913.22      10161190.5
      3637192.11     10161491.65
#Sta/Elev= 30
    4691  256.55  4921.6  251.02  4943.4  249.15  4949.5   247.3    4958  248.25
  4964.3  248.03  4995.9  245.23  4997.1   244.5  4999.8     244  5003.1   244.5
  5014.3  246.51  5021.6  246.87  5028.4   248.9  5042.6  249.75  5077.8   248.1
  5085.1  248.88  5091.9  248.04  5099.3  249.24  5106.1  248.02  5148.6  247.76
  5162.8  250.73    5177  251.12  5191.2  250.69  5198.5  249.54  5205.3  249.75
  5212.7  247.68  5219.5  247.01  5268.8  247.81  5304.5  252.57  5403.5  256.52
#Mann= 3 ,-1 , 0
    4691     .05       0  4997.1     .03       0  5003.1     .05       0
Bank Sta=4997.1,5003.1
XS Rating Curve= 0 ,0
Exp/Cntr=0.3,0.1

Type RM Length L Ch R = 1 ,5281    ,476,476,476
BEGIN DESCRIPTION:
UNT029 IN ROCK 8.0
END DESCRIPTION:
XS GIS Cut Line= 3
      3636328.61     10161287.84      3636453.91     10161545.67
      3636797.91     10161772.64
#Sta/Elev= 30
  4618.2  252.47  4683.5   252.8  4789.2  250.48  4855.9  247.74  4950.6  245.16
  4958.9   244.2  4964.9  244.29  4973.9  242.57  4979.9  242.33  4986.6  241.05
    4998  240.29  5000.7  239.79    5004  240.29  5010.1  241.36    5016  241.44
  5031.1  243.63  5046.2  242.65  5058.5   240.7  5073.2  241.22  5082.3  242.45
  5088.3  241.43  5103.4  243.42  5109.4   243.3  5130.4  244.94  5166.6  245.51
  5190.2  246.77  5238.8  247.98    5269  249.83  5298.1  250.16    5317  251.14
#Mann= 3 ,-1 , 0
  4618.2     .05       0    4998     .03       0    5004     .05       0
Bank Sta=4998,5004
XS Rating Curve= 0 ,0
Exp/Cntr=0.3,0.1

Type RM Length L Ch R = 1 ,4805    ,214,214,214
BEGIN DESCRIPTION:
UNT029 IN ROCK 7.0
END DESCRIPTION:
XS GIS Cut Line= 3
      3636231.12     10161839.85      3636442.11     10161941.64
      3636742.11     10161991.64
#Sta/Elev= 30
    4778   244.1  4794.7  244.25  4801.3  243.76  4856.8  242.32  4868.1  241.55
  4890.7  241.07  4901.2  241.15  4913.3  240.24  4930.3  240.17    4953  239.51
  4958.5  239.15  4975.6  239.12  4981.1  238.93  4990.1  238.14  4998.2  237.37
  5000.7   236.8  5003.5   236.3  5006.7   236.8  5009.5  238.74  5022.4  238.98
  5040.1  240.02  5045.2  239.85  5052.8  239.97  5113.6  242.38  5144.1  243.23
  5161.8  244.13  5204.9  245.52  5222.6  246.37  5227.7  246.39  5316.4  250.06
#Mann= 3 ,-1 , 0
    4778     .05       0  5000.7     .03       0  5006.7     .05       0
Bank Sta=5000.7,5006.7
XS Rating Curve= 0 ,0
Exp/Cntr=0.3,0.1

Type RM Length L Ch R = 1 ,4591    ,622,622,622
BEGIN DESCRIPTION:
UNT029 IN ROCK 6.0
END DESCRIPTION:
XS GIS Cut Line= 3
      3636100.09     10162133.71      3636392.11     10162141.64
      3636692.14     10162091.64
#Sta/Elev= 30
  4689.7   241.5  4741.7  241.11  4771.7  240.59  4802.2  239.85  4831.8   238.7
  4861.8  237.78  4881.8  237.38  4901.8  237.26  4918.8  236.68  4921.6  236.18
  4924.8  236.68  4961.8  237.57  4971.8  238.33  4984.4  238.13    4992  237.54
  5009.7  237.84  5022.4  237.61  5032.5  238.14  5042.7   239.1  5052.8  239.79
  5070.5  240.71  5113.6  241.66  5136.4  241.91  5154.2  242.43  5184.6  243.68
  5192.2  244.13  5225.1  245.28  5275.8  247.36  5283.4  247.82    5286  247.82
#Mann= 3 ,-1 , 0
  4689.7     .05       0  4918.8     .03       0  4924.8     .05       0
Bank Sta=4918.8,4924.8
XS Rating Curve= 0 ,0
Exp/Cntr=0.3,0.1

Type RM Length L Ch R = 1 ,3969    ,748,748,748
BEGIN DESCRIPTION:
UNT029 IN ROCK 5.0
END DESCRIPTION:
XS GIS Cut Line= 3
      3636006.11     10162359.61      3636194.45     10162441.34
      3636745.37     10162679.48
#Sta/Elev= 30
  4575.1  234.93  4589.9   236.3  4636.1  238.16  4723.6  236.18  4741.6  236.67
    4747  236.17  4799.6  236.37  4854.1  234.77  4893.4  234.32  4898.9  233.79
  4922.4  233.27  4940.4   233.9  4952.2   233.9  4969.3  232.89  4984.8  232.56
  4995.3  230.92    4998  230.42  5001.3  230.92  5006.6  232.29  5016.3   233.9
  5028.4  234.34  5039.3  233.46  5050.7  233.93  5068.8  235.76  5115.6  237.18
  5150.2  239.19  5191.7  239.86  5296.6  243.11  5372.5  243.74  5380.6  243.48
#Mann= 3 ,-1 , 0
  4575.1     .05       0  4995.3     .03       0  5001.3     .05       0
Bank Sta=4995.3,5001.3
XS Rating Curve= 0 ,0
Exp/Cntr=0.3,0.1

Type RM Length L Ch R = 1 ,3221    ,442,442,442
BEGIN DESCRIPTION:
UNT029 IN ROCK 4.0
END DESCRIPTION:
XS GIS Cut Line= 3
      3635754.44     10162615.36      3636284.03     10163136.88
      3636484.06     10163136.88
#Sta/Elev= 30
  4577.6  235.48  4644.1  231.78    4736  229.74  4750.1  228.62  4771.3  225.72
  4785.4  226.37  4813.7  230.97  4849.1  232.11  4912.7  230.98  4948.1  229.39
  4983.4  226.71  4990.5  226.41  4997.3  224.75  5011.7  226.97  5046.2  228.15
  5075.4  229.64    5139  230.13  5160.3  231.27  5167.3  230.65  5174.4  231.57
  5181.4   229.9  5188.6  229.96  5216.8  227.11  5223.9  225.81  5245.1  228.81
  5252.1  228.63  5259.3   229.7  5320.7  231.07  5413.9  235.02  5520.9  238.93
#Mann= 5 ,-1 , 0
  4577.6     .05       0  4983.4    .035       0  5011.7     .05       0
  5046.2     .16       0  5413.9     .05       0
Bank Sta=4983.4,5011.7
XS Rating Curve= 0 ,0
Exp/Cntr=0.3,0.1

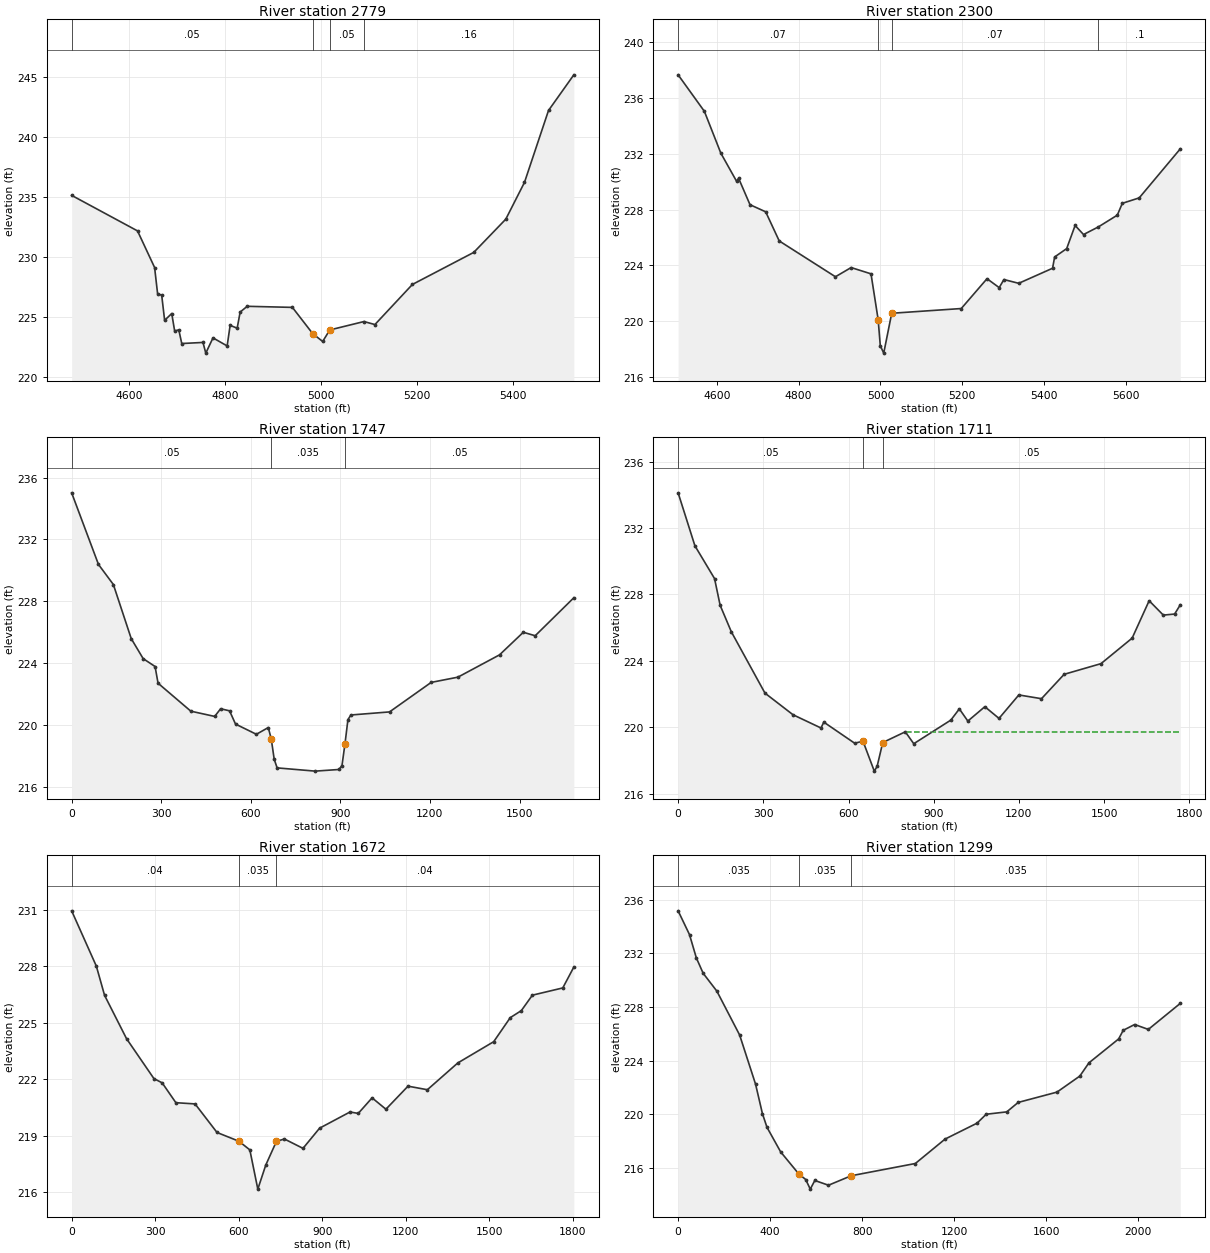
Type RM Length L Ch R = 1 ,2779    ,479,479,479
BEGIN DESCRIPTION:
UNT029 IN ROCK 3.0
END DESCRIPTION:
XS GIS Cut Line= 3
      3635615.75     10162827.11      3636002.52       10163369.
       3636342.1     10163541.64
#Sta/Elev= 30
    4480  235.16  4617.3   232.2  4652.9  229.15  4659.1  226.98  4667.7  226.84
  4673.8  224.75  4688.6  225.32  4694.7  223.86  4703.3  223.96  4709.5  222.82
  4753.7  222.91  4759.6  222.02  4774.6  223.29  4804.1  222.62  4810.3  224.33
    4825   224.1  4831.2  225.44  4845.9  225.92  4940.1  225.83  4982.3  223.65
  5003.2  222.99    5018  223.95  5089.3  224.65  5112.1   224.4  5190.2  227.74
  5318.1  230.41  5384.9  233.18  5423.8  236.24  5473.9  242.23  5526.7   245.2
#Mann= 4 ,-1 , 0
    4480     .05       0  4982.3    .035       0    5018     .05       0
  5089.3     .16       0
Bank Sta=4982.3,5018
XS Rating Curve= 0 ,0
Exp/Cntr=0.3,0.1

Type RM Length L Ch R = 1 ,2300    ,553,553,553
BEGIN DESCRIPTION:
UNT029 IN ROCK 2.0
END DESCRIPTION:
XS GIS Cut Line= 3
      3635416.08     10162850.12      3635586.67     10163418.76
      3636201.59      10163571.6
#Sta/Elev= 30
  4505.5  237.68  4569.7  235.06  4609.9  232.06  4648.2  230.05  4653.4  230.25
  4681.2  228.36  4719.5  227.85  4752.6  225.76    4890  223.19  4928.3  223.85
  4976.9   223.4  4994.4  220.11  4999.6  218.24    5008  217.71  5027.5  220.57
  5197.5  220.91  5260.4  223.05  5290.2  222.41  5301.7  222.99  5337.9  222.72
  5420.6   223.8  5425.7  224.61  5455.1  225.21  5475.7  226.87  5496.3  226.22
  5532.7  226.77  5578.8  227.61  5591.1  228.46  5632.4  228.85  5732.8  232.37
#Mann= 4 ,-1 , 0
  4505.5     .07       0  4994.4     .05       0  5027.5     .07       0
  5532.7      .1       0
Bank Sta=4994.4,5027.5
XS Rating Curve= 0 ,0
Exp/Cntr=0.3,0.1

Type RM Length L Ch R = 1 ,1747    ,36,36,36
XS GIS Cut Line= 4
     3635349.063    10162871.521     3635181.095    10163518.657
     3635192.813    10163624.125     3636095.157    10163706.157
#Sta/Elev= 30
       0235.0217 89.8091230.3856 139.703229.0846199.5758225.5815 239.491224.2865
279.4061223.7767289.3849222.6947399.1516 220.884478.9819220.5446498.9395221.0408
528.8759220.9067548.8334220.0498618.6849219.3878658.6001219.8245668.5789219.0765
678.3436217.7768688.1083217.2125815.8128217.0025895.4565217.1088 905.412217.3664
915.3675218.7615 925.323220.3348935.2784220.6376  1064.7220.83681204.076222.7469
1293.675223.08671433.052224.53061512.696225.99221552.518225.76861681.939228.2282
#Mann= 3 , 0 , 0
       0     .05       0668.5789    .035       0915.3675     .05       0
Bank Sta=668.5789,915.3675
XS Rating Curve= 0 ,0
Exp/Cntr=0.3,0.1

Type RM Length L Ch R = 1 ,1711    ,39,39,39
XS GIS Cut Line= 5
      3635338.84    10162878.587     3635146.131    10163510.531
     3635156.548     10163680.67      3635222.52    10163698.031
     3636095.784    10163748.378
#Sta/Elev= 30
       0 234.12459.18757 230.931128.2397228.9593147.9689227.3499187.4273225.7507
305.8024222.0591404.4484220.7571503.0943219.9583512.9589220.3123621.4695219.0427
651.0632219.1602690.7126217.3598700.6409217.6414720.4974219.0819799.9235219.7283
829.7083219.0111960.2951220.4338990.2186221.10861020.142 220.3751079.989221.2408
1129.862220.53591199.683221.94881279.479221.72311359.275 223.1921488.943223.8342
1598.663 225.372 1658.51227.62431708.382 226.758 1748.28226.82261768.229227.3801
#Mann= 3 ,-1 , 0
       0     .05       0651.0632    .035       0720.4974     .05       0
#XS Ineff= 2 , 0
                          801.14          219.73
Permanent Ineff=
       F       F
Bank Sta=651.0632,720.4974
XS Rating Curve= 0 ,0
Exp/Cntr=0.3,0.1

Type RM Length L Ch R = 1 ,1672    ,373,373,373
XS GIS Cut Line= 4
     3635273.805    10162902.189      3635101.93    10163509.828
     3635143.597    10163706.009     3636115.819    10163798.022
#Sta/Elev= 30
       0230.932388.68431227.9978118.2458226.4476197.0762 224.148295.6144222.0249
325.1758221.8006374.4449220.7464443.4216220.6814522.2521219.1657601.0826218.6996
640.1943218.2409668.8453216.1578697.4962217.4383735.6974218.6918764.3483218.8198
831.2006218.3226890.7737219.3935999.9911220.25251029.778220.17811079.422221.0035
1129.066220.39971208.497221.62371277.999221.43461387.217222.85541516.292223.9847
1575.865225.26191615.581225.63431655.296226.45481764.513226.83871804.229227.9479
#Mann= 3 , 0 , 0
       0     .04       0601.0826    .035       0735.6974     .04       0
Bank Sta=601.0826,735.6974
XS Rating Curve= 0 ,0
Exp/Cntr=0.3,0.1

Type RM Length L Ch R = 1 ,1299    ,346,346,346
XS GIS Cut Line= 4
     3634819.742    10162877.285     3634761.149    10163597.771
     3635220.784    10163760.531      3636191.27    10163854.281
#Sta/Elev= 30
       0235.165949.50414233.391579.20662231.6571108.9091230.5109168.3141229.1836
267.3223225.9137336.6281222.2459366.3306220.0572386.1323 219.037445.5372217.2067
524.7438215.5548554.4464215.1466 574.248214.4299594.0496215.0744653.4546 214.721
752.5771215.42841030.866216.33931160.072218.15941299.078219.34531338.771220.0095
1428.082 220.1861477.699220.88951646.397221.65861745.632222.85461785.325223.8406
 1914.33225.62131934.177226.26291983.794226.69552043.334226.33032182.262 228.271
#Mann= 3 , 0 , 0
       0    .035       0524.7438    .035       0752.5771    .035       0
Bank Sta=524.7438,752.5771
XS Rating Curve= 0 ,0
Exp/Cntr=0.3,0.1

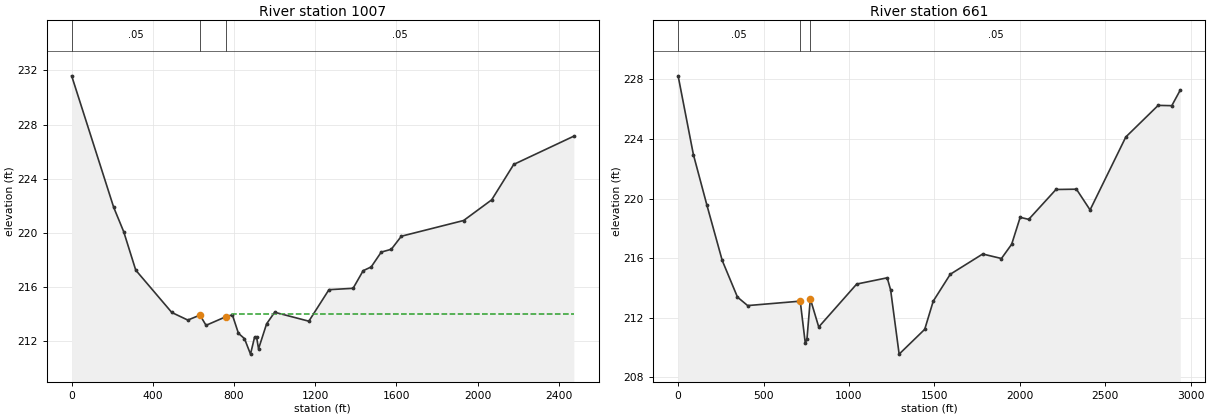
Type RM Length L Ch R = 1 ,1007    ,346,346,346
XS GIS Cut Line= 5
     3634700.537    10162867.388     3634473.974    10163403.846
     3634523.453    10163638.221      3635502.62    10163846.555
3636151.0565121910163875.1999785
#Sta/Elev= 30
       0231.6023 207.273221.8753256.6237220.0736315.8446217.2363493.5072214.1059
572.4683213.5444632.2429213.9129662.1854213.1564761.9941 213.805791.9368 213.928
821.8793212.5658851.6146212.1733881.3497 211.027901.1732212.2674911.0849 212.299
920.9966211.4213960.6436213.2656 1000.29214.1228 1168.79213.46181267.907215.7914
1386.848215.89321436.406217.19481476.053217.47421525.612218.57011575.171218.7788
1624.729219.74461931.576220.90622069.809222.43362178.421225.05222474.635227.1414
#Mann= 3 , 0 , 0
       0     .05       0632.2429    .035       0761.9941     .05       0
#XS Ineff= 2 , 0
                          792.61          214.01
Permanent Ineff=
       F       F
Bank Sta=632.2429,761.9941
XS Rating Curve= 0 ,0
Exp/Cntr=0.3,0.1

Type RM Length L Ch R = 1 ,661     ,0,0,0
XS GIS Cut Line= 6
     3634546.891    10162752.805     3634192.724      10163375.2
     3634114.599    10163463.742     3634289.078    10163630.409
     3635562.516    10163877.8053636130.2242440110163896.0340078
#Sta/Elev= 30
       0228.242389.35295 222.958168.7778219.5493258.1307215.8469347.4837213.3836
407.0523212.8165714.8236213.1139744.3439210.2904 754.184210.5742773.8641213.2703
823.0646211.3792 1045.24214.26161223.877214.68081243.834213.86771293.728209.5573
1443.411211.22171493.305213.11531593.093214.9203 1782.69216.27871892.457215.9777
 1952.33216.93332002.224218.74312052.118218.6048 2211.78220.61112331.525 220.631
  2411.3219.23862620.564224.13792809.897226.25862889.617226.23822939.442227.2909
#Mann= 3 , 0 , 0
       0     .05       0714.8236    .035       0773.8641     .05       0
#XS Ineff= 2 , 0
                         1222.16          214.61
Permanent Ineff=
       F       F
Bank Sta=714.8236,773.8641
XS Rating Curve= 0 ,0
Exp/Cntr=0.3,0.1

Chan Stop Cuts=-1
Use User Specified Reach Order=0
Composite Channel Slope=5