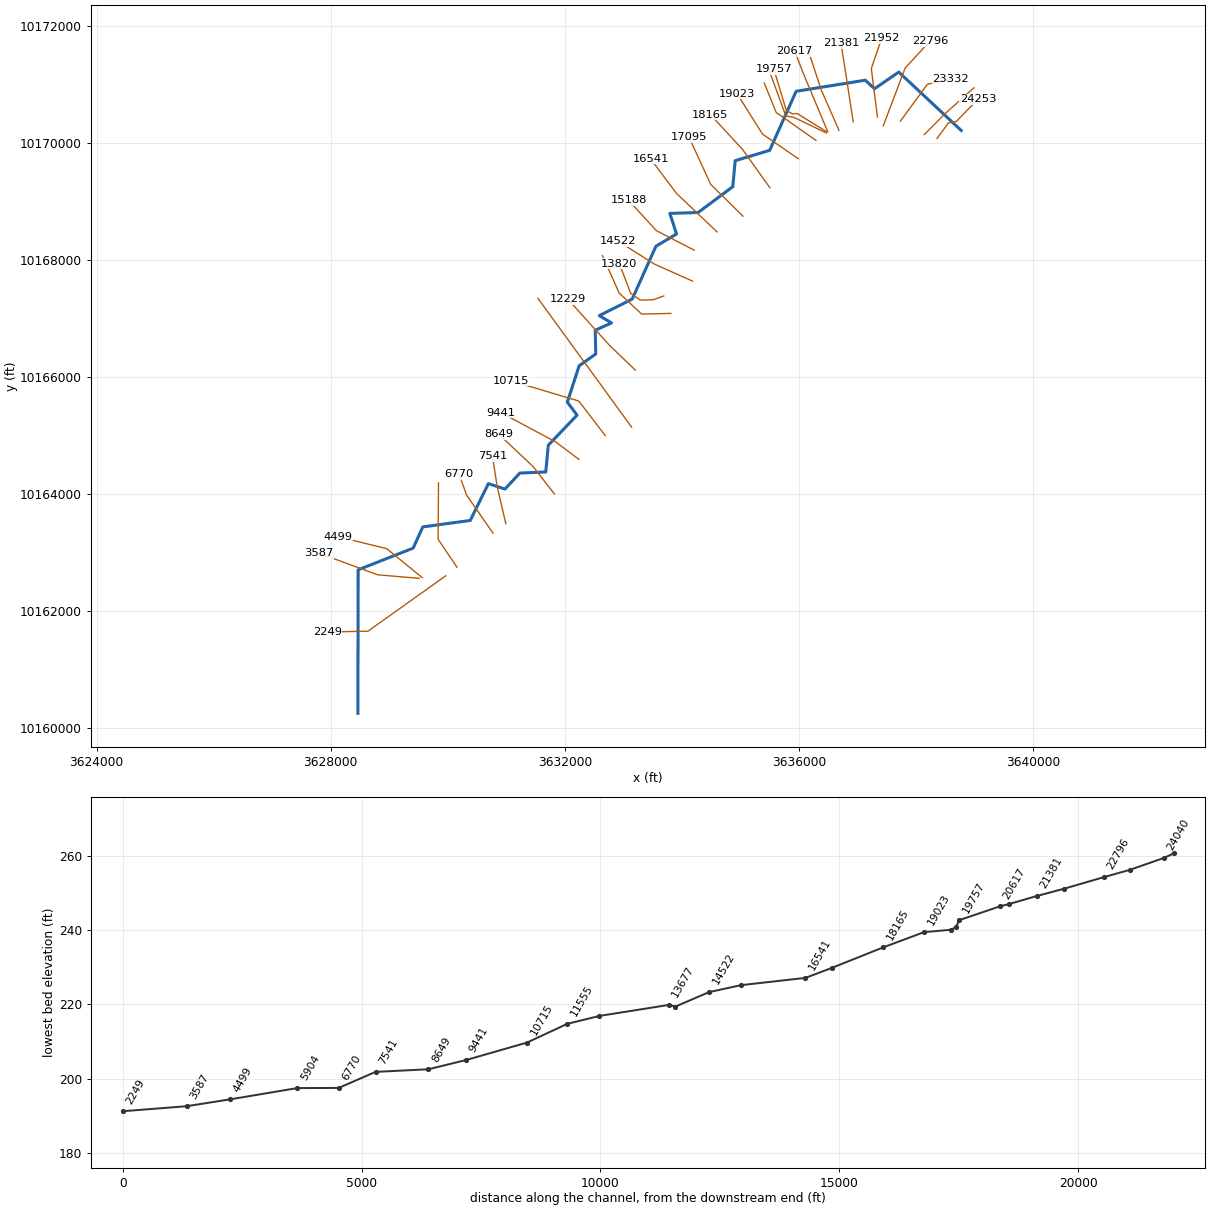
--- UNT030 IN ROCK.prj (project) ---

Proj Title=UNT030 IN ROCK Base Level Engineering
Current Plan=p01
Default Exp/Contr=0.3,0.1
English Units
Geom File=g01
Flow File=f01
Plan File=p01
Y Axis Title=Elevation
X Axis Title(PF)=Main Channel Distance
X Axis Title(XS)=Station
BEGIN DESCRIPTION:
UNT030 IN ROCK
END DESCRIPTION:
DSS Export Rating Curves= 0
DSS Export Rating Curve Sorted= 0
DSS Export Volume Flow Curves= 0
DXF OffsetX= 0
DXF OffsetY= 0
DXF ScaleX= 1
DXF ScaleY= 10

--- UNT030 IN ROCK.p01 (plan) ---

Plan Title=Multiple Run
Short Identifier=Multiple
Geom File=g01
Flow File=f01
Subcritical Flow
K Sum by GR= 0
Std Step Tol= 0.01
Critical Tol= 0.01
Num of Std Step Trials= 20
Max Error Tol= 0.3
Flow Tol Ratio= 0.001
Split Flow NTrial= 30
Split Flow Tol= 0.02
Split Flow Ratio= 0.02
Log Output Level= 0
Friction Slope Method= 1
Unsteady Friction Slope Method= 2
Unsteady Bridges Friction Slope Method= 1
Parabolic Critical Depth
Global Vel Dist=  1 , 1 , 1
Global Log Level= 0
CheckData=True
Encroach Param= -1, 0, 0, 0
BEGIN DESCRIPTION:
Multiple Run
END DESCRIPTION:

--- UNT030 IN ROCK.f01 (steady flow) ---

Flow Title=Multiple
Program Version=4.10
Number of Profiles= 7
Profile Names=10-year,25-year,50-year,1pct_min,100-year,1pct_plu,500-year
River Rch & RM=UNT030 IN ROCK,Reach-1         ,24253
     274     349     406     348     471     637     632
River Rch & RM=UNT030 IN ROCK,Reach-1         ,24040
     274     349     406     348     471     637     632
River Rch & RM=UNT030 IN ROCK,Reach-1         ,20617
     688     921    1109     978    1323    1789    1883
River Rch & RM=UNT030 IN ROCK,Reach-1         ,4499
     911    1239    1507    1341    1813    2452    2630
River Rch & RM=UNT030 IN ROCK,Reach-1         ,3587
     911    1239    1507    1341    1813    2452    2630
River Rch & RM=UNT030 IN ROCK,Reach-1         ,2249
    1123    1541    1887    1689    2284    3088    3351
Boundary for River Rch & Prof#=UNT030 IN ROCK,Reach-1         , 1
Up Type= 0
Dn Type= 3
Dn Slope=0.005
Boundary for River Rch & Prof#=UNT030 IN ROCK,Reach-1         , 2
Up Type= 0
Dn Type= 3
Dn Slope=0.005
Boundary for River Rch & Prof#=UNT030 IN ROCK,Reach-1         , 3
Up Type= 0
Dn Type= 3
Dn Slope=0.005
Boundary for River Rch & Prof#=UNT030 IN ROCK,Reach-1         , 4
Up Type= 0
Dn Type= 3
Dn Slope=0.005
Boundary for River Rch & Prof#=UNT030 IN ROCK,Reach-1         , 5
Up Type= 0
Dn Type= 3
Dn Slope=0.005
Boundary for River Rch & Prof#=UNT030 IN ROCK,Reach-1         , 6
Up Type= 0
Dn Type= 3
Dn Slope=0.005
Boundary for River Rch & Prof#=UNT030 IN ROCK,Reach-1         , 7
Up Type= 0
Dn Type= 3
Dn Slope=0.005
DSS Import GetInterval= 0
DSS Import GetPeak= 0
DSS Import FillOption= 0

--- UNT030 IN ROCK.g01 (geometry) ---

Geom Title=Existing Conditions
Program Version=4.10

River Reach=UNT030 IN ROCK  ,Reach-1
Reach XY= 30
      3638772.56     10170212.73      3637706.65     10171209.48
      3637290.93     10170924.23      3637135.14     10171070.76
      3635952.78     10170881.16      3635500.45     10169871.77
      3634911.11     10169695.24       3634870.5      10169251.3
      3634278.74     10168810.28      3633795.44     10168794.15
      3633908.99     10168442.56      3633557.21     10168233.63
      3633151.83     10167330.85      3632589.44     10167047.63
      3632798.57     10166923.19      3632519.98     10166797.78
      3632528.81     10166393.14      3632245.06     10166190.07
      3632043.13      10165570.6      3632209.48     10165347.01
      3631718.57     10164834.49       3631674.3     10164375.54
      3631233.27     10164358.39      3630976.78     10164083.98
      3630694.25     10164177.57      3630384.08     10163547.79
      3629573.65      10163437.9      3629409.34      10163075.1
      3628468.94     10162705.11      3628464.45     10160251.52

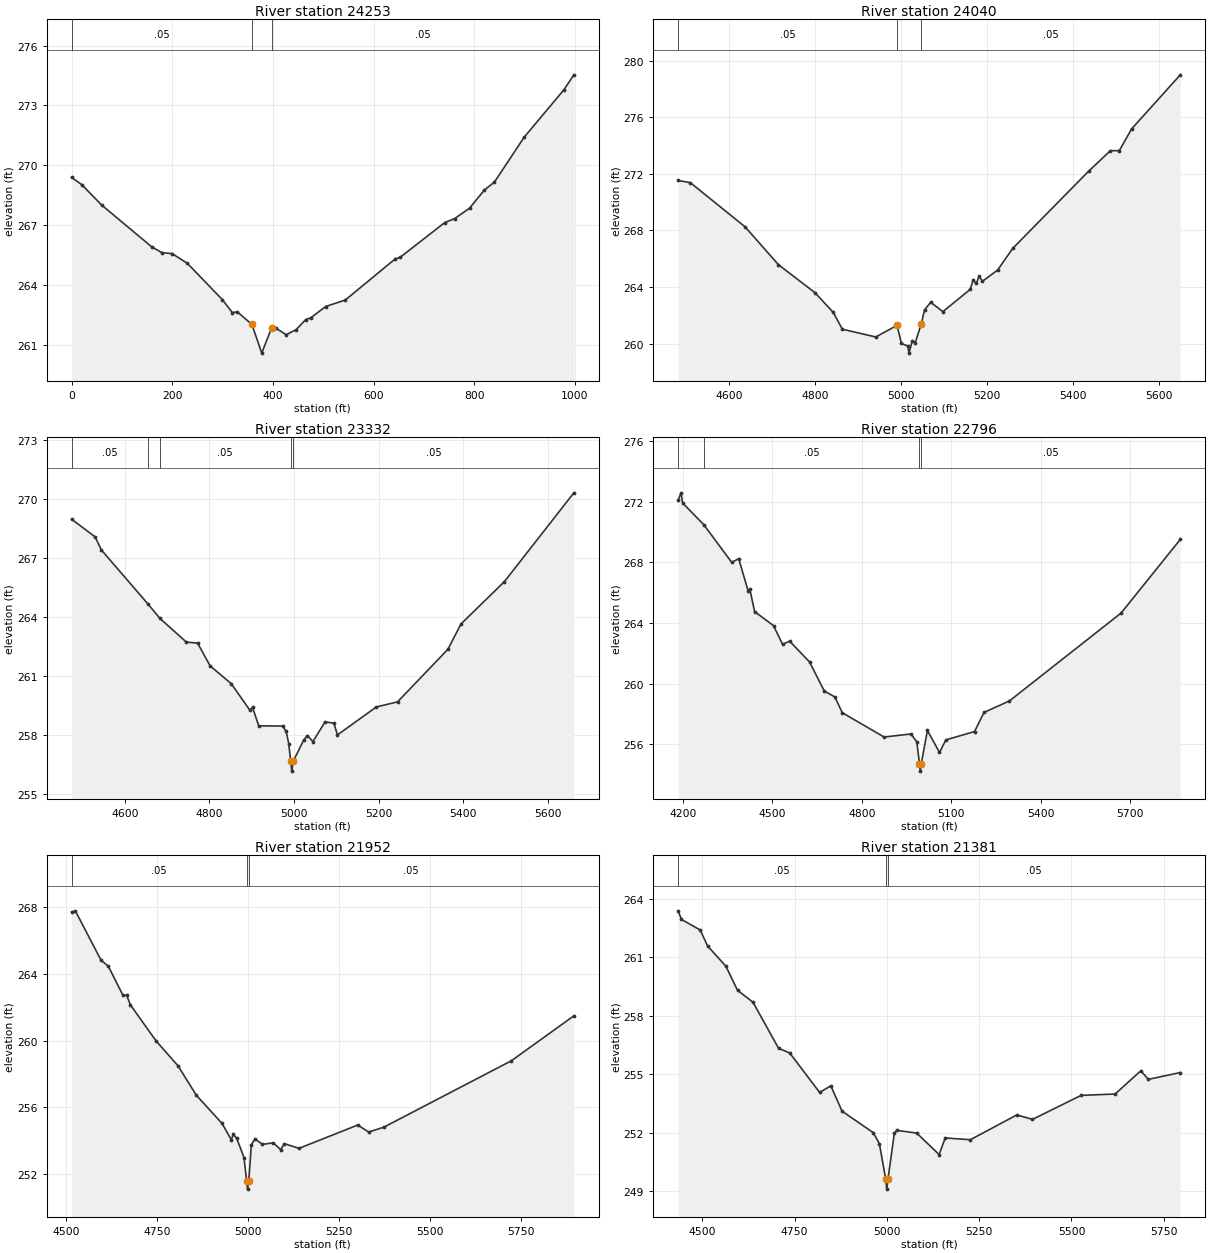
Type RM Length L Ch R = 1 ,24253   ,213,213,213
XS GIS Cut Line= 4
     3638360.644    10170075.899     3638555.956    10170341.524
     3638688.769    10170364.961     3639061.165    10170747.774
#Sta/Elev= 30
       0269.387719.95084269.026959.85251267.9961159.6067265.8945179.5575 265.612
199.5084265.5672229.4346265.0895299.2626 263.261319.2134262.6112329.1888262.6453
358.3043262.0105377.7146260.5744397.1249261.8279406.8301261.8144426.2404261.4961
445.6507261.7433 465.061262.2551474.9283262.3416504.5304262.9092543.9997 263.242
642.6731265.2946652.5404 265.375741.3464267.1218761.0811267.3208790.6832267.8439
820.2852 268.757840.0198269.1492899.2239271.4056978.1625273.7821997.8972 274.532
#Mann= 3 , 0 , 0
       0     .05       0358.3043    .035       0397.1249     .05       0
Bank Sta=358.3043,397.1249
XS Rating Curve= 0 ,0
Exp/Cntr=0.3,0.1

Type RM Length L Ch R = 1 ,24040   ,708,708,708
BEGIN DESCRIPTION:
UNT030 IN ROCK 37.0
END DESCRIPTION:
XS GIS Cut Line= 3
      3638142.09     10170141.63      3638511.28      10170510.5
       3638992.1     10170941.64
#Sta/Elev= 30
  4482.3  271.53  4510.6  271.38  4637.9  268.26  4715.7  265.58  4800.5  263.61
  4842.9  262.22  4864.2  261.03  4941.9  260.48  4991.4   261.3  5001.5  260.02
  5016.4  259.84  5019.2  259.34  5026.9  260.23  5033.6  260.08  5047.8  261.41
  5055.3  262.39  5069.5  262.93  5097.9  262.27  5161.5  263.84  5168.2   264.5
  5175.7  264.26  5182.4  264.77  5189.9  264.41    5225   265.2  5260.5  266.74
  5437.3   272.2  5487.4  273.63  5508.3  273.64  5536.7  275.17    5650  278.99
#Mann= 3 , 0 , 0
  4482.3     .05       0  4991.4    .035       0  5047.8     .05       0
Bank Sta=4991.4,5047.8
XS Rating Curve= 0 ,0
Exp/Cntr=0.3,0.1

Type RM Length L Ch R = 1 ,23332   ,536,536,536
BEGIN DESCRIPTION:
UNT030 IN ROCK 35.0
END DESCRIPTION:
XS GIS Cut Line= 3
      3637734.73     10170371.24      3638195.62     10171001.43
      3638592.14     10171091.65
#Sta/Elev= 30
  4474.4  268.96    4530  268.06  4544.6   267.4  4654.5  264.66  4683.1  263.92
  4745.4  262.72  4772.4  262.66  4801.7  261.51  4851.9   260.6  4895.9  259.25
  4902.1   259.4  4916.8  258.46  4973.2  258.45  4981.6  258.18  4987.8  257.55
  4992.2  256.66    4995  256.16  4998.2  256.66  5023.4  257.75  5031.8  257.97
  5044.8  257.66  5073.5  258.66  5094.4   258.6  5102.9     258  5194.8  259.42
    5245  259.68    5364  262.35  5395.1  263.64  5497.7  265.79  5661.8   270.3
#Mann= 5 ,-1 , 0
  4474.4     .05       0  4654.5     .08       0  4683.1     .05       0
  4992.2     .03       0  4998.2     .05       0
Bank Sta=4992.2,4998.2
XS Rating Curve= 0 ,0
Exp/Cntr=0.3,0.1

Type RM Length L Ch R = 1 ,22796   ,844,844,844
BEGIN DESCRIPTION:
UNT030 IN ROCK 34.0
END DESCRIPTION:
XS GIS Cut Line= 3
      3637442.11     10170291.65      3637815.17     10171277.13
      3638242.08     10171741.61
#Sta/Elev= 30
  4183.4  272.09  4193.1  272.58  4198.5  271.91  4269.9  270.47  4363.4  267.99
  4386.6  268.24  4418.4   266.1  4423.7  266.25    4440  264.75  4503.5  263.82
  4533.7  262.59  4557.6   262.8  4624.2  261.43  4673.8  259.51  4709.3  259.12
  4734.1  258.08  4874.2  256.48  4964.7  256.68  4984.2  256.15    4993  254.73
  4995.8  254.23    4999  254.73  5019.7  256.91  5060.2  255.46  5081.6  256.29
  5177.8  256.84  5209.4   258.1  5294.9  258.86  5669.8  264.66    5868  269.51
#Mann= 4 ,-1 , 0
  4183.4     .08       0  4269.9     .05       0    4993     .03       0
    4999     .05       0
Bank Sta=4993,4999
XS Rating Curve= 0 ,0
Exp/Cntr=0.3,0.1

Type RM Length L Ch R = 1 ,21952   ,571,571,571
BEGIN DESCRIPTION:
UNT030 IN ROCK 33.0
END DESCRIPTION:
XS GIS Cut Line= 3
       3637342.1     10170441.66      3637237.67     10171269.83
      3637413.56     10171786.16
#Sta/Elev= 30
  4514.2  267.72  4524.3   267.8  4594.8  264.84    4615  264.47  4655.3  262.72
  4665.4  262.73  4675.4  262.16    4746  259.99  4806.5  258.49  4856.9  256.72
  4927.4  255.03  4953.2  254.04  4958.2  254.37  4967.7  254.14  4987.9  252.98
    4995  251.58  4997.7  251.08    5001  251.58  5008.1  253.75  5018.1   254.1
  5038.5  253.77  5068.5  253.86  5088.7  253.45  5098.8  253.81  5139.1  253.53
  5300.4  254.93  5330.6  254.51    5372   254.8  5722.6  258.79  5894.4  261.49
#Mann= 3 ,-1 , 0
  4514.2     .05       0    4995     .03       0    5001     .05       0
Bank Sta=4995,5001
XS Rating Curve= 0 ,0
Exp/Cntr=0.3,0.1

Type RM Length L Ch R = 1 ,21381   ,573,573,573
BEGIN DESCRIPTION:
UNT030 IN ROCK 32.0
END DESCRIPTION:
XS GIS Cut Line= 3
      3636927.45     10170362.64      3636798.99     10171196.72
      3636719.25     10171707.31
#Sta/Elev= 30
  4434.2  263.37  4443.3  262.93  4493.9  262.39  4514.1  261.57  4563.8  260.53
  4595.1   259.3  4637.1  258.69  4706.4  256.33  4736.7  256.09  4817.7  254.07
    4848  254.41  4878.4  253.11  4963.2  252.01  4979.6  251.44  4996.8  249.62
  4999.5  249.12  5002.8  249.62    5020  251.98  5026.4  252.13  5080.7  251.99
  5141.4  250.89  5157.9  251.74  5226.1  251.65    5352  252.92  5394.4  252.69
    5526  253.92  5618.3  253.99  5687.9  255.18  5708.2  254.74  5794.9  255.09
#Mann= 3 ,-1 , 0
  4434.2     .05       0  4996.8    .035       0  5002.8     .05       0
Bank Sta=4996.8,5002.8
XS Rating Curve= 0 ,0
Exp/Cntr=0.3,0.1

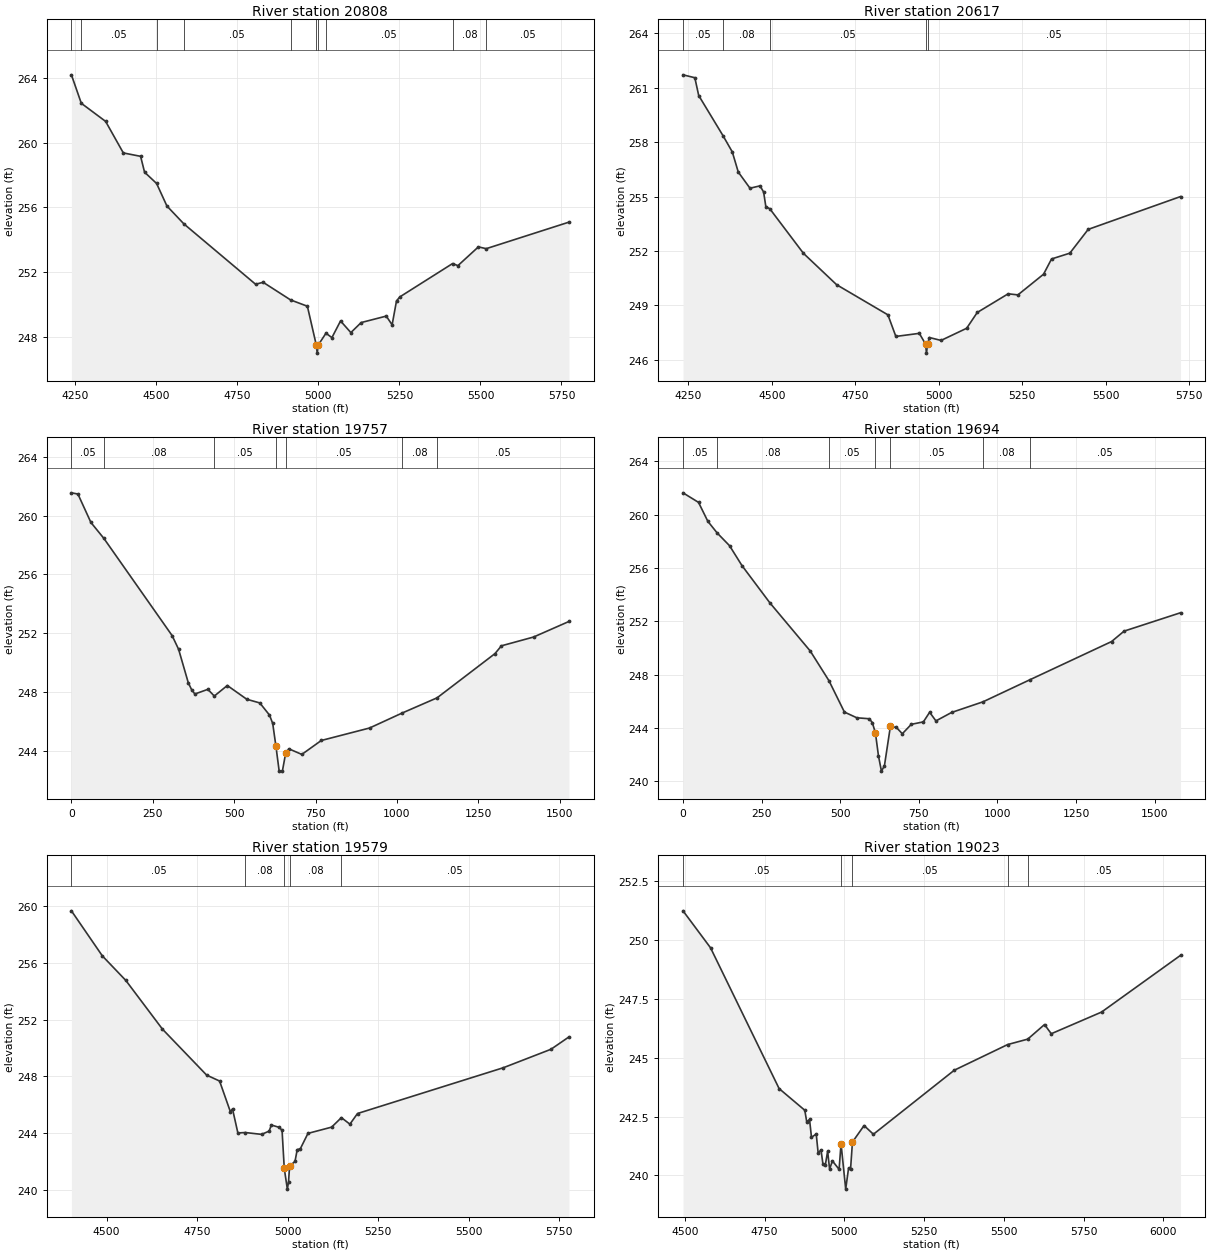
Type RM Length L Ch R = 1 ,20808   ,191,191,191
BEGIN DESCRIPTION:
UNT030 IN ROCK 31.0
END DESCRIPTION:
XS GIS Cut Line= 3
      3636684.41     10170215.01      3636378.83     10170912.62
      3636137.63     10171647.02
#Sta/Elev= 30
  4238.4   264.2  4268.9  262.44  4343.9  261.32  4398.5  259.37  4451.8  259.16
    4464  258.18  4501.2  257.48  4532.9  256.09  4585.4  254.98  4806.4  251.25
  4829.8  251.37  4914.4  250.28  4966.2  249.89  4993.7  247.49  4996.5  246.99
  4999.7  247.49  5023.5  248.22  5041.9  247.95  5068.5  248.98  5100.3  248.26
  5132.1  248.88  5209.5  249.28  5227.6  248.74  5241.1  250.22  5251.6  250.47
  5414.1  252.53  5430.5   252.4  5493.7  253.56  5517.9  253.45    5773  255.09
#Mann= 10 ,-1 , 0
  4238.4     .08       0  4268.9     .05       0  4501.2     .08       0
  4585.4     .05       0  4914.4     .08       0  4993.7     .07       0
  4999.7     .08       0  5023.5     .05       0  5414.1     .08       0
  5517.9     .05       0
Bank Sta=4993.7,4999.7
XS Rating Curve= 0 ,0
Exp/Cntr=0.3,0.1

Type RM Length L Ch R = 1 ,20617   ,860,860,860
BEGIN DESCRIPTION:
UNT030 IN ROCK 30.0
END DESCRIPTION:
XS GIS Cut Line= 3
      3636493.45     10170188.95      3636068.08     10171204.61
      3635929.68     10171567.91
#Sta/Elev= 30
  4234.3  261.71  4269.7  261.55  4281.3  260.57  4354.6  258.34  4381.9  257.46
  4399.8  256.35  4434.9  255.46  4464.9  255.59  4475.7  255.25  4482.4  254.44
  4494.1  254.33    4595  251.87  4694.4  250.14  4847.9  248.48  4871.7  247.29
  4941.9  247.46  4960.6  246.87  4963.4  246.37  4966.6  246.87  4972.3  247.23
    5007  247.07  5083.7  247.74  5115.4  248.61    5208  249.64  5237.2  249.58
    5314  250.72  5337.9  251.56  5392.7  251.88  5447.6  253.19  5724.2     255
#Mann= 5 ,-1 , 0
  4234.3     .05       0  4354.6     .08       0  4494.1     .05       0
  4960.6     .03       0  4966.6     .05       0
Bank Sta=4960.6,4966.6
XS Rating Curve= 0 ,0
Exp/Cntr=0.3,0.1

Type RM Length L Ch R = 1 ,19757   ,63,63,63
XS GIS Cut Line= 5
      3636471.49    10170191.573     3635970.188    10170501.469
     3635892.063    10170496.261     3635785.292     10170552.25
     3635570.448    10171263.188
#Sta/Elev= 30
       0261.545219.95752 261.46359.87255259.532299.78759258.4465309.3415251.8458
 329.299250.9142359.2353248.6266369.2141248.1747379.1928 247.875419.1079248.1915
439.0654247.7369478.9804248.4532 538.853247.5175 578.768247.2688608.5659246.4435
618.4754245.8723628.3849244.3177638.2944242.6349 648.204242.6392658.1135243.8357
 668.023244.1502707.8822243.7708 767.671244.7165916.0388245.56491014.837246.5698
1123.516247.61621301.353250.61991321.113251.14961419.911251.7468 1528.59252.8043
#Mann= 7 ,-1 , 0
       0     .05       099.78759     .08       0439.0654     .05       0
628.3849    .035       0658.1135     .05       01014.837     .08       0
1123.516     .05       0
Bank Sta=628.3849,658.1135
XS Rating Curve= 0 ,0
Exp/Cntr=0.3,0.1

Type RM Length L Ch R = 1 ,19694   ,115,115,115
XS GIS Cut Line= 4
     3636469.102    10170168.989     3635917.019    10170434.614
     3635776.394    10170460.656     3635491.672     10171240.17
#Sta/Elev= 30
       0261.636849.36979260.920678.99166259.5003108.6135258.6267148.1094257.6683
187.6052 256.177276.4708253.3796404.8323249.7686 464.076247.5526513.4458245.1902
552.9417244.7614592.4374244.6889602.3114244.3993612.1854243.6094621.6846241.9196
631.1838240.7599 640.683 241.153659.6814244.1121678.6798 244.038697.6782243.5641
726.1758244.2701764.6495244.4545784.6017245.1758 804.554244.5275854.4344245.1612
954.1953245.95841103.837247.61841363.215250.4789 1403.12251.26191582.689252.6412
#Mann= 7 ,-1 , 0
       0     .05       0108.6135     .08       0 464.076     .05       0
612.1854    .035       0659.6814     .05       0954.1953     .08       0
1103.837     .05       0
Bank Sta=612.1854,659.6814
XS Rating Curve= 0 ,0
Exp/Cntr=0.3,0.1

Type RM Length L Ch R = 1 ,19579   ,556,556,556
BEGIN DESCRIPTION:
UNT030 IN ROCK 29.0
END DESCRIPTION:
XS GIS Cut Line= 3
      3636292.07     10170041.67      3635612.16     10170519.29
      3635408.34     10171022.36
#Sta/Elev= 30
    4403  259.67  4488.5  256.49  4553.3  254.76  4654.3  251.33  4776.3  248.09
  4812.1  247.67  4841.7  245.52  4847.8   245.7  4862.6  244.01  4883.2  244.04
    4928  243.91  4948.9  244.14    4955  244.57  4977.3   244.4  4984.6  244.19
  4990.7  241.51  4999.2  240.05  5002.4  240.55  5005.5  241.69  5020.3     242
  5026.4  242.83  5035.1   242.9  5056.1  243.98  5121.4  244.42  5148.4  245.09
  5171.9  244.63  5192.9  245.38  5595.7  248.61  5727.1  249.91  5776.7  250.78
#Mann= 5 ,-1 , 0
    4403     .05       0  4883.2     .08       0  4990.7     .07       0
  5005.5     .08       0  5148.4     .05       0
Bank Sta=4990.7,5005.5
XS Rating Curve= 0 ,0
Exp/Cntr=0.3,0.1

Type RM Length L Ch R = 1 ,19023   ,858,858,858
BEGIN DESCRIPTION:
UNT030 IN ROCK 28.0
END DESCRIPTION:
XS GIS Cut Line= 3
      3635989.95     10169728.92       3635379.5     10170148.82
      3634942.09     10170841.67
#Sta/Elev= 30
  4493.9  251.24  4580.2  249.67  4795.3  243.69  4875.8  242.77  4881.9  242.28
  4890.7  242.38  4896.8  241.62  4911.7  241.76  4917.8  240.94  4926.6  241.09
  4932.7  240.49  4940.4  240.46  4947.5  241.03  4953.6  240.27  4962.4  240.62
  4983.4  240.26  4989.5  241.35  5004.1  239.42  5013.2  240.32  5019.3  240.26
  5025.3  241.42  5061.7  242.12    5091  241.75  5344.6  244.47    5512  245.56
  5574.9  245.79  5627.6  246.41  5648.8  246.02  5806.5  246.94  6054.2  249.35
#Mann= 5 ,-1 , 0
  4493.9     .05       0  4989.5    .035       0  5025.3     .05       0
    5512     .08       0  5574.9     .05       0
Bank Sta=4989.5,5025.3
XS Rating Curve= 0 ,0
Exp/Cntr=0.3,0.1

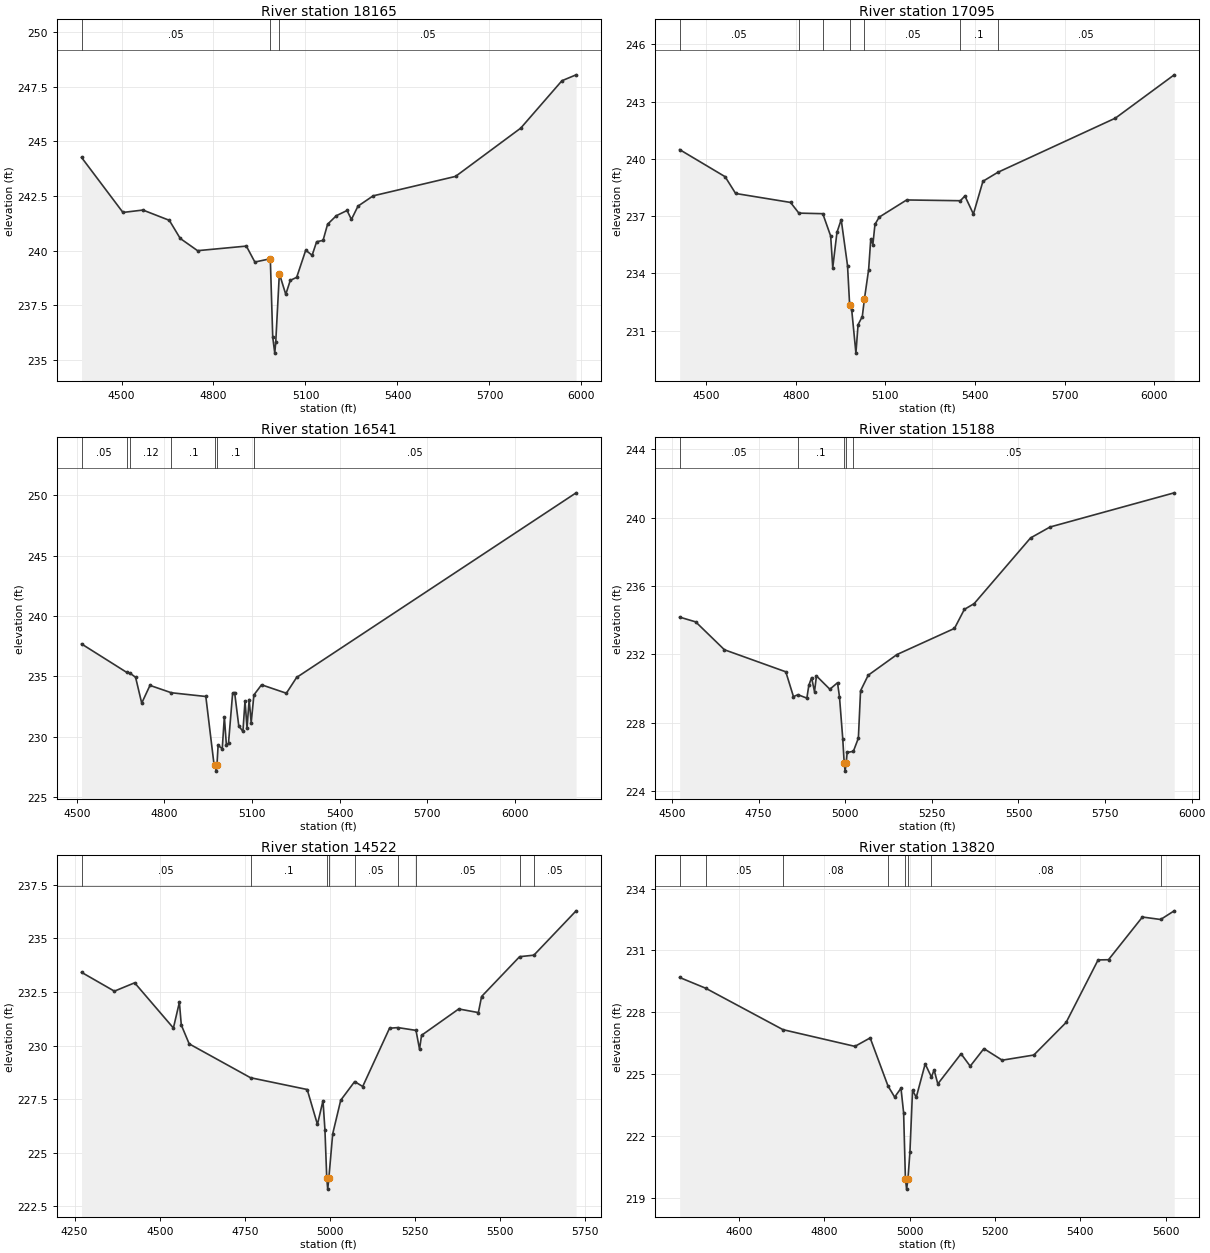
Type RM Length L Ch R = 1 ,18165   ,1070,1070,1070
BEGIN DESCRIPTION:
UNT030 IN ROCK 26.0
END DESCRIPTION:
XS GIS Cut Line= 3
      3635503.83     10169234.14      3635032.55     10169894.18
      3634487.62     10170482.59
#Sta/Elev= 30
  4369.6  244.27  4504.7  241.75  4569.9  241.86  4655.9  241.39  4691.5  240.56
  4748.1     240  4907.2  240.21  4934.9  239.48  4985.3  239.63  4993.2  236.04
  4999.8  235.31    5003  235.81  5014.8  238.95  5035.7     238  5050.4  238.64
  5071.3  238.78  5100.8  240.02  5121.7  239.79  5136.4  240.41  5157.3  240.47
  5172.1  241.21  5200.5   241.6  5235.6  241.84  5249.8  241.43  5271.3  242.04
  5320.7  242.51  5589.4   243.4    5802  245.61  5936.4  247.78  5982.6  248.05
#Mann= 3 , 0 , 0
  4369.6     .05       0  4985.3    .035       0  5014.8     .05       0
Bank Sta=4985.3,5014.8
XS Rating Curve= 0 ,0
Exp/Cntr=0.3,0.1

Type RM Length L Ch R = 1 ,17095   ,554,554,554
BEGIN DESCRIPTION:
UNT030 IN ROCK 25.0
END DESCRIPTION:
XS GIS Cut Line= 3
      3635043.79       10168748.      3634493.54     10169290.92
      3634123.65     10170093.47
#Sta/Elev= 30
  4410.7  240.49    4563  239.07  4598.3  238.19  4782.2  237.72  4810.1  237.16
  4890.2  237.13  4916.6  235.96  4923.6   234.3  4937.7  236.15  4951.9  236.82
  4973.1  234.41  4980.2  232.34  4987.3  232.06  5001.2  229.82  5008.4  231.31
  5022.6  231.74  5029.7  232.66  5043.8   234.2  5050.9   235.8    5058  235.51
    5065  236.57  5079.2  236.95  5171.1  237.85  5351.1  237.81  5366.3  238.06
  5394.7  237.11  5426.7  238.83  5476.7   239.3  5870.4  242.14  6067.4  244.41
#Mann= 7 ,-1 , 0
  4410.7     .05       0  4810.1     .12       0  4890.2     .05       0
  4980.2    .035       0  5029.7     .05       0  5351.1      .1       0
  5476.7     .05       0
Bank Sta=4980.2,5029.7
XS Rating Curve= 0 ,0
Exp/Cntr=0.3,0.1

Type RM Length L Ch R = 1 ,16541   ,1353,1353,1353
BEGIN DESCRIPTION:
UNT030 IN ROCK 24.0
END DESCRIPTION:
XS GIS Cut Line= 3
      3634601.11     10168478.88      3633906.63     10169138.64
      3633464.79     10169727.75
#Sta/Elev= 30
  4515.9  237.68    4670  235.33  4682.4  235.25  4701.1  234.91  4722.1  232.77
  4750.4  234.24  4823.7  233.63  4941.7  233.32  4969.7  227.71  4973.9  227.63
  4976.7  227.13  4979.9  227.63  4983.8  229.26    4998  228.99  5005.2  231.64
  5012.1  229.31  5019.4  229.44  5033.5  233.58  5040.4  233.65  5054.6  230.88
  5068.8  230.42    5076  232.96  5082.9  230.72  5090.2  233.07  5097.1  231.14
  5106.5  233.45  5132.6  234.29  5217.6  233.59  5252.8   234.9  6210.2  250.21
#Mann= 7 ,-1 , 0
  4515.9     .05       0    4670      .1       0  4682.4     .12       0
  4823.7      .1       0  4973.9     .07       0  4979.9      .1       0
  5106.5     .05       0
Bank Sta=4973.9,4979.9
XS Rating Curve= 0 ,0
Exp/Cntr=0.3,0.1

Type RM Length L Ch R = 1 ,15188   ,666,666,666
BEGIN DESCRIPTION:
UNT030 IN ROCK 23.0
END DESCRIPTION:
XS GIS Cut Line= 3
      3634210.41     10168166.43      3633565.21     10168500.08
       3633090.9     10169016.84
#Sta/Elev= 30
  4521.9  234.18  4568.3   233.9  4651.2  232.27  4828.4  230.98  4850.5  229.53
  4863.4  229.64  4889.2  229.44  4894.8  230.18  4902.8  230.64  4911.3  229.82
  4916.9  230.74  4955.6  229.96  4977.7  230.34  4983.4  229.51  4992.8  227.07
  4996.9  225.67  4999.6  225.17  5002.9  225.67  5005.5  226.26  5023.5  226.33
  5037.9   227.1  5044.2  229.87  5066.3  230.78  5149.3  231.99  5315.4  233.52
  5343.8  234.63  5372.2  234.97  5534.9  238.81  5591.1  239.45  5949.7  241.45
#Mann= 5 ,-1 , 0
  4521.9     .05       0  4863.4      .1       0  4996.9     .07       0
  5002.9      .1       0  5023.5     .05       0
Bank Sta=4996.9,5002.9
XS Rating Curve= 0 ,0
Exp/Cntr=0.3,0.1

Type RM Length L Ch R = 1 ,14522   ,702,702,702
BEGIN DESCRIPTION:
UNT030 IN ROCK 22.0
END DESCRIPTION:
XS GIS Cut Line= 3
      3634184.44     10167636.88      3633521.69     10167933.68
       3632908.4     10168322.64
#Sta/Elev= 30
  4270.3  233.42  4366.8  232.54  4426.3  232.93  4540.1  230.82  4557.7  232.02
  4563.3  230.96  4586.5  230.08  4766.6   228.5    4933  227.95  4963.1  226.32
  4979.4  227.43  4985.1  226.07  4990.5   223.8  4993.3   223.3  4996.5   223.8
  5007.9  225.88  5031.5  227.45  5072.4  228.32    5096  228.09  5174.8  230.81
  5199.3  230.84  5252.5  230.71  5262.9  229.83  5268.8  230.48  5378.1  231.71
  5435.7  231.54  5445.1  232.29  5556.8  234.15  5598.7  234.22  5722.7  236.29
#Mann= 9 ,-1 , 0
  4270.3     .05       0  4766.6      .1       0  4990.5     .07       0
  4996.5      .1       0  5072.4     .05       0  5199.3      .1       0
  5252.5     .05       0  5556.8     .08       0  5598.7     .05       0
Bank Sta=4990.5,4996.5
XS Rating Curve= 0 ,0
Exp/Cntr=0.3,0.1

Type RM Length L Ch R = 1 ,13820   ,143,143,143
BEGIN DESCRIPTION:
UNT030 IN ROCK 21.0
END DESCRIPTION:
XS GIS Cut Line= 5
      3633691.47     10167383.93       3633508.6     10167318.09
      3633287.31     10167314.44      3633126.36     10167427.83
       3632931.3     10167938.26
#Sta/Elev= 30
    4461  229.69  4521.9  229.17  4703.2  227.16  4871.8  226.35  4907.5  226.76
  4949.3  224.43  4964.9  223.89  4979.7  224.32  4985.9  223.13  4990.1  219.93
  4992.9  219.43  4996.1  219.93  5000.7  221.24  5006.8  224.22  5015.5  223.88
  5036.4   225.5  5051.1  224.86  5057.3  225.21    5066  224.53  5120.5  225.99
  5141.9  225.39    5174  226.24  5216.9  225.68    5291  225.93  5366.7  227.51
  5441.6  230.54    5466  230.55  5545.5  232.62  5588.1   232.5    5620  232.92
#Mann= 8 ,-1 , 0
    4461     .08       0  4521.9     .05       0  4703.2     .08       0
  4949.3      .1       0  4990.1     .07       0  4996.1      .1       0
  5051.1     .08       0  5588.1     .05       0
Bank Sta=4990.1,4996.1
XS Rating Curve= 0 ,0
Exp/Cntr=0.3,0.1

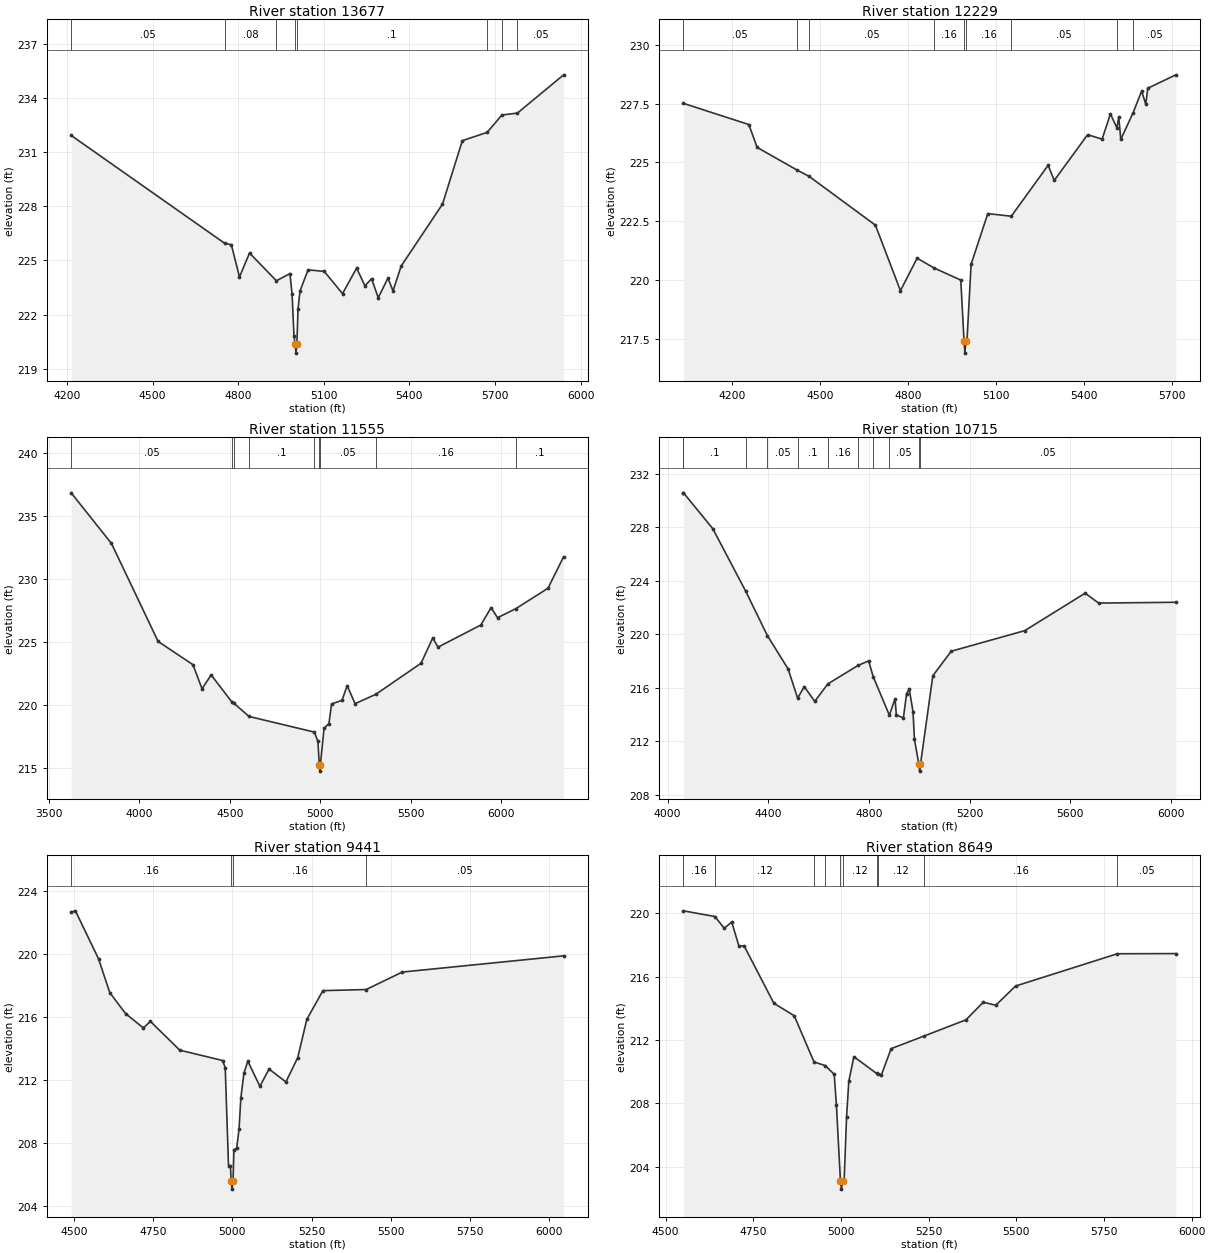
Type RM Length L Ch R = 1 ,13677   ,1448,1448,1448
BEGIN DESCRIPTION:
UNT030 IN ROCK 20.0
END DESCRIPTION:
XS GIS Cut Line= 4
      3633812.18     10167085.83      3633312.91     10167074.85
      3632930.67     10167431.48      3632643.54     10168073.43
#Sta/Elev= 30
  4214.9  231.93  4752.7  225.95  4776.2  225.87  4804.6  224.08  4839.8  225.41
  4934.1  223.87  4981.4  224.27  4988.8  223.16  4995.6  220.83  4999.6  220.36
  5002.4  219.86  5005.6  220.36  5009.8  222.31  5016.6   223.3  5044.9  224.48
  5101.6  224.39  5165.6  223.16    5215  224.57  5244.3  223.59  5267.5  223.99
  5290.7  222.93  5324.9  224.02  5342.5  223.31  5371.2  224.69  5515.9  228.12
  5585.5  231.64  5672.6   232.1  5723.8  233.06  5778.5  233.17  5940.3  235.29
#Mann= 8 ,-1 , 0
  4214.9     .05       0  4752.7     .08       0  4934.1      .1       0
  4999.6     .07       0  5005.6      .1       0  5672.6     .05       0
  5723.8      .1       0  5778.5     .05       0
Bank Sta=4999.6,5005.6
XS Rating Curve= 0 ,0
Exp/Cntr=0.3,0.1

Type RM Length L Ch R = 1 ,12229   ,674,674,674
BEGIN DESCRIPTION:
UNT030 IN ROCK 18.0
END DESCRIPTION:
XS GIS Cut Line= 3
      3633203.47     10166117.84      3632759.12     10166545.15
      3632048.98     10167333.09
#Sta/Elev= 30
  4034.9  227.51  4257.9  226.61  4286.2  225.64  4421.8  224.68  4463.3  224.41
    4689  222.34  4774.2  219.56    4831  220.94  4889.3  220.52  4979.7  220.01
  4990.9  217.41  4993.7  216.91  4996.9  217.41  5000.7  217.41  5014.9  220.68
  5071.7  222.83  5151.7  222.72  5277.2  224.88  5298.1  224.24  5411.7  226.18
    5461  225.99  5489.4  227.06  5511.4  226.47  5517.8  226.94  5524.6  225.98
  5566.6  227.11  5595.6  228.03  5609.8  227.47  5616.5  228.15  5712.1  228.72
#Mann= 9 ,-1 , 0
  4034.9     .05       0  4421.8     .08       0  4463.3     .05       0
  4889.3     .16       0  4990.9     .07       0  4996.9     .16       0
  5151.7     .05       0  5511.4     .16       0  5566.6     .05       0
Bank Sta=4990.9,4996.9
XS Rating Curve= 0 ,0
Exp/Cntr=0.3,0.1

Type RM Length L Ch R = 1 ,11555   ,840,840,840
BEGIN DESCRIPTION:
UNT030 IN ROCK 17.0
END DESCRIPTION:
XS GIS Cut Line= 3
       3633142.1     10165141.65      3632342.11     10166241.64
       3631542.1     10167341.66
#Sta/Elev= 30
  3623.5  236.82  3846.1  232.81  4103.8  225.05  4296.2  223.21  4346.5   221.3
  4396.7   222.4  4512.2  220.24    4523  220.15    4606  219.11  4967.1  217.87
  4986.7  217.13  4994.2  215.28  4996.9  214.78  5000.2  215.28  5020.3  218.16
  5047.4  218.55  5062.1   220.1  5119.7  220.39  5147.9  221.55  5191.9  220.12
    5307  220.87  5555.9  223.32  5620.8  225.32  5650.2   224.6  5886.3  226.35
  5943.1  227.73  5978.6  226.93  6079.1  227.64  6257.2  229.26  6343.8  231.76
#Mann= 9 ,-1 , 0
  3623.5     .05       0  4512.2      .1       0    4523     .05       0
    4606      .1       0  4967.1     .05       0  4994.2     .03       0
  5000.2     .05       0    5307     .16       0  6079.1      .1       0
Bank Sta=4994.2,5000.2
XS Rating Curve= 0 ,0
Exp/Cntr=0.3,0.1

Type RM Length L Ch R = 1 ,10715   ,1274,1274,1274
BEGIN DESCRIPTION:
UNT030 IN ROCK 15.0
END DESCRIPTION:
XS GIS Cut Line= 3
      3632691.32     10164998.05      3632239.96     10165588.29
      3631076.92     10165935.47
#Sta/Elev= 30
  4062.7  230.56  4063.2  230.56  4179.6  227.88  4310.6   223.2  4396.5  219.89
  4478.8   217.4  4516.7  215.22  4543.2  216.07  4584.8  214.97  4636.8  216.28
    4757  217.66  4798.8     218    4817  216.82  4881.3  213.94  4903.8  215.17
    4909  213.97  4936.9  213.73  4949.6  215.55    4960  215.92  4975.2  214.21
  4980.9  212.13  4998.8  210.26  5001.5  209.76  5004.8  210.26    5054  216.89
    5127  218.72  5419.2  220.26  5659.3  223.06  5712.8  222.32  6019.5  222.38
#Mann= 11 ,-1 , 0
  4062.7     .05       0  4063.2      .1       0  4310.6     .16       0
  4396.5     .05       0  4516.7      .1       0  4636.8     .16       0
    4757      .1       0    4817     .12       0  4881.3     .05       0
  4998.8    .035       0  5004.8     .05       0
Bank Sta=4998.8,5004.8
XS Rating Curve= 0 ,0
Exp/Cntr=0.3,0.1

Type RM Length L Ch R = 1 ,9441    ,792,792,792
BEGIN DESCRIPTION:
UNT030 IN ROCK 14.0
END DESCRIPTION:
XS GIS Cut Line= 3
      3632242.07     10164591.67      3631842.11     10164891.64
      3630911.81     10165388.65
#Sta/Elev= 30
  4491.2  222.67  4504.7  222.75  4577.6   219.7    4613  217.56    4663  216.22
  4719.3  215.31  4741.2  215.73  4833.9   213.9  4969.3  213.24  4977.6  212.78
    4988  206.56    4994  206.56  4996.3  205.57  4999.1  205.07  5002.3  205.57
    5005  207.57  5013.8  207.67  5021.2  208.89  5026.9  210.86  5036.5  212.42
  5048.9   213.2  5087.1   211.6  5115.9   212.7  5169.2  211.88  5206.6  213.43
  5235.1  215.85  5285.9  217.68  5422.5  217.75  5536.7  218.86  6045.9  219.89
#Mann= 4 ,-1 , 0
  4491.2     .16       0  4996.3     .07       0  5002.3     .16       0
  5422.5     .05       0
Bank Sta=4996.3,5002.3
XS Rating Curve= 0 ,0
Exp/Cntr=0.3,0.1

Type RM Length L Ch R = 1 ,8649    ,1108,1108,1108
BEGIN DESCRIPTION:
UNT030 IN ROCK 12.0
END DESCRIPTION:
XS GIS Cut Line= 3
      3631823.27     10163999.77      3631458.71      10164468.5
      3630868.44     10165024.05
#Sta/Elev= 30
  4550.5  220.15  4640.6  219.79  4666.9  219.05  4688.4  219.44  4709.2  217.91
  4723.7  217.94  4808.7  214.31  4866.6  213.53  4923.1  210.61  4954.8  210.38
  4980.7  209.83    4987  207.88  4998.5  203.08  5001.2  202.58  5004.5  203.08
  5008.9  203.08  5015.9  207.13  5022.3  209.39  5036.8  210.94  5101.8  209.88
  5105.1  209.87  5115.5  209.81  5143.1  211.45  5237.4  212.25  5356.5  213.27
  5405.8  214.38  5441.5  214.19  5497.7   215.4  5788.1  217.44  5954.9  217.45
#Mann= 10 ,-1 , 0
  4550.5     .16       0  4640.6     .12       0  4923.1     .16       0
  4954.8     .12       0  4998.5     .07       0  5004.5     .12       0
  5101.8     .16       0  5105.1     .12       0  5237.4     .16       0
  5788.1     .05       0
Bank Sta=4998.5,5004.5
XS Rating Curve= 0 ,0
Exp/Cntr=0.3,0.1

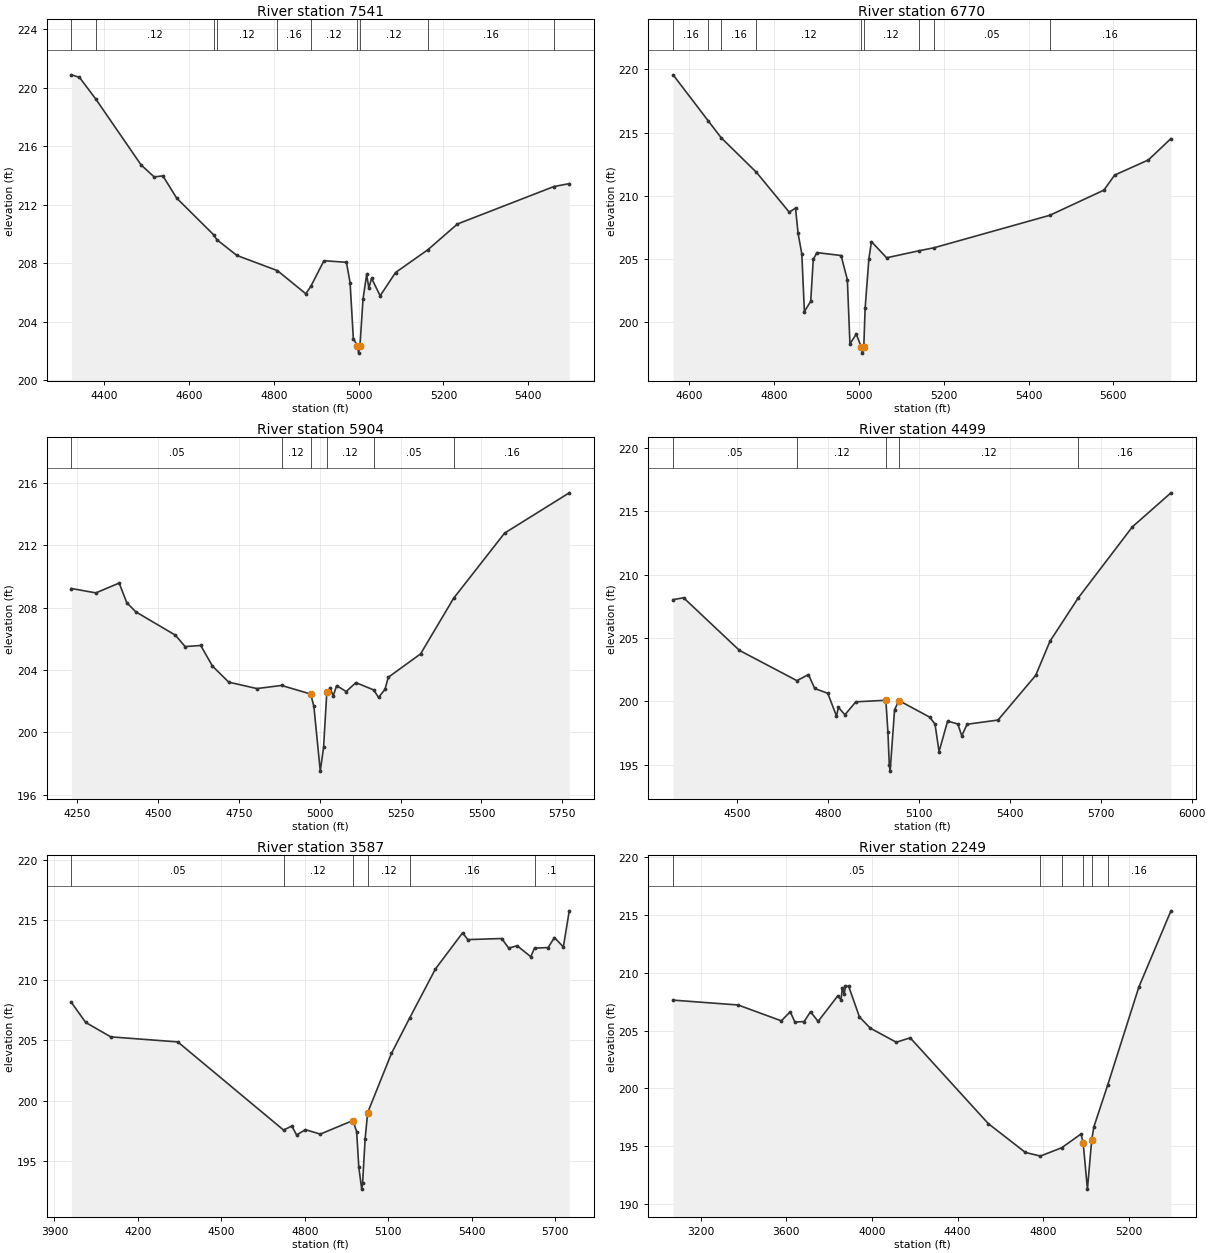
Type RM Length L Ch R = 1 ,7541    ,771,771,771
BEGIN DESCRIPTION:
UNT030 IN ROCK 10.0
END DESCRIPTION:
XS GIS Cut Line= 3
      3630992.11      10163491.6      3630842.11     10164141.64
      3630764.27      10164642.1
#Sta/Elev= 30
  4322.9   220.9  4341.8  220.73  4380.4  219.24  4487.1  214.74  4517.9  213.92
  4538.5  213.99    4571  212.47  4657.9  209.97  4665.7  209.63  4712.9  208.55
  4808.6  207.51  4875.4  205.93  4887.3  206.44  4918.2  208.19  4971.2  208.08
  4979.8  206.69  4987.5  202.86  4997.1  202.37  4999.9  201.87  5003.1  202.37
  5010.3  205.57  5018.9  207.25    5024  206.32  5030.5  206.99  5050.7  205.79
  5086.9  207.38  5163.6  208.95  5232.9   210.7  5460.2  213.26  5496.5  213.46
#Mann= 10 ,-1 , 0
  4322.9     .16       0  4380.4     .12       0  4657.9     .16       0
  4665.7     .12       0  4808.6     .16       0  4887.3     .12       0
  4997.1     .07       0  5003.1     .12       0  5163.6     .16       0
  5460.2      .1       0
Bank Sta=4997.1,5003.1
XS Rating Curve= 0 ,0
Exp/Cntr=0.3,0.1

Type RM Length L Ch R = 1 ,6770    ,866,866,866
BEGIN DESCRIPTION:
UNT030 IN ROCK 9.0
END DESCRIPTION:
XS GIS Cut Line= 3
      3630772.92     10163331.38      3630321.56     10163982.39
      3630192.12      10164341.6
#Sta/Elev= 30
  4561.9  219.57  4644.7  215.93  4675.1   214.6  4758.4  211.86  4835.7  208.71
  4850.6  209.03  4856.6  207.03  4865.4  205.41  4871.5  200.85  4886.4  201.66
  4892.4  204.98  4901.2  205.51    4958  205.28  4972.8  203.37  4978.9  198.29
  4993.8  199.06  5005.6  198.06  5008.4  197.56  5011.6  198.06  5014.7   201.1
  5023.5  204.99  5029.6  206.38  5065.4   205.1  5140.8  205.65  5176.8  205.89
  5450.1  208.46  5577.8  210.45  5603.1  211.64  5682.8  212.84  5735.9  214.53
#Mann= 9 ,-1 , 0
  4561.9     .16       0  4644.7     .12       0  4675.1     .16       0
  4758.4     .12       0  5005.6     .07       0  5011.6     .12       0
  5140.8      .1       0  5176.8     .05       0  5450.1     .16       0
Bank Sta=5005.6,5011.6
XS Rating Curve= 0 ,0
Exp/Cntr=0.3,0.1

Type RM Length L Ch R = 1 ,5904    ,1405,1405,1405
BEGIN DESCRIPTION:
UNT030 IN ROCK 7.0
END DESCRIPTION:
XS GIS Cut Line= 3
      3630156.64     10162749.72      3629835.45     10163227.18
      3629842.11     10164191.61
#Sta/Elev= 30
  4231.7  209.22  4307.4  208.94  4379.4  209.57  4402.7  208.32  4430.4  207.73
  4553.4  206.23  4583.3   205.5  4631.7  205.57  4667.9  204.25  4718.4  203.22
  4805.3  202.81  4881.6  203.01  4971.6  202.46  4981.6  201.68  5001.4  197.52
  5011.6  199.04  5021.6  202.56  5031.6  202.82  5041.6  202.35    5052     203
  5081.6  202.62  5111.6  203.19  5166.9  202.72  5181.6  202.24  5201.6  202.76
  5211.6  203.53  5311.6  205.03  5413.7  208.59  5571.6  212.77  5771.6  215.35
#Mann= 6 ,-1 , 0
  4231.7     .05       0  4881.6     .12       0  4971.6     .07       0
  5021.6     .12       0  5166.9     .05       0  5413.7     .16       0
Bank Sta=4971.6,5021.6
XS Rating Curve= 0 ,0
Exp/Cntr=0.3,0.1

Type RM Length L Ch R = 1 ,4499    ,912,912,912
BEGIN DESCRIPTION:
Mapping XS f01c01f2
END DESCRIPTION:
XS GIS Cut Line= 3
      3629561.59     10162572.84      3628957.42      10163065.9
      3628118.54     10163271.76
#Sta/Elev= 30
    4288  208.03  4322.6  208.18  4506.8  204.03  4696.8  201.64  4734.8  202.12
  4755.6  201.02  4798.7  200.64  4827.4  198.85  4833.8  199.53  4855.3  198.95
  4891.3  199.97  4990.4  200.09  4997.2  197.59  5001.7     195  5004.5   194.5
  5019.1  199.34  5033.4  200.07  5135.1  198.76  5152.7  198.21    5166  196.04
  5194.3  198.45  5227.8  198.22    5241  197.29  5258.6   198.2  5360.6  198.53
  5485.2  202.06    5532  204.74    5625  208.15  5804.4  213.78  5931.6  216.46
#Mann= 5 ,-1 , 0
    4288     .05       0  4696.8     .12       0  4990.4     .07       0
  5033.4     .12       0    5625     .16       0
Bank Sta=4990.4,5033.4
XS Rating Curve= 0 ,0
Exp/Cntr=0.3,0.1

Type RM Length L Ch R = 1 ,3587    ,1338,1338,1338
BEGIN DESCRIPTION:
UNT030 IN ROCK 6.0
END DESCRIPTION:
XS GIS Cut Line= 3
      3629512.98     10162558.96      3628802.46     10162619.54
      3627792.11     10162991.64
#Sta/Elev= 30
  3960.9  208.16    4012   206.5  4102.3   205.3  4343.2  204.88  4723.4  197.56
  4753.4  197.89  4770.3  197.15  4802.3  197.59  4855.5  197.22  4972.8  198.35
  4986.3  197.42  4994.1  194.46  5004.5  192.65  5007.7  193.15  5016.8  196.84
    5026  199.01  5111.3  203.92  5176.5  206.85  5269.5  210.94  5367.1  213.94
    5386  213.38  5507.8  213.47    5533  212.67  5563.4  212.87  5612.2  211.96
  5625.9  212.67  5674.6  212.72  5697.4  213.55  5729.4  212.77  5750.7  215.77
#Mann= 6 ,-1 , 0
  3960.9     .05       0  4723.4     .12       0  4972.8     .07       0
    5026     .12       0  5176.5     .16       0  5625.9      .1       0
Bank Sta=4972.8,5026
XS Rating Curve= 0 ,0
Exp/Cntr=0.3,0.1

Type RM Length L Ch R = 1 ,2249    ,680,680,680
BEGIN DESCRIPTION:
UNT030 IN ROCK 5.0
END DESCRIPTION:
XS GIS Cut Line= 3
      3629965.69      10162602.2      3628637.53       10161656.
      3627942.12     10161641.64
#Sta/Elev= 30
  3070.6  207.64  3374.5  207.22  3576.1  205.85  3617.9  206.63  3639.8  205.74
  3683.1  205.79  3712.6  206.64  3748.2   205.8  3840.4  208.02  3855.2  207.66
  3861.3  208.68    3870  208.16  3876.1  208.84  3890.9  208.84  3941.3  206.19
  3991.7  205.22  4113.4     204  4178.5  204.38  4543.7  196.96  4716.8  194.47
  4787.1  194.16  4886.8  194.88  4976.8  196.07  4986.8  195.29  5006.6   191.3
  5026.8  195.58  5036.8  196.69  5100.7  200.26  5246.9  208.77  5396.9  215.36
#Mann= 6 ,-1 , 0
  3070.6     .05       0  4787.1     .12       0  4886.8     .05       0
  4986.8     .04       0  5026.8     .05       0  5100.7     .16       0
Bank Sta=4986.8,5026.8
XS Rating Curve= 0 ,0
Exp/Cntr=0.3,0.1