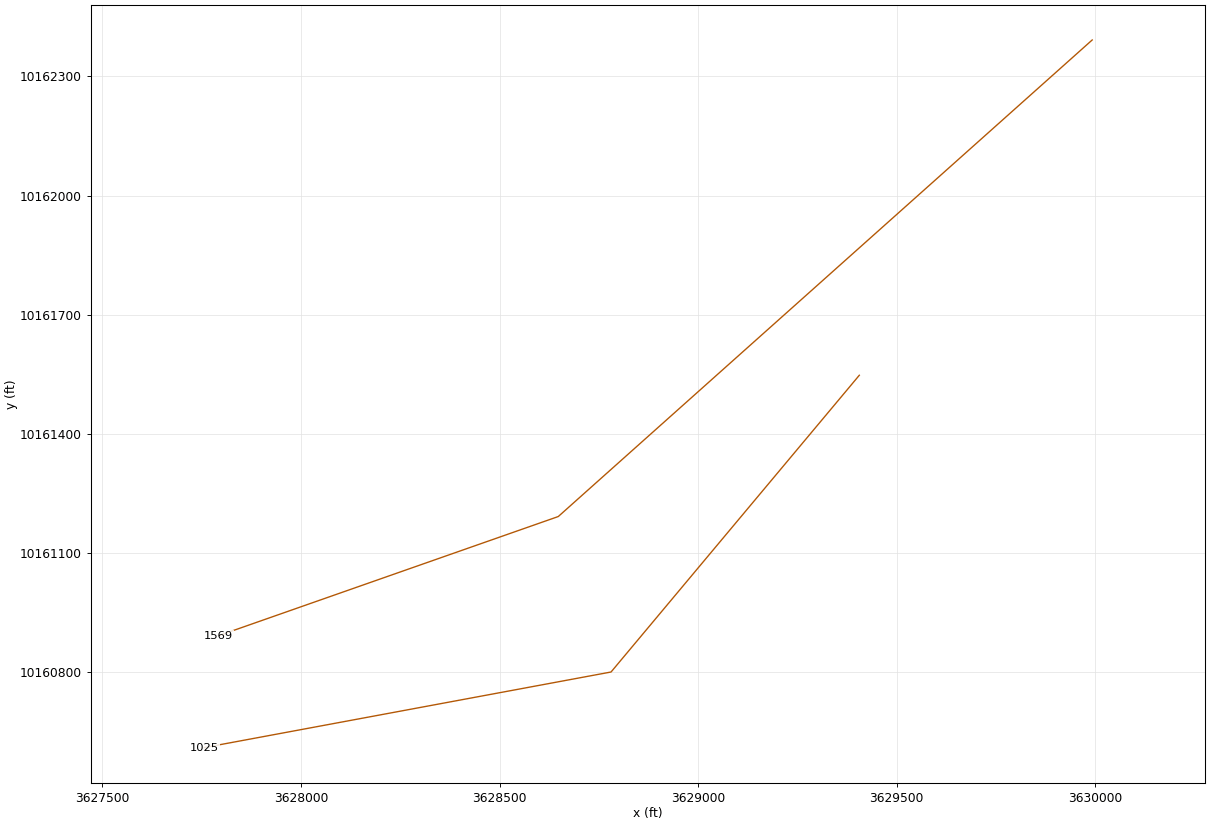
HEC-RAS study UNT030 IN ROCK.prj: UNT030 IN ROCK Base Level Engineering

--- UNT030 IN ROCK.g01 (geometry) --- (continued)

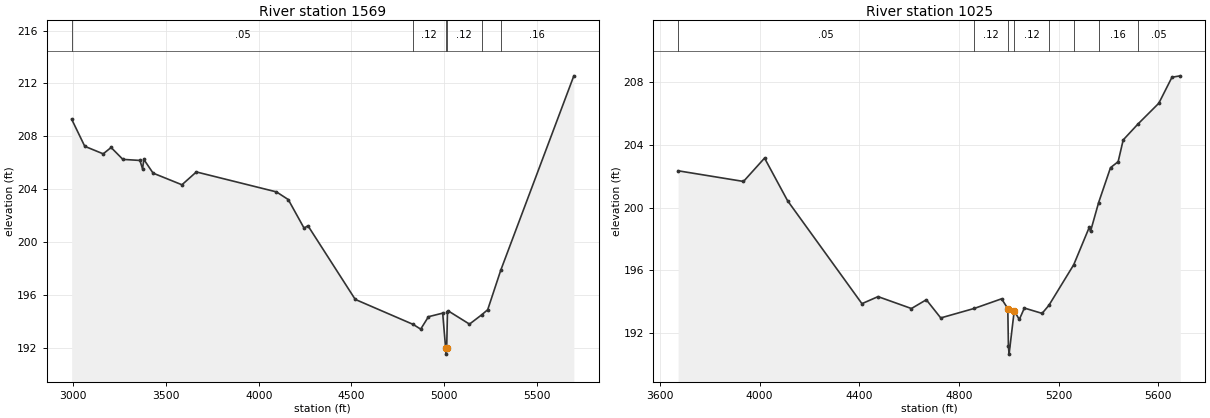
Type RM Length L Ch R = 1 ,1569    ,544,544,544
BEGIN DESCRIPTION:
UNT030 IN ROCK 3.0
END DESCRIPTION:
XS GIS Cut Line= 3
      3629992.12     10162391.66      3628647.79     10161191.75
      3627792.14     10160891.65
#Sta/Elev= 30
  2990.9   209.3  3061.6  207.25  3161.1  206.68  3203.7  207.16  3267.2  206.26
  3359.2  206.18  3373.4  205.54  3380.1  206.26  3430.2  205.22  3585.8  204.34
  3663.5  205.31  4095.7   203.8  4159.3  203.22  4244.5  201.06  4265.5  201.24
  4520.4  195.67  4832.6  193.78  4873.5  193.42  4915.4  194.36  4992.2  194.63
  5007.8  192.03  5010.6  191.53  5013.8  192.03    5018  194.71  5023.2  194.79
  5136.7   193.8  5202.3   194.5    5235  194.89  5305.5  197.88  5699.6  212.58
#Mann= 6 ,-1 , 0
  2990.9     .05       0  4832.6     .12       0  5007.8     .07       0
  5013.8     .12       0  5202.3     .05       0  5305.5     .16       0
Bank Sta=5007.8,5013.8
XS Rating Curve= 0 ,0
Exp/Cntr=0.3,0.1

Type RM Length L Ch R = 1 ,1025    ,0,0,0
BEGIN DESCRIPTION:
UNT030 IN ROCK 1.0
END DESCRIPTION:
XS GIS Cut Line= 3
      3629405.76     10161547.49      3628780.67     10160800.33
      3627756.76     10160610.05
#Sta/Elev= 30
  3672.7  202.36  3935.1  201.68  4019.6  203.17    4112  200.45  4410.5  193.88
  4475.1  194.33  4609.1  193.57  4668.9  194.13  4726.8  192.97  4862.1  193.58
  4970.9  194.19  4995.9  193.57  4998.4  191.16  5001.1  190.66  5021.7  193.42
  5042.1  192.87  5062.4   193.6  5133.6  193.26  5161.1  193.78  5260.7  196.37
  5322.8  198.75  5327.9  198.49  5360.4  200.33  5408.2  202.56  5438.8  202.94
  5459.1  204.33  5518.7  205.35    5602  206.67  5654.8  208.33  5688.3  208.42
#Mann= 8 ,-1 , 0
  3672.7     .05       0  4862.1     .12       0  4995.9     .07       0
  5021.7     .12       0  5161.1     .16       0  5260.7     .05       0
  5360.4     .16       0  5518.7     .05       0
Bank Sta=4995.9,5021.7
XS Rating Curve= 0 ,0
Exp/Cntr=0.3,0.1

Chan Stop Cuts=-1
Use User Specified Reach Order=0
Composite Channel Slope=5