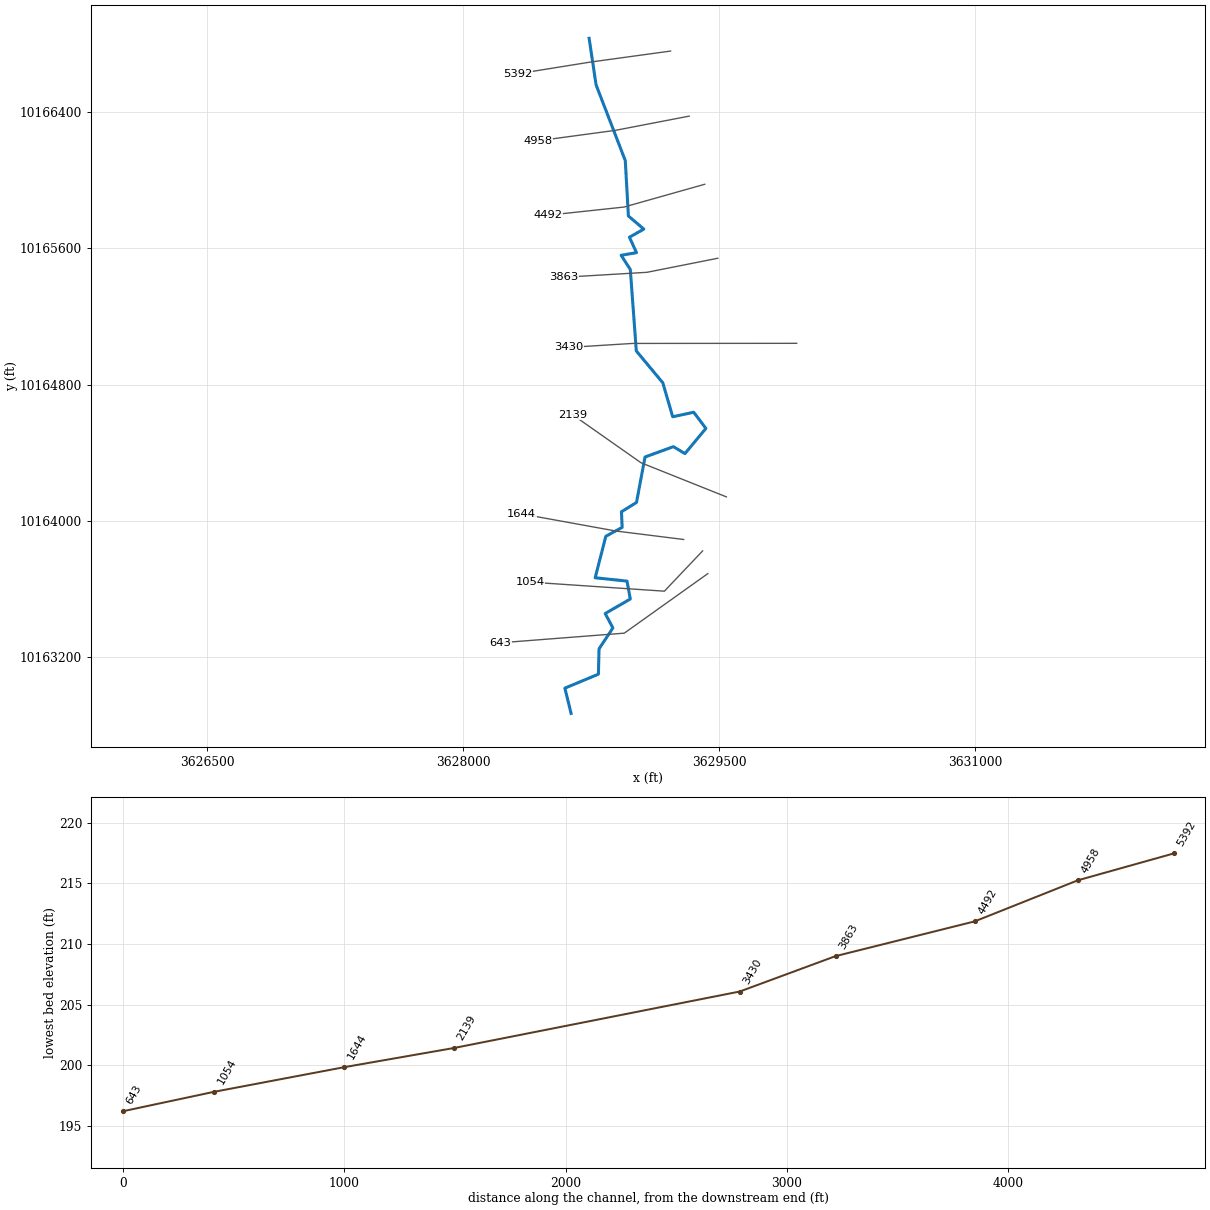
--- UNT031 IN ROCK.prj (project) ---

Proj Title=UNT031 IN ROCK Base Level Engineering
Current Plan=p01
Default Exp/Contr=0.3,0.1
English Units
Geom File=g01
Flow File=f01
Plan File=p01
BEGIN DESCRIPTION:
UNT031 IN ROCK
END DESCRIPTION:

--- UNT031 IN ROCK.p01 (plan) ---

Plan Title=Multiple Run
Short Identifier=Multiple
Geom File=g01
Flow File=f01
Subcritical Flow
K Sum by GR= 0
Std Step Tol= 0.01
Critical Tol= 0.01
Num of Std Step Trials= 20
Max Error Tol= 0.3
Flow Tol Ratio= 0.001
Split Flow NTrial= 30
Split Flow Tol= 0.02
Split Flow Ratio= 0.02
Log Output Level= 0
Friction Slope Method= 1
Unsteady Friction Slope Method= 2
Unsteady Bridges Friction Slope Method= 1
Parabolic Critical Depth
Global Vel Dist=  1 , 1 , 1
Global Log Level= 0
CheckData=True
Encroach Param= -1, 0, 0, 0
BEGIN DESCRIPTION:
Multiple Run
END DESCRIPTION:

--- UNT031 IN ROCK.f01 (steady flow) ---

Flow Title=Multiple
Number of Profiles=7
Profile Names=10-year,25-year,50-year,1pct_min,100-year,1pct_plu,500-year
River Rch & RM= UNT031 IN ROCK,Reach-1,5392
     417     546     648     565     764    1034    1062
Boundary for River Rch & Prof#=UNT031 IN ROCK,Reach-1,1
Up Type=0
Dn Type=3
Dn Slope=0.005
Boundary for River Rch & Prof#=UNT031 IN ROCK,Reach-1,2
Up Type=0
Dn Type=3
Dn Slope=0.005
Boundary for River Rch & Prof#=UNT031 IN ROCK,Reach-1,3
Up Type=0
Dn Type=3
Dn Slope=0.005
Boundary for River Rch & Prof#=UNT031 IN ROCK,Reach-1,4
Up Type=0
Dn Type=3
Dn Slope=0.005
Boundary for River Rch & Prof#=UNT031 IN ROCK,Reach-1,5
Up Type=0
Dn Type=3
Dn Slope=0.005
Boundary for River Rch & Prof#=UNT031 IN ROCK,Reach-1,6
Up Type=0
Dn Type=3
Dn Slope=0.005
Boundary for River Rch & Prof#=UNT031 IN ROCK,Reach-1,7
Up Type=0
Dn Type=3
Dn Slope=0.005

--- UNT031 IN ROCK.g01 (geometry) ---

Geom Title=Existing Conditions

River Reach=UNT031 IN ROCK,Reach-1
Reach XY= 30
      3628737.85     10166831.33      3628778.64     10166558.48
      3628949.78     10166114.22      3628968.00     10165789.57
      3629058.28     10165712.31      3628974.08     10165664.57
      3629015.75     10165574.29      3628925.47     10165558.67
      3628979.23     10165475.57      3629014.45     10164997.53
      3629169.67     10164810.85      3629227.75     10164611.52
      3629350.65     10164638.04      3629422.25     10164543.10
      3629299.52     10164395.35      3629232.02     10164436.15
      3629065.38     10164375.45      3629015.50     10164109.05
      3628927.23     10164053.96      3628931.48     10163962.74
      3628835.66     10163910.26      3628773.40     10163667.13
      3628959.97     10163647.55      3628979.20     10163542.44
      3628832.12     10163457.22      3628877.23     10163372.72
      3628796.06     10163250.35      3628792.26     10163101.57
      3628595.77     10163019.54      3628632.11     10162871.64

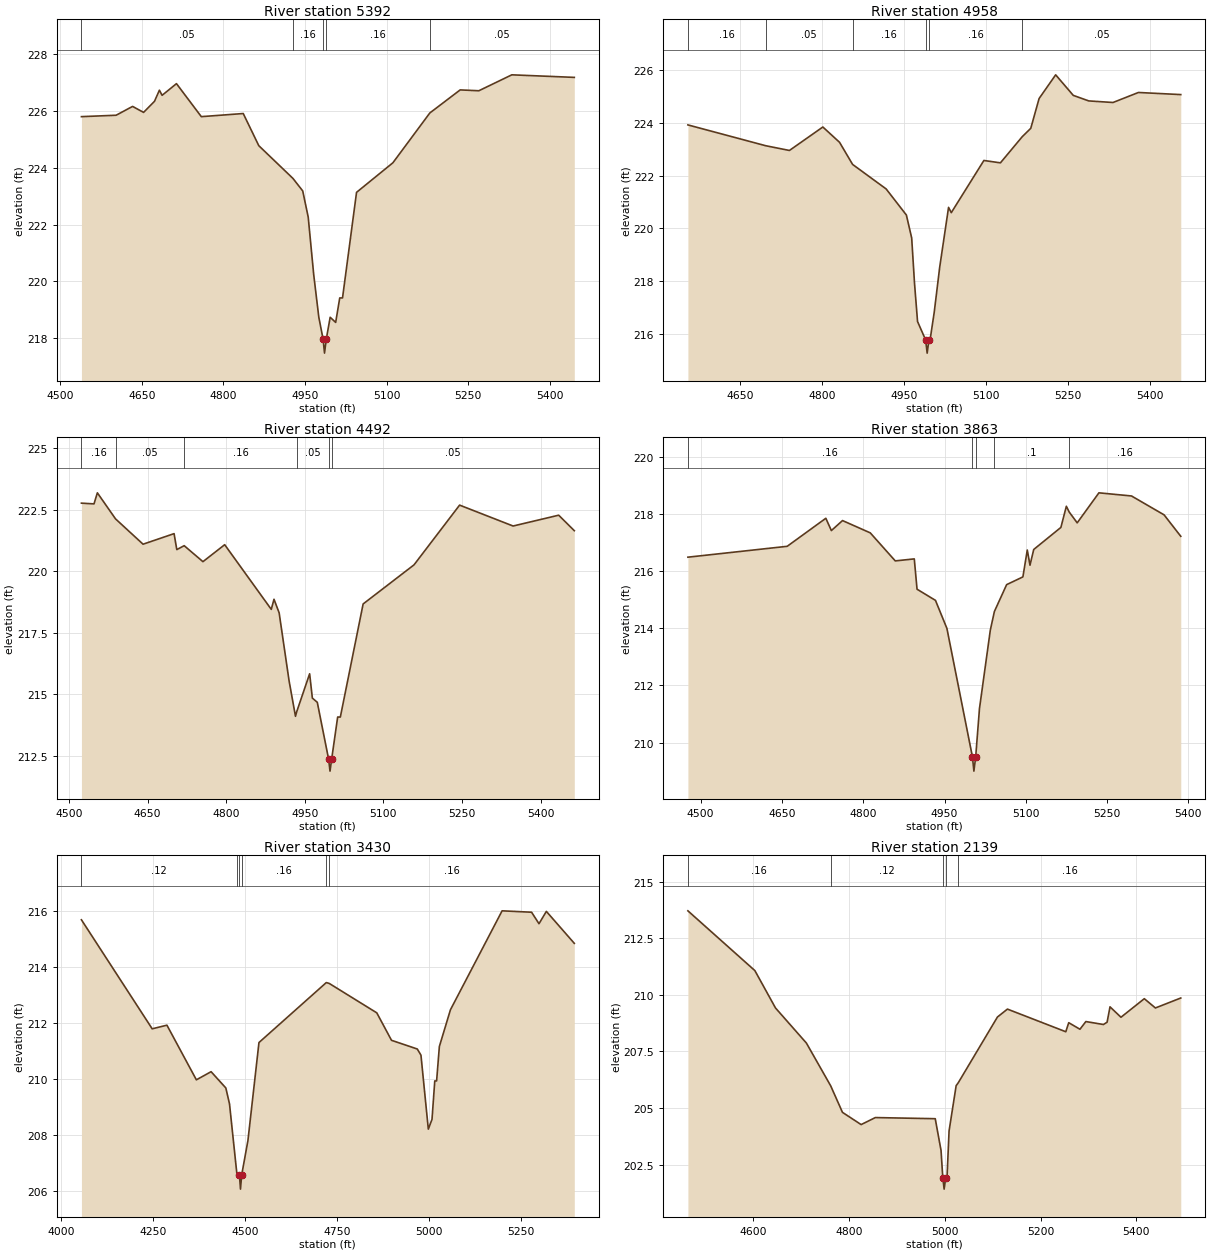
Type RM Length L Ch R = 1,5392,434,434,434
BEGIN DESCRIPTION:
UNT031 IN ROCK 9.0
END DESCRIPTION:
XS GIS Cut Line= 3
      3629215.30     10166756.71      3628742.11     10166691.64
      3628318.71     10166623.43
#Sta/Elev= 30
  4538.8  225.79  4602.6  225.84  4632.9  226.15  4653.1  225.94  4673.2  226.33
  4682.2  226.72  4687.2  226.54  4713.6  226.95  4759.3  225.79  4836.4  225.90
  4865.0  224.77  4927.8  223.62  4945.8  223.18  4955.9  222.26  4966.0  220.24
  4975.4  218.74  4983.2  217.98  4985.9  217.48  4989.2  217.98  4996.3  218.74
  5006.4  218.56  5013.9  219.42  5019.0  219.42  5044.8  223.13  5111.7  224.17
  5179.6  225.92  5235.4  226.73  5269.7  226.70  5330.4  227.26  5445.3  227.17
#Mann=5,-1,0
  4538.8    0.05       0  4927.8    0.16       0  4983.2    0.07       0
  4989.2    0.16       0  5179.6    0.05       0
Bank Sta=4983.2,4989.2
Exp/Cntr=0.3,0.1

Type RM Length L Ch R = 1,4958,466,466,466
BEGIN DESCRIPTION:
UNT031 IN ROCK 8.0
END DESCRIPTION:
XS GIS Cut Line= 3
      3629324.30     10166375.05      3628892.11     10166291.64
      3628435.43     10166229.89
#Sta/Elev= 30
  4554.9  223.92  4697.1  223.13  4740.5  222.95  4801.6  223.84  4832.1  223.26
  4856.0  222.42  4917.3  221.49  4954.3  220.50  4964.0  219.63  4969.1  217.93
  4974.7  216.46  4989.5  215.76  4992.3  215.26  4995.5  215.76  4997.6  215.76
  5005.2  216.81  5015.2  218.52  5031.4  220.79  5036.4  220.59  5096.0  222.57
  5126.2  222.48  5166.0  223.47  5181.7  223.79  5196.9  224.92  5227.2  225.82
  5259.4  225.04  5287.7  224.83  5332.0  224.77  5378.5  225.15  5455.9  225.07
#Mann=6,-1,0
  4554.9    0.16       0  4697.1    0.05       0  4856.0    0.16       0
  4989.5    0.07       0  4995.5    0.16       0  5166.0    0.05       0
Bank Sta=4989.5,4995.5
Exp/Cntr=0.3,0.1

Type RM Length L Ch R = 1,4492,629,629,629
BEGIN DESCRIPTION:
UNT031 IN ROCK 7.0
END DESCRIPTION:
XS GIS Cut Line= 3
      3629415.24     10165975.24      3628942.11     10165841.64
      3628495.71     10165793.64
#Sta/Elev= 30
  4523.8  222.77  4547.8  222.74  4554.2  223.19  4588.9  222.13  4641.4  221.10
  4700.6  221.53  4705.8  220.88  4719.9  221.04  4755.7  220.39  4797.2  221.08
  4886.1  218.45  4891.3  218.86  4901.1  218.31  4920.1  215.54  4932.3  214.10
  4934.7  214.29  4959.3  215.83  4964.5  214.84  4973.9  214.67  4995.4  212.37
  4998.2  211.87  5001.4  212.37  5012.8  214.07  5017.9  214.07  5061.4  218.67
  5158.5  220.26  5245.5  222.69  5347.6  221.84  5434.6  222.28  5464.4  221.65
#Mann=6,-1,0
  4523.8    0.16       0  4588.9    0.05       0  4719.9    0.16       0
  4934.7    0.05       0  4995.4   0.035       0  5001.4    0.05       0
Bank Sta=4995.4,5001.4
Exp/Cntr=0.3,0.1

Type RM Length L Ch R = 1,3863,433,433,433
BEGIN DESCRIPTION:
UNT031 IN ROCK 6.0
END DESCRIPTION:
XS GIS Cut Line= 3
      3629491.77     10165541.28      3629076.96     10165458.89
      3628591.33     10165430.02
#Sta/Elev= 30
  4476.5  216.48  4659.7  216.86  4731.0  217.84  4741.2  217.41  4761.8  217.76
  4813.0  217.33  4859.1  216.35  4894.2  216.42  4899.3  215.36  4933.3  214.97
  4954.4  213.99  5001.5  209.50  5004.2  209.00  5007.5  209.50  5014.5  211.19
  5034.5  213.93  5042.0  214.58  5064.6  215.52  5094.6  215.79  5102.7  216.73
  5107.7  216.20  5114.6  216.75  5164.7  217.52  5174.8  218.26  5180.0  218.06
  5194.8  217.68  5234.9  218.73  5295.0  218.62  5355.1  217.96  5385.9  217.21
#Mann=5,-1,0
  4476.5    0.16       0  5001.5    0.07       0  5007.5    0.16       0
  5042.0     0.1       0  5180.0    0.16       0
Bank Sta=5001.5,5007.5
Exp/Cntr=0.3,0.1

Type RM Length L Ch R = 1,3430,1291,1291,1291
BEGIN DESCRIPTION:
UNT031 IN ROCK 5.0
END DESCRIPTION:
XS GIS Cut Line= 3
      3629954.31     10165042.31      3628992.11     10165041.64
      3628616.35     10165018.13
#Sta/Elev= 30
  4056.1  215.69  4248.3  211.80  4288.3  211.93  4368.3  209.98  4408.3  210.27
  4448.3  209.69  4458.3  209.12  4478.2  206.64  4485.3  206.58  4488.1  206.08
  4491.3  206.58  4508.3  207.81  4538.3  211.31  4721.2  213.45  4729.1  213.42
  4858.3  212.37  4898.3  211.39  4968.3  211.08  4978.3  210.86  4998.3  208.22
  5008.3  208.57  5015.8  209.94  5020.8  209.94  5028.3  211.17  5058.4  212.48
  5198.7  216.01  5278.8  215.96  5298.9  215.55  5318.9  215.99  5394.8  214.85
#Mann=6,-1,0
  4056.1    0.12       0  4478.2    0.16       0  4485.3    0.07       0
  4491.3    0.16       0  4721.2    0.12       0  4729.1    0.16       0
Bank Sta=4485.3,4491.3
Exp/Cntr=0.3,0.1

Type RM Length L Ch R = 1,2139,495,495,495
BEGIN DESCRIPTION:
UNT031 IN ROCK 4.0
END DESCRIPTION:
XS GIS Cut Line= 3
      3629542.10     10164141.64      3629042.11     10164341.64
      3628639.79     10164624.31
#Sta/Elev= 30
  4462.9  213.71  4602.9  211.07  4646.0  209.42  4710.6  207.87  4761.4  205.98
  4786.0  204.81  4825.0  204.27  4854.7  204.58  4979.9  204.53  4992.0  203.13
  4995.7  201.92  4998.5  201.42  5001.7  201.92  5004.5  201.92  5008.8  203.99
  5023.6  205.99  5028.1  206.12  5109.9  209.02  5130.8  209.37  5252.8  208.37
  5258.9  208.77  5282.4  208.48  5294.7  208.82  5331.4  208.69  5339.1  208.79
  5345.2  209.47  5368.1  209.01  5416.9  209.83  5440.1  209.42  5493.1  209.86
#Mann=5,-1,0
  4462.9    0.16       0  4761.4    0.12       0  4995.7    0.07       0
  5001.7    0.12       0  5028.1    0.16       0
Bank Sta=4995.7,5001.7
Exp/Cntr=0.3,0.1

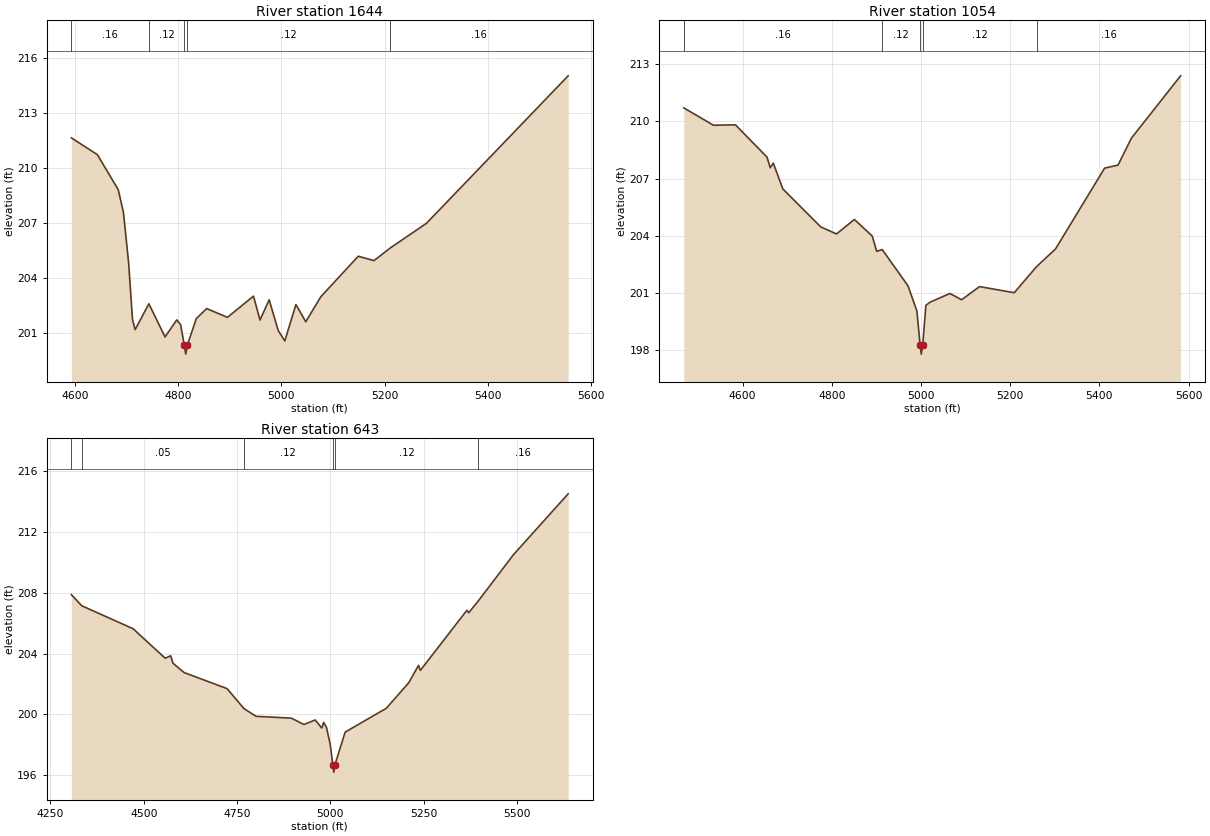
Type RM Length L Ch R = 1,1644,590,590,590
BEGIN DESCRIPTION:
UNT031 IN ROCK 3.0
END DESCRIPTION:
XS GIS Cut Line= 3
      3629292.11     10163891.64      3628892.11     10163941.64
      3628342.14     10164041.64
#Sta/Elev= 30
  4593.4  211.66  4643.8  210.74  4684.1  208.83  4694.2  207.59  4704.3  204.82
  4711.8  201.73  4716.9  201.18  4743.5  202.59  4774.8  200.78  4797.5  201.71
  4805.0  201.44  4812.1  200.34  4814.9  199.84  4818.1  200.34  4835.3  201.78
  4855.4  202.33  4895.7  201.85  4946.1  203.01  4958.7  201.70  4976.4  202.81
  4994.0  201.13  5006.7  200.56  5028.3  202.55  5047.3  201.61  5076.6  202.98
  5149.0  205.19  5179.5  204.95  5210.4  205.63  5281.1  206.99  5555.5  215.05
#Mann=5,-1,0
  4593.4    0.16       0  4743.5    0.12       0  4812.1    0.07       0
  4818.1    0.12       0  5210.4    0.16       0
Bank Sta=4812.1,4818.1
Exp/Cntr=0.3,0.1

Type RM Length L Ch R = 1,1054,411,411,411
BEGIN DESCRIPTION:
UNT031 IN ROCK 2.0
END DESCRIPTION:
XS GIS Cut Line= 3
      3629403.08     10163824.67      3629178.94     10163588.41
      3628392.10     10163641.64
#Sta/Elev= 30
  4467.9  210.71  4534.4  209.80  4583.8  209.82  4654.5  208.13  4661.8  207.57
  4668.7  207.81  4690.1  206.46  4775.1  204.47  4810.4  204.10  4850.5  204.86
  4890.6  203.99  4900.6  203.19  4913.1  203.28  4970.8  201.38  4990.8  200.06
  4997.9  198.30  5000.6  197.80  5003.9  198.30  5010.9  200.36  5020.9  200.53
  5064.9  200.98  5091.1  200.65  5131.2  201.34  5209.1  201.02  5259.3  202.39
  5301.6  203.31  5411.8  207.55  5441.9  207.71  5471.9  209.12  5582.2  212.39
#Mann=5,-1,0
  4467.9    0.16       0  4913.1    0.12       0  4997.9    0.07       0
  5003.9    0.12       0  5259.3    0.16       0
Bank Sta=4997.9,5003.9
Exp/Cntr=0.3,0.1

Type RM Length L Ch R = 1,643,0,0,0
BEGIN DESCRIPTION:
UNT031 IN ROCK 1.0
END DESCRIPTION:
XS GIS Cut Line= 3
      3629433.36     10163691.39      3628943.95     10163342.26
      3628216.44     10163285.57
#Sta/Elev= 30
  4306.2  207.87  4334.0  207.14  4471.5  205.63  4557.5  203.69  4572.3  203.85
  4578.4  203.36  4607.9  202.75  4723.4  201.69  4768.5  200.38  4800.9  199.87
  4895.5  199.75  4929.3  199.33  4959.4  199.63  4977.0  199.10  4982.1  199.47
  4989.5  199.15  4999.5  198.05  5006.5  196.70  5009.3  196.20  5012.5  196.70
  5039.6  198.83  5150.0  200.40  5210.1  202.08  5236.2  203.22  5241.2  202.89
  5365.7  206.84  5370.7  206.68  5396.8  207.47  5490.3  210.49  5637.1  214.50
#Mann=6,-1,0
  4306.2    0.16       0  4334.0    0.05       0  4768.5    0.12       0
  5006.5    0.07       0  5012.5    0.12       0  5396.8    0.16       0
Bank Sta=5006.5,5012.5
Exp/Cntr=0.3,0.1

Chan Stop Cuts=-1