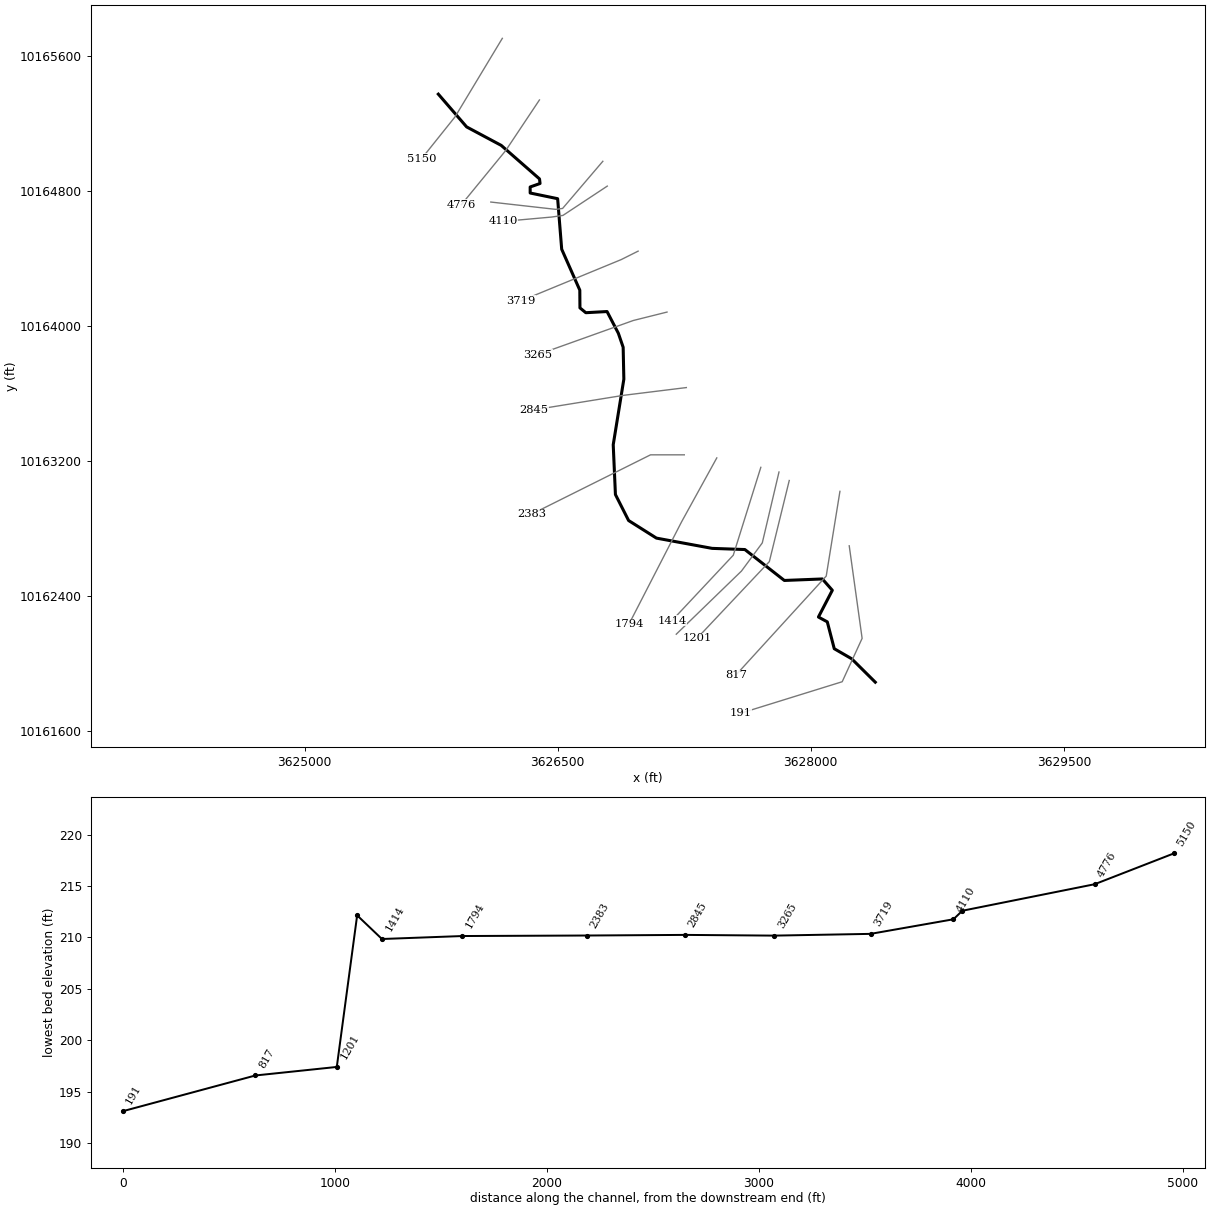
--- UNT032 IN ROCK.prj (project) ---

Proj Title=UNT032 IN ROCK Base Level Engineering
Current Plan=p01
Default Exp/Contr=0.3,0.1
English Units
Geom File=g01
Flow File=f01
Plan File=p01
BEGIN DESCRIPTION:
UNT032 IN ROCK
END DESCRIPTION:

--- UNT032 IN ROCK.p01 (plan) ---

Plan Title=Multiple Run
Short Identifier=Multiple
Geom File=g01
Flow File=f01
Subcritical Flow
K Sum by GR= 0
Std Step Tol= 0.01
Critical Tol= 0.01
Num of Std Step Trials= 20
Max Error Tol= 0.3
Flow Tol Ratio= 0.001
Split Flow NTrial= 30
Split Flow Tol= 0.02
Split Flow Ratio= 0.02
Log Output Level= 0
Friction Slope Method= 1
Unsteady Friction Slope Method= 2
Unsteady Bridges Friction Slope Method= 1
Parabolic Critical Depth
Global Vel Dist=  1 , 1 , 1
Global Log Level= 0
CheckData=True
Encroach Param= -1, 0, 0, 0
BEGIN DESCRIPTION:
Multiple Run
END DESCRIPTION:

--- UNT032 IN ROCK.f01 (steady flow) ---

Flow Title=Multiple
Number of Profiles=7
Profile Names=10-year,25-year,50-year,1pct_min,100-year,1pct_plu,500-year
River Rch & RM= UNT032 IN ROCK,Reach-1,5150
     309     396     463     398     538     727     726
Boundary for River Rch & Prof#=UNT032 IN ROCK,Reach-1,1
Up Type=0
Dn Type=3
Dn Slope=0.005
Boundary for River Rch & Prof#=UNT032 IN ROCK,Reach-1,2
Up Type=0
Dn Type=3
Dn Slope=0.005
Boundary for River Rch & Prof#=UNT032 IN ROCK,Reach-1,3
Up Type=0
Dn Type=3
Dn Slope=0.005
Boundary for River Rch & Prof#=UNT032 IN ROCK,Reach-1,4
Up Type=0
Dn Type=3
Dn Slope=0.005
Boundary for River Rch & Prof#=UNT032 IN ROCK,Reach-1,5
Up Type=0
Dn Type=3
Dn Slope=0.005
Boundary for River Rch & Prof#=UNT032 IN ROCK,Reach-1,6
Up Type=0
Dn Type=3
Dn Slope=0.005
Boundary for River Rch & Prof#=UNT032 IN ROCK,Reach-1,7
Up Type=0
Dn Type=3
Dn Slope=0.005

--- UNT032 IN ROCK.g01 (geometry) ---

Geom Title=Existing Conditions

River Reach=UNT032 IN ROCK,Reach-1
Reach XY= 30
      3625792.97     10165376.03      3625960.66     10165181.96
      3626165.74     10165072.36      3626392.52     10164873.80
      3626395.78     10164846.67      3626337.18     10164826.05
      3626337.18     10164790.25      3626499.94     10164756.61
      3626523.99     10164457.13      3626631.27     10164214.66
      3626632.14     10164109.62      3626666.86     10164080.98
      3626792.73     10164087.92      3626859.57     10163959.45
      3626888.21     10163876.12      3626892.27     10163687.18
      3626829.34     10163298.72      3626842.36     10163003.58
      3626920.48     10162849.50      3627085.41     10162745.34
      3627415.27     10162684.57      3627609.50     10162677.63
      3627843.26     10162494.43      3628068.59     10162503.32
      3628127.62     10162436.29      3628045.21     10162277.64
      3628097.73     10162249.15      3628139.04     10162090.00
      3628242.23     10162030.40      3628382.11     10161891.64

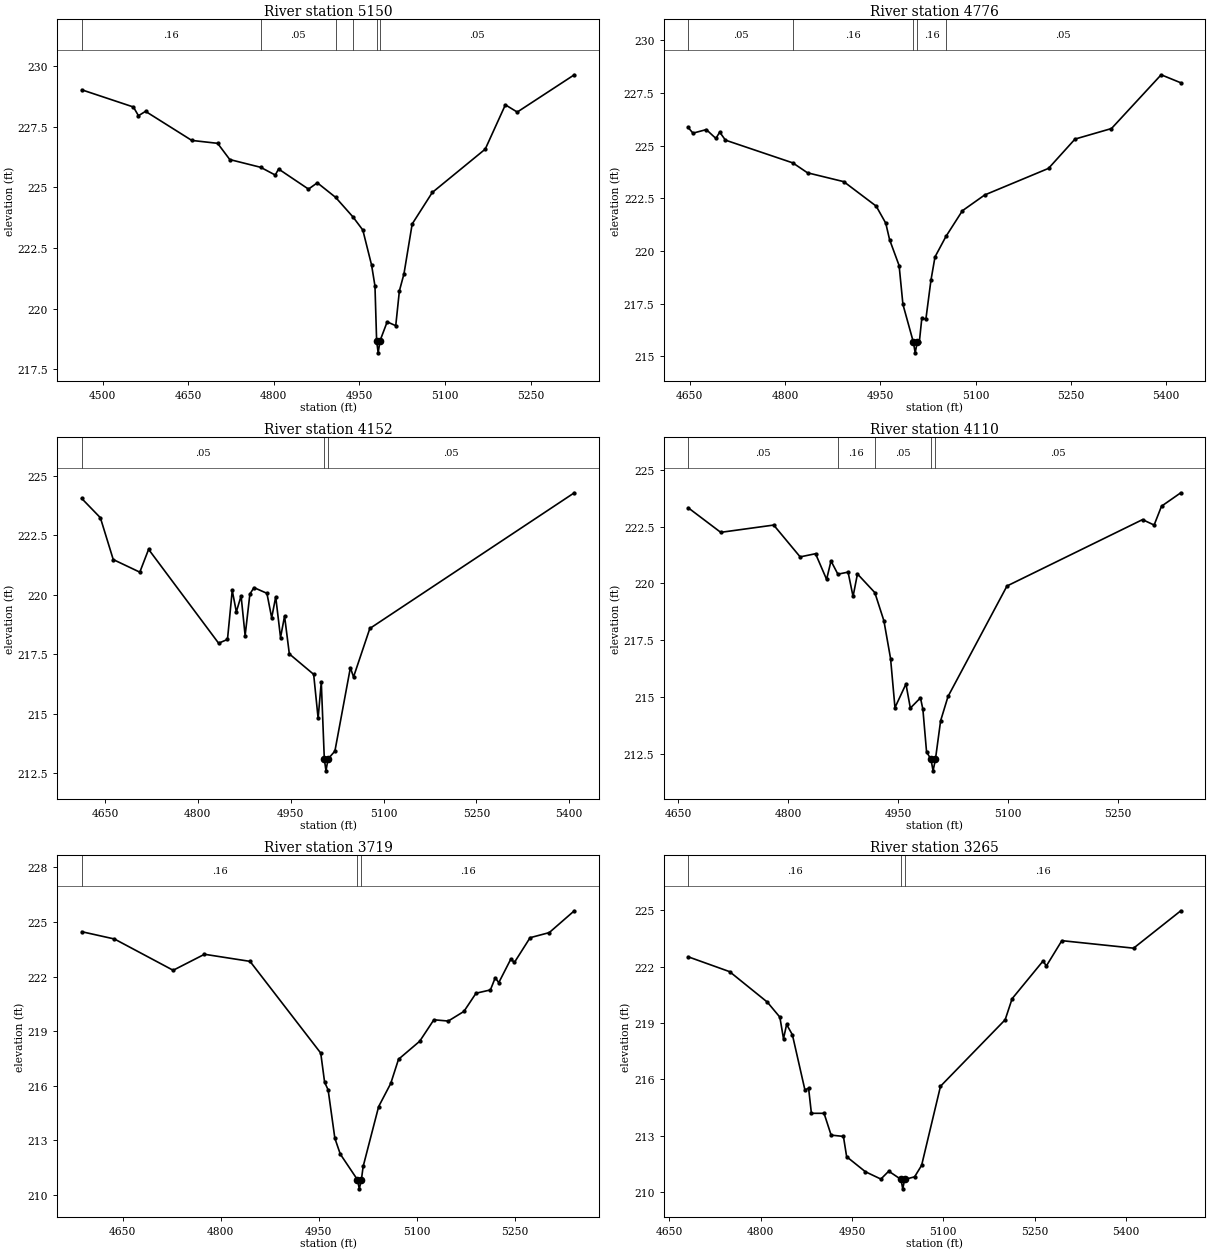
Type RM Length L Ch R = 1,5150,374,374,374
BEGIN DESCRIPTION:
UNT032 IN ROCK 11.0
END DESCRIPTION:
XS GIS Cut Line= 3
      3626172.19     10165706.79      3625892.11     10165241.64
      3625692.12     10164991.66
#Sta/Elev= 30
  4463.5  229.03  4554.0  228.32  4562.9  227.96  4575.3  228.14  4656.3  226.94
  4701.6  226.82  4722.9  226.15  4777.0  225.83  4802.6  225.51  4808.4  225.76
  4860.8  224.93  4876.3  225.19  4908.3  224.59  4938.8  223.78  4956.0  223.24
  4971.4  221.79  4977.3  220.93  4980.2  218.67  4982.9  218.17  4986.2  218.67
  4998.7  219.45  5013.7  219.29  5020.1  220.73  5028.1  221.43  5042.5  223.49
  5077.7  224.79  5170.5  226.58  5205.8  228.41  5226.6  228.11  5326.6  229.65
#Mann=6,-1,0
  4463.5    0.16       0  4777.0    0.05       0  4908.3    0.16       0
  4938.8    0.05       0  4980.2   0.035       0  4986.2    0.05       0
Bank Sta=4980.2,4986.2
Exp/Cntr=0.3,0.1

Type RM Length L Ch R = 1,4776,624,624,624
BEGIN DESCRIPTION:
UNT032 IN ROCK 10.0
END DESCRIPTION:
XS GIS Cut Line= 3
      3626392.10     10165341.63      3626192.11     10165041.64
      3625929.18     10164720.75
#Sta/Elev= 30
  4647.5  225.86  4655.0  225.59  4676.0  225.76  4691.1  225.34  4697.1  225.64
  4706.1  225.26  4812.2  224.18  4835.3  223.71  4892.4  223.29  4943.4  222.13
  4958.5  221.32  4964.5  220.54  4979.5  219.31  4985.5  217.47  5002.0  215.67
  5004.8  215.17  5008.0  215.67  5011.3  215.67  5015.2  216.80  5021.7  216.78
  5029.6  218.61  5036.0  219.72  5053.2  220.69  5079.1  221.91  5114.3  222.66
  5214.7  223.92  5256.4  225.31  5313.8  225.81  5392.0  228.36  5422.9  227.98
#Mann=5,-1,0
  4647.5    0.05       0  4812.2    0.16       0  5002.0    0.07       0
  5008.0    0.16       0  5053.2    0.05       0
Bank Sta=5002,5008
Exp/Cntr=0.3,0.1

Type RM Length L Ch R = 1,4152,42,42,42
BEGIN DESCRIPTION:
Mapping XS 8bed4f8f
END DESCRIPTION:
XS GIS Cut Line= 4
      3626767.75     10164978.22      3626529.37     10164698.82
      3626488.14     10164693.40      3626103.84     10164736.75
#Sta/Elev= 30
  4612.5  224.05  4642.6  223.24  4663.4  221.48  4706.3  220.95  4720.5  221.91
  4833.6  217.96  4847.9  218.12  4855.6  220.18  4862.2  219.28  4869.9  219.95
  4876.4  218.28  4884.1  220.03  4890.7  220.30  4911.6  220.06  4919.3  219.03
  4925.8  219.91  4933.6  218.20  4940.1  219.10  4947.8  217.51  4987.1  216.65
  4994.3  214.80  4999.4  216.33  5004.3  213.09  5007.0  212.59  5010.3  213.09
  5021.4  213.42  5046.4  216.93  5051.5  216.54  5077.8  218.58  5408.1  224.29
#Mann=3,-1,0
  4612.5    0.05       0  5004.3   0.035       0  5010.3    0.05       0
Bank Sta=5004.3,5010.3
Exp/Cntr=0.3,0.1

Type RM Length L Ch R = 1,4110,391,391,391
BEGIN DESCRIPTION:
UNT032 IN ROCK 9.0
END DESCRIPTION:
XS GIS Cut Line= 4
      3626794.10     10164831.18      3626531.54     10164657.59
      3626464.27     10164647.82      3626175.87     10164621.90
#Sta/Elev= 30
  4663.8  223.33  4708.2  222.25  4780.5  222.57  4816.6  221.17  4837.6  221.31
  4852.7  220.18  4858.7  220.99  4868.1  220.41  4882.0  220.50  4888.8  219.43
  4894.8  220.42  4918.5  219.60  4930.9  218.36  4940.0  216.70  4946.0  214.54
  4961.0  215.58  4967.0  214.52  4980.8  214.97  4984.1  214.47  4989.1  212.60
  4995.2  212.26  4998.0  211.76  5001.2  212.26  5008.3  213.96  5018.4  215.03
  5098.9  219.89  5283.9  222.81  5299.7  222.57  5309.8  223.40  5336.1  223.99
#Mann=5,-1,0
  4663.8    0.05       0  4868.1    0.16       0  4918.5    0.05       0
  4995.2   0.035       0  5001.2    0.05       0
Bank Sta=4995.2,5001.2
Exp/Cntr=0.3,0.1

Type RM Length L Ch R = 1,3719,454,454,454
BEGIN DESCRIPTION:
UNT032 IN ROCK 8.0
END DESCRIPTION:
XS GIS Cut Line= 3
      3626976.86     10164445.82      3626876.83     10164395.81
      3626283.37     10164151.29
#Sta/Elev= 30
  4587.4  224.47  4637.4  224.07  4727.3  222.35  4775.2  223.23  4844.9  222.84
  4953.1  217.80  4959.0  216.20  4964.4  215.78  4974.7  213.12  4983.0  212.25
  5009.3  210.84  5012.1  210.34  5015.3  210.84  5018.0  211.57  5041.7  214.86
  5060.2  216.13  5072.1  217.46  5104.5  218.45  5126.2  219.63  5148.2  219.56
  5172.2  220.09  5190.7  221.09  5212.7  221.27  5220.1  221.94  5225.5  221.67
  5244.0  222.97  5249.4  222.78  5273.4  224.14  5302.7  224.42  5341.1  225.62
#Mann=3,-1,0
  4587.4    0.16       0  5009.3    0.07       0  5015.3    0.16       0
Bank Sta=5009.3,5015.3
Exp/Cntr=0.3,0.1

Type RM Length L Ch R = 1,3265,420,420,420
BEGIN DESCRIPTION:
UNT032 IN ROCK 7.0
END DESCRIPTION:
XS GIS Cut Line= 3
      3627148.10     10164084.79      3626948.11     10164034.79
      3626380.55     10163831.83
#Sta/Elev= 30
  4681.0  222.52  4749.0  221.73  4810.9  220.11  4831.5  219.31  4837.5  218.16
  4842.6  218.92  4852.1  218.37  4872.7  215.43  4878.7  215.53  4883.3  214.19
  4904.1  214.19  4915.7  213.03  4935.9  212.96  4941.2  211.88  4972.0  211.08
  4997.4  210.69  5010.3  211.11  5030.5  210.67  5033.3  210.17  5036.5  210.67
  5052.8  210.81  5064.3  211.42  5095.3  215.63  5201.5  219.17  5212.9  220.29
  5263.8  222.30  5269.1  222.03  5294.6  223.38  5412.4  222.98  5489.9  224.97
#Mann=3,-1,0
  4681.0    0.16       0  5030.5    0.07       0  5036.5    0.16       0
Bank Sta=5030.5,5036.5
Exp/Cntr=0.3,0.1

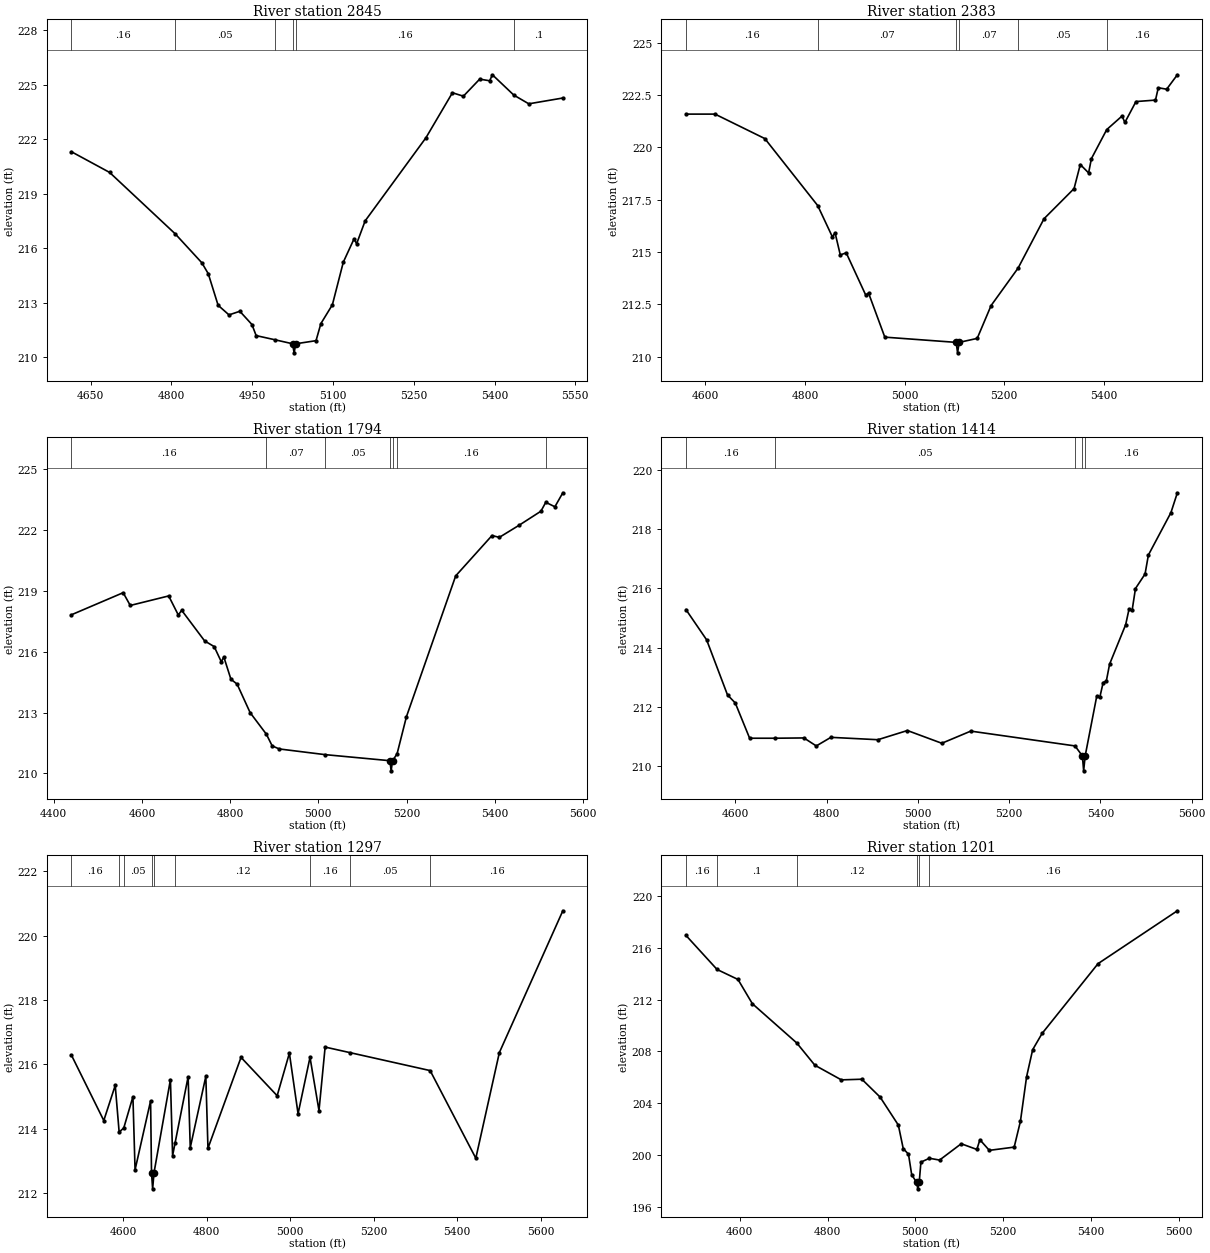
Type RM Length L Ch R = 1,2845,462,462,462
BEGIN DESCRIPTION:
UNT032 IN ROCK 6.0
END DESCRIPTION:
XS GIS Cut Line= 3
      3627262.49     10163637.38      3626892.11     10163591.64
      3626359.74     10163505.44
#Sta/Elev= 30
  4614.3  221.32  4685.2  220.18  4806.9  216.80  4856.5  215.20  4868.4  214.60
  4886.7  212.86  4906.9  212.33  4927.0  212.53  4949.5  211.80  4957.3  211.19
  4992.2  210.96  5025.0  210.74  5027.8  210.24  5031.0  210.74  5068.5  210.91
  5077.5  211.85  5098.9  212.89  5119.2  215.24  5139.1  216.52  5143.9  216.25
  5159.7  217.51  5272.6  222.09  5321.8  224.57  5342.1  224.38  5372.4  225.32
  5390.9  225.23  5396.0  225.56  5435.8  224.44  5463.6  223.96  5526.8  224.28
#Mann=6,-1,0
  4614.3    0.16       0  4806.9    0.05       0  4992.2    0.16       0
  5025.0    0.07       0  5031.0    0.16       0  5435.8     0.1       0
Bank Sta=5025,5031
Exp/Cntr=0.3,0.1

Type RM Length L Ch R = 1,2383,589,589,589
BEGIN DESCRIPTION:
UNT032 IN ROCK 5.0
END DESCRIPTION:
XS GIS Cut Line= 3
      3627250.46     10163238.86      3627050.44     10163238.86
      3626346.48     10162887.71
#Sta/Elev= 30
  4561.1  221.59  4619.5  221.59  4719.5  220.42  4825.6  217.22  4855.0  215.73
  4860.6  215.91  4871.0  214.86  4882.9  214.96  4922.1  212.94  4927.7  213.04
  4960.4  210.93  5103.7  210.68  5106.5  210.18  5109.7  210.68  5145.9  210.87
  5173.8  212.44  5228.0  214.23  5280.1  216.59  5340.4  218.03  5352.9  219.18
  5369.6  218.78  5375.2  219.46  5406.0  220.85  5436.8  221.50  5442.4  221.19
  5464.7  222.19  5503.9  222.26  5509.5  222.85  5526.3  222.78  5547.8  223.47
#Mann=6,-1,0
  4561.1    0.16       0  4825.6    0.07       0  5103.7    0.07       0
  5109.7    0.07       0  5228.0    0.05       0  5406.0    0.16       0
Bank Sta=5103.7,5109.7
Exp/Cntr=0.3,0.1

Type RM Length L Ch R = 1,1794,380,380,380
BEGIN DESCRIPTION:
UNT032 IN ROCK 3.0
END DESCRIPTION:
XS GIS Cut Line= 3
      3627443.02     10163220.67      3627233.32     10162839.83
      3626922.74     10162235.64
#Sta/Elev= 30
  4440.2  217.83  4557.5  218.92  4573.6  218.29  4660.7  218.76  4682.5  217.82
  4690.2  218.05  4742.2  216.54  4763.9  216.26  4780.0  215.51  4785.7  215.75
  4801.8  214.65  4815.8  214.41  4845.4  213.00  4882.1  211.94  4895.4  211.36
  4911.4  211.21  5015.0  210.93  5162.3  210.63  5165.0  210.13  5168.3  210.63
  5178.5  210.97  5199.7  212.80  5311.4  219.75  5393.7  221.74  5410.3  221.65
  5454.6  222.24  5504.6  222.94  5515.6  223.38  5536.3  223.16  5554.3  223.85
#Mann=7,-1,0
  4440.2    0.16       0  4882.1    0.07       0  5015.0    0.05       0
  5162.3    0.07       0  5168.3    0.05       0  5178.5    0.16       0
  5515.6     0.1       0
Bank Sta=5162.3,5168.3
Exp/Cntr=0.3,0.1

Type RM Length L Ch R = 1,1414,117,117,117
BEGIN DESCRIPTION:
Mapping XS 6ce52d95
END DESCRIPTION:
XS GIS Cut Line= 3
      3627703.93     10163164.83      3627540.75     10162644.03
      3627177.35     10162256.40
#Sta/Elev= 30
  4491.6  215.28  4536.9  214.26  4582.7  212.40  4599.7  212.13  4631.2  210.94
  4686.7  210.94  4750.1  210.95  4777.3  210.68  4809.3  210.97  4912.3  210.89
  4977.0  211.20  5052.4  210.77  5115.9  211.18  5344.5  210.68  5360.6  210.34
  5363.3  209.84  5366.6  210.34  5391.9  212.35  5398.7  212.32  5406.1  212.82
  5412.9  212.86  5420.2  213.44  5455.4  214.77  5462.7  215.29  5469.6  215.26
  5476.9  215.99  5497.9  216.48  5505.2  217.12  5554.6  218.55  5568.7  219.22
#Mann=5,-1,0
  4491.6    0.16       0  4686.7    0.05       0  5344.5    0.16       0
  5360.6   0.033       0  5366.6    0.16       0
Bank Sta=5360.6,5366.6
Exp/Cntr=0.3,0.1

Type RM Length L Ch R = 1,1297,96,96,96
BEGIN DESCRIPTION:
Mapping XS 7c06a5b2
END DESCRIPTION:
XS GIS Cut Line= 4
      3627811.57     10163137.05      3627712.62     10162716.94
      3627589.36     10162550.28      3627202.91     10162175.96
#Sta/Elev= 30
  4476.0  216.29  4553.5  214.26  4580.9  215.35  4590.3  213.90  4601.4  214.03
  4623.3  215.00  4628.4  212.73  4665.6  214.87  4667.8  212.64  4670.5  212.14
  4673.8  212.64  4713.1  215.53  4718.3  213.17  4724.2  213.56  4755.5  215.62
  4760.6  213.42  4797.9  215.63  4803.0  213.40  4882.2  216.22  4968.7  215.03
  4998.0  216.35  5018.8  214.47  5047.4  216.22  5068.9  214.57  5083.6  216.54
  5142.2  216.37  5335.1  215.81  5444.5  213.09  5500.9  216.37  5652.9  220.77
#Mann=9,-1,0
  4476.0    0.16       0  4590.3     0.1       0  4601.4    0.05       0
  4667.8    0.07       0  4673.8    0.05       0  4724.2    0.12       0
  5047.4    0.16       0  5142.2    0.05       0  5335.1    0.16       0
Bank Sta=4667.8,4673.8
Exp/Cntr=0.3,0.1

Type RM Length L Ch R = 1,1201,384,384,384
BEGIN DESCRIPTION:
Mapping XS 1861f4e9
END DESCRIPTION:
XS GIS Cut Line= 3
      3627872.35     10163086.76      3627754.29     10162605.83
      3627326.32     10162151.87
#Sta/Elev= 30
  4477.6  216.95  4548.5  214.32  4596.1  213.55  4628.8  211.68  4729.9  208.65
  4771.2  206.93  4831.5  205.80  4878.2  205.85  4919.8  204.47  4961.3  202.31
  4972.4  200.50  4984.4  200.06  4991.7  198.48  5002.8  197.89  5005.6  197.39
  5008.8  197.89  5012.7  199.45  5032.0  199.75  5055.2  199.61  5104.5  200.87
  5140.1  200.43  5147.0  201.18  5168.5  200.36  5225.1  200.61  5239.3  202.60
  5253.4  206.05  5267.2  208.13  5288.6  209.38  5416.1  214.77  5596.7  218.85
#Mann=6,-1,0
  4477.6    0.16       0  4548.5     0.1       0  4729.9    0.12       0
  5002.8    0.07       0  5008.8    0.12       0  5032.0    0.16       0
Bank Sta=5002.8,5008.8
Exp/Cntr=0.3,0.1

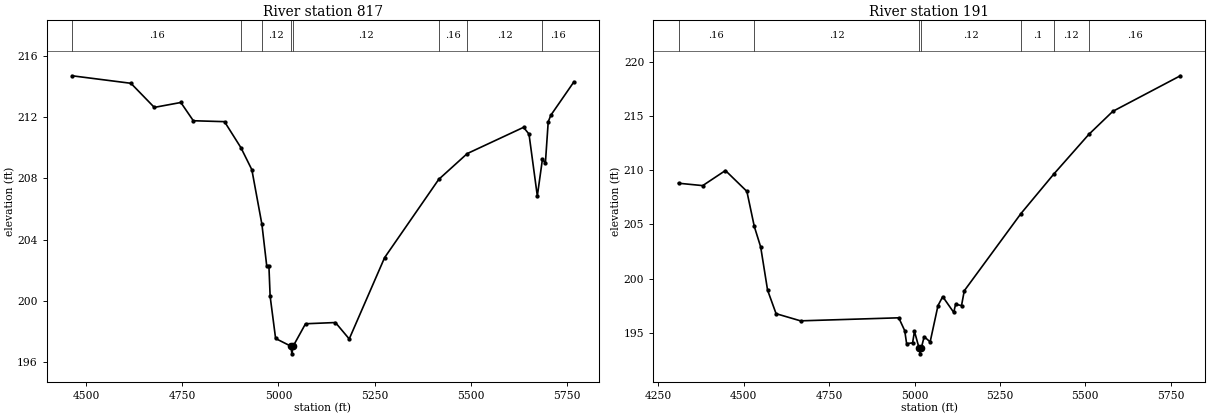
Type RM Length L Ch R = 1,817,626,626,626
BEGIN DESCRIPTION:
UNT032 IN ROCK 2.0
END DESCRIPTION:
XS GIS Cut Line= 3
      3628172.70     10163022.51      3628091.50     10162520.42
      3627555.84     10161933.54
#Sta/Elev= 30
  4463.9  214.68  4616.7  214.19  4677.5  212.62  4746.4  212.94  4778.8  211.75
  4859.8  211.69  4902.3  210.00  4930.8  208.56  4957.0  204.99  4969.4  202.30
  4975.1  202.30  4978.3  200.31  4992.5  197.56  5032.1  197.06  5034.8  196.56
  5038.1  197.06  5070.2  198.52  5147.9  198.60  5183.7  197.53  5275.6  202.83
  5416.2  207.93  5490.2  209.61  5636.4  211.32  5650.6  210.88  5672.2  206.85
  5685.6  209.26  5693.1  208.97  5700.5  211.68  5707.3  212.11  5767.1  214.28
#Mann=8,-1,0
  4463.9    0.16       0  4902.3     0.1       0  4957.0    0.12       0
  5032.1    0.07       0  5038.1    0.12       0  5416.2    0.16       0
  5490.2    0.12       0  5685.6    0.16       0
Bank Sta=5032.1,5038.1
Exp/Cntr=0.3,0.1

Type RM Length L Ch R = 1,191,0,0,0
BEGIN DESCRIPTION:
UNT032 IN ROCK 1.0
END DESCRIPTION:
XS GIS Cut Line= 4
      3628227.77     10162699.83      3628304.15     10162151.27
      3628186.10     10161894.33      3627581.95     10161706.83
#Sta/Elev= 30
  4308.9  208.80  4379.7  208.58  4446.2  209.97  4509.0  208.05  4530.7  204.82
  4549.4  202.93  4569.6  198.95  4594.5  196.78  4666.1  196.12  4953.7  196.40
  4971.2  195.21  4976.7  194.02  4994.2  194.09  4999.7  195.15  5013.4  193.58
  5016.2  193.08  5019.4  193.58  5028.1  194.66  5045.6  194.18  5068.6  197.53
  5082.4  198.35  5114.6  196.90  5120.1  197.64  5137.5  197.53  5145.5  198.89
  5311.6  206.01  5407.8  209.65  5509.9  213.29  5580.3  215.42  5778.1  218.70
#Mann=7,-1,0
  4308.9    0.16       0  4530.7    0.12       0  5013.4    0.07       0
  5019.4    0.12       0  5311.6     0.1       0  5407.8    0.12       0
  5509.9    0.16       0
Bank Sta=5013.4,5019.4
Exp/Cntr=0.3,0.1

Chan Stop Cuts=-1