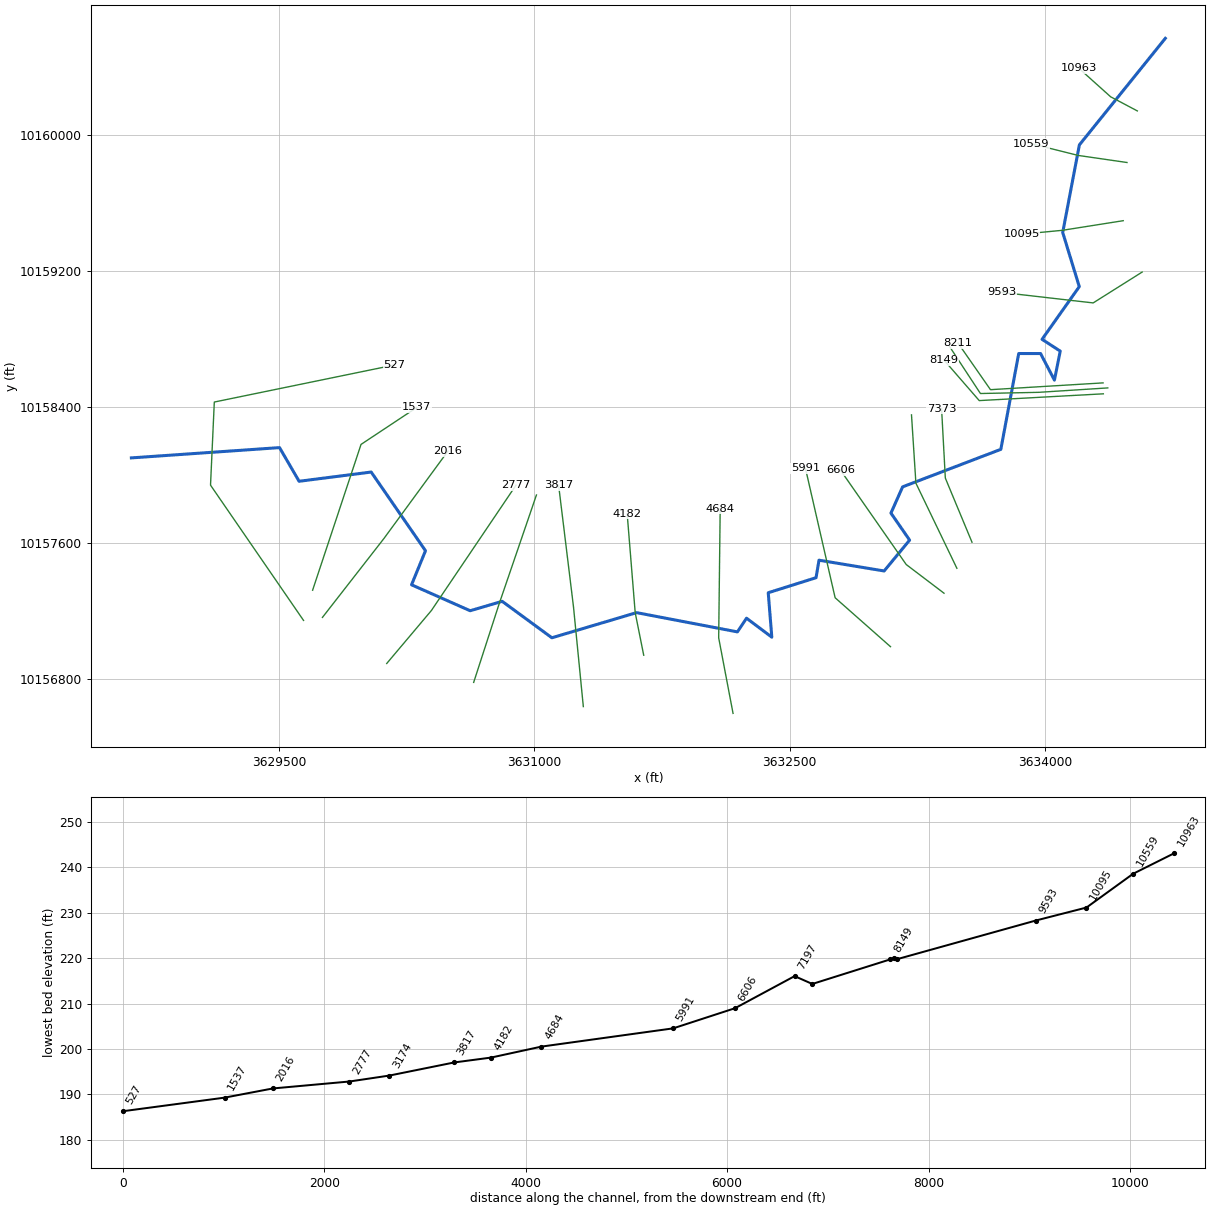
--- UNT033 IN ROCK.prj (project) ---

Proj Title=UNT033 IN ROCK Base Level Engineering
Current Plan=p01
Default Exp/Contr=0.3,0.1
English Units
Geom File=g01
Flow File=f01
Plan File=p01
BEGIN DESCRIPTION:
UNT033 IN ROCK
END DESCRIPTION:

--- UNT033 IN ROCK.p01 (plan) ---

Plan Title=Multiple Run
Short Identifier=Multiple
Geom File=g01
Flow File=f01
Subcritical Flow
K Sum by GR= 0
Std Step Tol= 0.01
Critical Tol= 0.01
Num of Std Step Trials= 20
Max Error Tol= 0.3
Flow Tol Ratio= 0.001
Split Flow NTrial= 30
Split Flow Tol= 0.02
Split Flow Ratio= 0.02
Log Output Level= 0
Friction Slope Method= 1
Unsteady Friction Slope Method= 2
Unsteady Bridges Friction Slope Method= 1
Parabolic Critical Depth
Global Vel Dist=  1 , 1 , 1
Global Log Level= 0
CheckData=True
Encroach Param= -1, 0, 0, 0
BEGIN DESCRIPTION:
Multiple Run
END DESCRIPTION:

--- UNT033 IN ROCK.f01 (steady flow) ---

Flow Title=Multiple
Number of Profiles=7
Profile Names=10-year,25-year,50-year,1pct_min,100-year,1pct_plu,500-year
River Rch & RM= UNT033 IN ROCK,Reach-1,10963
     507     673     807     709     959    1297    1357
Boundary for River Rch & Prof#=UNT033 IN ROCK,Reach-1,1
Up Type=0
Dn Type=3
Dn Slope=0.005
Boundary for River Rch & Prof#=UNT033 IN ROCK,Reach-1,2
Up Type=0
Dn Type=3
Dn Slope=0.005
Boundary for River Rch & Prof#=UNT033 IN ROCK,Reach-1,3
Up Type=0
Dn Type=3
Dn Slope=0.005
Boundary for River Rch & Prof#=UNT033 IN ROCK,Reach-1,4
Up Type=0
Dn Type=3
Dn Slope=0.005
Boundary for River Rch & Prof#=UNT033 IN ROCK,Reach-1,5
Up Type=0
Dn Type=3
Dn Slope=0.005
Boundary for River Rch & Prof#=UNT033 IN ROCK,Reach-1,6
Up Type=0
Dn Type=3
Dn Slope=0.005
Boundary for River Rch & Prof#=UNT033 IN ROCK,Reach-1,7
Up Type=0
Dn Type=3
Dn Slope=0.005

--- UNT033 IN ROCK.g01 (geometry) ---

Geom Title=Existing Conditions

River Reach=UNT033 IN ROCK,Reach-1
Reach XY= 30
      3634706.70     10160568.32      3634201.76     10159941.89
      3634103.85     10159426.78      3634201.24     10159108.55
      3633982.49     10158798.66      3634089.26     10158729.39
      3634055.14     10158559.06      3633973.70     10158715.09
      3633845.38     10158715.26      3633740.28     10158151.96
      3633163.17     10157931.34      3633094.66     10157777.02
      3633204.38     10157618.27      3633054.68     10157436.87
      3632672.06     10157500.14      3632654.65     10157397.31
      3632373.72     10157308.86      3632394.77     10157047.53
      3632246.25     10157159.05      3632192.60     10157078.71
      3631600.22     10157191.87      3631102.69     10157044.06
      3630810.67     10157258.37      3630622.49     10157203.02
      3630278.12     10157355.57      3630360.07     10157555.74
      3630041.07     10158018.40      3629617.53     10157964.17
      3629502.50     10158162.09      3628632.11     10158101.64

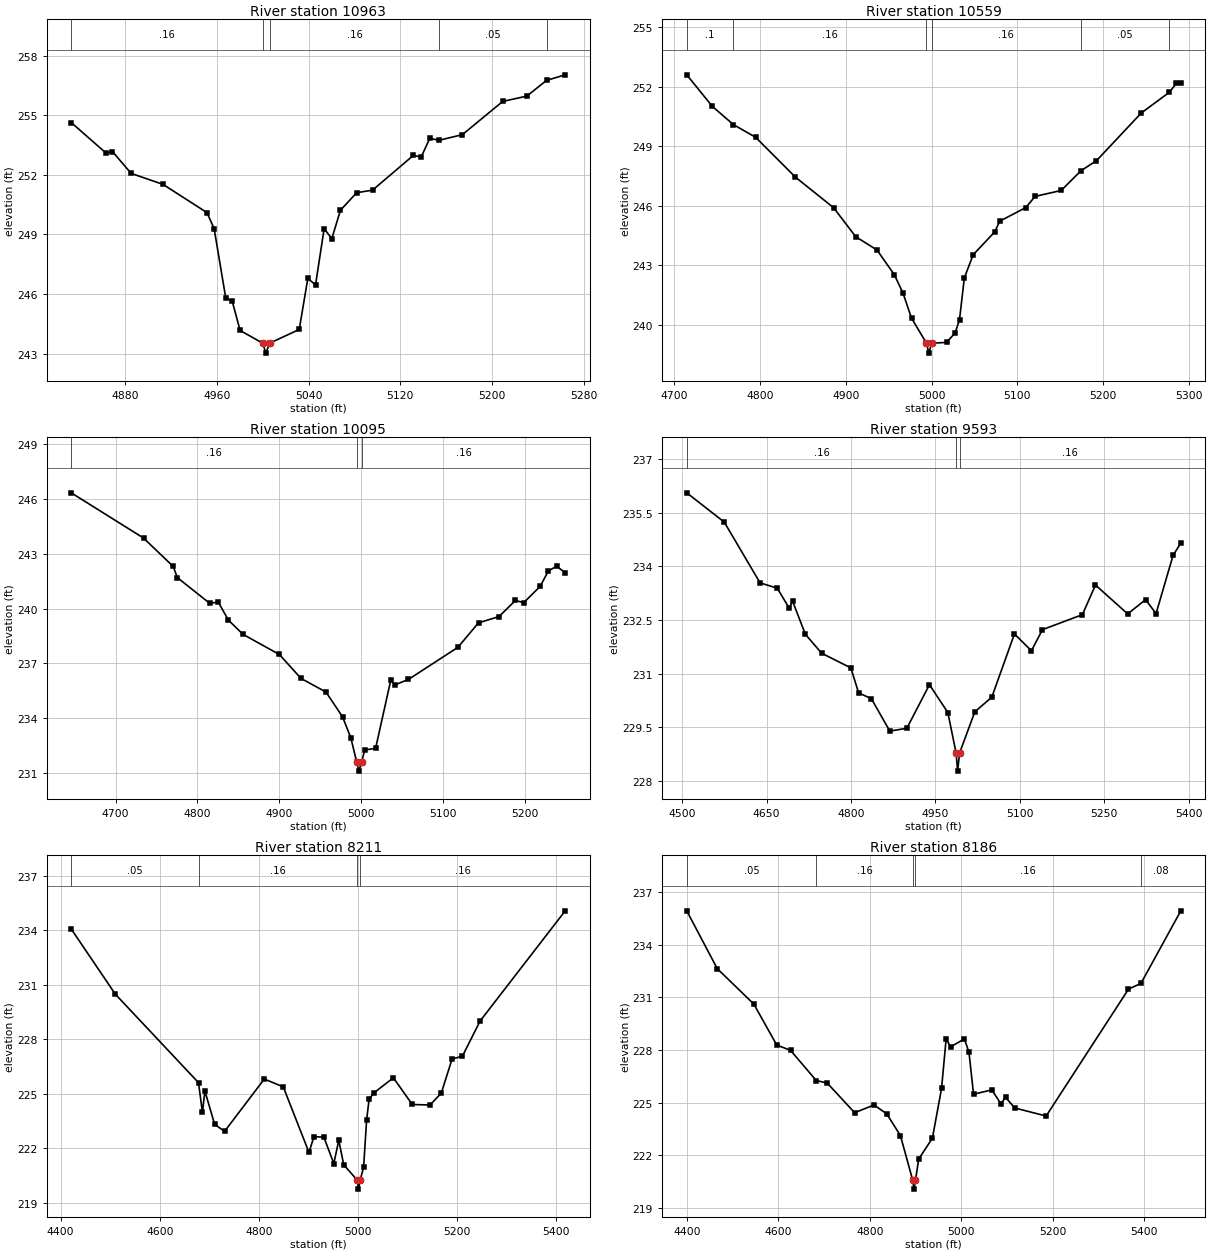
Type RM Length L Ch R = 1,10963,404,404,404
BEGIN DESCRIPTION:
UNT033 IN ROCK 19.0
END DESCRIPTION:
XS GIS Cut Line= 3
      3634542.14     10160141.62      3634385.51     10160224.57
      3634197.24     10160393.67
#Sta/Elev= 30
  4833.3  254.63  4863.5  253.10  4869.2  253.17  4885.5  252.07  4913.2  251.52
  4951.5  250.10  4957.8  249.29  4967.9  245.80  4973.5  245.65  4980.4  244.17
  5000.1  243.53  5002.8  243.03  5006.1  243.53  5031.9  244.22  5039.4  246.79
  5046.1  246.46  5053.6  249.29  5060.3  248.79  5067.8  250.22  5082.0  251.10
  5095.8  251.23  5131.4  252.98  5138.1  252.89  5145.6  253.83  5153.9  253.74
  5174.0  254.02  5209.1  255.69  5230.2  255.96  5247.3  256.75  5263.6  257.03
#Mann=5,-1,0
  4833.3    0.16       0  5000.1    0.07       0  5006.1    0.16       0
  5153.9    0.05       0  5247.3    0.08       0
Bank Sta=5000.1,5006.1
Exp/Cntr=0.3,0.1

Type RM Length L Ch R = 1,10559,464,464,464
BEGIN DESCRIPTION:
UNT033 IN ROCK 18.0
END DESCRIPTION:
XS GIS Cut Line= 3
      3634481.55     10159838.32      3634194.54     10159879.95
      3633917.42     10159949.37
#Sta/Elev= 30
  4714.6  252.59  4744.4  251.00  4769.0  250.08  4794.9  249.44  4841.3  247.43
  4885.8  245.89  4911.5  244.43  4936.3  243.76  4956.6  242.51  4966.7  241.58
  4976.6  240.32  4994.0  239.06  4996.7  238.56  5000.0  239.06  5017.4  239.10
  5027.4  239.58  5032.5  240.25  5038.1  242.35  5048.4  243.52  5073.7  244.68
  5079.3  245.21  5109.8  245.90  5120.5  246.46  5151.0  246.76  5174.2  247.76
  5192.1  248.26  5244.2  250.66  5277.0  251.71  5285.3  252.16  5290.3  252.16
#Mann=6,-1,0
  4714.6     0.1       0  4769.0    0.16       0  4994.0    0.07       0
  5000.0    0.16       0  5174.2    0.05       0  5277.0    0.08       0
Bank Sta=4994,5000
Exp/Cntr=0.3,0.1

Type RM Length L Ch R = 1,10095,502,502,502
BEGIN DESCRIPTION:
UNT033 IN ROCK 17.0
END DESCRIPTION:
XS GIS Cut Line= 3
      3634459.36     10159496.23      3634103.40     10159439.85
      3633861.63     10159416.46
#Sta/Elev= 30
  4645.9  246.32  4734.2  243.85  4770.4  242.30  4775.5  241.69  4815.2  240.28
  4825.4  240.36  4837.8  239.37  4855.7  238.59  4900.1  237.49  4926.6  236.18
  4957.0  235.44  4977.2  234.09  4987.4  232.94  4994.5  231.62  4997.2  231.12
  5000.5  231.62  5004.4  232.28  5017.6  232.36  5036.2  236.10  5041.2  235.83
  5057.8  236.13  5118.1  237.88  5143.3  239.22  5168.3  239.56  5188.4  240.44
  5198.5  240.32  5218.6  241.21  5228.6  242.05  5238.7  242.31  5249.2  241.96
#Mann=3,-1,0
  4645.9    0.16       0  4994.5    0.07       0  5000.5    0.16       0
Bank Sta=4994.5,5000.5
Exp/Cntr=0.3,0.1

Type RM Length L Ch R = 1,9593,1382,1382,1382
BEGIN DESCRIPTION:
UNT033 IN ROCK 16.0
END DESCRIPTION:
XS GIS Cut Line= 3
      3634570.48     10159194.15      3634282.66     10159012.79
      3633748.57     10159074.18
#Sta/Elev= 30
  4508.1  236.06  4574.8  235.24  4638.4  233.54  4669.0  233.39  4690.2  232.83
  4696.1  233.03  4718.9  232.10  4747.9  231.57  4799.7  231.16  4813.5  230.46
  4836.1  230.30  4869.0  229.39  4899.2  229.47  4939.4  230.69  4972.1  229.91
  4986.8  228.77  4989.5  228.27  4992.8  228.77  5020.0  229.93  5050.2  230.34
  5090.4  232.11  5120.6  231.64  5140.2  232.23  5211.2  232.65  5234.4  233.48
  5291.7  232.67  5323.4  233.07  5342.1  232.68  5372.3  234.31  5385.9  234.65
#Mann=3,-1,0
  4508.1    0.16       0  4986.8    0.07       0  4992.8    0.16       0
Bank Sta=4986.8,4992.8
Exp/Cntr=0.3,0.1

Type RM Length L Ch R = 1,8211,25,25,25
BEGIN DESCRIPTION:
Mapping XS d0c97d41
END DESCRIPTION:
XS GIS Cut Line= 3
      3634340.93     10158542.62      3633679.43     10158502.68
      3633488.59     10158776.80
#Sta/Elev= 30
  4421.4  234.06  4510.4  230.47  4678.2  225.60  4686.1  223.97  4691.1  225.14
  4710.7  223.31  4730.8  222.92  4810.9  225.80  4849.2  225.37  4901.1  221.76
  4911.1  222.63  4931.1  222.60  4951.2  221.15  4961.2  222.43  4971.2  221.08
  4998.3  220.24  5001.0  219.74  5004.3  220.24  5011.3  220.94  5017.4  223.55
  5022.4  224.68  5031.3  225.02  5071.4  225.87  5109.5  224.40  5145.3  224.37
  5168.1  225.03  5189.8  226.90  5210.7  227.06  5246.5  229.00  5418.1  235.06
#Mann=4,-1,0
  4421.4    0.05       0  4678.2    0.16       0  4998.3    0.07       0
  5004.3    0.16       0
Bank Sta=4998.3,5004.3
Exp/Cntr=0.3,0.1

Type RM Length L Ch R = 1,8186,37,37,37
BEGIN DESCRIPTION:
UNT033 IN ROCK 15.0
END DESCRIPTION:
XS GIS Cut Line= 4
      3634368.63     10158513.10      3633962.42     10158487.06
      3633620.40     10158480.11      3633438.54     10158757.24
#Sta/Elev= 30
  4399.5  235.92  4466.2  232.63  4546.3  230.61  4596.4  228.28  4626.5  227.98
  4682.9  226.26  4706.7  226.12  4766.8  224.43  4809.2  224.87  4836.9  224.37
  4866.9  223.13  4893.9  220.58  4896.6  220.08  4899.9  220.58  4906.9  221.79
  4936.9  222.98  4956.9  225.81  4966.9  228.62  4976.9  228.18  5006.9  228.63
  5016.9  227.87  5026.9  225.48  5066.9  225.73  5086.9  224.93  5096.9  225.31
  5116.9  224.70  5185.7  224.24  5365.8  231.46  5393.1  231.79  5480.1  235.91
#Mann=5,-1,0
  4399.5    0.05       0  4682.9    0.16       0  4893.9    0.07       0
  4899.9    0.16       0  5393.1    0.08       0
Bank Sta=4893.9,4899.9
Exp/Cntr=0.3,0.1

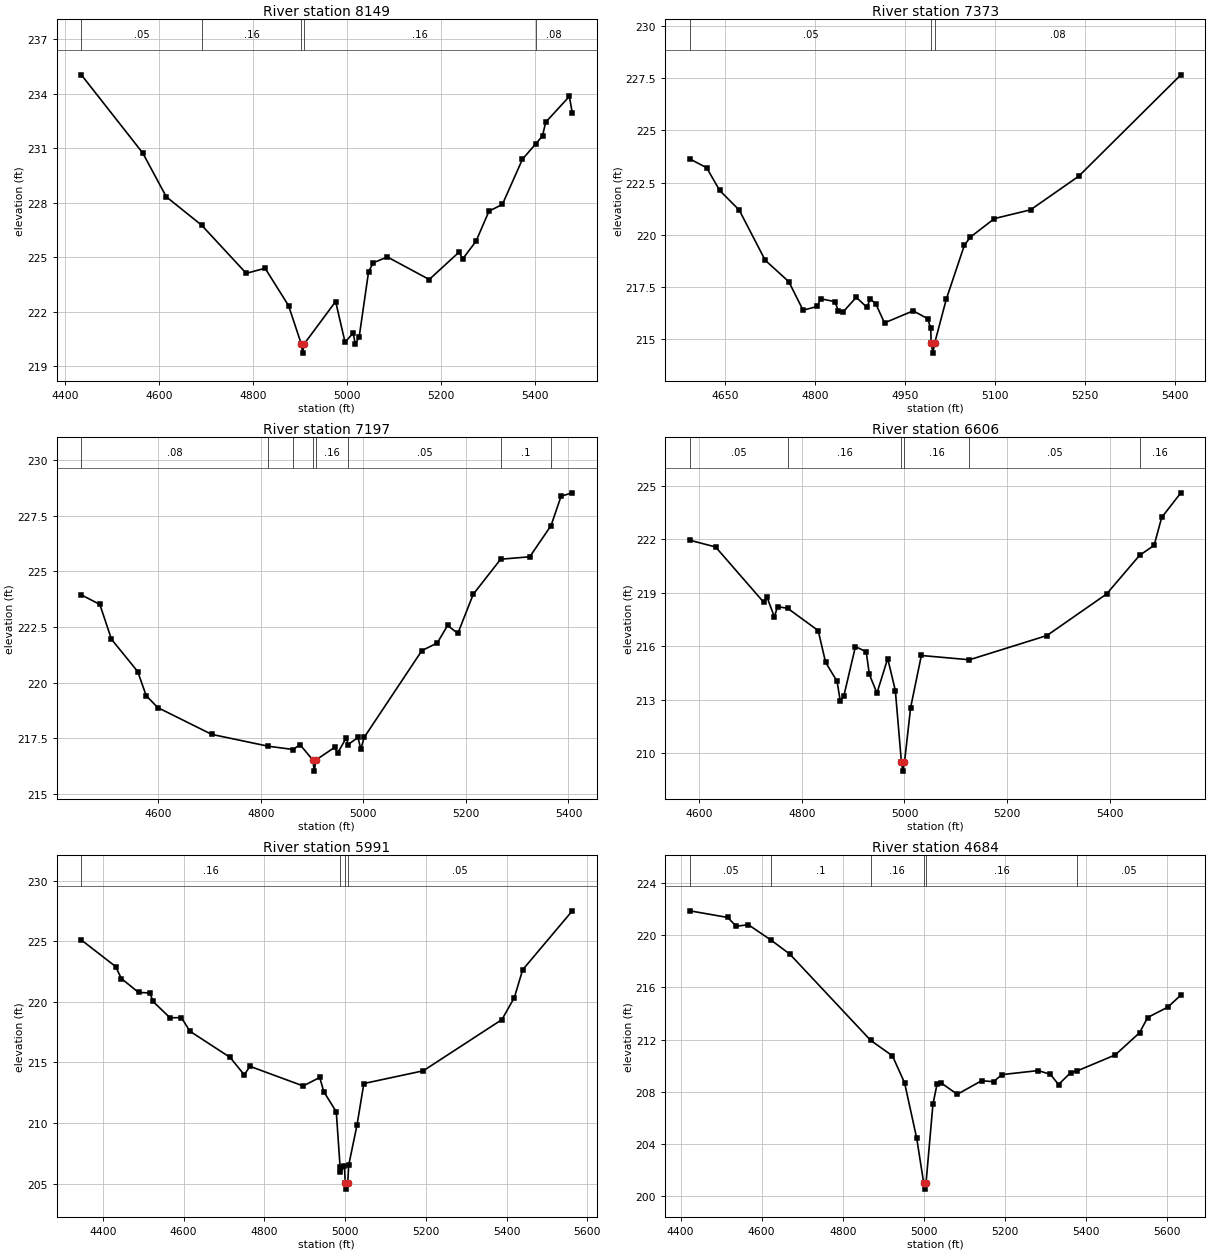
Type RM Length L Ch R = 1,8149,776,776,776
BEGIN DESCRIPTION:
Mapping XS ba4c14e0
END DESCRIPTION:
XS GIS Cut Line= 3
      3634342.59     10158478.38      3633613.46     10158438.45
      3633406.97     10158676.17
#Sta/Elev= 30
  4434.9  235.04  4565.6  230.74  4615.7  228.33  4690.9  226.77  4785.9  224.12
  4826.0  224.40  4876.0  222.34  4903.1  220.23  4905.8  219.73  4909.1  220.23
  4976.2  222.57  4996.2  220.33  5013.3  220.83  5018.3  220.23  5026.3  220.62
  5046.3  224.21  5056.3  224.70  5086.4  225.02  5175.4  223.78  5239.0  225.29
  5246.6  224.91  5275.1  225.89  5302.6  227.54  5331.1  227.91  5373.9  230.40
  5402.0  231.24  5416.6  231.68  5423.2  232.43  5473.6  233.85  5480.0  232.94
#Mann=5,-1,0
  4434.9    0.05       0  4690.9    0.16       0  4903.1    0.07       0
  4909.1    0.16       0  5402.0    0.08       0
Bank Sta=4903.1,4909.1
Exp/Cntr=0.3,0.1

Type RM Length L Ch R = 1,7373,176,176,176
BEGIN DESCRIPTION:
UNT033 IN ROCK 14.0
END DESCRIPTION:
XS GIS Cut Line= 3
      3633570.82     10157605.84      3633414.24     10157982.71
      3633392.11     10158391.61
#Sta/Elev= 30
  4591.9  223.63  4619.8  223.21  4641.5  222.12  4674.0  221.18  4717.3  218.77
  4756.6  217.74  4780.4  216.37  4803.9  216.55  4809.7  216.92  4833.6  216.78
  4839.0  216.34  4847.2  216.29  4868.9  216.99  4886.7  216.51  4892.1  216.91
  4901.4  216.68  4916.0  215.76  4963.7  216.34  4987.6  215.97  4993.0  215.51
  4993.7  214.81  4996.5  214.31  4999.7  214.81  5019.0  216.91  5049.0  219.49
  5059.0  219.88  5099.1  220.77  5159.2  221.19  5239.3  222.80  5409.5  227.67
#Mann=3,-1,0
  4591.9    0.05       0  4993.7    0.07       0  4999.7    0.08       0
Bank Sta=4993.7,4999.7
Exp/Cntr=0.3,0.1

Type RM Length L Ch R = 1,7197,591,591,591
BEGIN DESCRIPTION:
UNT033 IN ROCK 13.0
END DESCRIPTION:
XS GIS Cut Line= 3
      3633482.01     10157452.59      3633241.30     10157953.02
      3633215.44     10158354.48
#Sta/Elev= 30
  4449.9  223.94  4486.0  223.51  4508.6  221.95  4559.8  220.50  4576.5  219.41
  4599.1  218.88  4704.1  217.68  4813.9  217.15  4863.0  217.00  4876.3  217.22
  4901.4  216.53  4904.2  216.03  4907.4  216.53  4944.2  217.10  4949.7  216.84
  4966.8  217.53  4970.1  217.22  4989.4  217.54  4995.0  217.02  5001.7  217.55
  5114.1  221.44  5144.1  221.78  5164.2  222.57  5184.2  222.21  5214.3  223.97
  5267.7  225.54  5324.5  225.65  5366.0  227.05  5385.6  228.37  5407.5  228.52
#Mann=8,-1,0
  4449.9    0.08       0  4813.9    0.05       0  4863.0    0.16       0
  4901.4    0.03       0  4907.4    0.16       0  4970.1    0.05       0
  5267.7     0.1       0  5366.0    0.16       0
Bank Sta=4901.4,4907.4
Exp/Cntr=0.3,0.1

Type RM Length L Ch R = 1,6606,615,615,615
BEGIN DESCRIPTION:
UNT033 IN ROCK 12.0
END DESCRIPTION:
XS GIS Cut Line= 3
      3633406.48     10157306.00      3633184.34     10157474.83
      3632797.84     10158030.15
#Sta/Elev= 30
  4582.3  221.94  4632.4  221.56  4725.9  218.46  4732.2  218.76  4746.7  217.64
  4753.0  218.21  4772.5  218.12  4832.0  216.87  4846.5  215.08  4868.8  214.02
  4874.8  212.94  4881.8  213.18  4904.5  215.97  4925.5  215.68  4931.6  214.41
  4946.4  213.36  4967.3  215.30  4982.2  213.50  4994.0  209.48  4996.8  208.98
  5000.0  209.48  5011.9  212.54  5032.8  215.47  5126.4  215.23  5277.2  216.59
  5393.3  218.92  5457.5  221.09  5485.8  221.65  5500.6  223.22  5537.9  224.60
#Mann=6,-1,0
  4582.3    0.05       0  4772.5    0.16       0  4994.0    0.07       0
  5000.0    0.16       0  5126.4    0.05       0  5457.5    0.16       0
Bank Sta=4994,5000
Exp/Cntr=0.3,0.1

Type RM Length L Ch R = 1,5991,1307,1307,1307
BEGIN DESCRIPTION:
UNT033 IN ROCK 11.0
END DESCRIPTION:
XS GIS Cut Line= 3
      3633092.13     10156991.62      3632766.73     10157279.35
      3632592.10     10158041.65
#Sta/Elev= 30
  4346.6  225.11  4431.5  222.92  4445.7  221.93  4488.4  220.78  4516.9  220.74
  4523.5  220.06  4566.2  218.69  4594.6  218.70  4615.5  217.58  4715.1  215.42
  4750.2  213.98  4764.4  214.68  4896.2  213.06  4937.2  213.76  4947.5  212.57
  4978.2  210.93  4987.7  206.34  4988.5  205.95  4998.4  206.41  5000.5  205.04
  5003.3  204.54  5006.5  205.04  5009.0  206.52  5029.5  209.82  5046.5  213.26
  5193.7  214.31  5388.6  218.54  5419.4  220.36  5439.9  222.65  5563.0  227.52
#Mann=4,-1,0
  4346.6    0.16       0  4987.7    0.05       0  5000.5    0.03       0
  5006.5    0.05       0
Bank Sta=5000.5,5006.5
Exp/Cntr=0.3,0.1

Type RM Length L Ch R = 1,4684,502,502,502
BEGIN DESCRIPTION:
UNT033 IN ROCK 9.0
END DESCRIPTION:
XS GIS Cut Line= 3
      3632166.98     10156599.61      3632082.57     10157043.89
      3632091.45     10157803.61
#Sta/Elev= 30
  4422.8  221.87  4516.5  221.36  4536.8  220.69  4567.4  220.80  4623.3  219.62
  4669.2  218.56  4869.0  211.94  4922.8  210.75  4952.8  208.68  4982.8  204.42
  4999.8  201.03  5002.5  200.53  5005.8  201.03  5022.8  207.04  5032.8  208.56
  5042.8  208.68  5082.8  207.80  5142.8  208.84  5172.8  208.77  5192.8  209.31
  5282.8  209.62  5312.8  209.33  5332.8  208.55  5362.8  209.46  5379.2  209.60
  5472.8  210.82  5532.8  212.52  5552.8  213.69  5602.8  214.49  5634.8  215.41
#Mann=6,-1,0
  4422.8    0.05       0  4623.3     0.1       0  4869.0    0.16       0
  4999.8    0.07       0  5005.8    0.16       0  5379.2    0.05       0
Bank Sta=4999.8,5005.8
Exp/Cntr=0.3,0.1

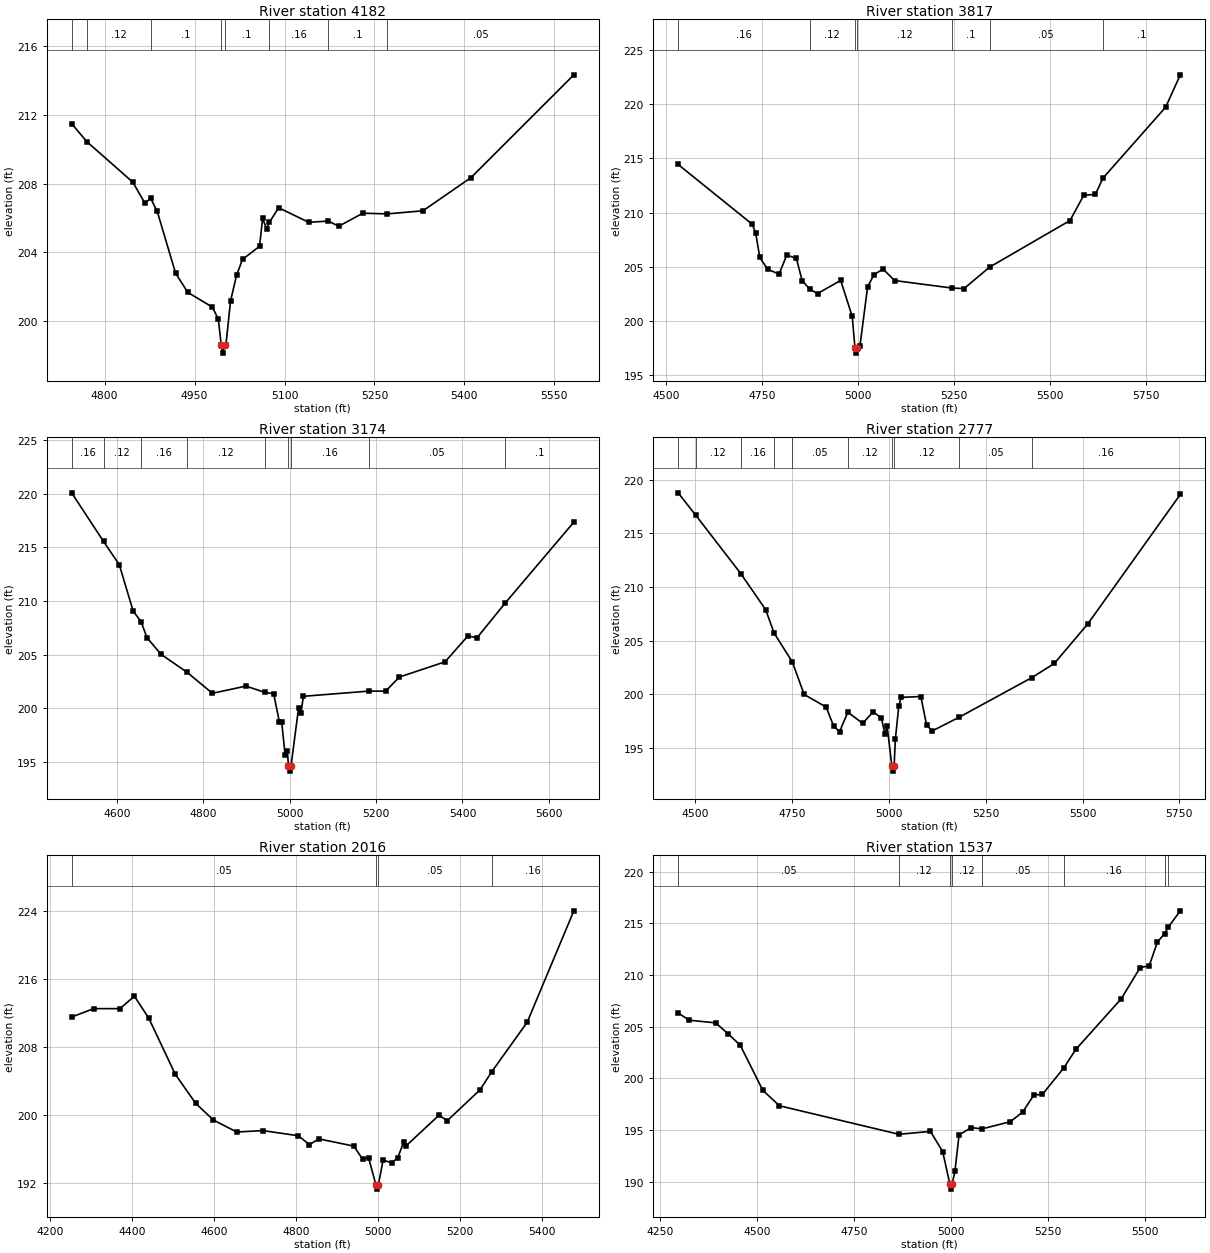
Type RM Length L Ch R = 1,4182,365,365,365
BEGIN DESCRIPTION:
UNT033 IN ROCK 8.0
END DESCRIPTION:
XS GIS Cut Line= 3
      3631642.10     10156941.65      3631592.11     10157191.64
      3631545.01     10157772.50
#Sta/Elev= 30
  4744.9  211.49  4770.3  210.44  4846.9  208.08  4867.3  206.84  4876.6  207.15
  4887.7  206.37  4918.3  202.77  4938.7  201.65  4979.4  200.80  4989.6  200.09
  4994.3  198.61  4997.0  198.11  5000.3  198.61  5002.3  198.61  5009.9  201.14
  5019.9  202.64  5029.9  203.58  5058.4  204.34  5063.4  205.97  5070.1  205.35
  5074.7  205.73  5090.1  206.59  5140.3  205.74  5173.0  205.81  5190.5  205.51
  5230.6  206.27  5271.3  206.23  5330.9  206.41  5411.2  208.35  5582.6  214.34
#Mann=8,-1,0
  4744.9    0.16       0  4770.3    0.12       0  4876.6     0.1       0
  4994.3    0.07       0  5000.3     0.1       0  5074.7    0.16       0
  5173.0     0.1       0  5271.3    0.05       0
Bank Sta=4994.3,5000.3
Exp/Cntr=0.3,0.1

Type RM Length L Ch R = 1,3817,643,643,643
BEGIN DESCRIPTION:
UNT033 IN ROCK 7.0
END DESCRIPTION:
XS GIS Cut Line= 3
      3631287.33     10156639.60      3631229.58     10157226.04
      3631142.11     10157941.64
#Sta/Elev= 30
  4530.4  214.43  4723.4  208.93  4732.6  208.14  4743.5  205.86  4763.6  204.78
  4793.7  204.32  4813.8  206.07  4838.9  205.78  4854.0  203.72  4873.9  202.93
  4894.2  202.53  4954.5  203.74  4984.6  200.43  4991.7  197.54  4994.4  197.04
  4997.7  197.54  5004.7  197.67  5024.8  203.16  5041.4  204.27  5065.0  204.79
  5095.2  203.73  5244.6  203.04  5276.4  202.99  5343.1  204.97  5552.8  209.26
  5588.7  211.59  5619.0  211.67  5638.8  213.17  5802.4  219.71  5840.6  222.69
#Mann=7,-1,0
  4530.4    0.16       0  4873.9    0.12       0  4991.7    0.07       0
  4997.7    0.12       0  5244.6     0.1       0  5343.1    0.05       0
  5638.8     0.1       0
Bank Sta=4991.7,4997.7
Exp/Cntr=0.3,0.1

Type RM Length L Ch R = 1,3174,397,397,397
BEGIN DESCRIPTION:
UNT033 IN ROCK 6.0
END DESCRIPTION:
XS GIS Cut Line= 3
      3630643.14     10156781.75      3630792.11     10157241.64
      3631011.89     10157883.55
#Sta/Elev= 30
  4495.8  220.08  4569.6  215.55  4606.0  213.39  4638.0  209.08  4656.4  208.08
  4670.0  206.60  4702.0  205.06  4763.0  203.36  4821.5  201.41  4899.2  202.08
  4942.2  201.50  4963.2  201.37  4976.6  198.70  4981.9  198.70  4989.6  195.69
  4994.9  196.07  4997.4  194.66  5000.1  194.16  5003.4  194.66  5020.9  200.06
  5026.1  199.56  5032.1  201.13  5182.9  201.61  5222.3  201.61  5254.0  202.92
  5359.7  204.34  5412.6  206.75  5433.7  206.58  5498.8  209.81  5657.7  217.35
#Mann=9,-1,0
  4495.8    0.16       0  4569.6    0.12       0  4656.4    0.16       0
  4763.0    0.12       0  4942.2    0.16       0  4997.4    0.07       0
  5003.4    0.16       0  5182.9    0.05       0  5498.8     0.1       0
Bank Sta=4997.4,5003.4
Exp/Cntr=0.3,0.1

Type RM Length L Ch R = 1,2777,761,761,761
BEGIN DESCRIPTION:
UNT033 IN ROCK 5.0
END DESCRIPTION:
XS GIS Cut Line= 3
      3630132.25     10156892.85      3630394.36     10157203.83
      3630892.10     10157941.63
#Sta/Elev= 30
  4455.7  218.77  4501.3  216.68  4617.9  211.23  4681.7  207.89  4703.7  205.70
  4750.8  203.01  4781.1  199.99  4837.8  198.82  4857.7  197.01  4872.6  196.53
  4894.0  198.34  4932.1  197.30  4959.5  198.38  4980.5  197.79  4989.5  196.34
  4995.5  197.02  5007.5  193.35  5010.2  192.85  5013.5  193.35  5016.6  195.82
  5025.4  198.87  5031.5  199.72  5082.4  199.80  5097.4  197.12  5112.3  196.60
  5181.9  197.88  5369.1  201.56  5427.2  202.88  5514.1  206.59  5752.4  218.62
#Mann=10,-1,0
  4455.7    0.16       0  4501.3    0.12       0  4617.9    0.16       0
  4703.7    0.12       0  4750.8    0.05       0  4894.0    0.12       0
  5007.5    0.07       0  5013.5    0.12       0  5181.9    0.05       0
  5369.1    0.16       0
Bank Sta=5007.5,5013.5
Exp/Cntr=0.3,0.1

Type RM Length L Ch R = 1,2016,479,479,479
BEGIN DESCRIPTION:
UNT033 IN ROCK 3.0
END DESCRIPTION:
XS GIS Cut Line= 3
      3629754.63     10157163.85      3630114.48     10157625.88
      3630492.13     10158141.67
#Sta/Elev= 30
  4251.9  211.57  4305.4  212.56  4369.7  212.56  4405.0  214.03  4440.3  211.41
  4504.5  204.85  4554.3  201.42  4597.7  199.45  4654.7  198.04  4718.1  198.21
  4804.9  197.60  4831.7  196.56  4854.9  197.23  4940.6  196.38  4961.4  194.84
  4976.1  195.02  4994.0  191.82  4996.7  191.32  5000.0  191.82  5011.6  194.73
  5032.5  194.42  5047.1  194.99  5061.8  196.85  5068.0  196.43  5147.5  200.00
  5168.4  199.39  5247.9  203.00  5276.3  205.12  5362.9  210.95  5476.8  224.07
#Mann=4,-1,0
  4251.9    0.05       0  4994.0   0.035       0  5000.0    0.05       0
  5276.3    0.16       0
Bank Sta=4994,5000
Exp/Cntr=0.3,0.1

Type RM Length L Ch R = 1,1537,1010,1010,1010
BEGIN DESCRIPTION:
UNT033 IN ROCK 2.0
END DESCRIPTION:
XS GIS Cut Line= 3
      3629696.86     10157323.75      3629981.43     10158180.97
      3630308.50     10158397.93
#Sta/Elev= 30
  4296.3  206.33  4324.6  205.63  4393.2  205.37  4424.9  204.33  4456.6  203.21
  4514.7  198.86  4557.5  197.36  4866.0  194.60  4947.3  194.88  4979.0  192.92
  4997.3  189.80  5000.1  189.30  5003.3  189.80  5010.6  191.05  5021.1  194.54
  5052.7  195.25  5080.1  195.12  5153.4  195.82  5185.1  196.74  5214.1  198.39
  5236.3  198.46  5291.8  201.04  5322.3  202.80  5439.6  207.70  5488.3  210.71
  5511.8  210.89  5532.9  213.18  5551.3  213.99  5561.0  214.62  5592.0  216.20
#Mann=8,-1,0
  4296.3    0.05       0  4866.0    0.12       0  4997.3    0.07       0
  5003.3    0.12       0  5080.1    0.05       0  5291.8    0.16       0
  5551.3    0.05       0  5561.0    0.16       0
Bank Sta=4997.3,5003.3
Exp/Cntr=0.3,0.1

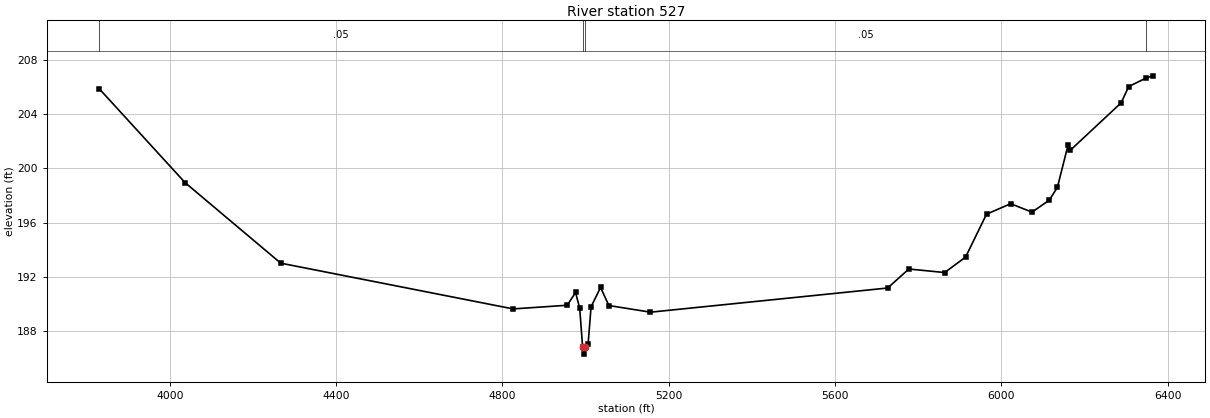
Type RM Length L Ch R = 1,527,0,0,0
BEGIN DESCRIPTION:
UNT033 IN ROCK 1.0
END DESCRIPTION:
XS GIS Cut Line= 4
      3629643.56     10157146.06      3629097.11     10157941.30
      3629119.32     10158430.00      3630176.65     10158647.68
#Sta/Elev= 30
  3830.4  205.85  4036.7  198.94  4266.7  193.01  4825.7  189.64  4955.8  189.91
  4975.8  190.85  4985.8  189.68  4992.8  186.81  4995.6  186.31  4998.8  186.81
  5005.9  187.03  5013.1  189.80  5035.9  191.22  5055.9  189.89  5156.0  189.40
  5726.4  191.18  5777.4  192.58  5863.6  192.32  5913.9  193.46  5964.2  196.62
  6022.4  197.39  6073.5  196.77  6115.2  197.65  6134.7  198.60  6160.4  201.72
  6165.5  201.32  6287.9  204.82  6306.2  206.02  6347.4  206.64  6364.0  206.81
#Mann=4,-1,0
  3830.4    0.05       0  4992.8    0.03       0  4998.8    0.05       0
  6347.4    0.16       0
Bank Sta=4992.8,4998.8
Exp/Cntr=0.3,0.1

Chan Stop Cuts=-1