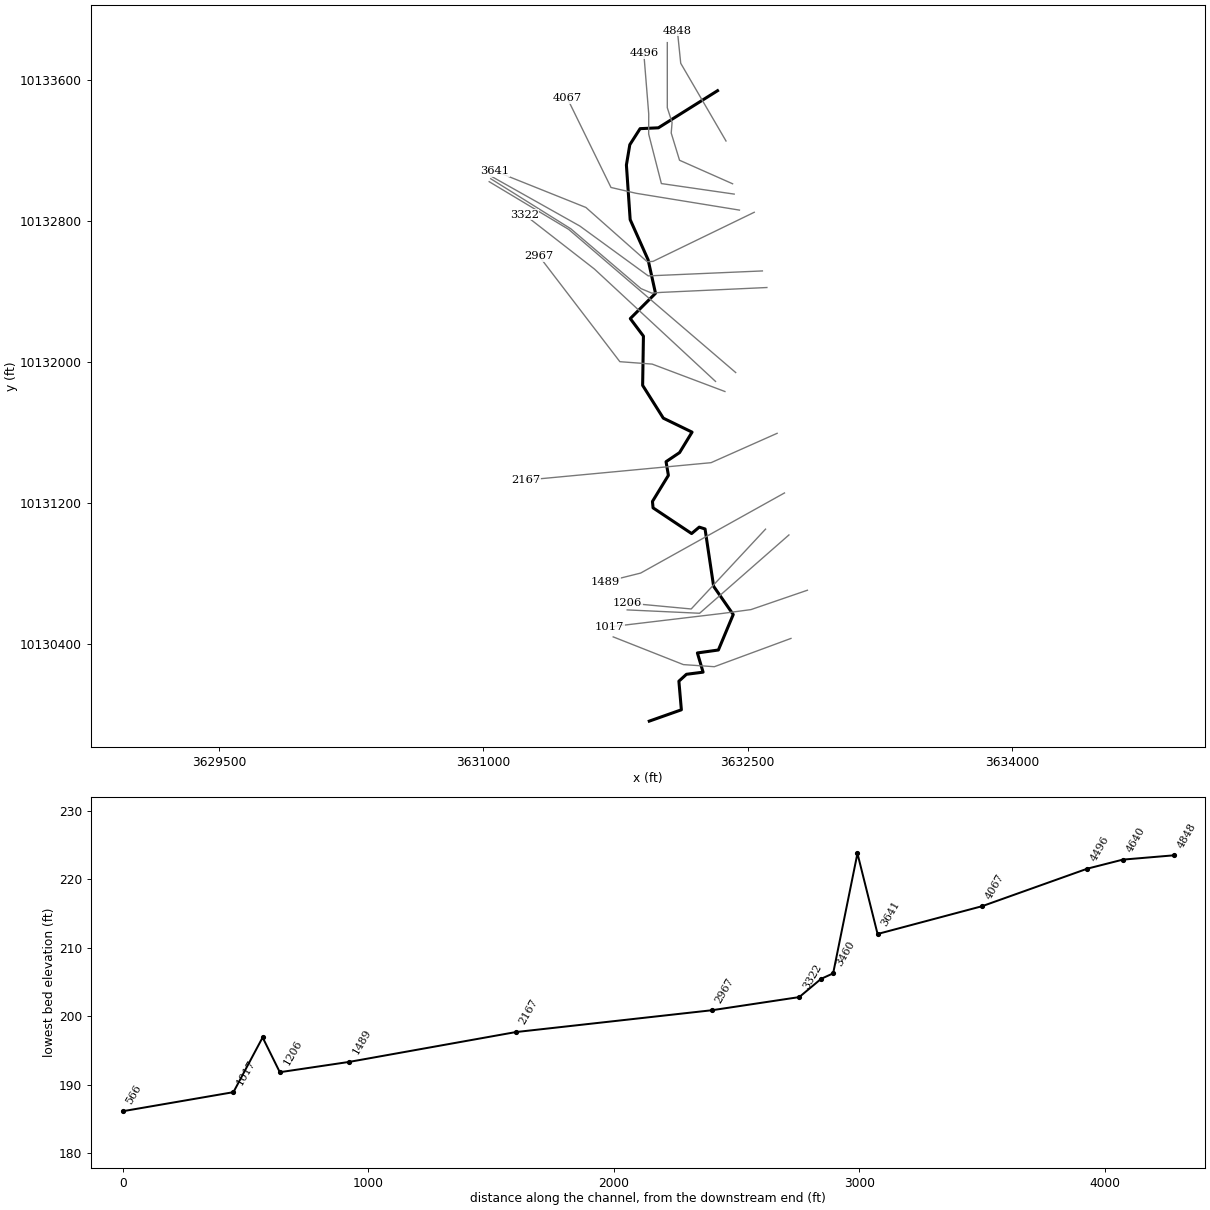
--- UNT042 IN ROCK.prj (project) ---

Proj Title=UNT042 IN ROCK Base Level Engineering
Current Plan=p01
Default Exp/Contr=0.3,0.1
English Units
Geom File=g01
Flow File=f01
Plan File=p01
Y Axis Title=Elevation
X Axis Title(PF)=Main Channel Distance
X Axis Title(XS)=Station
BEGIN DESCRIPTION:
UNT042 IN ROCK
END DESCRIPTION:
DSS Export Rating Curves= 0
DSS Export Rating Curve Sorted= 0
DSS Export Volume Flow Curves= 0
DXF OffsetX= 0
DXF OffsetY= 0
DXF ScaleX= 1
DXF ScaleY= 10

--- UNT042 IN ROCK.p01 (plan) ---

Plan Title=Multiple Run
Short Identifier=Multiple
Geom File=g01
Flow File=f01
Subcritical Flow
K Sum by GR= 0
Std Step Tol= 0.01
Critical Tol= 0.01
Num of Std Step Trials= 20
Max Error Tol= 0.3
Flow Tol Ratio= 0.001
Split Flow NTrial= 30
Split Flow Tol= 0.02
Split Flow Ratio= 0.02
Log Output Level= 0
Friction Slope Method= 1
Unsteady Friction Slope Method= 2
Unsteady Bridges Friction Slope Method= 1
Parabolic Critical Depth
Global Vel Dist=  1 , 1 , 1
Global Log Level= 0
CheckData=True
Encroach Param= -1, 0, 0, 0
BEGIN DESCRIPTION:
Multiple Run
END DESCRIPTION:

--- UNT042 IN ROCK.f01 (steady flow) ---

Flow Title=Multiple
Number of Profiles=7
Profile Names=10-year,25-year,50-year,1pct_min,100-year,1pct_plu,500-year
River Rch & RM= UNT042 IN ROCK,Reach-1,4848
     450     597     716     629     851    1151    1205
Boundary for River Rch & Prof#=UNT042 IN ROCK,Reach-1,1
Up Type=0
Dn Type=3
Dn Slope=0.005
Boundary for River Rch & Prof#=UNT042 IN ROCK,Reach-1,2
Up Type=0
Dn Type=3
Dn Slope=0.005
Boundary for River Rch & Prof#=UNT042 IN ROCK,Reach-1,3
Up Type=0
Dn Type=3
Dn Slope=0.005
Boundary for River Rch & Prof#=UNT042 IN ROCK,Reach-1,4
Up Type=0
Dn Type=3
Dn Slope=0.005
Boundary for River Rch & Prof#=UNT042 IN ROCK,Reach-1,5
Up Type=0
Dn Type=3
Dn Slope=0.005
Boundary for River Rch & Prof#=UNT042 IN ROCK,Reach-1,6
Up Type=0
Dn Type=3
Dn Slope=0.005
Boundary for River Rch & Prof#=UNT042 IN ROCK,Reach-1,7
Up Type=0
Dn Type=3
Dn Slope=0.005

--- UNT042 IN ROCK.g01 (geometry) ---

Geom Title=Existing Conditions
Program Version=4.10

River Reach=UNT042 IN ROCK  ,Reach-1
Reach XY= 30
       3632329.6     10133540.07       3631993.8     10133329.43
      3631890.07     10133324.69      3631831.61     10133233.39
      3631812.34     10133118.29      3631833.69     10132808.39
      3631935.43     10132580.53      3631977.53      10132390.1
      3631834.35     10132246.54        3631909.     10132146.94
      3631904.44     10131867.61      3632021.84     10131681.36
      3632184.97     10131602.05      3632114.11     10131485.93
      3632037.35     10131434.26      3632050.65     10131356.67
      3631960.17     10131208.67      3631963.64     10131172.22
      3632182.39     10131026.38      3632225.79     10131062.84
      3632258.78     10131052.42      3632307.39      10130726.9
      3632418.67     10130566.67      3632334.41     10130365.42
      3632215.27     10130348.67      3632247.56     10130239.68
      3632153.14     10130227.53      3632110.25      10130188.4
      3632124.28       10130026.      3631942.11     10129961.64

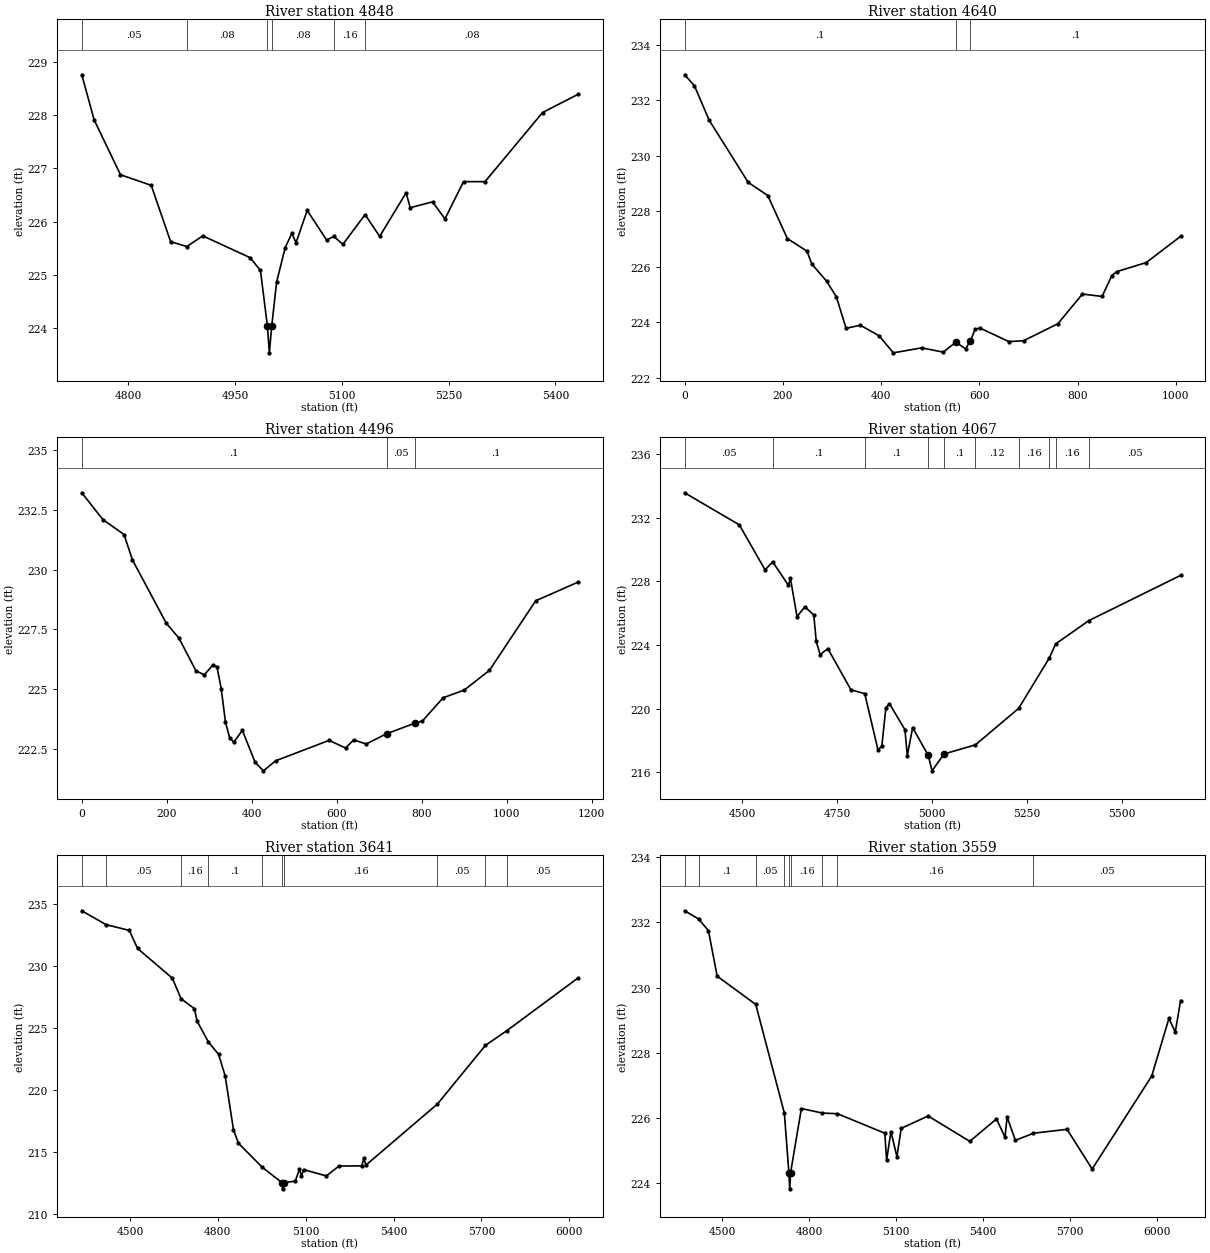
Type RM Length L Ch R = 1 ,4848    ,208,208,208
BEGIN DESCRIPTION:
UNT042 IN ROCK 11.0
END DESCRIPTION:
XS GIS Cut Line= 3
      3632377.63     10133254.65      3632120.67     10133695.65
      3632101.58     10133881.37
#Sta/Elev= 30
  4734.5  228.76  4751.9  227.91  4788.9  226.88  4832.1  226.68  4859.4  225.62
  4882.1  225.53  4904.6  225.73  4971.1  225.32  4985.6  225.08  4995.4  224.03
  4998.1  223.53  5001.4  224.03  5008.3  224.86  5020.4  225.51  5029.8  225.78
  5035.6   225.6  5051.3  226.21  5078.6  225.65  5088.7  225.72  5101.4  225.57
  5132.7  226.13  5153.1  225.72  5190.3  226.54  5196.1  226.26  5227.5  226.37
  5244.9  226.05    5271  226.75  5301.2  226.75  5382.1  228.05  5431.6  228.39
#Mann= 6 ,-1 , 0
  4734.5     .05       0  4882.1     .08       0  4995.4     .07       0
  5001.4     .08       0  5088.7     .16       0  5132.7     .08       0
Bank Sta=4995.4,5001.4
XS Rating Curve= 0 ,0
Exp/Cntr=0.3,0.1

Type RM Length L Ch R = 1 ,4640    ,144,144,144
BEGIN DESCRIPTION:
Mapping XS 5daf8975
END DESCRIPTION:
XS GIS Cut Line= 6
      3632415.03    10133011.787     3632113.891    10133145.286
      3632066.67    10133299.834     3632071.532    10133359.556
     3632044.448    10133443.584     3632044.448    10133813.028
#Sta/Elev= 30
       0232.914819.92719232.522649.81797231.2857129.5267229.0386169.3811 228.565
209.2355227.0144249.0898226.5625259.0534 226.097288.9442225.4827308.8714224.9222
328.7986223.7808357.6486223.8968396.1153223.5102424.9653222.8998482.6653 223.079
526.6373222.9251552.4038223.2872571.8639223.0412581.5939223.3199 591.324223.7438
 601.054223.7934 659.963223.3059 689.946223.3351759.9067223.9473809.8785225.0178
 849.856224.9309869.8447225.6847879.8391225.8248939.8053226.15181009.766227.0955
#Mann= 3 , 0 , 0
       0      .1       0552.4038     .05       0581.5939      .1       0
Bank Sta=552.4038,581.5939
XS Rating Curve= 0 ,0
Exp/Cntr=0.3,0.1

Type RM Length L Ch R = 1 ,4496    ,429,429,429
BEGIN DESCRIPTION:
Mapping XS a535573d
END DESCRIPTION:
XS GIS Cut Line= 5
     3632424.145    10132953.193      3632010.85    10133012.952
     3631938.676    10133294.235      3631939.03    10133408.105
     3631911.028    10133753.306
#Sta/Elev= 30
       0233.210549.71887232.090399.43774231.4647119.3253230.3995198.8755227.7554
228.7068227.1308268.4819225.7707288.3694225.5964 308.257226.0061318.2007225.9334
328.1445225.0172338.0883223.6301348.0321222.9586357.9758222.7867377.8634223.2774
407.6947221.9477427.3091221.5835456.3208222.0048582.0385222.8572620.7208222.5389
 640.062222.8803669.0737 222.704  717.16223.1333782.9876223.5701801.7955223.6723
850.3181 224.639899.8425224.9592 959.272225.78391068.226228.69531167.275229.4691
#Mann= 3 , 0 , 0
       0      .1       0  717.16     .05       0782.9876      .1       0
Bank Sta=717.16,782.9876
XS Rating Curve= 0 ,0
Exp/Cntr=0.3,0.1

Type RM Length L Ch R = 1 ,4067    ,426,426,426
BEGIN DESCRIPTION:
UNT042 IN ROCK 10.0
END DESCRIPTION:
XS GIS Cut Line= 4
      3632453.96     10132862.32       3631867.2      10132957.8
      3631724.84     10132990.79      3631476.83     10133497.21
#Sta/Elev= 30
  4349.2  233.56  4492.9  231.55  4560.8  228.72    4581  229.22  4622.4  227.74
  4627.4  228.21  4644.9  225.77  4665.2   226.4  4688.9  225.89  4695.5  224.22
  4705.7  223.39  4725.9  223.77  4786.7  221.18    4823  220.94  4857.7  217.42
  4867.8  217.63  4878.6  220.06    4888  220.31  4928.6  218.68    4935  217.05
  4948.9  218.81    4990  217.06    5000  216.09  5031.6  217.15  5113.9  217.72
  5227.6  220.01  5308.7  223.19  5325.3  224.07  5412.4  225.53  5653.7  228.37
#Mann= 10 ,-1 , 0
  4349.2     .05       0    4581      .1       0    4823      .1       0
    4990     .07       0  5031.6      .1       0  5113.9     .12       0
  5227.6     .16       0  5308.7      .1       0  5325.3     .16       0
  5412.4     .05       0
Bank Sta=4990,5031.6
XS Rating Curve= 0 ,0
Exp/Cntr=0.3,0.1

Type RM Length L Ch R = 1 ,3641    ,82,82,82
BEGIN DESCRIPTION:
UNT042 IN ROCK 8.0
END DESCRIPTION:
XS GIS Cut Line= 5
      3632537.97     10132849.99      3631963.45     10132571.36
      3631930.47     10132569.19      3631582.38     10132877.35
      3631065.62     10133084.22
#Sta/Elev= 30
  4335.8  234.44  4418.8  233.32  4497.9  232.86  4526.3   231.4  4644.7  229.01
  4674.9  227.34  4720.2  226.55  4729.4  225.54  4768.2  223.85  4802.7  222.87
  4825.2  221.13  4853.6  216.79  4870.4   215.7  4950.9  213.78  5018.9  212.52
  5021.7  212.02  5024.9  212.52  5064.6  212.64  5078.8   213.6  5085.5  213.07
    5093  213.57  5170.8  213.06  5213.5  213.86  5291.3  213.87  5298.8  214.49
  5305.5  213.93  5549.8  218.86  5713.7  223.59  5787.1  224.78  6028.9  229.01
#Mann= 10 ,-1 , 0
  4335.8     .08       0  4418.8     .05       0  4674.9     .16       0
  4768.2      .1       0  4950.9     .16       0  5018.9     .07       0
  5024.9     .16       0  5549.8     .05       0  5713.7     .16       0
  5787.1     .05       0
Bank Sta=5018.9,5024.9
XS Rating Curve= 0 ,0
Exp/Cntr=0.3,0.1

Type RM Length L Ch R = 1 ,3559    ,99,99,99
BEGIN DESCRIPTION:
Mapping XS 1df00469
END DESCRIPTION:
XS GIS Cut Line= 4
      3632584.21     10132517.05      3631936.27     10132488.92
      3631548.01     10132771.89      3631041.91     10133056.26
#Sta/Elev= 30
  4370.7  232.36  4418.7  232.11  4452.9  231.75  4482.9  230.35  4615.9  229.48
  4714.5  226.14  4730.1  224.31  4732.9  223.81  4736.1  224.31  4773.2  226.28
  4845.7  226.14  4897.5  226.12  5060.8  225.52    5067  224.69  5081.7  225.57
  5102.5   224.8  5117.2  225.67    5210  226.05  5353.6  225.27  5445.6  225.96
  5474.9   225.4  5482.2  226.02  5510.8   225.3    5573  225.52  5688.7  225.64
  5775.4  224.42  5980.7  227.28    6040  229.05  6061.7  228.63  6080.2   229.6
#Mann= 9 ,-1 , 0
  4370.7     .08       0  4418.7      .1       0  4615.9     .05       0
  4714.5     .16       0  4730.1     .07       0  4736.1     .16       0
  4845.7      .1       0  4897.5     .16       0    5573     .05       0
Bank Sta=4730.1,4736.1
XS Rating Curve= 0 ,0
Exp/Cntr=0.3,0.1

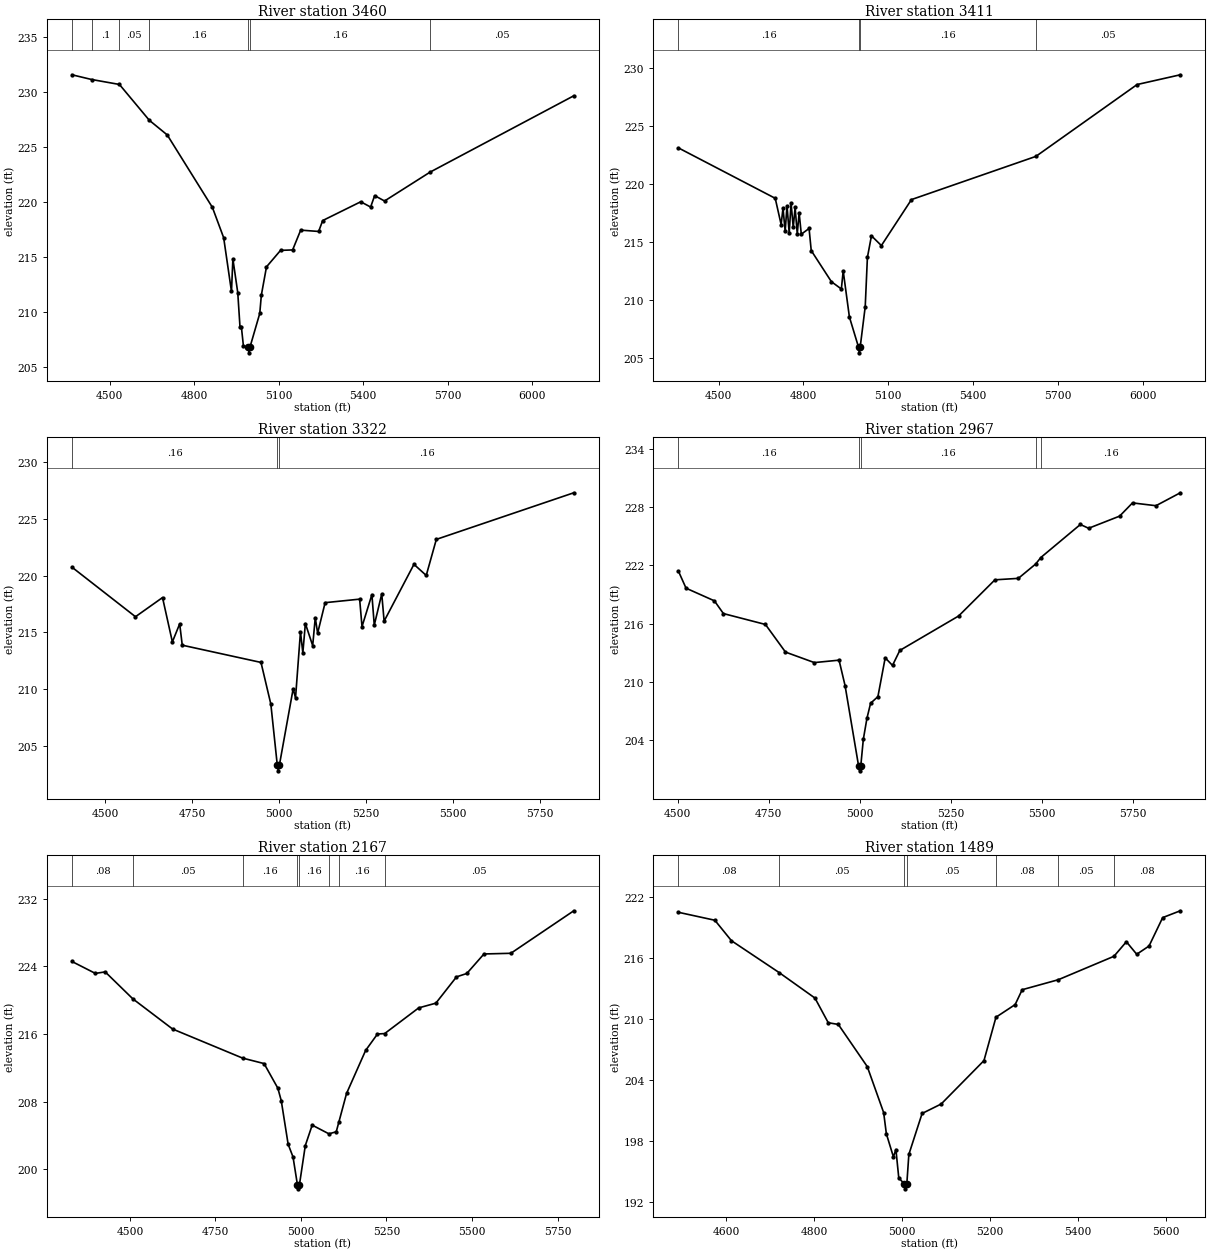
Type RM Length L Ch R = 1 ,3460    ,49,49,49
BEGIN DESCRIPTION:
UNT042 IN ROCK 7.0
END DESCRIPTION:
XS GIS Cut Line= 6
      3632609.72     10132422.92       3632011.2     10132395.32
      3631956.25     10132391.15      3631895.18     10132416.67
      3631496.79     10132756.27      3631042.05      10133040.5
#Sta/Elev= 30
  4366.5  231.55  4436.3  231.12  4534.9  230.67    4641  227.41  4704.5  226.08
  4864.7  219.49  4904.7  216.73  4932.4  211.84  4937.4   214.8  4954.7  211.73
  4962.7  208.58  4967.7  208.58  4974.8  206.87  4991.8  206.76  4994.6  206.26
  4997.8  206.76  5032.8  209.85  5038.3   211.5  5056.6  214.08  5106.5  215.58
  5149.3  215.62  5177.9  217.42  5241.6   217.3  5255.9  218.29  5390.9     220
    5426  219.52  5440.3  220.56  5475.4  220.07  5637.2   222.7  6146.7  229.64
#Mann= 7 ,-1 , 0
  4366.5     .08       0  4436.3      .1       0  4534.9     .05       0
    4641     .16       0  4991.8     .07       0  4997.8     .16       0
  5637.2     .05       0
Bank Sta=4991.8,4997.8
XS Rating Curve= 0 ,0
Exp/Cntr=0.3,0.1

Type RM Length L Ch R = 1 ,3411    ,89,89,89
BEGIN DESCRIPTION:
Mapping XS b6aef5a4
END DESCRIPTION:
XS GIS Cut Line= 3
      3632432.71      10131940.3      3631484.79      10132752.8
      3631033.39     10133023.64
#Sta/Elev= 30
  4358.2  223.11  4700.4  218.77  4721.3  216.51  4727.9  217.93  4735.5  215.93
  4742.1  218.12  4749.8  215.77  4756.4  218.37  4764.1  216.26  4770.7  217.99
  4778.3   215.7  4784.9  217.53  4792.6  215.68  4820.1  216.17  4827.7  214.27
    4899  211.59  4934.2  210.96  4940.8  212.51  4962.7  208.55  4994.9  205.96
  4997.6  205.46  5000.9  205.96  5018.7  209.44  5026.4  213.68  5040.7  215.54
  5075.8   214.7  5182.2  218.66  5622.2  222.38  5980.3  228.57  6133.1  229.41
#Mann= 4 ,-1 , 0
  4358.2     .16       0  4994.9     .07       0  5000.9     .16       0
  5622.2     .05       0
Bank Sta=4994.9,5000.9
XS Rating Curve= 0 ,0
Exp/Cntr=0.3,0.1

Type RM Length L Ch R = 1 ,3322    ,355,355,355
BEGIN DESCRIPTION:
Mapping XS 3e09edd0
END DESCRIPTION:
XS GIS Cut Line= 3
      3632318.13     10131889.95      3631630.63     10132527.97
      3631232.98     10132837.25
#Sta/Elev= 30
  4405.1  220.75  4587.6  216.38  4665.3  218.07  4693.6  214.16  4714.6  215.75
    4722  213.87  4948.2  212.35  4976.5  208.67    4995  203.29  4997.8  202.79
    5001  203.29  5040.6  210.03  5047.4  209.22  5061.6  215.05  5068.4  213.19
  5075.7  215.78  5096.7  213.83  5104.1   216.3  5110.9  214.93  5132.4  217.62
  5231.6  217.93  5238.4  215.51  5266.8  218.33  5273.6  215.64  5295.1  218.39
  5301.9  215.99  5387.6     221  5422.9  220.02  5451.9   223.2  5846.8  227.31
#Mann= 3 ,-1 , 0
  4405.1     .16       0    4995     .07       0    5001     .16       0
Bank Sta=4995,5001
XS Rating Curve= 0 ,0
Exp/Cntr=0.3,0.1

Type RM Length L Ch R = 1 ,2967    ,800,800,800
BEGIN DESCRIPTION:
UNT042 IN ROCK 6.0
END DESCRIPTION:
XS GIS Cut Line= 4
      3632371.55     10131832.65      3631958.58     10131988.28
      3631775.16     10132001.93      3631316.98     10132600.69
#Sta/Elev= 30
    4502  221.39  4522.8  219.65  4600.7  218.35  4625.5  217.04    4741  215.92
  4796.1  213.08  4875.4     212  4943.3  212.25  4959.8  209.64    4997  201.37
  4999.7  200.87    5003  201.37    5010  204.11    5020  206.28    5030  207.82
  5050.1   208.5  5070.1  212.49  5090.2  211.71  5110.3  213.25  5271.9  216.79
  5371.7  220.51    5436  220.66  5483.8  222.14  5497.7   222.8  5606.5   226.2
  5629.2  225.81  5714.4  227.06  5749.8  228.42  5814.2  228.13  5881.2  229.46
#Mann= 5 ,-1 , 0
    4502     .16       0    4997     .07       0    5003     .16       0
  5483.8     .05       0  5497.7     .16       0
Bank Sta=4997,5003
XS Rating Curve= 0 ,0
Exp/Cntr=0.3,0.1

Type RM Length L Ch R = 1 ,2167    ,678,678,678
BEGIN DESCRIPTION:
UNT042 IN ROCK 4.0
END DESCRIPTION:
XS GIS Cut Line= 3
      3632667.78     10131595.33      3632292.81     10131428.67
      3631240.69     10131329.71
#Sta/Elev= 30
  4330.5  224.57    4399  223.16  4427.7  223.34  4508.5  220.15  4624.7  216.58
  4829.3  213.14  4892.2  212.49  4932.4  209.58  4942.4   208.1  4962.5  202.95
  4976.8  201.44  4989.6  198.17  4992.4  197.67  4995.6  198.17  5012.7  202.79
  5032.8  205.21  5081.7  204.18  5103.1  204.42  5110.6  205.54  5133.3  208.96
  5189.1  214.05  5223.7  215.99  5244.7  216.04  5344.2  219.08  5394.4  219.64
  5454.7  222.75  5484.8  223.15    5535  225.46  5613.6  225.54  5797.6  230.57
#Mann= 8 ,-1 , 0
  4330.5     .08       0  4508.5     .05       0  4829.3     .16       0
  4989.6     .07       0  4995.6     .16       0  5081.7     .05       0
  5110.6     .16       0  5244.7     .05       0
Bank Sta=4989.6,4995.6
XS Rating Curve= 0 ,0
Exp/Cntr=0.3,0.1

Type RM Length L Ch R = 1 ,1489    ,283,283,283
BEGIN DESCRIPTION:
UNT042 IN ROCK 3.0
END DESCRIPTION:
XS GIS Cut Line= 3
       3632709.5     10131256.81      3631893.15     10130802.06
      3631693.17     10130752.07
#Sta/Elev= 30
  4491.4  220.46  4574.1  219.68  4611.8  217.67  4720.3  214.54  4801.6  212.04
  4831.8  209.62  4854.7  209.45  4920.5  205.31  4957.7   200.8  4963.9  198.71
  4979.9  196.45  4985.6  197.17  4992.1  194.38  5004.4  193.81  5007.1  193.31
  5010.4  193.81    5015  196.69  5045.1  200.71  5088.5  201.64  5185.7   205.9
    5213  210.16  5256.6   211.4  5272.6  212.86  5354.6  213.84  5481.1  216.14
  5509.4  217.57  5532.9  216.34  5560.9  217.15  5591.9  219.94    5632  220.61
#Mann= 7 ,-1 , 0
  4491.4     .08       0  4720.3     .05       0  5004.4     .04       0
  5010.4     .05       0    5213     .08       0  5354.6     .05       0
  5481.1     .08       0
Bank Sta=5004.4,5010.4
XS Rating Curve= 0 ,0
Exp/Cntr=0.3,0.1

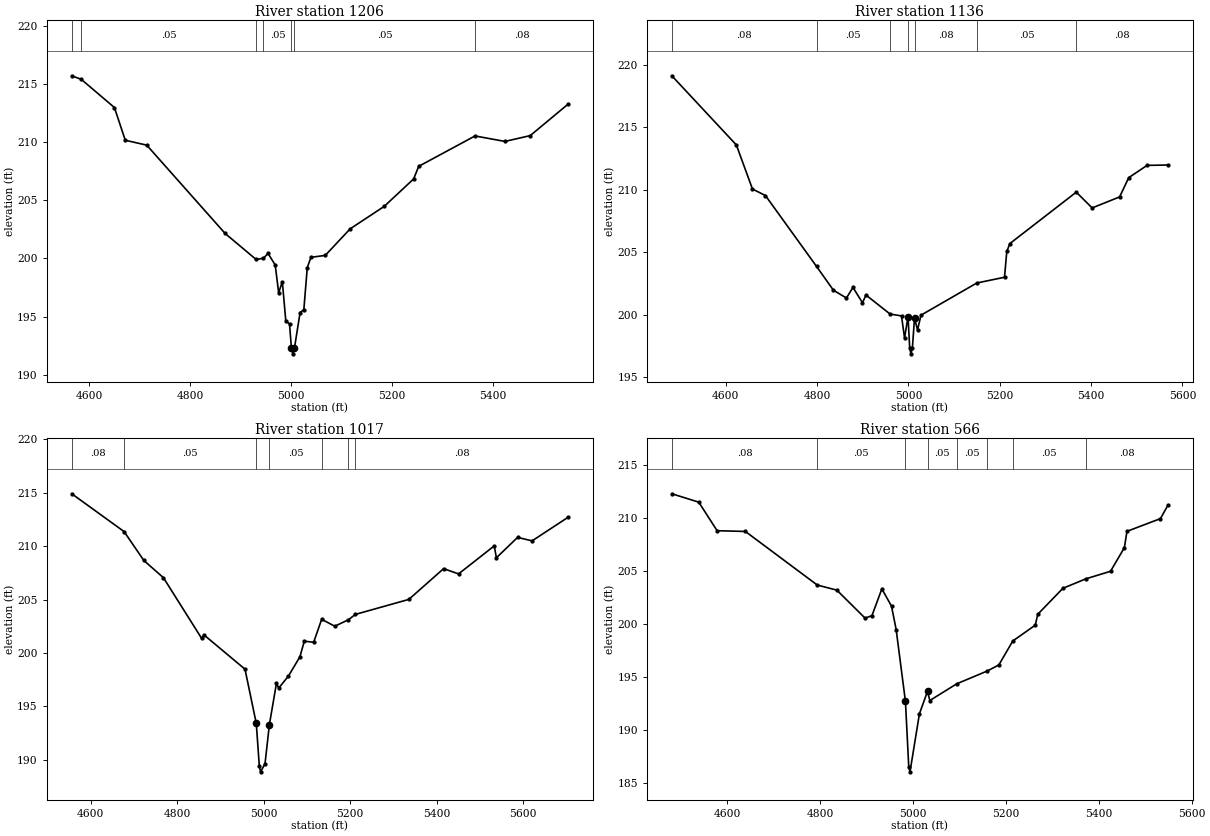
Type RM Length L Ch R = 1 ,1206    ,70,70,70
BEGIN DESCRIPTION:
Mapping XS 3646011f
END DESCRIPTION:
XS GIS Cut Line= 3
      3632601.99     10131051.42       3632180.1     10130598.29
      3631818.11     10130632.14
#Sta/Elev= 30
  4565.3  215.69  4584.2  215.38  4649.8  212.96  4671.3  210.15  4713.8  209.73
  4869.2  202.14  4930.5  199.91  4945.1  200.01  4954.2  200.43  4968.4  199.43
  4975.2  197.05  4982.5     198  4989.4  194.61  4996.7  194.37  5000.5   192.3
  5003.3   191.8  5006.5   192.3  5017.7  195.35  5025.1   195.6  5031.9  199.21
  5039.2  200.09  5067.6  200.26  5116.9  202.54  5184.4  204.47  5242.7  206.83
  5252.7  207.91  5364.3  210.52  5423.5  210.05  5473.7  210.55    5548  213.23
#Mann= 7 ,-1 , 0
  4565.3     .08       0  4584.2     .05       0  4930.5     .08       0
  4945.1     .05       0  5000.5     .04       0  5006.5     .05       0
  5364.3     .08       0
Bank Sta=5000.5,5006.5
XS Rating Curve= 0 ,0
Exp/Cntr=0.3,0.1

Type RM Length L Ch R = 1 ,1136    ,119,119,119
BEGIN DESCRIPTION:
Mapping XS c7306c2f
END DESCRIPTION:
XS GIS Cut Line= 3
      3632734.83     10131018.46      3632227.85     10130573.98
      3631816.72     10130593.06
#Sta/Elev= 30
  4482.1  219.11  4623.4  213.58  4658.6  210.06    4687  209.54    4799  203.87
  4835.9  201.97  4864.4  201.35  4878.6   202.2  4899.5  200.97  4907.1  201.59
  4959.9  200.07  4984.9  199.92  4991.6  198.16  4999.2  199.86  5002.8  197.39
  5005.6  196.89  5008.8  197.39  5013.4  199.74    5020   198.8  5027.6  199.98
  5149.7  202.55  5210.4  203.01  5215.4  205.07  5222.1   205.7  5367.5  209.81
  5402.3  208.55  5462.4  209.43  5482.4  210.97  5522.5  211.95  5567.9  211.98
#Mann= 7 ,-1 , 0
  4482.1     .08       0    4799     .05       0  4959.9     .08       0
  4999.2     .05       0  5013.4     .08       0  5149.7     .05       0
  5367.5     .08       0
Bank Sta=4999.2,5013.4
XS Rating Curve= 0 ,0
Exp/Cntr=0.3,0.1

Type RM Length L Ch R = 1 ,1017    ,451,451,451
BEGIN DESCRIPTION:
UNT042 IN ROCK 2.0
END DESCRIPTION:
XS GIS Cut Line= 4
      3632839.71     10130704.72      3632519.51     10130594.81
      3632358.74     10130573.17      3631717.05     10130496.66
#Sta/Elev= 30
  4556.1  214.91  4677.1  211.37  4722.7  208.67  4768.1  207.05  4856.5  201.37
  4861.8   201.7  4956.7  198.49  4982.8  193.41  4989.9  189.38  4992.7  188.88
    5003  189.64  5013.1   193.3  5029.5  197.18  5034.6  196.72  5056.9  197.83
  5083.7  199.65  5093.8  201.11  5115.5  201.01    5134  203.16  5164.3  202.51
    5196  203.12  5212.1  203.62  5335.5  205.02    5416   207.9  5450.6  207.41
  5533.1  210.03  5538.1  208.92  5587.2  210.83  5620.6   210.5  5703.1  212.69
#Mann= 7 ,-1 , 0
  4556.1     .08       0  4677.1     .05       0  4982.8     .04       0
  5013.1     .05       0    5134     .08       0    5196     .05       0
  5212.1     .08       0
Bank Sta=4982.8,5013.1
XS Rating Curve= 0 ,0
Exp/Cntr=0.3,0.1

Type RM Length L Ch R = 1 ,566     ,0,0,0
BEGIN DESCRIPTION:
UNT042 IN ROCK 1.0
END DESCRIPTION:
XS GIS Cut Line= 4
      3632746.47     10130431.17       3632311.4      10130270.6
      3632135.62     10130282.53      3631737.42     10130439.86
#Sta/Elev= 30
  4480.5  212.29  4538.5   211.5    4578  208.81  4638.9  208.74  4793.7  203.69
  4835.9  203.21  4896.7  200.57  4911.5  200.81  4932.8  203.33  4953.6   201.7
  4963.6   199.5  4983.6  192.72  4990.7  186.59  4993.4  186.09  5013.7  191.56
  5031.1  193.67  5036.1  192.81  5093.9  194.38  5159.2  195.58  5184.7  196.16
  5214.8  198.42  5263.2  199.91  5268.5  200.93  5322.6  203.38  5371.8  204.27
  5425.3  204.99  5455.2  207.22  5460.6  208.75  5532.8  209.95  5548.6  211.19
#Mann= 8 ,-1 , 0
  4480.5     .08       0  4793.7     .05       0  4983.6    .035       0
  5031.1     .05       0  5093.9     .05       0  5159.2     .08       0
  5214.8     .05       0  5371.8     .08       0
Bank Sta=4983.6,5031.1
XS Rating Curve= 0 ,0
Exp/Cntr=0.3,0.1

Chan Stop Cuts=-1
Use User Specified Reach Order=0
Composite Channel Slope=5