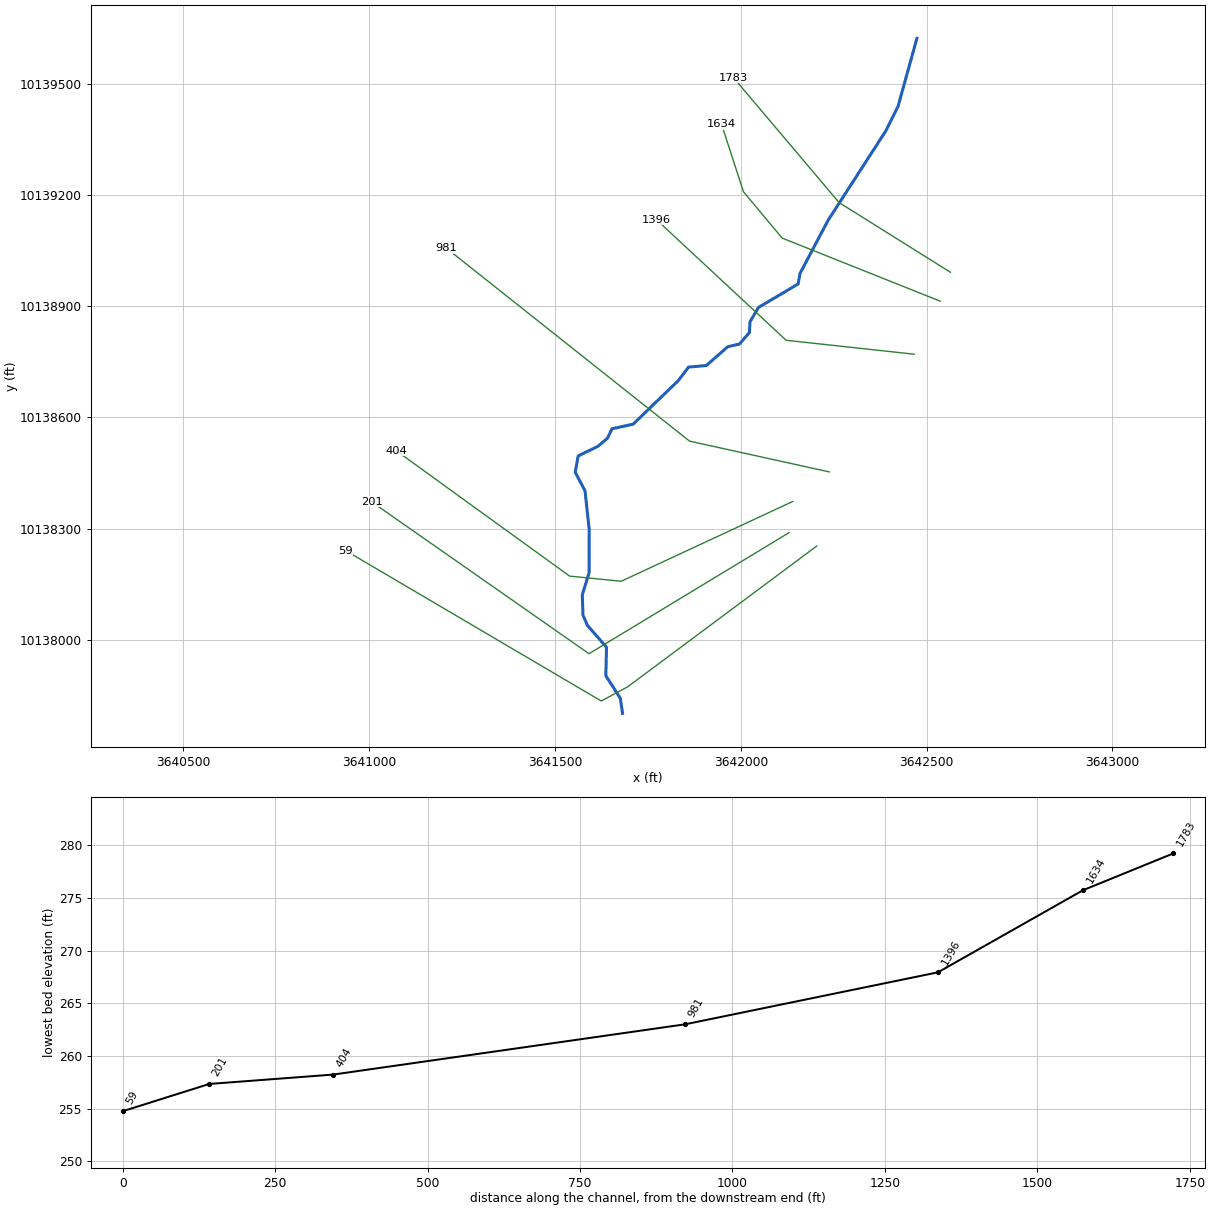
--- UNT045 IN ROCK.prj (project) ---

Proj Title=UNT045 IN ROCK Base Level Engineering
Current Plan=p01
Default Exp/Contr=0.3,0.1
English Units
Geom File=g01
Flow File=f01
Plan File=p01
Y Axis Title=Elevation
X Axis Title(PF)=Main Channel Distance
X Axis Title(XS)=Station
BEGIN DESCRIPTION:
UNT045 IN ROCK
END DESCRIPTION:
DSS Export Rating Curves= 0
DSS Export Rating Curve Sorted= 0
DSS Export Volume Flow Curves= 0
DXF OffsetX= 0
DXF OffsetY= 0
DXF ScaleX= 1
DXF ScaleY= 10

--- UNT045 IN ROCK.p01 (plan) ---

Plan Title=Multiple Run
Short Identifier=Multiple
Geom File=g01
Flow File=f01
Subcritical Flow
K Sum by GR= 0
Std Step Tol= 0.01
Critical Tol= 0.01
Num of Std Step Trials= 20
Max Error Tol= 0.3
Flow Tol Ratio= 0.001
Split Flow NTrial= 30
Split Flow Tol= 0.02
Split Flow Ratio= 0.02
Log Output Level= 0
Friction Slope Method= 1
Unsteady Friction Slope Method= 2
Unsteady Bridges Friction Slope Method= 1
Parabolic Critical Depth
Global Vel Dist=  1 , 1 , 1
Global Log Level= 0
CheckData=True
Encroach Param= -1, 0, 0, 0
BEGIN DESCRIPTION:
Multiple Run
END DESCRIPTION:

--- UNT045 IN ROCK.f01 (steady flow) ---

Flow Title=Multiple
Program Version=4.10
Number of Profiles= 7
Profile Names=10-year,25-year,50-year,1pct_min,100-year,1pct_plu,500-year
River Rch & RM=UNT045 IN ROCK,Reach-1         ,1783
     125     151     170     141     191     258     239
Boundary for River Rch & Prof#=UNT045 IN ROCK,Reach-1         , 1
Up Type= 0
Dn Type= 3
Dn Slope=0.005
Boundary for River Rch & Prof#=UNT045 IN ROCK,Reach-1         , 2
Up Type= 0
Dn Type= 3
Dn Slope=0.005
Boundary for River Rch & Prof#=UNT045 IN ROCK,Reach-1         , 3
Up Type= 0
Dn Type= 3
Dn Slope=0.005
Boundary for River Rch & Prof#=UNT045 IN ROCK,Reach-1         , 4
Up Type= 0
Dn Type= 3
Dn Slope=0.005
Boundary for River Rch & Prof#=UNT045 IN ROCK,Reach-1         , 5
Up Type= 0
Dn Type= 3
Dn Slope=0.005
Boundary for River Rch & Prof#=UNT045 IN ROCK,Reach-1         , 6
Up Type= 0
Dn Type= 3
Dn Slope=0.005
Boundary for River Rch & Prof#=UNT045 IN ROCK,Reach-1         , 7
Up Type= 0
Dn Type= 3
Dn Slope=0.005
DSS Import GetInterval= 0
DSS Import GetPeak= 0
DSS Import FillOption= 0

--- UNT045 IN ROCK.g01 (geometry) ---

Geom Title=Existing Conditions
Program Version=4.10

River Reach=UNT045 IN ROCK  ,Reach-1
Reach XY= 30
      3642473.78     10139621.91        3642423.     10139438.32
      3642389.69      10139371.7      3642234.89     10139131.38
      3642159.37     10138988.15      3642154.17     10138959.51
      3642047.39     10138896.14      3642024.42     10138857.09
      3642023.28     10138828.63       3641996.2     10138797.38
      3641964.95     10138790.44      3641907.31     10138739.74
      3641859.36     10138735.25      3641830.92     10138698.08
      3641710.09     10138581.41      3641653.29     10138569.06
      3641641.34     10138543.91      3641616.34     10138522.38
      3641562.27     10138495.65       3641554.3     10138451.74
      3641580.58     10138402.08      3641591.91     10138297.38
      3641591.72     10138181.16      3641573.35       10138121.
      3641575.19     10138066.34      3641587.09     10138038.81
       3641638.5     10137980.04      3641636.64     10137903.01
      3641675.58      10137842.3      3641681.66     10137801.51

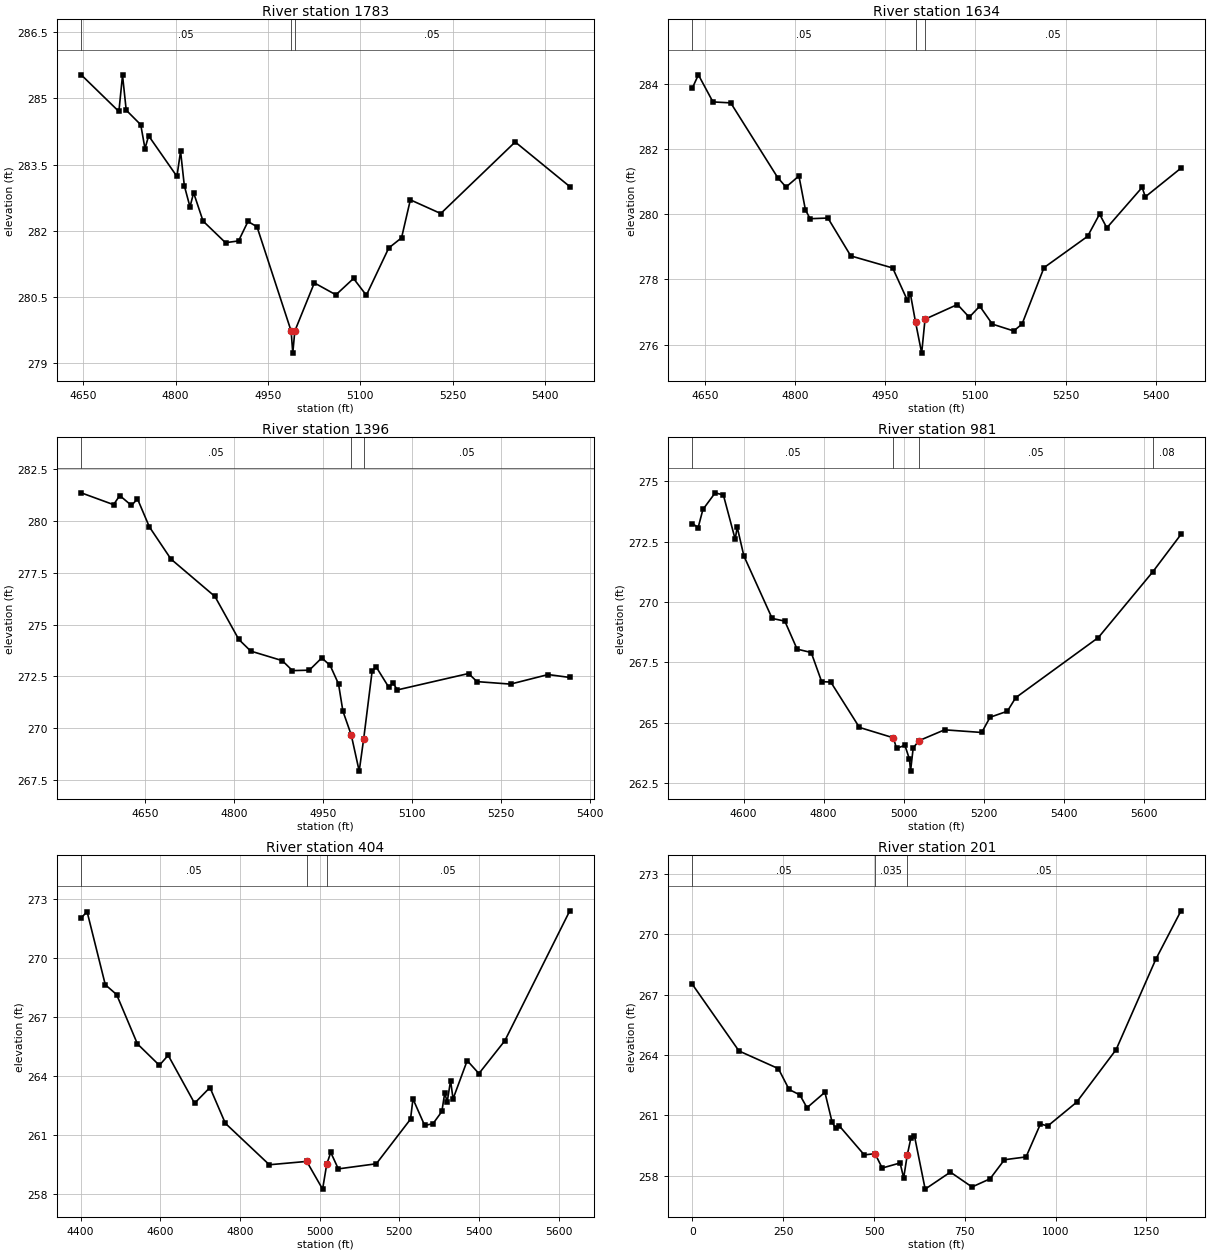
Type RM Length L Ch R = 1 ,1783    ,148,148,148
BEGIN DESCRIPTION:
UNT045 IN ROCK 4.0
END DESCRIPTION:
XS GIS Cut Line= 3
      3642564.02     10138991.01      3642264.15      10139179.2
      3641980.71     10139515.31
#Sta/Elev= 30
  4646.7  285.53  4707.9   284.7  4713.8  285.52  4719.8  284.73  4743.4   284.4
  4750.3  283.86  4756.2  284.15  4802.2  283.23  4808.1   283.8  4814.2  283.02
  4823.4  282.54  4829.3  282.86  4844.6  282.22  4881.1  281.73  4902.3  281.77
  4917.6  282.21  4932.3  282.09  4987.7  279.73  4990.4  279.23  4993.7  279.73
  5025.4  280.82  5060.5  280.55  5089.1  280.92  5109.9  280.54  5146.3  281.61
  5167.1  281.84  5181.4   282.7  5230.8  282.39  5351.7  284.01  5440.4     283
#Mann= 3 ,-1 , 0
  4646.7     .05       0  4987.7     .03       0  4993.7     .05       0
Bank Sta=4987.7,4993.7
XS Rating Curve= 0 ,0
Exp/Cntr=0.3,0.1

Type RM Length L Ch R = 1 ,1634    ,238,238,238
BEGIN DESCRIPTION:
Mapping XS 963544c9
END DESCRIPTION:
XS GIS Cut Line= 4
      3642536.53     10138913.08      3642111.18     10139083.22
      3642007.02     10139208.22        3641948.     10139390.47
#Sta/Elev= 30
  4629.4  283.87  4639.3  284.27  4663.5  283.44  4693.1  283.41  4771.2  281.12
    4785  280.83  4806.5  281.17  4817.3  280.13  4825.1  279.86  4854.7  279.88
  4892.7  278.72  4962.4  278.35  4986.6  277.37    4992  277.54  5000.4  276.69
  5010.6  275.74  5016.2  276.78  5070.1  277.23  5089.7  276.84  5107.2  277.18
  5128.1  276.63  5163.6  276.42  5177.5  276.63    5214  278.36  5286.5  279.32
  5306.4     280  5318.5  279.58  5377.2  280.82  5382.5  280.53  5441.8  281.41
#Mann= 3 , 0 , 0
  4629.4     .05       0  5000.4    .035       0  5016.2     .05       0
Bank Sta=5000.4,5016.2
XS Rating Curve= 0 ,0
Exp/Cntr=0.3,0.1

Type RM Length L Ch R = 1 ,1396    ,415,415,415
BEGIN DESCRIPTION:
UNT045 IN ROCK 3.0
END DESCRIPTION:
XS GIS Cut Line= 3
      3642466.42     10138770.11      3642121.79     10138807.68
       3641772.4     10139133.34
#Sta/Elev= 30
  4541.7  281.34  4596.3  280.77  4606.7  281.21  4626.5  280.73  4636.6  281.05
  4656.7   279.7  4693.1  278.15  4767.3  276.35  4807.6  274.28  4827.7  273.72
  4880.9  273.26  4898.1  272.78  4926.5   272.8  4947.5  273.39  4961.7  273.03
  4975.8  272.14  4983.2  270.83  4997.3  269.68  5010.7  267.94  5018.3   269.5
  5032.5  272.75  5039.3  272.96  5060.8  271.97  5067.7  272.19    5075  271.85
  5195.2  272.64  5209.4  272.25    5266  272.13  5329.5  272.59    5366  272.45
#Mann= 3 , 0 , 0
  4541.7     .05       0  4997.3    .035       0  5018.3     .05       0
Bank Sta=4997.3,5018.3
XS Rating Curve= 0 ,0
Exp/Cntr=0.3,0.1

Type RM Length L Ch R = 1 ,981     ,577,577,577
BEGIN DESCRIPTION:
UNT045 IN ROCK 2.0
END DESCRIPTION:
XS GIS Cut Line= 3
      3642237.67     10138452.79      3641861.95     10138535.66
      3641206.96     10139056.53
#Sta/Elev= 30
  4471.9  273.25  4486.2  273.08  4498.1  273.83  4528.8  274.52  4549.3  274.43
  4578.8   272.6  4583.9   273.1  4600.5  271.91  4671.3  269.32  4702.9  269.21
  4733.6  268.05  4768.9  267.91  4795.1   266.7  4817.7  266.69  4889.4  264.81
  4974.3  264.38  4982.3  263.94  5003.1  264.07  5014.5   263.5  5017.3     263
  5023.9  263.96  5038.3  264.26  5102.4  264.71  5195.3   264.6  5216.1  265.23
  5259.4  265.48  5280.2  266.04  5486.9  268.53    5623  271.25  5693.5   272.8
#Mann= 4 ,-1 , 0
  4471.9     .05       0  4974.3    .035       0  5038.3     .05       0
    5623     .08       0
Bank Sta=4974.3,5038.3
XS Rating Curve= 0 ,0
Exp/Cntr=0.3,0.1

Type RM Length L Ch R = 1 ,404     ,203,203,203
BEGIN DESCRIPTION:
Mapping XS 749e20a5
END DESCRIPTION:
XS GIS Cut Line= 4
      3642139.87     10138373.07      3641678.06     10138157.79
      3641539.17     10138171.68      3641072.17     10138510.21
#Sta/Elev= 30
  4401.7  272.03  4416.4  272.35  4462.1  268.63  4490.5  268.13  4542.7  265.62
  4597.8  264.53  4619.9  265.04  4686.1   262.6  4724.7   263.4  4763.3  261.58
  4873.7  259.47  4967.5  259.64  5007.4  258.23  5017.7  259.49  5027.8   260.1
  5046.8  259.26  5142.1  259.52    5228  261.79  5234.1  262.82  5263.5  261.47
  5284.4  261.56  5306.6  262.18  5313.8  263.12    5320  262.67  5328.5  263.75
  5334.7  262.82  5370.2  264.77  5399.6  264.11  5464.6  265.78  5627.6  272.39
#Mann= 3 , 0 , 0
  4401.7     .05       0  4967.5    .035       0  5017.7     .05       0
Bank Sta=4967.5,5017.7
XS Rating Curve= 0 ,0
Exp/Cntr=0.3,0.1

Type RM Length L Ch R = 1 ,201     ,142,142,142
XS GIS Cut Line= 3
     3642129.599    10138288.768     3641591.404    10137962.379
     3641006.335    10138372.102
#Sta/Elev= 30
       0267.4995128.1548264.1979236.5934263.3219266.1676262.2867295.7418262.0176
315.4579261.3803364.7482262.1471384.4643260.6743394.3224260.3645404.1804 260.484
473.1868259.0381 502.761259.1013522.4771258.3871571.7674258.6386581.6255 257.896
591.4835259.0315601.3416259.8563611.1996259.9939640.8362257.3402710.2789258.1846
769.8012257.4469819.4031257.8512859.0847258.7993 918.607258.9385958.2885260.5781
978.1293260.46991057.492261.64751166.617264.26591275.741 268.7451345.184271.1533
#Mann= 3 , 0 , 0
       0     .05       0 502.761    .035       0591.4835     .05       0
Bank Sta=502.761,591.4835
XS Rating Curve= 0 ,0
Exp/Cntr=0.3,0.1

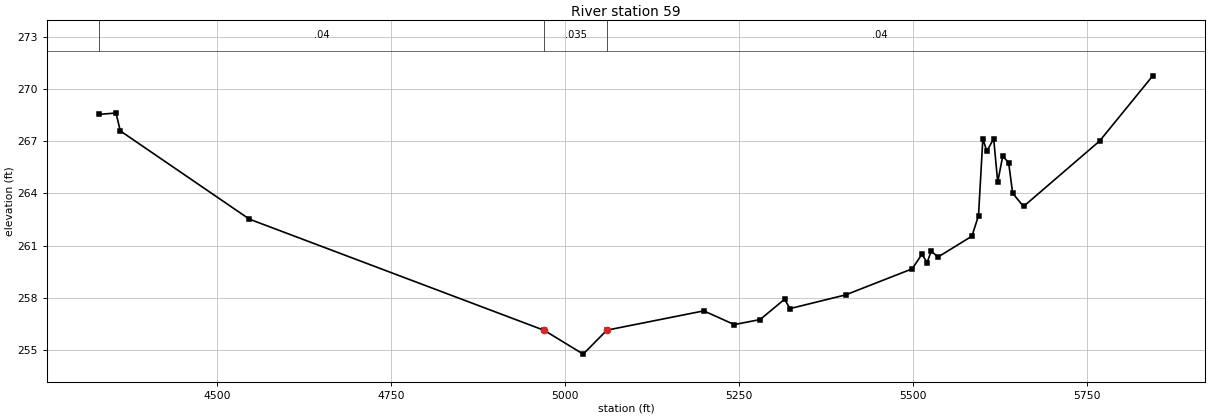
Type RM Length L Ch R = 1 ,59      ,0,0,0
BEGIN DESCRIPTION:
UNT045 IN ROCK 1.0
END DESCRIPTION:
XS GIS Cut Line= 4
      3642204.15     10138252.71      3641695.42     10137873.07
      3641624.24     10137834.88      3640936.39     10138240.52
#Sta/Elev= 30
  4330.4  268.55  4354.5  268.63  4360.7   267.6  4546.2  262.52  4969.9  256.12
    5026  254.75    5060  256.13  5199.3  257.24  5243.1  256.45  5280.2  256.74
  5315.4  257.91  5323.1  257.37  5403.1  258.16  5498.8  259.66  5512.8   260.5
  5520.2  260.02  5526.1  260.68  5535.9  260.34  5584.6  261.54  5594.1  262.72
  5600.3  267.14  5606.1  266.43  5615.9  267.15  5621.7  264.65  5628.9  266.15
  5637.4  265.77  5643.2  264.01  5658.8  263.25  5768.2  267.02  5844.5  270.77
#Mann= 3 , 0 , 0
  4330.4     .04       0  4969.9    .035       0    5060     .04       0
Bank Sta=4969.9,5060
XS Rating Curve= 0 ,0
Exp/Cntr=0.3,0.1
Stream Node=UNT045 IN ROCK  ,Reach-1         , 0 , 0 ,Upstream end
Stream Node=UNT045 IN ROCK  ,Reach-1         , 0 , 1 ,Downstream end

Chan Stop Cuts=-1
Use User Specified Reach Order=0
Composite Channel Slope=5