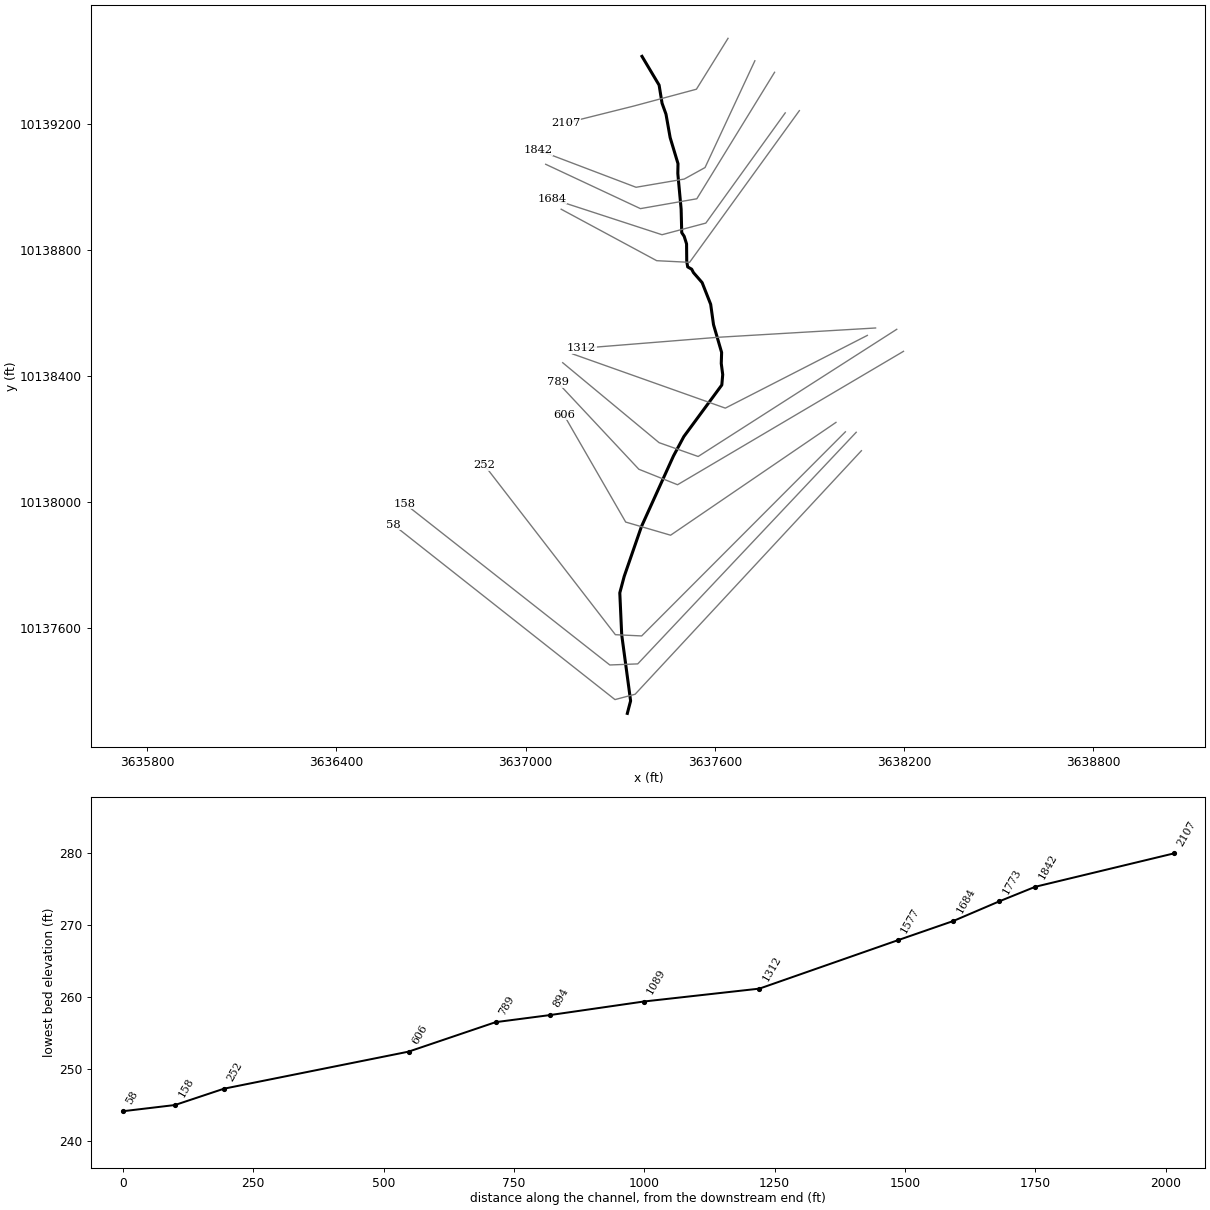
--- UNT047 IN ROCK.prj (project) ---

Proj Title=UNT047 IN ROCK Base Level Engineering
Current Plan=p01
Default Exp/Contr=0.3,0.1
English Units
Geom File=g01
Flow File=f01
Plan File=p01
Y Axis Title=Elevation
X Axis Title(PF)=Main Channel Distance
X Axis Title(XS)=Station
BEGIN DESCRIPTION:
UNT047 IN ROCK
END DESCRIPTION:
DSS Export Rating Curves= 0
DSS Export Rating Curve Sorted= 0
DSS Export Volume Flow Curves= 0
DXF OffsetX= 0
DXF OffsetY= 0
DXF ScaleX= 1
DXF ScaleY= 10

--- UNT047 IN ROCK.p01 (plan) ---

Plan Title=Multiple Run
Short Identifier=Multiple
Geom File=g01
Flow File=f01
Subcritical Flow
K Sum by GR= 0
Std Step Tol= 0.01
Critical Tol= 0.01
Num of Std Step Trials= 20
Max Error Tol= 0.3
Flow Tol Ratio= 0.001
Split Flow NTrial= 30
Split Flow Tol= 0.02
Split Flow Ratio= 0.02
Log Output Level= 0
Friction Slope Method= 1
Unsteady Friction Slope Method= 2
Unsteady Bridges Friction Slope Method= 1
Parabolic Critical Depth
Global Vel Dist=  1 , 1 , 1
Global Log Level= 0
CheckData=True
Encroach Param= -1, 0, 0, 0
BEGIN DESCRIPTION:
Multiple Run
END DESCRIPTION:

--- UNT047 IN ROCK.f01 (steady flow) ---

Flow Title=Multiple
Program Version=4.10
Number of Profiles= 7
Profile Names=10-year,25-year,50-year,1pct_min,100-year,1pct_plu,500-year
River Rch & RM=UNT047 IN ROCK,Reach-1         ,2107
     208     263     306     262     354     479     475
Boundary for River Rch & Prof#=UNT047 IN ROCK,Reach-1         , 1
Up Type= 0
Dn Type= 3
Dn Slope=0.015
Boundary for River Rch & Prof#=UNT047 IN ROCK,Reach-1         , 2
Up Type= 0
Dn Type= 3
Dn Slope=0.015
Boundary for River Rch & Prof#=UNT047 IN ROCK,Reach-1         , 3
Up Type= 0
Dn Type= 3
Dn Slope=0.015
Boundary for River Rch & Prof#=UNT047 IN ROCK,Reach-1         , 4
Up Type= 0
Dn Type= 3
Dn Slope=0.015
Boundary for River Rch & Prof#=UNT047 IN ROCK,Reach-1         , 5
Up Type= 0
Dn Type= 3
Dn Slope=0.015
Boundary for River Rch & Prof#=UNT047 IN ROCK,Reach-1         , 6
Up Type= 0
Dn Type= 3
Dn Slope=0.015
Boundary for River Rch & Prof#=UNT047 IN ROCK,Reach-1         , 7
Up Type= 0
Dn Type= 3
Dn Slope=0.015
DSS Import GetInterval= 0
DSS Import GetPeak= 0
DSS Import FillOption= 0

--- UNT047 IN ROCK.g01 (geometry) ---

Geom Title=Existing Conditions
Program Version=4.10

River Reach=UNT047 IN ROCK  ,Reach-1
Reach XY= 30
      3637368.79     10139413.24      3637423.04     10139322.15
      3637432.38     10139264.71      3637444.88     10139229.99
      3637458.07     10139155.69      3637482.97     10139073.01
      3637482.38      10139041.8       3637492.9     10138928.91
      3637494.79     10138854.41      3637502.54     10138842.68
      3637510.12     10138818.56      3637510.68     10138763.01
      3637513.71     10138745.65      3637526.32     10138738.46
        3637532.      10138727.6      3637559.46     10138695.96
      3637586.54     10138627.21      3637595.57     10138562.63
      3637621.27     10138474.44      3637620.13     10138439.44
      3637624.74      10138404.3      3637621.88     10138371.33
      3637501.54     10138207.87      3637468.56     10138146.24
      3637366.99     10137922.28      3637312.31     10137764.29
      3637298.42     10137712.21      3637304.49      10137579.4
       3637332.7     10137369.85      3637322.32     10137330.17

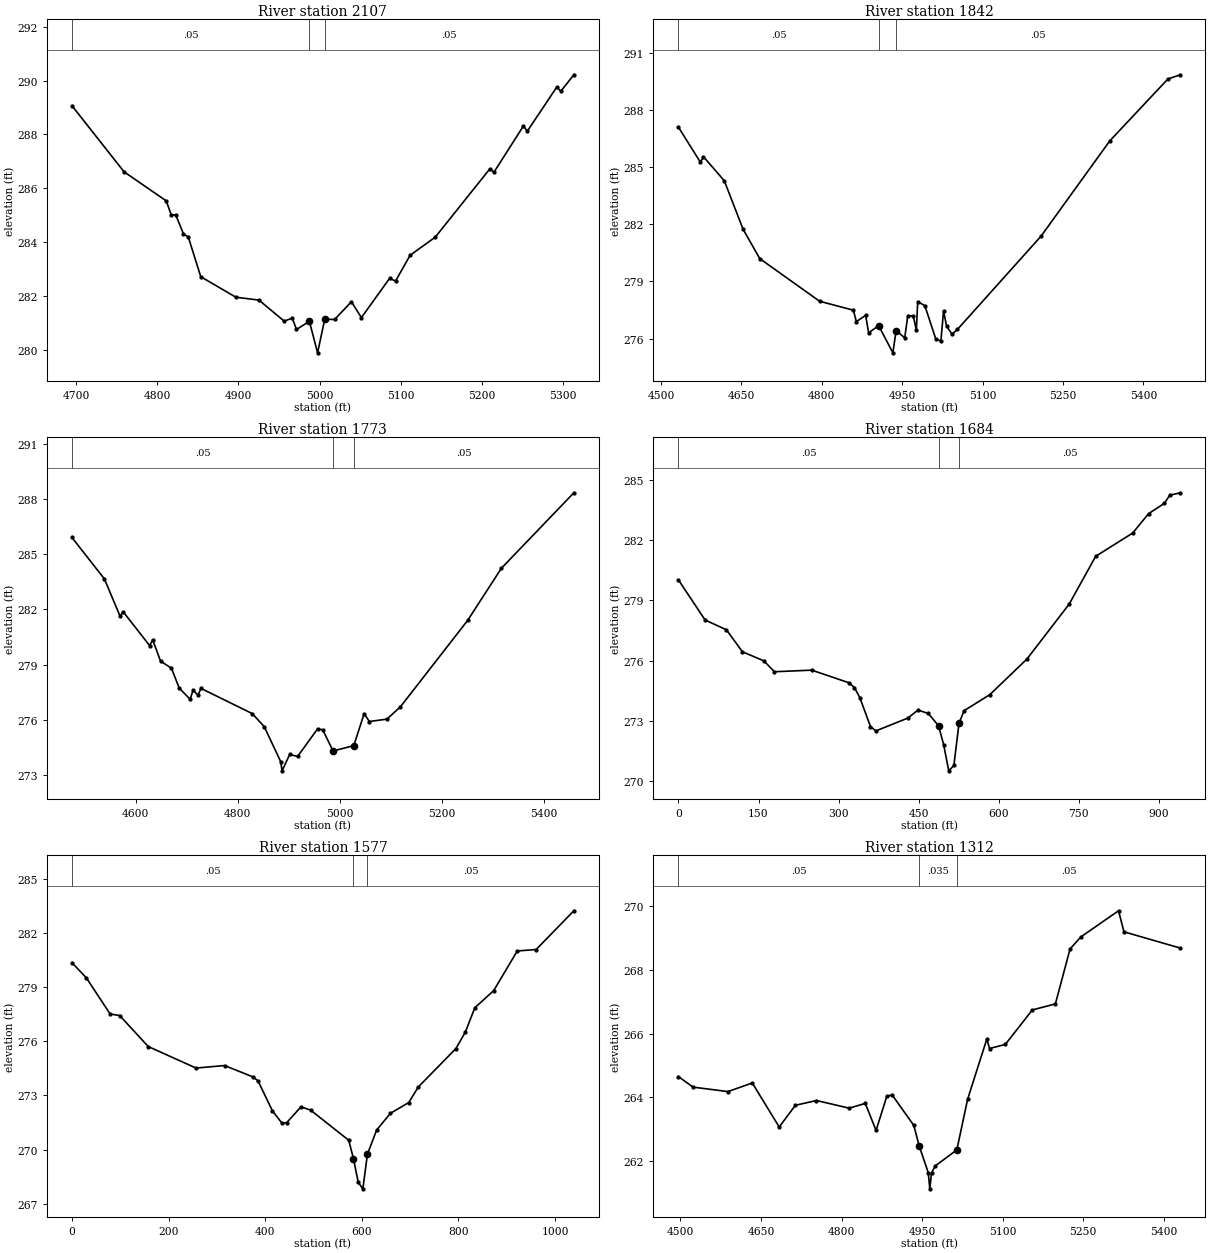
Type RM Length L Ch R = 1 ,2107    ,266,266,266
BEGIN DESCRIPTION:
UNT047 IN ROCK 5.0
END DESCRIPTION:
XS GIS Cut Line= 4
      3637641.59     10139470.39      3637541.36     10139309.07
      3637342.02     10139255.54      3637126.28     10139201.61
#Sta/Elev= 30
  4694.8  289.07  4759.1  286.61  4811.1  285.53    4817  285.02  4822.9     285
  4832.3   284.3  4838.2  284.19  4853.6  282.71  4896.8  281.95  4925.4  281.84
  4956.4  281.06  4966.4  281.17  4971.6  280.75  4987.5  281.05  4997.6  279.88
  5006.4  281.13  5018.6  281.12  5039.3  281.78  5051.6  281.19  5086.4  282.65
  5093.7  282.55  5111.7  283.51  5142.6  284.18  5209.9  286.72  5215.1   286.6
  5251.2  288.31  5256.3  288.13  5292.4  289.76  5297.5  289.61  5313.5  290.22
#Mann= 3 , 0 , 0
  4694.8     .05       0  4987.5     .03       0  5006.4     .05       0
Bank Sta=4987.5,5006.4
XS Rating Curve= 0 ,0
Exp/Cntr=0.3,0.1

Type RM Length L Ch R = 1 ,1842    ,69,69,69
BEGIN DESCRIPTION:
Mapping XS d3e33c51
END DESCRIPTION:
XS GIS Cut Line= 5
      3637726.65     10139399.19      3637568.68     10139060.69
      3637502.71     10139024.23      3637349.93     10138998.19
      3637039.21     10139116.23
#Sta/Elev= 30
  4532.6  287.11  4573.7  285.26  4579.2  285.56  4618.2  284.29  4653.3  281.74
  4684.4   280.2    4796  277.96    4859  277.49  4864.5  276.89  4881.9  277.22
  4887.4   276.3  4906.1  276.68  4932.7  275.25  4938.7  276.42  4954.8  276.04
  4960.5  277.21  4970.8  277.18  4976.5  276.44    4979  277.94  4992.3  277.73
  5012.6  275.99  5022.2  275.86  5027.2  277.45  5032.9  276.65    5043  276.23
  5053.1  276.48  5209.1  281.38  5337.4  286.39  5445.8  289.64  5468.9  289.86
#Mann= 3 , 0 , 0
  4532.6     .05       0  4906.1    .035       0  4938.7     .05       0
Bank Sta=4906.1,4938.7
XS Rating Curve= 0 ,0
Exp/Cntr=0.3,0.1

Type RM Length L Ch R = 1 ,1773    ,88,88,88
BEGIN DESCRIPTION:
Mapping XS 9dccbc87
END DESCRIPTION:
XS GIS Cut Line= 4
      3637789.17     10139362.77      3637542.64     10138961.73
      3637363.82     10138930.48       3637063.5     10139071.09
#Sta/Elev= 30
  4475.3  285.91  4538.9  283.66  4569.7  281.63  4575.6  281.88  4627.7  280.03
  4633.6  280.35    4649  279.19  4670.3  278.81  4685.7  277.72    4707  277.12
  4712.8  277.62  4722.4  277.34  4728.2  277.71  4828.8  276.34  4852.3  275.63
  4884.5  273.73  4887.2  273.23  4902.2  274.12  4917.6  274.01  4956.8  275.51
  4966.9  275.46  4987.2  274.31  5027.8   274.6  5048.1  276.34  5058.3  275.91
  5092.8  276.04  5119.2  276.71  5250.9   281.4  5317.2  284.24  5459.2  288.34
#Mann= 3 , 0 , 0
  4475.3     .05       0  4987.2    .035       0  5027.8     .05       0
Bank Sta=4987.2,5027.8
XS Rating Curve= 0 ,0
Exp/Cntr=0.3,0.1

Type RM Length L Ch R = 1 ,1684    ,107,107,107
XS GIS Cut Line= 4
     3637822.921     10139234.01     3637571.185    10138884.618
     3637432.296    10138847.725     3637082.904    10138961.657
#Sta/Elev= 30
       0280.022249.96208278.023289.93174277.5351 119.909276.4388159.8786275.9912
179.8635275.4456249.8104 275.525319.7573274.8927329.7497274.6536339.7421274.1598
 359.727272.7173369.7194 272.497429.6739273.1373448.8435273.5348468.0131273.3656
487.1827272.7582496.7675271.8158506.3524270.5092515.9372270.7767 525.522272.8742
535.1068273.5078583.3552274.3058652.7186276.0764731.9911278.8178781.5364281.1958
850.8998282.3554 880.627 283.319910.3542283.8366920.2632284.2389940.0814  284.36
#Mann= 3 , 0 , 0
       0     .05       0487.1827    .035       0 525.522     .05       0
Bank Sta=487.1827,525.522
XS Rating Curve= 0 ,0
Exp/Cntr=0.3,0.1

Type RM Length L Ch R = 1 ,1577    ,265,265,265
XS GIS Cut Line= 4
     3637867.745    10139241.106     3637519.655    10138760.203
     3637415.488    10138765.412     3637112.537    10138928.606
#Sta/Elev= 30
       0 280.35629.62952279.523779.01205 277.51598.76506277.4284158.0241275.7093
256.7892274.5201316.0482274.6594375.3072274.0203385.1837273.8073414.8132272.1556
434.5663271.4682444.4427271.4932474.0723272.3716493.8253 272.191572.8373270.5199
582.7139269.5006592.5903268.1839602.1019267.8279611.6134269.7498630.6365271.0837
659.1711272.0128697.2172272.6088716.7389273.4678794.8256275.6016814.3473276.5177
 833.869277.8594872.9124278.8085921.7166281.0063960.7599281.08591038.847283.2326
#Mann= 3 , 0 , 0
       0     .05       0582.7139    .035       0611.6134     .05       0
Bank Sta=582.7139,611.6134
XS Rating Curve= 0 ,0
Exp/Cntr=0.3,0.1

Type RM Length L Ch R = 1 ,1312    ,222,222,222
BEGIN DESCRIPTION:
UNT047 IN ROCK 3.0
END DESCRIPTION:
XS GIS Cut Line= 3
      3638109.41     10138552.06      3637606.68     10138522.35
      3637177.47     10138487.84
#Sta/Elev= 30
  4496.4  264.65  4523.7  264.32  4588.5  264.18  4633.9  264.45    4684  263.07
  4714.1  263.75  4753.4   263.9  4814.3  263.66  4844.3  263.81  4864.3  262.96
  4884.4  264.04  4894.4  264.07  4934.5  263.12  4944.5  262.48  4961.5  261.63
  4964.3  261.13  4967.5  261.63  4974.5  261.85  5014.6  262.35  5034.7  263.94
  5070.5  265.83  5075.5  265.53  5104.9  265.66  5155.1  266.74  5198.1  266.93
  5225.3  268.65  5245.4  269.03  5315.6  269.85  5325.7  269.19  5430.6  268.68
#Mann= 3 , 0 , 0
  4496.4     .05       0  4944.5    .035       0  5014.6     .05       0
#XS Ineff= 2 , 0
         4884.77  264.03
Permanent Ineff=
       F       F
Bank Sta=4944.5,5014.6
XS Rating Curve= 0 ,0
Exp/Cntr=0.3,0.1

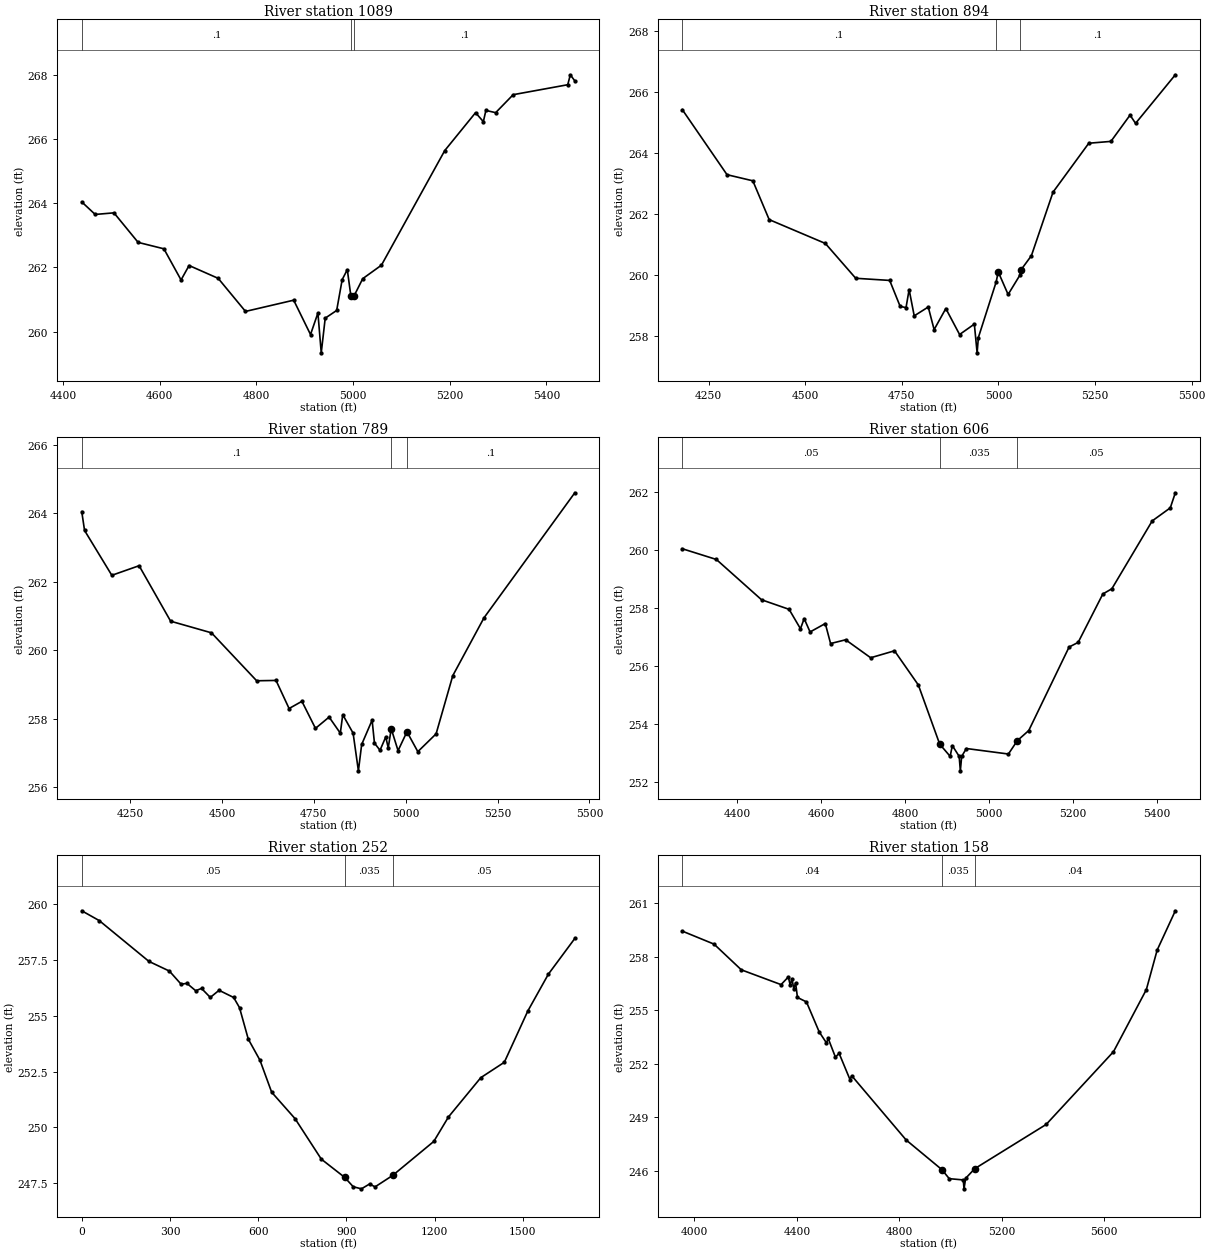
Type RM Length L Ch R = 1 ,1089    ,180,180,180
BEGIN DESCRIPTION:
Mapping XS f9956552
END DESCRIPTION:
XS GIS Cut Line= 3
      3638083.31     10138528.56      3637633.02     10138297.96
      3637148.63     10138469.88
#Sta/Elev= 30
    4439  264.04  4466.8  263.65  4505.6   263.7  4555.6  262.78  4608.9  262.58
  4644.4  261.61    4661  262.06  4721.2  261.66  4777.7  260.63  4877.4  260.98
  4912.2  259.91  4927.5  260.58  4934.4  259.34  4942.6  260.42  4966.3  260.66
  4977.7  261.62  4988.3  261.93 4995.71  261.11  5002.5  261.12  5020.2  261.65
  5058.9  262.07  5189.9  265.64  5253.6  266.82  5269.7  266.54    5275  266.89
  5295.2  266.82  5331.4  267.38  5444.3  267.69  5449.6     268  5458.9  267.81
#Mann= 3 , 0 , 0
    4439      .1       0 4995.71     .05       0  5002.5      .1       0
#Block Obstruct= 2 , 0
         4984.36  260.89
Bank Sta=4995.71,5002.5
XS Rating Curve= 0 ,0
Exp/Cntr=0.3,0.1

Type RM Length L Ch R = 1 ,894     ,104,104,104
BEGIN DESCRIPTION:
UNT047 IN ROCK 2.0
END DESCRIPTION:
XS GIS Cut Line= 4
      3638176.51     10138547.87      3637546.85     10138144.64
      3637423.01     10138188.46      3637117.45     10138441.96
#Sta/Elev= 30
  4181.7  265.42  4297.5  263.29  4364.3  263.09  4406.6  261.82    4552  261.04
  4630.6   259.9  4718.5  259.83  4745.6  258.98  4760.8  258.94  4768.8  259.53
    4782  258.67  4818.3  258.96  4833.5  258.22  4863.8  258.91  4899.4  258.06
  4937.6   258.4  4944.8  257.46    4948  257.96  4994.1  259.78  4999.4  260.11
    5025  259.37  5055.9  260.01  5058.6  260.18  5085.3  260.64  5141.3  262.72
  5233.8  264.32  5291.1  264.38  5340.6  265.24  5354.9  264.97  5457.8  266.56
#Mann= 3 ,-1 , 0
  4181.7      .1       0  4994.1     .05       0  5055.9      .1       0
#Block Obstruct= 2 , 0
         4998.97  259.36
Bank Sta=4999.4,5058.6
XS Rating Curve= 0 ,0
Exp/Cntr=0.3,0.1

Type RM Length L Ch R = 1 ,789     ,167,167,167
BEGIN DESCRIPTION:
Mapping XS b72d8fb9
END DESCRIPTION:
XS GIS Cut Line= 4
      3638197.87     10138478.05      3637481.57      10138055.1
      3637358.78     10138104.21      3637100.94     10138379.79
#Sta/Elev= 30
  4118.6  264.05  4126.2   263.5  4200.4  262.19  4274.6  262.47  4360.4  260.85
  4471.6  260.51  4594.5  259.11  4647.2  259.12  4682.7   258.3  4717.6  258.51
  4754.5  257.72  4791.6  258.05  4822.1  257.58  4828.7  258.12  4856.9  257.58
  4871.3  256.48  4880.2  257.25  4908.6  257.96    4915  257.29  4930.1  257.08
  4945.7  257.47  4952.5  257.15  4960.6  257.71  4979.2  257.07  5003.4  257.62
    5033  257.04  5082.7  257.56  5128.1  259.26  5213.1  260.95  5460.1   264.6
#Mann= 3 , 0 , 0
  4118.6      .1       0  4960.6     .05       0  5003.4      .1       0
#XS Ineff= 2 , 0
         4829.09   258.1
Permanent Ineff=
       F       F
Bank Sta=4960.6,5003.4
XS Rating Curve= 0 ,0
Exp/Cntr=0.3,0.1

Type RM Length L Ch R = 1 ,606     ,354,354,354
BEGIN DESCRIPTION:
Mapping XS 255df159
END DESCRIPTION:
XS GIS Cut Line= 4
       3637983.8     10138252.73      3637459.47     10137895.07
      3637317.11     10137936.74      3637121.04     10138276.84
#Sta/Elev= 30
  4268.9  260.05  4350.2  259.68  4457.9  258.29  4523.6  257.96  4550.7  257.29
  4559.5  257.64  4573.6  257.18  4609.9  257.47  4622.5  256.78  4658.4  256.91
  4718.1  256.29  4774.9  256.53  4831.8  255.35  4882.7  253.31  4907.6  252.89
  4912.8  253.26  4929.1  252.89  4931.9  252.39  4935.1  252.89  4946.3  253.16
  5046.5  252.97  5067.7  253.43    5095  253.78  5191.2  256.66  5212.8  256.82
  5271.7  258.49  5293.2  258.67  5389.4  261.01  5432.5  261.46  5444.5  261.98
#Mann= 3 , 0 , 0
  4268.9     .05       0  4882.7    .035       0  5067.7     .05       0
Bank Sta=4882.7,5067.7
XS Rating Curve= 0 ,0
Exp/Cntr=0.3,0.1

Type RM Length L Ch R = 1 ,252     ,94,94,94
XS GIS Cut Line= 5
     3638013.658    10138222.845     3637367.825     10137575.71
     3637284.492    10137579.616     3636869.127    10138117.376
3636869.1267761410138117.3762898
#Sta/Elev= 30
       0259.698159.62614259.2577228.5669257.4323298.1307256.9997337.8814256.4133
357.7568256.4496387.5699256.1208407.4453256.2235437.2583255.8204467.0714256.1397
516.7598255.8179536.6353255.3628566.4483253.9544 606.199253.0106645.9498251.5798
725.4514250.3974814.8906 248.584 894.392247.7678923.5369 247.348951.3452 247.255
979.1534247.4728997.6923247.34271057.648247.85541197.544 249.3771247.507250.4737
1357.425252.23051437.366252.91771517.306 255.2121587.255256.86141677.188258.4591
#Mann= 3 , 0 , 0
       0     .05       0 894.392    .035       01057.648     .05       0
Bank Sta=894.392,1057.648
XS Rating Curve= 0 ,0
Exp/Cntr=0.3,0.1

Type RM Length L Ch R = 1 ,158     ,100,100,100
BEGIN DESCRIPTION:
UNT047 IN ROCK 1.0
END DESCRIPTION:
XS GIS Cut Line= 4
      3638047.98     10138221.43      3637355.31     10137487.09
      3637266.77     10137483.62      3636616.38     10137995.25
#Sta/Elev= 30
  3952.3  259.44  4076.4  258.71  4182.8  257.27  4338.1  256.44  4366.5  256.87
  4373.8  256.41  4380.6  256.76  4387.9   256.2  4394.8  256.54  4402.1  255.72
  4437.3  255.47    4487  253.79  4515.4  253.17  4522.2  253.42  4550.5  252.37
  4564.7  252.59  4607.2  251.12  4614.1  251.33  4826.5  247.73  4965.9  246.07
    4995  245.56  5049.8  245.49  5052.6  244.99    5059  245.58  5094.5  246.12
  5373.4   248.6  5636.4  252.68  5764.7  256.16    5807  258.38  5877.9  260.58
#Mann= 3 ,-1 , 0
  3952.3     .04       0  4965.9    .035       0  5094.5     .04       0
Bank Sta=4965.9,5094.5
XS Rating Curve= 0 ,0
Exp/Cntr=0.3,0.1

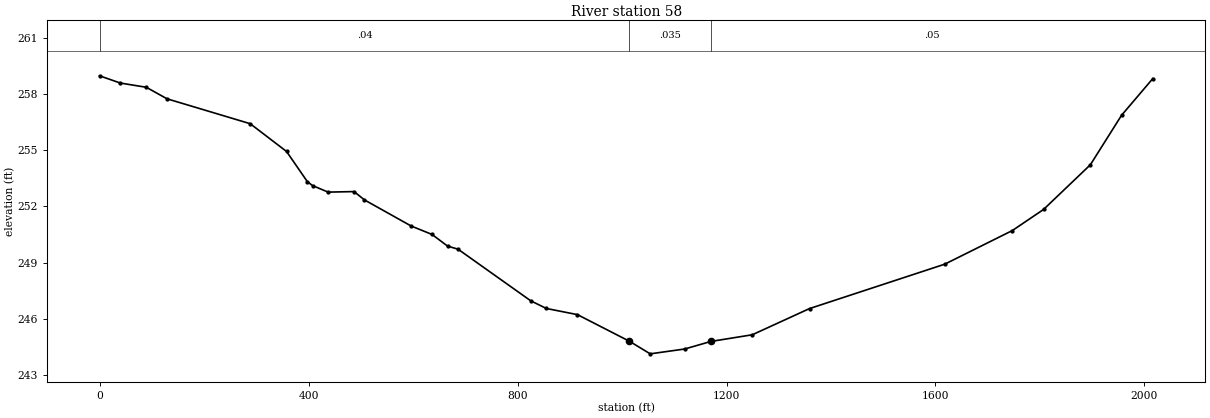
Type RM Length L Ch R = 1 ,58      ,0,0,0
XS GIS Cut Line= 5
      3638064.44    10138162.949     3637346.992    10137390.814
      3637283.19    10137373.887     3636580.065    10137928.574
3636580.0646166510137928.5743024
#Sta/Elev= 30
       0258.967639.77226258.579889.48759258.3545129.2599257.7383288.3489256.4103
357.9504254.9285397.7226253.3198407.6657253.1082437.4949252.7587487.2102252.7876
507.0963 252.343596.5839 250.948636.3562250.5008666.1854249.8766686.0715249.7148
825.2745246.9595855.1036  246.55 914.762246.21981014.193244.79971053.965 244.128
1119.992244.3859 1169.76244.78771249.389 245.1461358.878246.54351617.672248.9127
1747.068250.7078 1806.79251.83241896.372254.21681956.094256.85852015.816258.8155
#Mann= 3 , 0 , 0
       0     .04       01014.193    .035       0 1169.76     .05       0
Bank Sta=1014.193,1169.76
XS Rating Curve= 0 ,0
Exp/Cntr=0.3,0.1
Stream Node=UNT047 IN ROCK  ,Reach-1         , 0 , 0 ,Upstream end
Stream Node=UNT047 IN ROCK  ,Reach-1         , 0 , 1 ,Downstream end

Chan Stop Cuts=-1
Use User Specified Reach Order=0
Composite Channel Slope=5