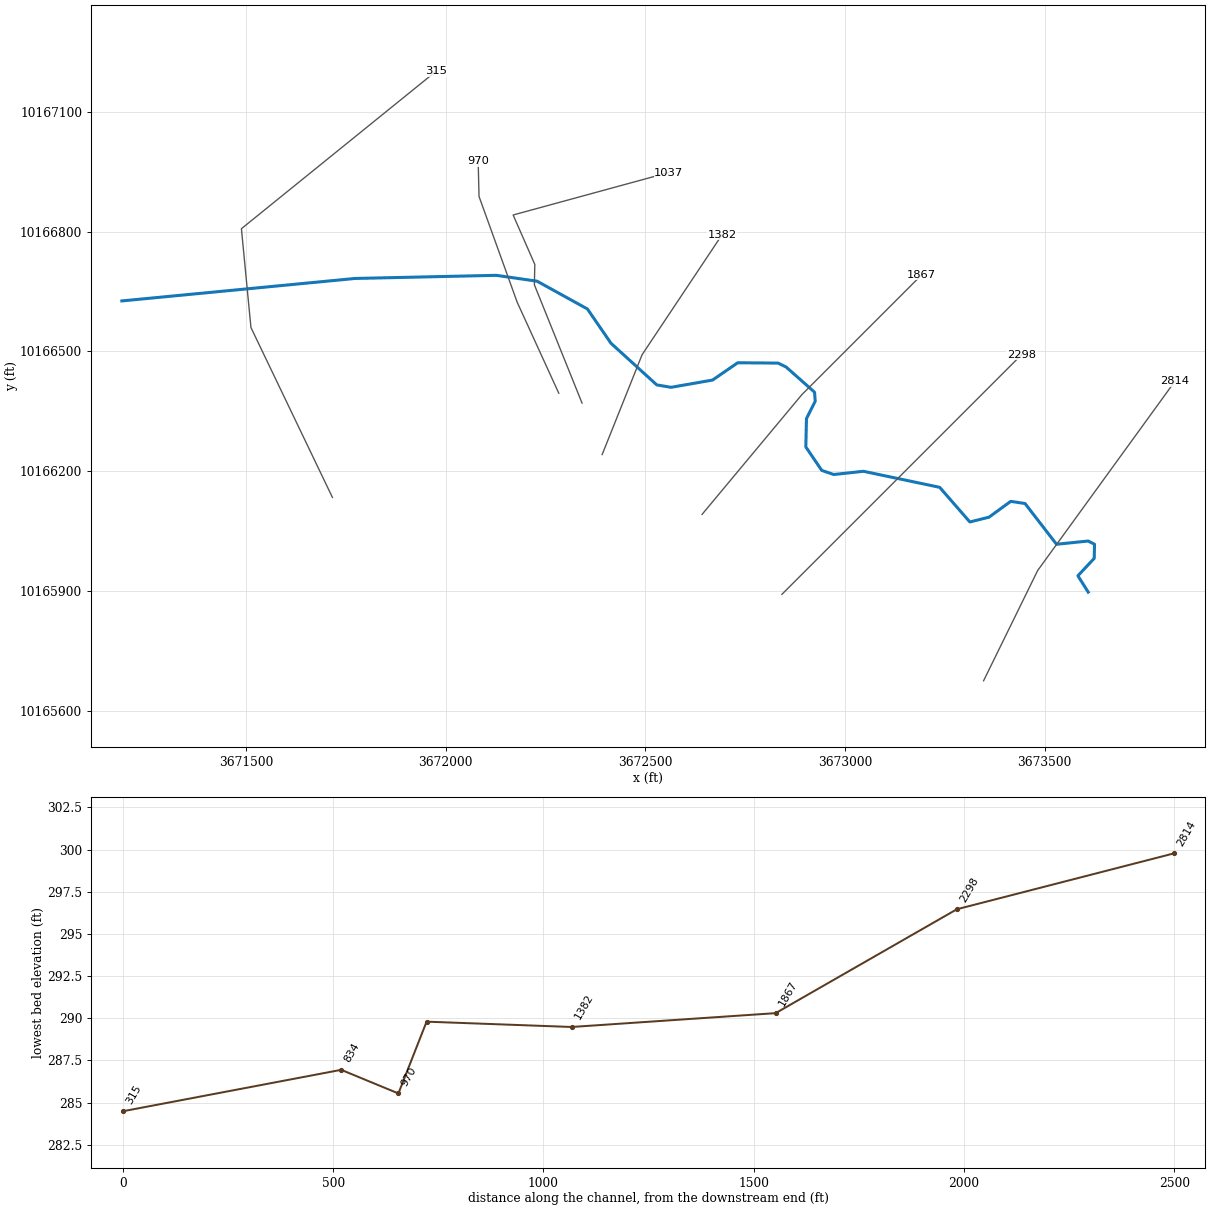
--- UNT051 IN ROCK.prj (project) ---

Proj Title=UNT051 IN ROCK Base Level Engineering
Current Plan=p01
Default Exp/Contr=0.3,0.1
English Units
Geom File=g01
Flow File=f01
Plan File=p01
Y Axis Title=Elevation
X Axis Title(PF)=Main Channel Distance
X Axis Title(XS)=Station
BEGIN DESCRIPTION:
UNT051 IN ROCK
END DESCRIPTION:
DSS Export Rating Curves= 0
DSS Export Rating Curve Sorted= 0
DSS Export Volume Flow Curves= 0
DXF OffsetX= 0
DXF OffsetY= 0
DXF ScaleX= 1
DXF ScaleY= 10

--- UNT051 IN ROCK.p01 (plan) ---

Plan Title=Multiple Run
Short Identifier=Multiple
Geom File=g01
Flow File=f01
Subcritical Flow
K Sum by GR= 0
Std Step Tol= 0.01
Critical Tol= 0.01
Num of Std Step Trials= 20
Max Error Tol= 0.3
Flow Tol Ratio= 0.001
Split Flow NTrial= 30
Split Flow Tol= 0.02
Split Flow Ratio= 0.02
Log Output Level= 0
Friction Slope Method= 1
Unsteady Friction Slope Method= 2
Unsteady Bridges Friction Slope Method= 1
Parabolic Critical Depth
Global Vel Dist=  1 , 1 , 1
Global Log Level= 0
CheckData=True
Encroach Param= -1, 0, 0, 0
BEGIN DESCRIPTION:
Multiple Run
END DESCRIPTION:

--- UNT051 IN ROCK.f01 (steady flow) ---

Flow Title=Multiple
Program Version=4.10
Number of Profiles= 7
Profile Names=10-year,25-year,50-year,1pct_min,100-year,1pct_plu,500-year
River Rch & RM=UNT051 IN ROCK,Reach-1         ,2814
     739    1002    1218    1086    1468    1986    2130
Boundary for River Rch & Prof#=UNT051 IN ROCK,Reach-1         , 1
Up Type= 0
Dn Type= 3
Dn Slope=0.015
Boundary for River Rch & Prof#=UNT051 IN ROCK,Reach-1         , 2
Up Type= 0
Dn Type= 3
Dn Slope=0.015
Boundary for River Rch & Prof#=UNT051 IN ROCK,Reach-1         , 3
Up Type= 0
Dn Type= 3
Dn Slope=0.015
Boundary for River Rch & Prof#=UNT051 IN ROCK,Reach-1         , 4
Up Type= 0
Dn Type= 3
Dn Slope=0.015
Boundary for River Rch & Prof#=UNT051 IN ROCK,Reach-1         , 5
Up Type= 0
Dn Type= 3
Dn Slope=0.015
Boundary for River Rch & Prof#=UNT051 IN ROCK,Reach-1         , 6
Up Type= 0
Dn Type= 3
Dn Slope=0.015
Boundary for River Rch & Prof#=UNT051 IN ROCK,Reach-1         , 7
Up Type= 0
Dn Type= 3
Dn Slope=0.015
DSS Import GetInterval= 0
DSS Import GetPeak= 0
DSS Import FillOption= 0

--- UNT051 IN ROCK.g01 (geometry) ---

Geom Title=Existing Conditions
Program Version=4.10

River Reach=UNT051 IN ROCK  ,Reach-1
Reach XY= 30
        3673609.     10165897.24      3673583.13     10165938.14
      3673624.08     10165981.77      3673624.72     10166017.08
      3673608.98     10166025.14      3673529.59     10166017.03
      3673450.89     10166118.98      3673414.95     10166124.46
      3673360.52     10166084.77      3673312.65     10166072.85
       3673237.1     10166159.56      3673046.27     10166199.72
      3672971.98     10166191.68      3672941.98     10166201.86
      3672902.02     10166260.61      3672903.58     10166331.59
      3672925.54      10166375.2      3672923.81     10166397.77
       3672852.6     10166460.81      3672832.63     10166470.59
      3672731.49     10166471.45       3672668.6     10166428.15
      3672564.43     10166409.92      3672528.84       10166416.
      3672414.26     10166520.16      3672355.23      10166606.1
      3672229.36     10166675.55      3672126.93      10166690.3
      3671773.63     10166682.49      3671189.63     10166626.24

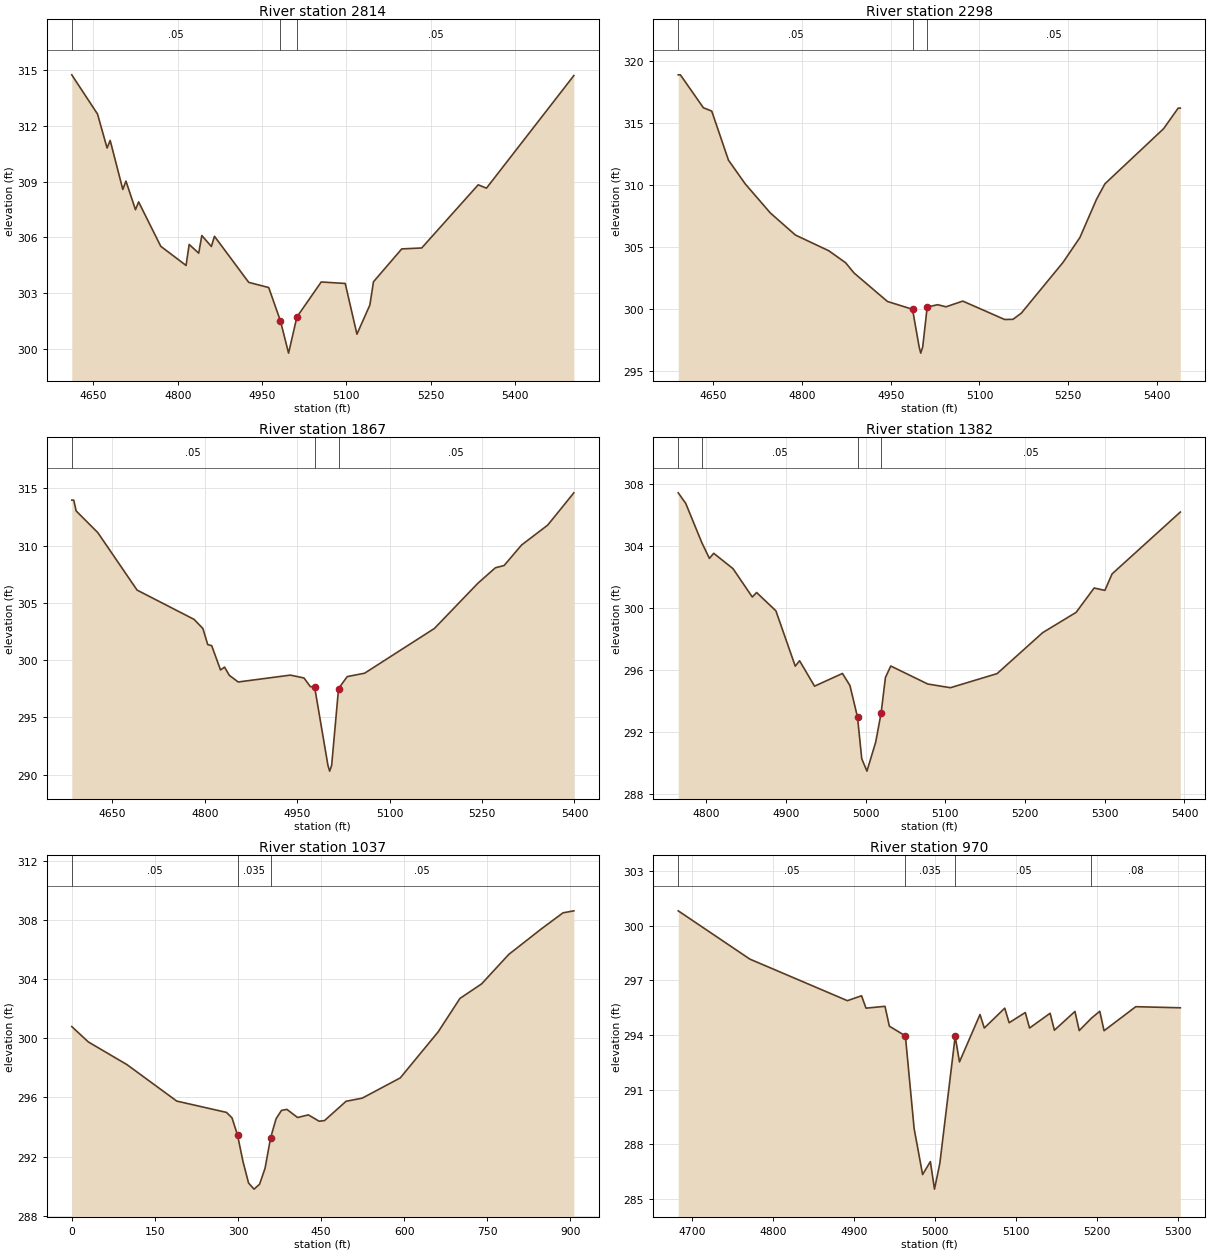
Type RM Length L Ch R = 1 ,2814    ,516,516,516
BEGIN DESCRIPTION:
UNT051 IN ROCK 5.0
END DESCRIPTION:
XS GIS Cut Line= 3
      3673347.02      10165675.3      3673482.44     10165951.34
      3673826.21     10166425.33
#Sta/Elev= 30
  4611.6  314.75  4657.4  312.64  4674.4  310.81  4679.9  311.22  4702.4  308.58
    4708  309.03  4724.9  307.49  4730.5  307.91  4769.9  305.52  4814.9  304.49
  4820.4  305.62  4837.4  305.15  4842.9   306.1  4859.9  305.51  4865.4  306.06
  4926.3  303.58  4961.9   303.3  4982.8   301.5  4997.2  299.77  5012.1  301.72
  5055.3   303.6    5098  303.52  5118.8  300.79  5141.8  302.36  5148.2  303.61
  5198.5  305.38    5234  305.43  5334.5  308.83  5349.2  308.65  5504.6  314.71
#Mann= 3 , 0 , 0
  4611.6     .05       0  4982.8    .035       0  5012.1     .05       0
Bank Sta=4982.8,5012.1
XS Rating Curve= 0 ,0
Exp/Cntr=0.3,0.1

Type RM Length L Ch R = 1 ,2298    ,431,431,431
BEGIN DESCRIPTION:
UNT051 IN ROCK 4.0
END DESCRIPTION:
XS GIS Cut Line= 3
      3672842.08     10165891.62      3673142.11     10166191.64
      3673442.13     10166491.67
#Sta/Elev= 30
  4590.9  318.87  4594.5  318.87  4633.4  316.22  4647.5  315.95  4675.8     312
  4704.1  310.09  4746.5  307.75  4788.9  305.97  4845.5   304.7  4873.8  303.74
  4887.9  302.92  4944.5  300.62  4986.9  299.99  4998.1  296.96  5000.8  296.46
  5004.1  296.96  5011.7  300.17  5029.3  300.36  5043.5  300.19  5071.8  300.65
  5142.5  299.17  5156.6  299.18  5170.8  299.68  5241.5  303.78  5269.8  305.77
    5298  308.86  5312.2   310.1  5411.2  314.53  5435.9  316.19  5439.5  316.19
#Mann= 3 , 0 , 0
  4590.9     .05       0  4986.9    .035       0  5011.7     .05       0
Bank Sta=4986.9,5011.7
XS Rating Curve= 0 ,0
Exp/Cntr=0.3,0.1

Type RM Length L Ch R = 1 ,1867    ,485,485,485
BEGIN DESCRIPTION:
UNT051 IN ROCK 3.0
END DESCRIPTION:
XS GIS Cut Line= 3
      3672642.14     10166091.68      3672892.11     10166391.64
      3673192.09     10166691.62
#Sta/Elev= 30
  4584.3  313.98  4587.5  313.98  4591.4  313.04  4626.6  311.14  4690.3  306.12
  4782.8  303.56  4797.1  302.76  4804.9  301.36  4811.4  301.26  4825.7  299.14
  4832.2  299.39    4840  298.67  4854.4  298.09    4939  298.69  4961.1  298.44
  4971.5  297.68  4978.3  297.68    5000   290.8  5002.8   290.3    5006   290.8
  5017.2  297.52  5031.3  298.56  5059.6  298.86  5172.8  302.77  5243.5  306.73
  5271.7  308.07  5285.9  308.27  5314.2  310.06  5356.6   311.8    5399  314.62
#Mann= 3 , 0 , 0
  4584.3     .05       0  4978.3    .035       0  5017.2     .05       0
Bank Sta=4978.3,5017.2
XS Rating Curve= 0 ,0
Exp/Cntr=0.3,0.1

Type RM Length L Ch R = 1 ,1382    ,345,345,345
BEGIN DESCRIPTION:
UNT051 IN ROCK 2.0
END DESCRIPTION:
XS GIS Cut Line= 3
       3672392.1     10166241.62      3672492.11     10166491.64
      3672692.08     10166791.61
#Sta/Elev= 30
    4765  307.43  4774.4  306.75  4794.4  304.24  4804.1   303.2  4809.5  303.53
  4833.7  302.54  4857.9  300.71  4863.3     301  4887.5  299.82  4911.8  296.25
  4917.2   296.6    4936  294.96    4971  295.78  4980.4     295  4989.9  292.96
  4995.2  290.28  5001.7  289.48  5012.7  291.35  5019.5  293.23  5024.9  295.52
  5031.6  296.26  5077.9   295.1  5106.4  294.86    5165  295.77  5222.1  298.41
  5264.1  299.72  5286.7  301.29  5300.2  301.14  5309.2   302.2  5394.8  306.19
#Mann= 4 ,-1 , 0
    4765     .08       0  4794.4     .05       0  4989.9    .035       0
  5019.5     .05       0
Bank Sta=4989.9,5019.5
XS Rating Curve= 0 ,0
Exp/Cntr=0.3,0.1

Type RM Length L Ch R = 1 ,1037    ,67,67,67
XS GIS Cut Line= 5
     3672341.769    10166370.443     3672222.412    10166666.667
     3672223.497    10166717.665     3672169.243    10166841.363
     3672558.783      10166947.7
#Sta/Elev= 30
       0300.803229.91456 299.762 99.7152298.2239189.4589295.7568279.2026294.9915
289.1741  294.62299.1456293.4523309.1171291.6458319.0887290.2022329.0088 289.795
 338.929 290.128348.8492291.2099358.7693293.2601368.6895294.5599378.4036295.1233
388.1176295.1979407.5457294.6446426.9739294.8237 446.402294.3931456.1161 294.437
494.9724 295.742524.2657 295.958592.7933 297.326661.3209300.4492700.4796302.7073
739.6382303.6948788.5865305.6875847.3245307.4147886.4831308.5044906.0624308.6406
#Mann= 3 , 0 , 0
       0     .05       0299.1456    .035       0358.7693     .05       0
Bank Sta=299.1456,358.7693
XS Rating Curve= 0 ,0
Exp/Cntr=0.3,0.1

Type RM Length L Ch R = 1 ,970     ,136,136,136
BEGIN DESCRIPTION:
Mapping XS 2366252e
END DESCRIPTION:
XS GIS Cut Line= 4
       3672283.5     10166395.18      3672179.34     10166623.04
      3672083.85      10166887.8      3672081.68     10166976.68
#Sta/Elev= 30
  4682.5  300.81  4771.1  298.16  4891.7  295.88  4909.2  296.15  4914.7  295.47
  4938.2  295.57  4943.6  294.48  4963.4  293.95  4974.2  288.87  4984.7  286.34
  4994.3  287.05  4999.4  285.54    5006  286.95    5025  293.92  5030.3  292.52
  5055.7  295.12    5061  294.38  5086.3  295.47  5091.7  294.67  5111.7  295.23
    5117  294.38  5142.4  295.19  5147.7  294.26  5173.1  295.29  5178.4  294.24
  5193.5  294.92  5203.8   295.3  5209.1  294.23  5248.3  295.55  5303.4  295.49
#Mann= 4 ,-1 , 0
  4682.5     .05       0  4963.4    .035       0    5025     .05       0
  5193.5     .08       0
Bank Sta=4963.4,5025
XS Rating Curve= 0 ,0
Exp/Cntr=0.3,0.1

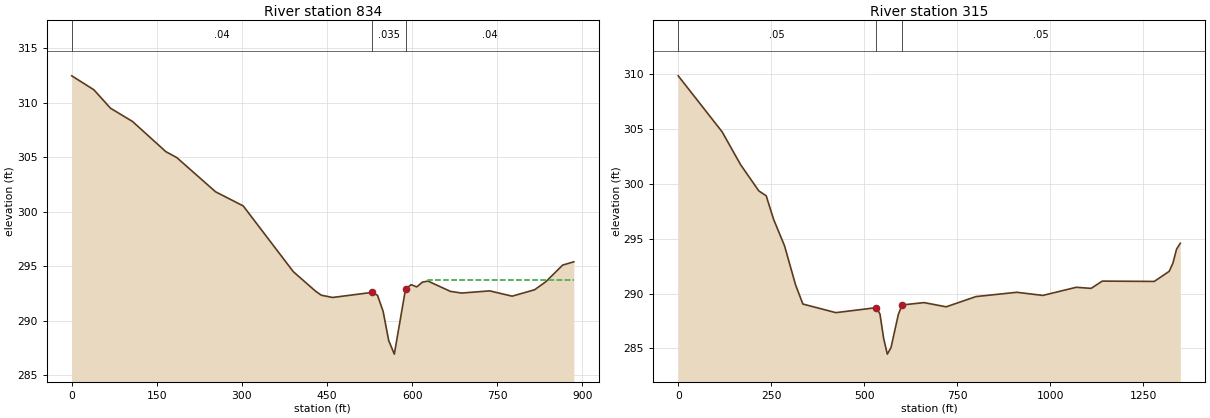
Type RM Length L Ch R = 1 ,834     ,519,519,519
#Sta/Elev= 30
       0312.482539.00385311.201368.25674309.5113107.2606308.2862165.7664305.5269
185.2683304.9736 253.525301.8389302.2798300.5407390.5952294.5053430.1557292.7009
440.0458292.3458 459.826292.1401529.0569292.6019538.9471292.3428548.8372290.8759
558.7274288.1869568.6175286.9395588.3977292.9115598.2878293.3153 608.178293.1083
618.0681293.5439627.9583293.6444667.5187292.6975 687.299292.5463736.7496292.7449
776.3102292.2594815.8707292.8461835.6509293.5798865.3214295.1101885.1016295.4145
#Mann= 3 , 0 , 0
       0     .04       0529.0569    .035       0588.3977     .04       0
#XS Ineff= 2 , 0
                          627.84          293.71
Permanent Ineff=
       F       F
Bank Sta=529.0569,588.3977
XS Rating Curve= 0 ,0
Exp/Cntr=0.3,0.1

Type RM Length L Ch R = 1 ,315     ,0,0,0
XS GIS Cut Line= 4
     3671716.828    10166134.285     3671512.835    10166559.632
     3671488.963    10166807.028     3671977.245    10167201.993
#Sta/Elev= 30
       0 309.873118.2956 304.754167.5854301.7725216.8752299.3688236.5912298.9294
256.3071296.7939 285.881294.3617315.4549290.8132335.1708289.0542423.8925288.2691
532.5494 288.724542.4438 288.148552.3384285.9196562.2328 284.485572.1274285.0798
591.9164  288.11601.8109288.9703661.1779289.1852720.5449288.8001800.4879289.7347
910.4097290.1266980.3598289.84051070.296290.58241110.267290.48331140.246291.1461
1280.146291.11751320.118292.03651330.111292.77191340.104294.06981350.097294.5988
#Mann= 3 ,-1 , 0
       0     .05       0532.5494    .035       0601.8109     .05       0
Bank Sta=532.5494,601.8109
XS Rating Curve= 0 ,0
Exp/Cntr=0.3,0.1

Chan Stop Cuts=-1
Use User Specified Reach Order=0
Composite Channel Slope=5