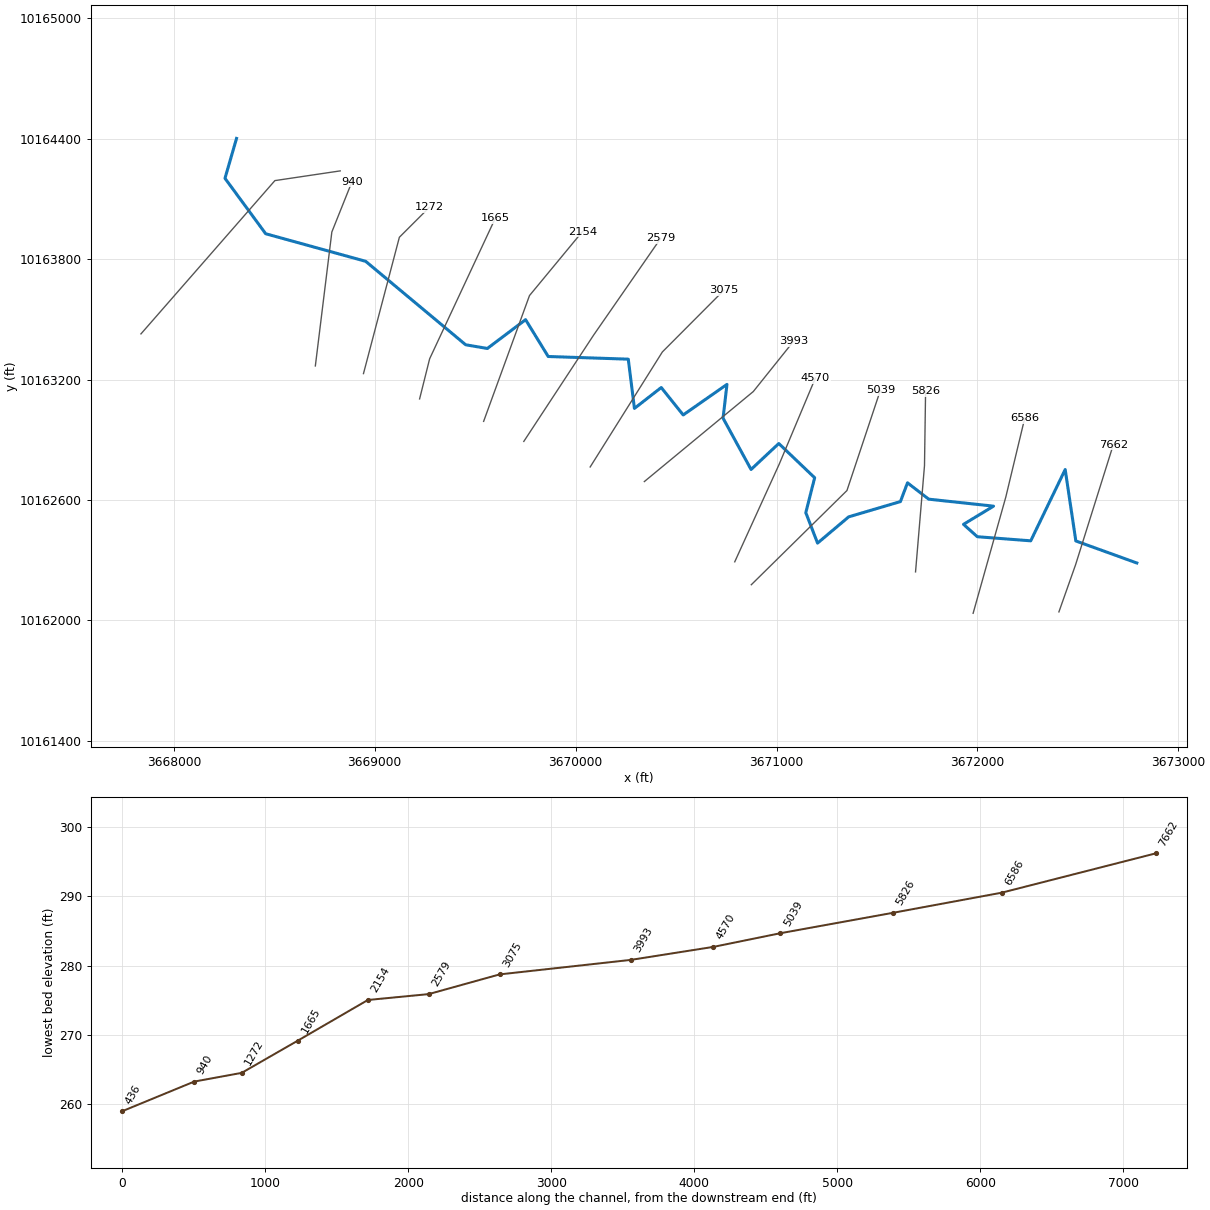
--- UNT052 IN ROCK.prj (project) ---

Proj Title=UNT052 IN ROCK Base Level Engineering
Current Plan=p01
Default Exp/Contr=0.3,0.1
English Units
Geom File=g01
Flow File=f01
Plan File=p01
BEGIN DESCRIPTION:
UNT052 IN ROCK
END DESCRIPTION:

--- UNT052 IN ROCK.p01 (plan) ---

Plan Title=Multiple Run
Short Identifier=Multiple
Geom File=g01
Flow File=f01
Subcritical Flow
K Sum by GR= 0
Std Step Tol= 0.01
Critical Tol= 0.01
Num of Std Step Trials= 20
Max Error Tol= 0.3
Flow Tol Ratio= 0.001
Split Flow NTrial= 30
Split Flow Tol= 0.02
Split Flow Ratio= 0.02
Log Output Level= 0
Friction Slope Method= 1
Unsteady Friction Slope Method= 2
Unsteady Bridges Friction Slope Method= 1
Parabolic Critical Depth
Global Vel Dist=  1 , 1 , 1
Global Log Level= 0
CheckData=True
Encroach Param= -1, 0, 0, 0
BEGIN DESCRIPTION:
Multiple Run
END DESCRIPTION:

--- UNT052 IN ROCK.f01 (steady flow) ---

Flow Title=Multiple
Number of Profiles=7
Profile Names=10-year,25-year,50-year,1pct_min,100-year,1pct_plu,500-year
River Rch & RM= UNT052 IN ROCK,Reach-1,7662
     964    1327    1629    1464    1979    2677    2923
Boundary for River Rch & Prof#=UNT052 IN ROCK,Reach-1,1
Up Type=0
Dn Type=3
Dn Slope=0.005
Boundary for River Rch & Prof#=UNT052 IN ROCK,Reach-1,2
Up Type=0
Dn Type=3
Dn Slope=0.005
Boundary for River Rch & Prof#=UNT052 IN ROCK,Reach-1,3
Up Type=0
Dn Type=3
Dn Slope=0.005
Boundary for River Rch & Prof#=UNT052 IN ROCK,Reach-1,4
Up Type=0
Dn Type=3
Dn Slope=0.005
Boundary for River Rch & Prof#=UNT052 IN ROCK,Reach-1,5
Up Type=0
Dn Type=3
Dn Slope=0.005
Boundary for River Rch & Prof#=UNT052 IN ROCK,Reach-1,6
Up Type=0
Dn Type=3
Dn Slope=0.005
Boundary for River Rch & Prof#=UNT052 IN ROCK,Reach-1,7
Up Type=0
Dn Type=3
Dn Slope=0.005

--- UNT052 IN ROCK.g01 (geometry) ---

Geom Title=Existing Conditions

River Reach=UNT052 IN ROCK,Reach-1
Reach XY= 30
      3672793.63     10162285.87      3672490.06     10162395.69
      3672437.05     10162751.75      3672265.59     10162396.39
      3671999.49     10162416.81      3671930.89     10162478.54
      3672080.38     10162569.16      3671757.73     10162603.90
      3671652.10     10162685.40      3671616.89     10162591.94
      3671359.41     10162515.84      3671204.44     10162385.02
      3671145.77     10162536.65      3671189.94     10162710.62
      3671011.40     10162881.30      3670873.32     10162751.85
      3670733.94     10163007.60      3670753.41     10163175.95
      3670535.52     10163023.58      3670426.23     10163160.32
      3670292.74     10163056.14      3670262.11     10163301.60
      3669863.55     10163314.87      3669750.94     10163498.45
      3669560.73     10163354.89      3669452.71     10163373.32
      3668954.75     10163789.31      3668457.21     10163926.60
      3668254.60     10164202.88      3668312.11     10164401.64

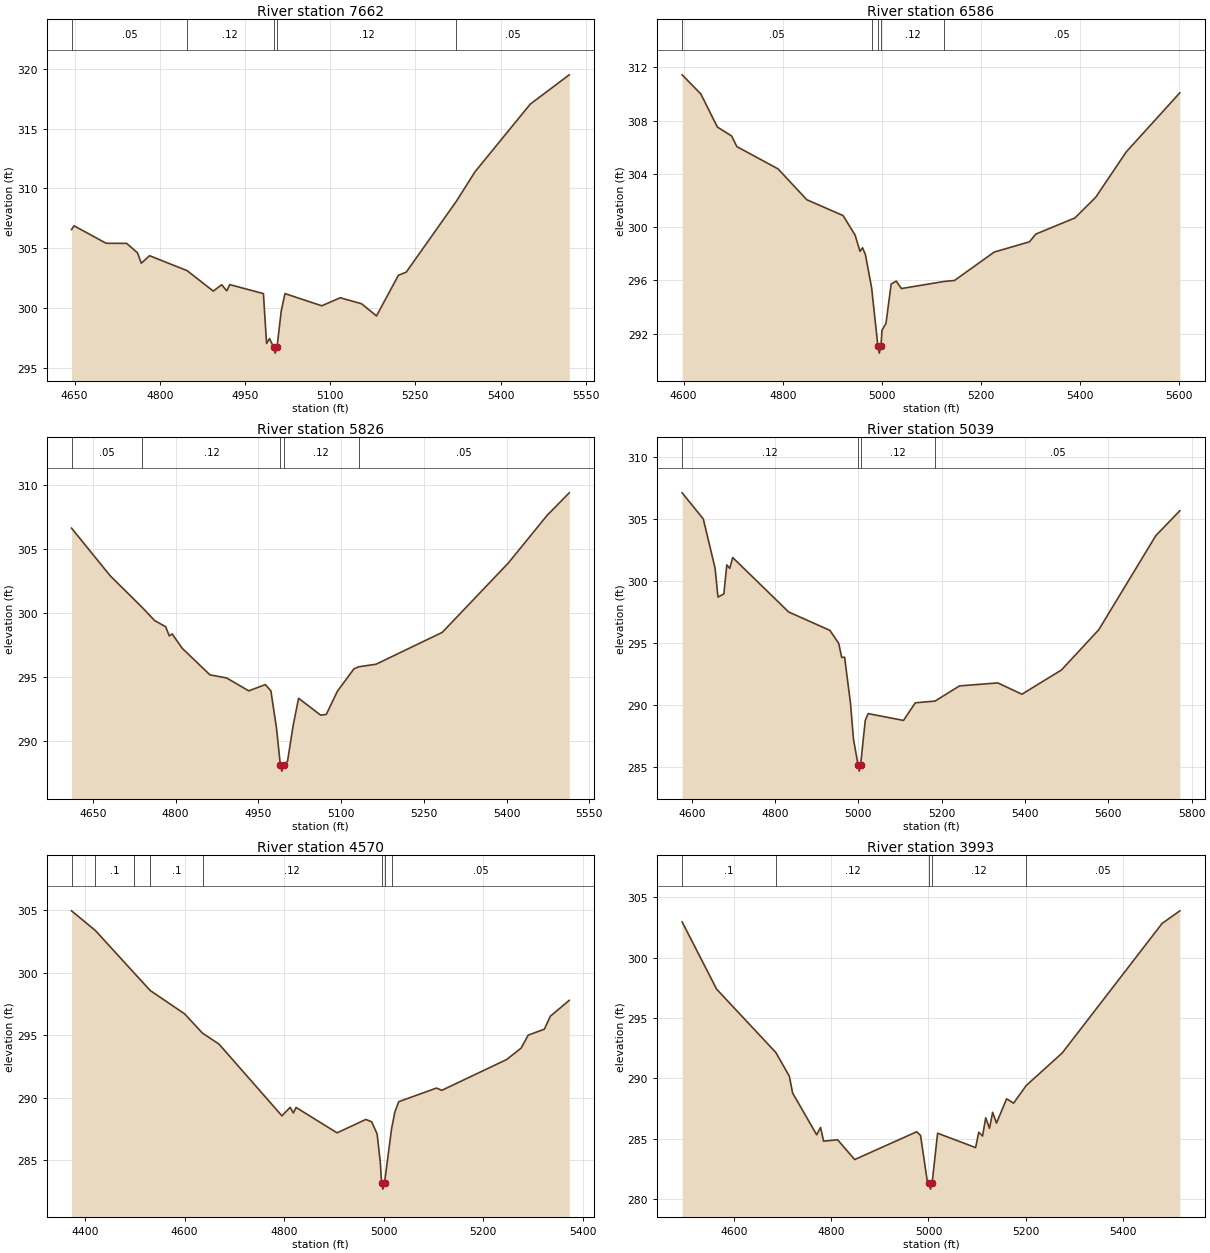
Type RM Length L Ch R = 1,7662,1076,1076,1076
BEGIN DESCRIPTION:
UNT052 IN ROCK 13.0
END DESCRIPTION:
XS GIS Cut Line= 3
      3672405.80     10162042.12      3672489.13     10162278.23
      3672676.62     10162875.41
#Sta/Elev= 30
  4644.7  306.56  4649.1  306.87  4705.6  305.41  4741.8  305.40  4760.8  304.61
  4767.5  303.74  4782.0  304.37  4848.2  303.12  4894.2  301.41  4909.1  301.94
  4918.0  301.43  4923.3  301.95  4982.5  301.20  4988.1  297.03  4993.3  297.44
  5000.5  296.72  5003.2  296.22  5006.5  296.72  5013.9  299.74  5020.5  301.20
  5085.3  300.18  5117.8  300.85  5155.4  300.35  5181.6  299.33  5220.2  302.73
  5234.1  303.00  5322.5  308.94  5355.1  311.39  5452.4  317.05  5521.0  319.50
#Mann=5,-1,0
  4644.7    0.05       0  4848.2    0.12       0  5000.5    0.07       0
  5006.5    0.12       0  5322.5    0.05       0
Bank Sta=5000.5,5006.5
Exp/Cntr=0.3,0.1

Type RM Length L Ch R = 1,6586,760,760,760
BEGIN DESCRIPTION:
UNT052 IN ROCK 12.0
END DESCRIPTION:
XS GIS Cut Line= 3
      3671978.73     10162035.22      3672141.29     10162613.90
      3672235.56     10163006.97
#Sta/Elev= 30
  4596.9  311.44  4634.7  310.00  4668.0  307.52  4696.8  306.85  4707.4  306.05
  4790.5  304.38  4848.7  302.06  4922.0  300.87  4946.3  299.40  4956.1  298.19
  4961.3  298.45  4967.1  297.94  4979.7  295.43  4992.4  291.04  4995.1  290.54
  4998.4  291.04  5000.6  292.26  5008.7  292.78  5019.1  295.73  5029.4  295.95
  5039.8  295.39  5125.8  295.92  5147.2  296.00  5227.3  298.13  5298.5  298.90
  5311.3  299.48  5390.2  300.69  5432.2  302.24  5493.9  305.65  5602.2  310.09
#Mann=5,-1,0
  4596.9    0.05       0  4979.7    0.12       0  4992.4    0.07       0
  4998.4    0.12       0  5125.8    0.05       0
Bank Sta=4992.4,4998.4
Exp/Cntr=0.3,0.1

Type RM Length L Ch R = 1,5826,787,787,787
BEGIN DESCRIPTION:
UNT052 IN ROCK 11.0
END DESCRIPTION:
XS GIS Cut Line= 3
      3671692.10     10162241.60      3671736.68     10162771.10
      3671742.11     10163141.69
#Sta/Elev= 30
  4611.6  306.61  4681.9  302.88  4740.1  300.40  4762.2  299.39  4782.2  298.91
  4788.8  298.19  4793.9  298.35  4812.3  297.22  4862.5  295.15  4892.6  294.91
  4932.8  293.90  4962.9  294.39  4972.9  293.90  4982.9  291.04  4990.0  288.13
  4992.7  287.63  4996.0  288.13  5003.0  288.39  5013.1  291.16  5023.1  293.32
  5063.2  292.00  5073.3  292.06  5093.3  293.86  5123.4  295.62  5131.8  295.78
  5163.5  295.98  5283.5  298.47  5403.5  303.90  5473.5  307.61  5513.6  309.37
#Mann=5,-1,0
  4611.6    0.05       0  4740.1    0.12       0  4990.0    0.07       0
  4996.0    0.12       0  5131.8    0.05       0
Bank Sta=4990,4996
Exp/Cntr=0.3,0.1

Type RM Length L Ch R = 1,5039,469,469,469
BEGIN DESCRIPTION:
UNT052 IN ROCK 10.0
END DESCRIPTION:
XS GIS Cut Line= 3
      3670874.58     10162177.56      3671350.68     10162646.98
      3671516.90     10163146.24
#Sta/Elev= 30
  4576.9  307.08  4627.6  304.98  4655.9  301.03  4662.9  298.69  4677.0  298.94
  4684.1  301.28  4691.2  301.00  4698.3  301.87  4832.6  297.49  4931.6  296.01
  4952.8  294.96  4959.9  293.83  4966.9  293.85  4981.0  290.16  4988.2  287.25
  4999.3  285.18  5002.1  284.68  5005.3  285.18  5016.5  288.76  5023.5  289.31
  5108.3  288.76  5136.6  290.18  5184.1  290.32  5242.7  291.54  5334.7  291.78
  5392.6  290.87  5487.5  292.82  5577.1  296.06  5714.2  303.64  5771.7  305.64
#Mann=4,-1,0
  4576.9    0.12       0  4999.3    0.07       0  5005.3    0.12       0
  5184.1    0.05       0
Bank Sta=4999.3,5005.3
Exp/Cntr=0.3,0.1

Type RM Length L Ch R = 1,4570,577,577,577
BEGIN DESCRIPTION:
UNT052 IN ROCK 9.0
END DESCRIPTION:
XS GIS Cut Line= 3
      3670792.12     10162291.68      3671013.44     10162778.23
      3671193.53     10163207.68
#Sta/Elev= 30
  4372.8  304.95  4420.9  303.37  4498.4  299.99  4530.9  298.58  4600.1  296.71
  4636.0  295.17  4669.3  294.29  4795.6  288.56  4812.2  289.24  4818.6  288.79
  4824.1  289.23  4906.4  287.20  4964.2  288.27  4976.1  288.08  4986.9  287.11
  4993.4  284.82  4995.8  283.20  4998.5  282.70  5001.8  283.20  5015.9  287.51
  5022.5  288.85  5030.3  289.69  5106.2  290.78  5117.0  290.60  5247.2  293.06
  5276.5  293.98  5290.5  295.01  5323.1  295.49  5334.9  296.52  5373.0  297.79
#Mann=8,-1,0
  4372.8    0.16       0  4420.9     0.1       0  4498.4    0.16       0
  4530.9     0.1       0  4636.0    0.12       0  4995.8    0.07       0
  5001.8    0.12       0  5015.9    0.05       0
Bank Sta=4995.8,5001.8
Exp/Cntr=0.3,0.1

Type RM Length L Ch R = 1,3993,918,918,918
BEGIN DESCRIPTION:
UNT052 IN ROCK 8.0
END DESCRIPTION:
XS GIS Cut Line= 3
      3670342.09     10162691.63      3670884.47     10163140.25
      3671084.45     10163390.23
#Sta/Elev= 30
  4493.2  302.95  4564.2  297.38  4685.9  292.14  4713.8  290.17  4720.5  288.78
  4770.0  285.32  4777.9  285.93  4784.3  284.79  4813.0  284.91  4848.2  283.27
  4975.8  285.57  4983.7  285.27  4998.0  281.37  5001.5  281.32  5004.2  280.82
  5007.5  281.32  5018.8  285.45  5097.0  284.26  5103.5  285.53  5111.3  285.22
  5117.8  286.73  5125.6  285.86  5132.1  287.18  5140.0  286.29  5160.8  288.30
  5175.1  287.94  5201.1  289.40  5275.3  292.10  5480.6  302.82  5517.2  303.87
#Mann=5,-1,0
  4493.2     0.1       0  4685.9    0.12       0  5001.5    0.07       0
  5007.5    0.12       0  5201.1    0.05       0
Bank Sta=5001.5,5007.5
Exp/Cntr=0.3,0.1

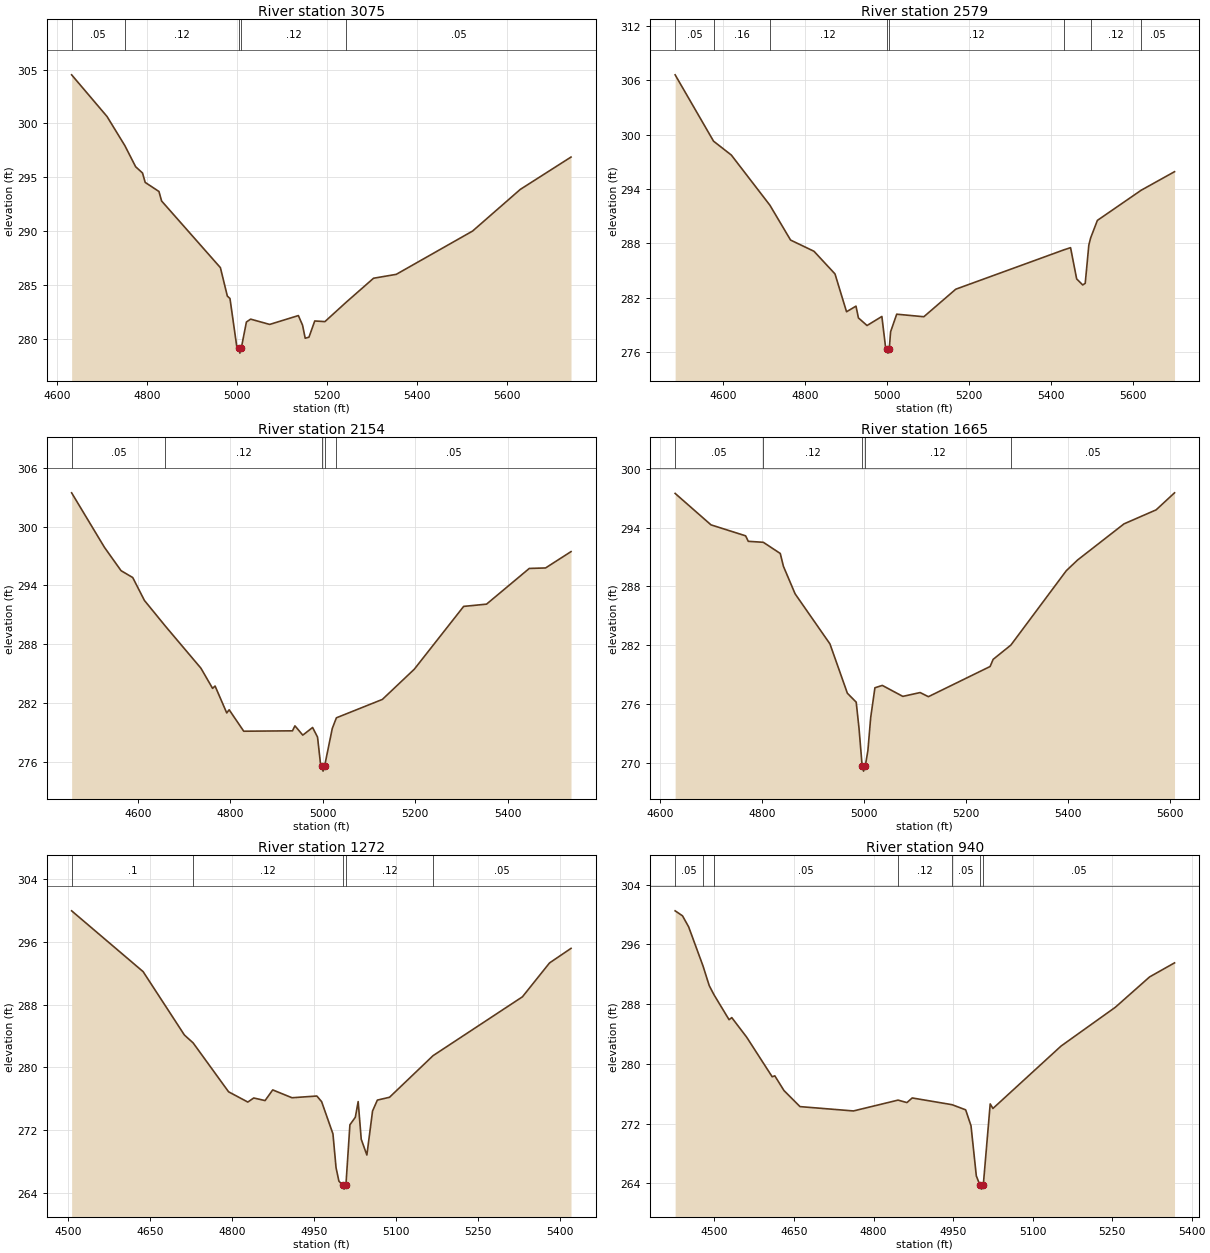
Type RM Length L Ch R = 1,3075,496,496,496
BEGIN DESCRIPTION:
UNT052 IN ROCK 7.0
END DESCRIPTION:
XS GIS Cut Line= 3
      3670072.49     10162764.37      3670431.79     10163337.54
      3670738.14     10163645.28
#Sta/Elev= 30
  4632.0  304.51  4710.7  300.65  4750.5  297.94  4774.4  295.99  4789.7  295.41
  4795.6  294.54  4826.2  293.70  4832.1  292.82  4962.9  286.64  4978.3  284.01
  4984.2  283.78  4999.5  279.27  5003.5  279.22  5006.2  278.72  5009.5  279.22
  5020.7  281.60  5030.1  281.87  5072.5  281.38  5136.3  282.20  5145.6  281.31
  5151.5  280.10  5159.9  280.20  5172.7  281.70  5195.3  281.64  5243.0  283.45
  5303.5  285.66  5354.0  286.02  5523.7  290.03  5629.8  293.89  5742.7  296.89
#Mann=5,-1,0
  4632.0    0.05       0  4750.5    0.12       0  5003.5    0.07       0
  5009.5    0.12       0  5243.0    0.05       0
Bank Sta=5003.5,5009.5
Exp/Cntr=0.3,0.1

Type RM Length L Ch R = 1,2579,425,425,425
BEGIN DESCRIPTION:
UNT052 IN ROCK 6.0
END DESCRIPTION:
XS GIS Cut Line= 3
      3669742.09     10162891.61      3670089.95     10163422.03
      3670423.15     10163903.21
#Sta/Elev= 30
  4483.0  306.61  4576.8  299.28  4620.2  297.75  4714.4  292.21  4764.9  288.36
  4822.1  287.12  4873.4  284.62  4901.6  280.44  4924.7  281.06  4930.6  279.76
  4951.7  278.92  4987.9  279.92  4997.0  276.48  5000.0  276.37  5002.7  275.87
  5006.0  276.37  5009.2  278.23  5024.1  280.17  5090.4  279.89  5168.3  282.93
  5432.6  287.28  5448.7  287.52  5463.6  284.07  5478.4  283.40  5484.5  283.58
  5493.3  287.80  5497.8  288.60  5514.2  290.53  5621.1  293.86  5702.6  295.91
#Mann=8,-1,0
  4483.0    0.05       0  4576.8    0.16       0  4714.4    0.12       0
  5000.0    0.07       0  5006.0    0.12       0  5432.6    0.05       0
  5497.8    0.12       0  5621.1    0.05       0
Bank Sta=5000,5006
Exp/Cntr=0.3,0.1

Type RM Length L Ch R = 1,2154,489,489,489
BEGIN DESCRIPTION:
UNT052 IN ROCK 5.0
END DESCRIPTION:
XS GIS Cut Line= 3
      3669542.12     10162991.68      3669770.38     10163618.50
      3670033.74     10163937.30
#Sta/Elev= 30
  4456.5  303.47  4527.6  297.89  4563.5  295.51  4588.7  294.81  4614.0  292.47
  4659.4  289.84  4736.3  285.54  4761.5  283.48  4766.9  283.72  4792.1  280.97
  4797.4  281.29  4828.9  279.10  4934.4  279.14  4939.7  279.65  4956.7  278.70
  4977.9  279.48  4988.6  278.50  4995.5  275.57  4997.8  275.52  5000.6  275.02
  5003.8  275.52  5020.5  279.38  5029.4  280.47  5128.9  282.35  5198.0  285.44
  5304.8  291.86  5354.3  292.09  5446.8  295.74  5482.0  295.79  5537.1  297.46
#Mann=5,-1,0
  4456.5    0.05       0  4659.4    0.12       0  4997.8    0.07       0
  5003.8    0.12       0  5029.4    0.05       0
Bank Sta=4997.8,5003.8
Exp/Cntr=0.3,0.1

Type RM Length L Ch R = 1,1665,393,393,393
BEGIN DESCRIPTION:
UNT052 IN ROCK 4.0
END DESCRIPTION:
XS GIS Cut Line= 3
      3669223.36     10163103.47      3669273.36     10163303.45
      3669600.24     10164003.90
#Sta/Elev= 30
  4629.8  297.50  4700.1  294.29  4768.0  293.17  4773.2  292.61  4802.7  292.51
  4835.9  291.37  4842.1  290.06  4865.0  287.25  4933.3  282.14  4967.5  277.10
  4984.8  276.19  4990.3  273.53  4996.5  269.65  4999.2  269.15  5002.5  269.65
  5007.7  271.24  5013.2  274.62  5021.5  277.66  5036.0  277.90  5076.2  276.78
  5110.1  277.17  5126.4  276.75  5247.3  279.83  5253.3  280.56  5288.1  282.02
  5396.7  289.61  5418.8  290.70  5509.8  294.39  5572.8  295.82  5608.9  297.56
#Mann=5,-1,0
  4629.8    0.05       0  4802.7    0.12       0  4996.5    0.07       0
  5002.5    0.12       0  5288.1    0.05       0
Bank Sta=4996.5,5002.5
Exp/Cntr=0.3,0.1

Type RM Length L Ch R = 1,1272,332,332,332
BEGIN DESCRIPTION:
UNT052 IN ROCK 3.0
END DESCRIPTION:
XS GIS Cut Line= 3
      3668944.01     10163229.66      3669122.66     10163909.00
      3669271.48     10164057.82
#Sta/Elev= 30
  4507.0  299.99  4637.7  292.23  4713.2  284.14  4729.1  283.14  4793.9  276.90
  4829.1  275.59  4839.9  276.11  4860.6  275.78  4874.6  277.14  4909.8  276.14
  4955.3  276.36  4964.0  275.64  4984.7  271.53  4990.4  267.20  4995.6  265.50
  5002.4  264.98  5005.1  264.48  5008.4  264.98  5015.7  272.69  5025.6  273.65
  5030.8  275.65  5036.4  270.85  5046.7  268.83  5057.1  274.45  5065.9  275.84
  5088.1  276.20  5167.7  281.51  5331.1  289.02  5380.6  293.34  5419.9  295.20
#Mann=5,-1,0
  4507.0     0.1       0  4729.1    0.12       0  5002.4    0.07       0
  5008.4    0.12       0  5167.7    0.05       0
Bank Sta=5002.4,5008.4
Exp/Cntr=0.3,0.1

Type RM Length L Ch R = 1,940,504,504,504
BEGIN DESCRIPTION:
UNT052 IN ROCK 2.0
END DESCRIPTION:
XS GIS Cut Line= 3
      3668704.42     10163267.86      3668786.55     10163935.39
      3668886.54     10164185.37
#Sta/Elev= 30
  4425.9  300.49  4439.8  299.82  4451.4  298.34  4478.5  293.10  4490.2  290.47
  4499.2  289.25  4527.6  285.91  4532.7  286.19  4560.7  283.58  4608.9  278.27
  4613.9  278.39  4631.2  276.42  4661.4  274.27  4762.2  273.69  4846.3  275.14
  4863.0  274.81  4873.0  275.43  4948.0  274.53  4973.8  273.84  4983.9  271.70
  4993.9  264.99  5001.0  263.72  5003.8  263.22  5007.0  263.72  5020.1  274.63
  5025.2  274.02  5153.7  282.38  5256.0  287.57  5320.7  291.64  5367.7  293.52
#Mann=7,-1,0
  4425.9    0.05       0  4478.5     0.1       0  4499.2    0.05       0
  4846.3    0.12       0  4948.0    0.05       0  5001.0    0.03       0
  5007.0    0.05       0
Bank Sta=5001,5007
Exp/Cntr=0.3,0.1

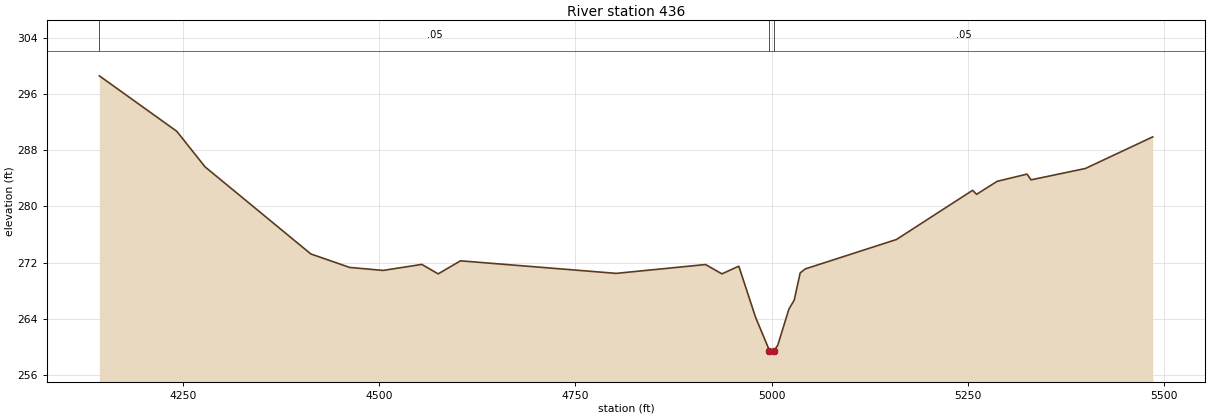
Type RM Length L Ch R = 1,436,0,0,0
BEGIN DESCRIPTION:
UNT052 IN ROCK 1.0
END DESCRIPTION:
XS GIS Cut Line= 3
      3667836.34     10163427.52      3668503.02     10164191.42
      3668828.23     10164239.86
#Sta/Elev= 30
  4143.1  298.63  4241.8  290.72  4277.9  285.64  4412.7  273.22  4462.1  271.30
  4504.8  270.87  4554.1  271.73  4575.0  270.38  4603.5  272.24  4801.9  270.45
  4915.8  271.71  4936.7  270.38  4958.2  271.48  4979.4  264.23  4997.3  259.43
  5000.0  258.93  5003.3  259.43  5007.9  260.22  5022.1  265.37  5028.8  266.63
  5036.4  270.51  5043.0  271.09  5159.1  275.28  5256.2  282.30  5261.3  281.73
  5287.5  283.58  5325.6  284.61  5330.6  283.79  5399.9  285.41  5485.8  289.92
#Mann=3,-1,0
  4143.1    0.05       0  4997.3    0.03       0  5003.3    0.05       0
Bank Sta=4997.3,5003.3
Exp/Cntr=0.3,0.1

Chan Stop Cuts=-1