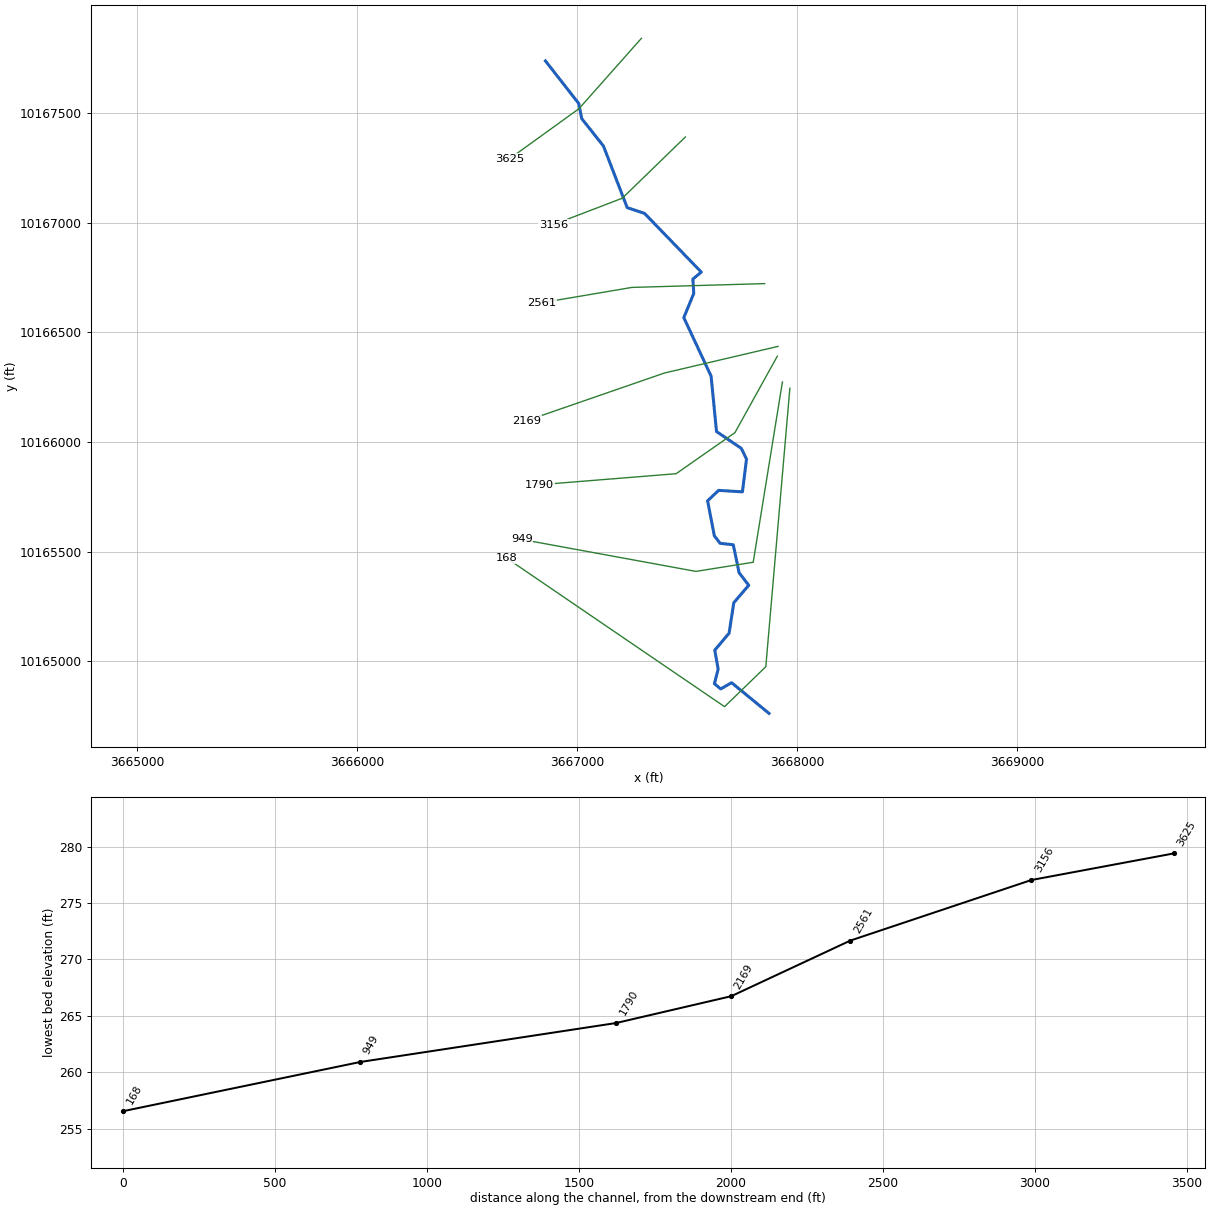
--- UNT054 IN ROCK.prj (project) ---

Proj Title=UNT054 IN ROCK Base Level Engineering
Current Plan=p01
Default Exp/Contr=0.3,0.1
English Units
Geom File=g01
Flow File=f01
Plan File=p01
Y Axis Title=Elevation
X Axis Title(PF)=Main Channel Distance
X Axis Title(XS)=Station
BEGIN DESCRIPTION:
UNT054 IN ROCK
END DESCRIPTION:
DSS Export Rating Curves= 0
DSS Export Rating Curve Sorted= 0
DSS Export Volume Flow Curves= 0
DXF OffsetX= 0
DXF OffsetY= 0
DXF ScaleX= 1
DXF ScaleY= 10

--- UNT054 IN ROCK.p01 (plan) ---

Plan Title=Multiple Run
Short Identifier=Multiple
Geom File=g01
Flow File=f01
Subcritical Flow
K Sum by GR= 0
Std Step Tol= 0.01
Critical Tol= 0.01
Num of Std Step Trials= 20
Max Error Tol= 0.3
Flow Tol Ratio= 0.001
Split Flow NTrial= 30
Split Flow Tol= 0.02
Split Flow Ratio= 0.02
Log Output Level= 0
Friction Slope Method= 1
Unsteady Friction Slope Method= 2
Unsteady Bridges Friction Slope Method= 1
Parabolic Critical Depth
Global Vel Dist=  1 , 1 , 1
Global Log Level= 0
CheckData=True
Encroach Param= -1, 0, 0, 0
BEGIN DESCRIPTION:
Multiple Run
END DESCRIPTION:

--- UNT054 IN ROCK.f01 (steady flow) ---

Flow Title=Multiple
Number of Profiles=7
Profile Names=10-year,25-year,50-year,1pct_min,100-year,1pct_plu,500-year
River Rch & RM= UNT054 IN ROCK,Reach-1,3625
     979    1353    1666    1503    2033    2749    3025
Boundary for River Rch & Prof#=UNT054 IN ROCK,Reach-1,1
Up Type=0
Dn Type=3
Dn Slope=0.005
Boundary for River Rch & Prof#=UNT054 IN ROCK,Reach-1,2
Up Type=0
Dn Type=3
Dn Slope=0.005
Boundary for River Rch & Prof#=UNT054 IN ROCK,Reach-1,3
Up Type=0
Dn Type=3
Dn Slope=0.005
Boundary for River Rch & Prof#=UNT054 IN ROCK,Reach-1,4
Up Type=0
Dn Type=3
Dn Slope=0.005
Boundary for River Rch & Prof#=UNT054 IN ROCK,Reach-1,5
Up Type=0
Dn Type=3
Dn Slope=0.005
Boundary for River Rch & Prof#=UNT054 IN ROCK,Reach-1,6
Up Type=0
Dn Type=3
Dn Slope=0.005
Boundary for River Rch & Prof#=UNT054 IN ROCK,Reach-1,7
Up Type=0
Dn Type=3
Dn Slope=0.005

--- UNT054 IN ROCK.g01 (geometry) ---

Geom Title=Existing Conditions
Program Version=4.10

River Reach=UNT054 IN ROCK  ,Reach-1
Reach XY= 30
      3666856.06     10167738.57      3667007.34     10167544.36
      3667020.84     10167475.44      3667119.51     10167350.57
      3667227.67     10167069.16      3667306.49     10167042.87
      3667564.29      10166775.1      3667526.18      10166743.3
      3667530.09     10166677.62       3667484.9     10166567.42
      3667608.97     10166300.34      3667633.51     10166047.49
       3667745.9     10165971.18      3667769.93      10165921.9
      3667751.46     10165772.45      3667643.08     10165779.09
      3667593.04     10165731.52      3667623.66     10165571.82
      3667649.82     10165537.66      3667709.81     10165530.88
      3667736.24     10165403.37      3667779.98     10165346.06
      3667712.12     10165266.63      3667690.67     10165127.27
      3667625.51     10165050.05      3667641.12     10164963.69
       3667624.1     10164896.82      3667652.66     10164873.13
      3667702.11     10164901.64      3667872.11     10164761.64

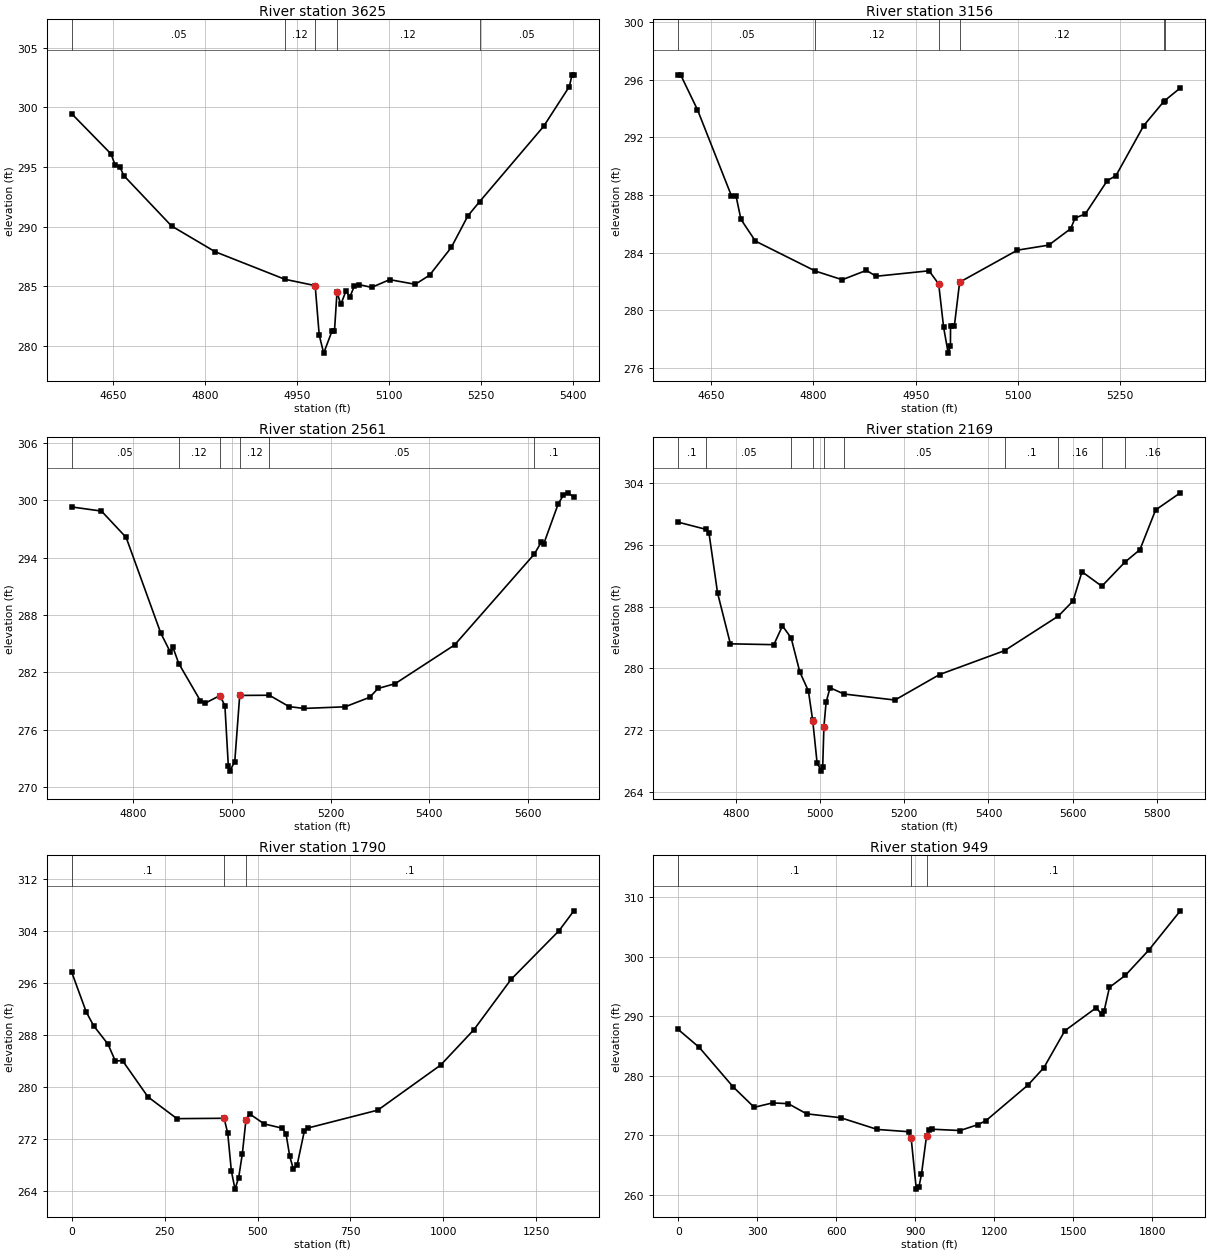
Type RM Length L Ch R = 1 ,3625    ,469,469,469
BEGIN DESCRIPTION:
UNT054 IN ROCK 5.0
END DESCRIPTION:
XS GIS Cut Line= 3
      3667292.13     10167841.67      3667008.35     10167520.57
      3666692.14     10167291.66
#Sta/Elev= 30
  4582.2  299.45  4646.2  296.09  4652.9  295.16  4660.5  295.02  4667.1  294.27
  4744.9  290.05    4816  287.89  4929.8  285.58  4979.2  285.05  4985.8   280.9
  4993.1  279.39  5006.7  281.25  5010.7  281.25  5014.8  284.51    5021  283.47
  5029.5  284.61  5035.7  284.08  5043.1  285.02  5050.4  285.14  5071.3   284.9
  5100.7  285.55  5142.4  285.16  5165.7  285.92  5201.2  288.25  5228.3   290.9
  5247.6   292.1  5351.8   298.4  5393.8  301.74  5398.1  302.72  5401.1  302.72
#Mann= 5 ,-1 , 0
  4582.2     .05       0  4929.8     .12       0  4979.2     .07       0
  5014.8     .12       0  5247.6     .05       0
Bank Sta=4979.2,5014.8
XS Rating Curve= 0 ,0
Exp/Cntr=0.3,0.1

Type RM Length L Ch R = 1 ,3156    ,595,595,595
BEGIN DESCRIPTION:
UNT054 IN ROCK 4.0
END DESCRIPTION:
XS GIS Cut Line= 3
      3667492.09     10167391.63      3667205.22     10167112.16
      3666892.11     10166991.64
#Sta/Elev= 30
  4601.9  296.33  4605.4  296.33  4630.1  293.91  4679.7  287.96  4686.7  287.91
  4693.8  286.31    4715   284.8    4803  282.72  4842.3  282.12  4877.7  282.77
  4891.9  282.36  4969.6  282.74  4983.7  281.82  4990.9  278.83  4997.6  277.03
  5000.9  277.53  5001.1  278.92  5006.7  278.92  5014.4  281.95    5099  284.17
    5145  284.52  5177.2  285.66  5183.7   286.4  5198.6  286.68  5230.8  288.99
  5243.6  289.34  5284.3  292.81  5313.5  294.47  5314.8  294.53  5337.9  295.42
#Mann= 6 ,-1 , 0
  4601.9     .05       0    4803     .12       0  4983.7     .07       0
  5014.4     .12       0  5313.5      .1       0  5314.8     .16       0
Bank Sta=4983.7,5014.4
XS Rating Curve= 0 ,0
Exp/Cntr=0.3,0.1

Type RM Length L Ch R = 1 ,2561    ,392,392,392
BEGIN DESCRIPTION:
UNT054 IN ROCK 3.0
END DESCRIPTION:
XS GIS Cut Line= 3
       3667852.3     10166722.53      3667249.02     10166705.17
      3666841.02     10166635.73
#Sta/Elev= 30
  4675.7  299.31  4735.9  298.88  4785.9  296.12    4856  286.12  4875.7  284.09
  4880.7  284.62  4892.5  282.93    4936  279.06    4946  278.78    4976  279.58
    4986  278.51    4993  272.17  4995.8  271.67    5006  272.67    5016  279.59
  5076.1  279.61  5116.1  278.42  5146.1  278.23  5229.6   278.4  5279.2  279.39
  5296.4  280.32    5331  280.82  5451.4  284.87    5613  294.38  5627.1  295.63
  5632.1  295.45  5661.6  299.66  5671.7  300.52  5681.9  300.79  5693.1  300.32
#Mann= 6 ,-1 , 0
  4675.7     .05       0  4892.5     .12       0    4976     .07       0
    5016     .12       0  5076.1     .05       0    5613      .1       0
Bank Sta=4976,5016
XS Rating Curve= 0 ,0
Exp/Cntr=0.3,0.1

Type RM Length L Ch R = 1 ,2169    ,379,379,379
BEGIN DESCRIPTION:
UNT054 IN ROCK 2.0
END DESCRIPTION:
XS GIS Cut Line= 3
      3667913.04     10166436.06      3667396.59     10166314.55
      3666771.55     10166097.52
#Sta/Elev= 30
  4663.4  298.89  4729.4  297.96  4736.3  297.53  4756.8  289.74  4787.2  283.18
  4890.4  283.07  4910.9   285.5  4931.5  283.94    4952  279.56  4972.5  277.09
  4982.6  273.32  4982.8  273.25  4993.1  267.81  5003.1  266.74  5006.4  267.24
  5009.3  272.47  5014.5  275.63  5023.9  277.51  5056.8   276.7    5178  275.92
  5283.8  279.21  5438.3   282.3  5566.1  286.77    5601  288.72  5622.1  292.49
  5669.2  290.62  5723.9  293.72  5759.7  295.34    5797  300.47  5855.6  302.68
#Mann= 10 ,-1 , 0
  4663.4      .1       0  4729.4     .05       0  4931.5     .12       0
  4982.6     .07       0  5009.3     .12       0  5056.8     .05       0
  5438.3      .1       0  5566.1     .16       0  5669.2      .1       0
  5723.9     .16       0
Bank Sta=4982.8,5009.3
XS Rating Curve= 0 ,0
Exp/Cntr=0.3,0.1

Type RM Length L Ch R = 1 ,1790    ,841,841,841
XS GIS Cut Line= 4
      3667910.13    10166391.655     3667717.422    10166042.696
     3667450.061    10165855.196     3666828.533    10165804.849
#Sta/Elev= 30
       0 297.602 39.0394291.5235 58.5591289.4436 97.5985286.5869117.1182  284.02
136.6379284.0669204.9568278.5157283.0356275.1725409.9762275.2276419.7985272.9647
429.6208267.1167439.4432264.3629449.2655266.1322459.0879269.7733468.9102275.0059
478.7325 275.904518.0219274.3603567.1335273.7026576.9559272.7619586.7783 269.384
596.6006267.4088606.4229268.0057626.0676273.2821635.8899 273.737823.8412276.4783
993.0765 283.3951082.672 288.8261182.222296.51271311.637303.99631351.457307.0428
#Mann= 3 , 0 , 0
       0      .1       0409.9762     .05       0468.9102      .1       0
Bank Sta=409.9762,468.9102
XS Rating Curve= 0 ,0
Exp/Cntr=0.3,0.1

Type RM Length L Ch R = 1 ,949     ,781,781,781
XS GIS Cut Line= 4
     3667933.134    10166274.033     3667800.321    10165451.116
     3667539.905     10165409.45     3666748.238    10165555.283
#Sta/Elev= 30
       0287.7593 79.5373284.7571208.7854278.0894288.3227274.6725357.9178275.4118
417.5708275.2856 487.166273.5783616.4141272.9203755.6043270.9498874.2126270.5695
883.9803269.5064903.5158 260.914913.2835261.2437923.0513263.3745942.5867269.9183
952.3545270.8781962.1223270.98951069.567270.76761138.707 271.7761168.585272.4527
1327.932278.43961387.687281.3361 1467.36287.54931586.871291.42591606.789290.3001
1616.748290.94671636.667294.84871696.422296.83981786.054301.11541905.565307.7129
#Mann= 3 , 0 , 0
       0      .1       0883.9803     .05       0942.5867      .1       0
Bank Sta=883.9803,942.5867
XS Rating Curve= 0 ,0
Exp/Cntr=0.3,0.1

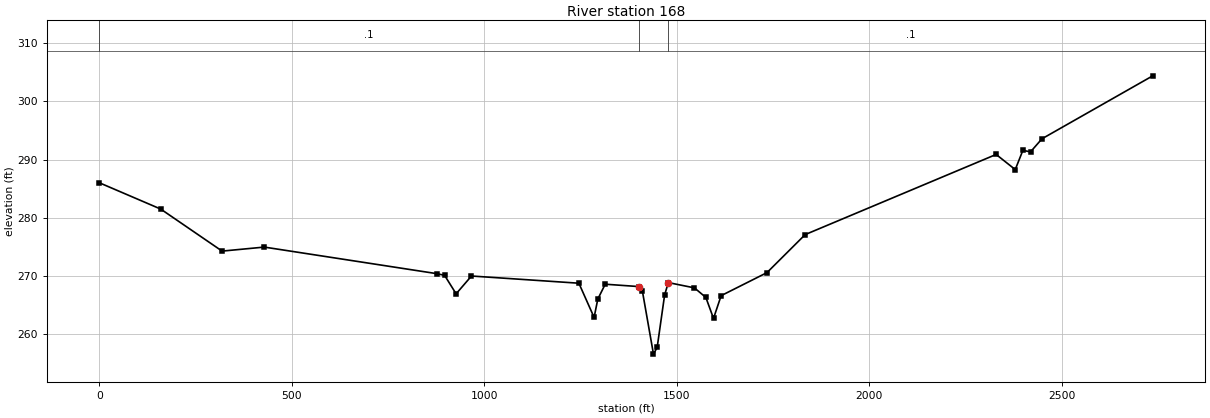
Type RM Length L Ch R = 1 ,168     ,0,0,0
XS GIS Cut Line= 4
     3667966.988    10166245.387     3667857.613    10164974.554
     3667670.113    10164792.262      3666680.53    10165469.346
#Sta/Elev= 30
       0286.0225159.4414281.4991318.8828274.2687428.4988274.9597876.9278270.3878
 896.858270.0958926.7532266.9223966.6136269.98541245.636268.74631285.171262.8653
 1294.81266.02111314.089268.57491400.845268.17191410.484267.44161439.403256.5508
1449.042257.71911468.321266.71611477.961268.85371545.719 267.9471575.483266.2999
1595.326262.69171615.168 266.6071734.224270.56791833.438277.10862329.504 290.894
2379.111288.28912398.954291.59882418.796291.3356 2448.56293.58692736.279304.4139
#Mann= 3 , 0 , 0
       0      .1       01400.845     .05       01477.961      .1       0
Bank Sta=1400.845,1477.961
XS Rating Curve= 0 ,0
Exp/Cntr=0.3,0.1

Chan Stop Cuts=-1
Use User Specified Reach Order=0
Composite Channel Slope=5