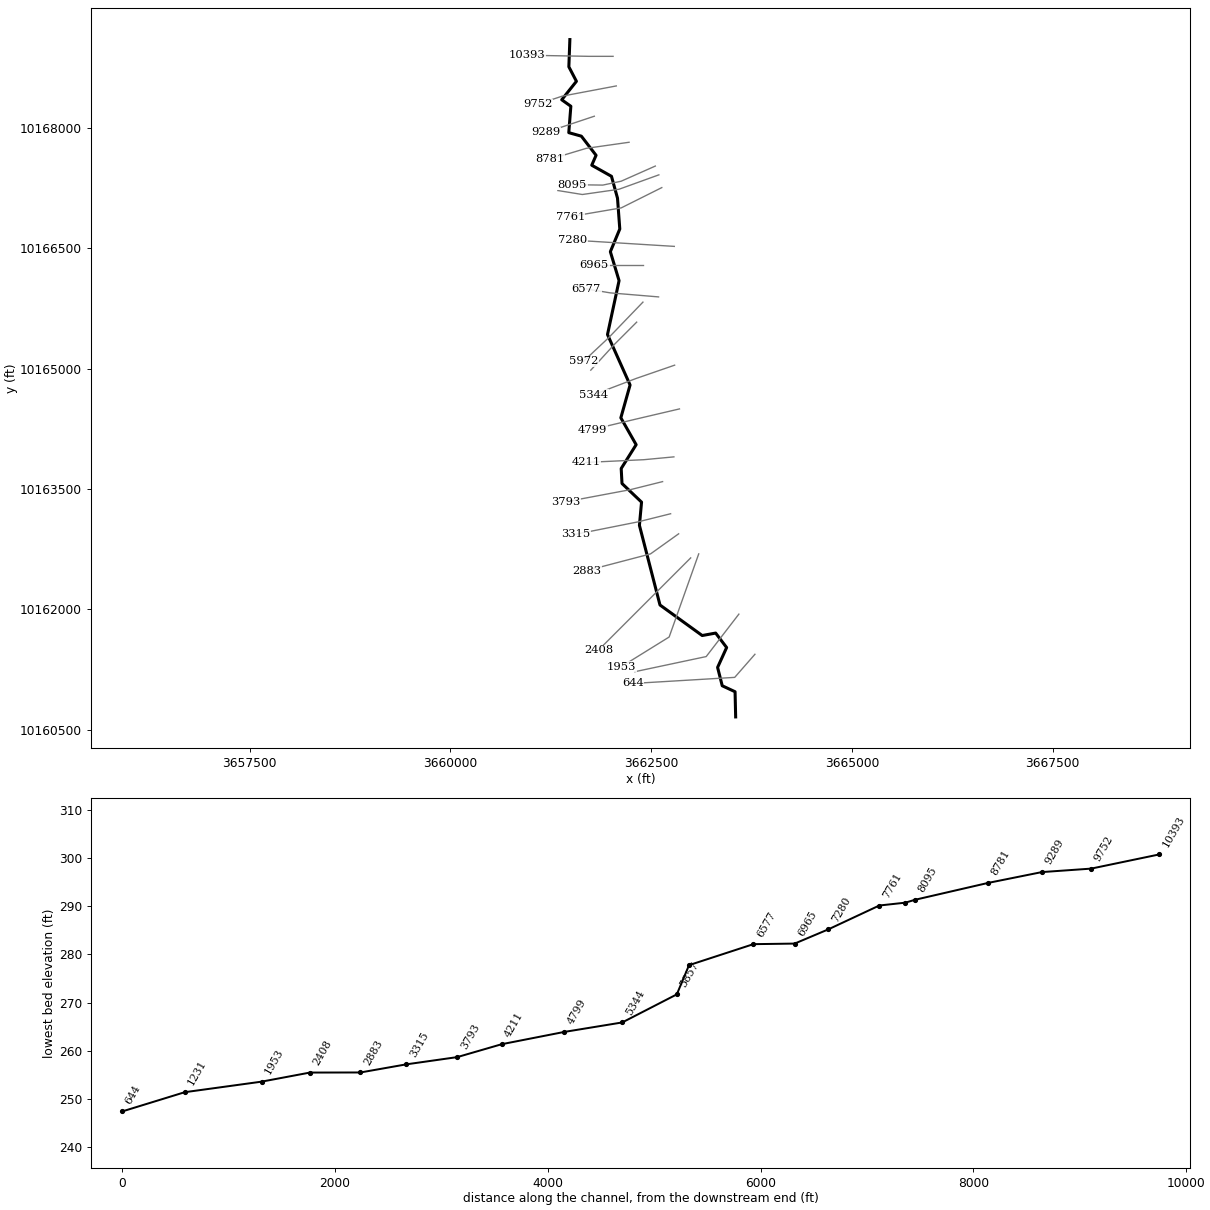
--- UNT055 IN ROCK.prj (project) ---

Proj Title=UNT055 IN ROCK Base Level Engineering
Current Plan=p01
Default Exp/Contr=0.3,0.1
English Units
Geom File=g01
Flow File=f01
Plan File=p01
Y Axis Title=Elevation
X Axis Title(PF)=Main Channel Distance
X Axis Title(XS)=Station
BEGIN DESCRIPTION:
UNT055 IN ROCK
END DESCRIPTION:
DSS Export Rating Curves= 0
DSS Export Rating Curve Sorted= 0
DSS Export Volume Flow Curves= 0
DXF OffsetX= 0
DXF OffsetY= 0
DXF ScaleX= 1
DXF ScaleY= 10

--- UNT055 IN ROCK.p01 (plan) ---

Plan Title=Multiple Run
Short Identifier=Multiple
Geom File=g01
Flow File=f01
Subcritical Flow
K Sum by GR= 0
Std Step Tol= 0.01
Critical Tol= 0.01
Num of Std Step Trials= 20
Max Error Tol= 0.3
Flow Tol Ratio= 0.001
Split Flow NTrial= 30
Split Flow Tol= 0.02
Split Flow Ratio= 0.02
Log Output Level= 0
Friction Slope Method= 1
Unsteady Friction Slope Method= 2
Unsteady Bridges Friction Slope Method= 1
Parabolic Critical Depth
Global Vel Dist=  1 , 1 , 1
Global Log Level= 0
CheckData=True
Encroach Param= -1, 0, 0, 0
BEGIN DESCRIPTION:
Multiple Run
END DESCRIPTION:

--- UNT055 IN ROCK.f01 (steady flow) ---

Flow Title=Multiple
Number of Profiles=7
Profile Names=10-year,25-year,50-year,1pct_min,100-year,1pct_plu,500-year
River Rch & RM= UNT055 IN ROCK,Reach-1,10393
    1033    1434    1772    1603    2167    2931    3245
Boundary for River Rch & Prof#=UNT055 IN ROCK,Reach-1,1
Up Type=0
Dn Type=3
Dn Slope=0.005
Boundary for River Rch & Prof#=UNT055 IN ROCK,Reach-1,2
Up Type=0
Dn Type=3
Dn Slope=0.005
Boundary for River Rch & Prof#=UNT055 IN ROCK,Reach-1,3
Up Type=0
Dn Type=3
Dn Slope=0.005
Boundary for River Rch & Prof#=UNT055 IN ROCK,Reach-1,4
Up Type=0
Dn Type=3
Dn Slope=0.005
Boundary for River Rch & Prof#=UNT055 IN ROCK,Reach-1,5
Up Type=0
Dn Type=3
Dn Slope=0.005
Boundary for River Rch & Prof#=UNT055 IN ROCK,Reach-1,6
Up Type=0
Dn Type=3
Dn Slope=0.005
Boundary for River Rch & Prof#=UNT055 IN ROCK,Reach-1,7
Up Type=0
Dn Type=3
Dn Slope=0.005

--- UNT055 IN ROCK.g01 (geometry) ---

Geom Title=Existing Conditions
Program Version=4.10

River Reach=UNT055 IN ROCK  ,Reach-1
Reach XY= 30
      3661487.65     10169096.06      3661475.04     10168756.84
       3661569.3     10168576.45      3661386.29     10168346.45
      3661499.83     10168265.74      3661474.13     10167936.92
       3661630.9     10167893.17      3661813.85      10167654.8
      3661760.03     10167531.53      3662005.69     10167393.51
      3662080.81     10167121.18      3662109.22     10166737.25
      3661991.83     10166454.58      3662100.31     10166094.03
      3661956.21     10165423.03      3662237.36     10164794.88
      3662122.42     10164386.14      3662312.92     10164051.38
      3662126.75     10163754.59      3662136.86     10163568.13
      3662380.23     10163336.16      3662353.78     10163047.44
      3662609.81     10162055.24      3663135.46     10161675.07
       3663303.2     10161705.67      3663439.71     10161525.33
      3663327.09     10161277.89      3663385.02     10161049.45
      3663544.76     10160975.06      3663552.11     10160661.64

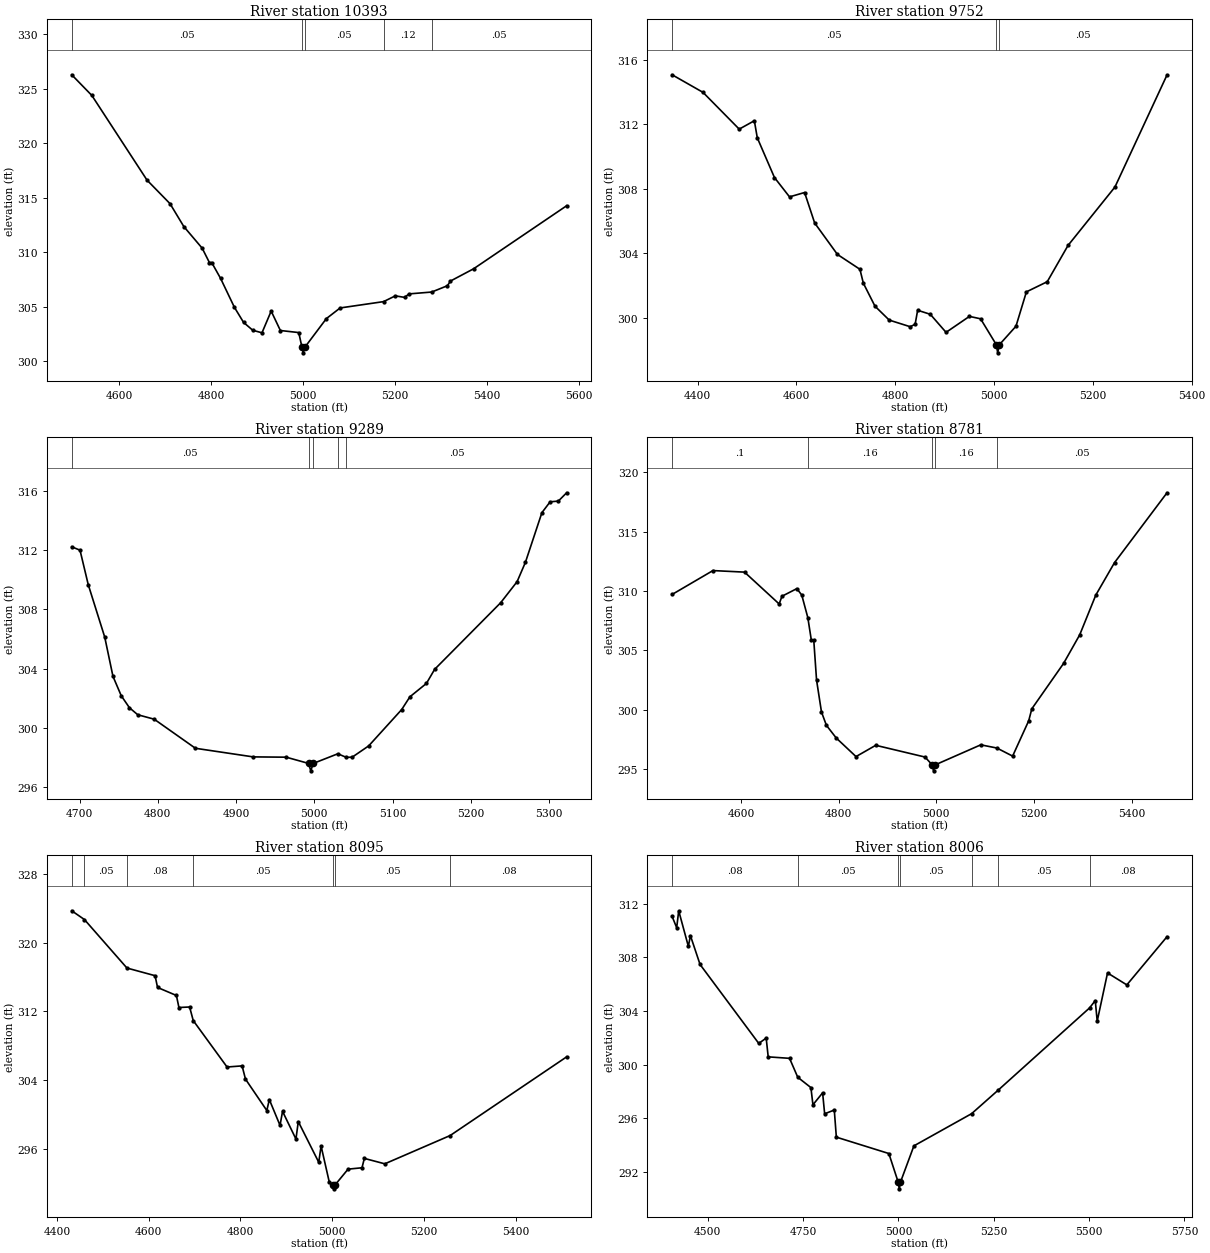
Type RM Length L Ch R = 1 ,10393   ,641,641,641
BEGIN DESCRIPTION:
UNT055 IN ROCK 21.0
END DESCRIPTION:
XS GIS Cut Line= 3
      3662025.86     10168887.29      3661725.91     10168887.29
      3660949.59     10168901.38
#Sta/Elev= 30
  4496.5   326.3  4540.3   324.4  4660.3  316.63  4710.3  314.47  4740.3  312.37
  4780.3  310.38  4795.9  309.07  4800.9  309.07  4820.3  307.61  4850.3  304.96
  4870.3  303.57  4890.3  302.85  4910.3  302.62  4930.3  304.61  4950.3  302.83
  4990.3  302.64  4997.3  301.28    5000  300.78  5003.3  301.28  5050.3  303.92
  5080.3   304.9  5174.7  305.48  5200.3  306.01  5220.3  305.87  5230.3  306.19
  5279.4  306.36  5313.6  306.94  5320.3  307.37  5370.4  308.49  5572.9  314.28
#Mann= 5 ,-1 , 0
  4496.5     .05       0  4997.3     .03       0  5003.3     .05       0
  5174.7     .12       0  5279.4     .05       0
Bank Sta=4997.3,5003.3
XS Rating Curve= 0 ,0
Exp/Cntr=0.3,0.1

Type RM Length L Ch R = 1 ,9752    ,463,463,463
BEGIN DESCRIPTION:
UNT055 IN ROCK 20.0
END DESCRIPTION:
XS GIS Cut Line= 3
      3662065.58      10168518.8      3661392.11     10168391.64
      3661092.11     10168291.64
#Sta/Elev= 30
  4348.4  315.07  4410.9  313.98  4484.2   311.7  4514.8  312.22  4520.8  311.16
  4555.5   308.7    4586   307.5  4616.5  307.77  4636.9  305.88    4683  303.93
  4728.5  303.01  4735.4  302.15    4759  300.72  4787.8  299.86  4830.2  299.45
  4840.2   299.6  4845.3  300.47  4870.9  300.22  4902.8   299.1  4950.1  300.09
  4972.7  299.94  5004.6  298.33  5007.3  297.83  5010.6  298.33  5044.3  299.48
  5065.4  301.61  5107.6  302.24  5149.7  304.49  5244.6  308.11    5350  315.06
#Mann= 3 ,-1 , 0
  4348.4     .05       0  5004.6     .03       0  5010.6     .05       0
Bank Sta=5004.6,5010.6
XS Rating Curve= 0 ,0
Exp/Cntr=0.3,0.1

Type RM Length L Ch R = 1 ,9289    ,508,508,508
BEGIN DESCRIPTION:
UNT055 IN ROCK 19.0
END DESCRIPTION:
XS GIS Cut Line= 3
      3661792.13     10168141.65      3661492.11     10168041.64
      3661192.09     10167941.64
#Sta/Elev= 30
    4690  312.21  4700.6  311.98  4711.1  309.66  4732.2  306.12  4742.7  303.48
  4753.3  302.17  4763.8  301.36  4774.4  300.89  4795.4  300.59  4848.1  298.63
  4921.9  298.05  4964.1  298.03  4992.7  297.61  4995.5  297.11  4998.7  297.61
  5030.1  298.26  5040.8  298.02  5048.4  298.03  5069.5  298.79  5111.7  301.24
  5122.2   302.1  5143.3     303  5153.8  303.95  5238.2  308.44  5259.2  309.86
  5269.8  311.16  5290.9  314.51  5301.4  315.24  5311.9  315.29  5322.5  315.85
#Mann= 5 ,-1 , 0
    4690     .05       0  4992.7     .03       0  4998.7     .05       0
  5030.1     .16       0  5040.8     .05       0
Bank Sta=4992.7,4998.7
XS Rating Curve= 0 ,0
Exp/Cntr=0.3,0.1

Type RM Length L Ch R = 1 ,8781    ,686,686,686
BEGIN DESCRIPTION:
UNT055 IN ROCK 18.0
END DESCRIPTION:
XS GIS Cut Line= 3
      3662224.92     10167817.37      3661692.11     10167741.64
      3661236.86      10167604.9
#Sta/Elev= 30
  4458.9   309.7  4542.5  311.71  4607.2  311.58  4678.1   308.9  4683.9  309.55
  4714.3  310.19  4724.4  309.65  4736.8  307.75  4743.9  305.88    4749  305.84
  4754.7  302.49  4764.8   299.8  4774.9  298.68  4795.1  297.61  4835.5  296.05
  4875.9     297  4976.9  296.01  4991.5  295.35  4994.3  294.85  4997.5  295.35
    5091  297.04    5124  296.77  5156.2  296.09  5189.2  299.07  5195.5  300.07
  5260.5  303.89  5293.6   306.3  5326.6  309.65  5364.9  312.38  5472.4  318.26
#Mann= 5 ,-1 , 0
  4458.9      .1       0  4736.8     .16       0  4991.5     .07       0
  4997.5     .16       0    5124     .05       0
Bank Sta=4991.5,4997.5
XS Rating Curve= 0 ,0
Exp/Cntr=0.3,0.1

Type RM Length L Ch R = 1 ,8095    ,89,89,89
BEGIN DESCRIPTION:
UNT055 IN ROCK 17.0
END DESCRIPTION:
XS GIS Cut Line= 4
      3662551.61     10167520.96      3662125.91     10167332.23
      3661897.98     10167283.99      3661517.75      10167289.2
#Sta/Elev= 30
  4432.2  323.69  4459.9  322.67  4552.6  317.03  4613.9  316.14  4619.3  314.77
  4660.4  313.84  4665.9  312.44  4689.2   312.5  4697.1  310.92  4770.8  305.52
  4803.6  305.65    4811  304.11  4857.5  300.46    4863  301.73  4886.3  298.73
  4891.8  300.36    4921  297.14  4926.1  299.17  4970.7  294.44  4975.8  296.33
  4993.7  292.13    5001  291.85  5003.7  291.35    5007  291.85  5034.6  293.64
    5065   293.8  5070.1  294.89  5114.7  294.26  5257.2  297.55  5511.1   306.7
#Mann= 7 ,-1 , 0
  4432.2     .08       0  4459.9     .05       0  4552.6     .08       0
  4697.1     .05       0    5001     .03       0    5007     .05       0
  5257.2     .08       0
Bank Sta=5001,5007
XS Rating Curve= 0 ,0
Exp/Cntr=0.3,0.1

Type RM Length L Ch R = 1 ,8006    ,245,245,245
BEGIN DESCRIPTION:
Mapping XS 46cd7e1e
END DESCRIPTION:
XS GIS Cut Line= 4
      3662595.91      10167411.6       3662098.5     10167231.91
      3661642.78     10167166.81      3661338.09     10167216.28
#Sta/Elev= 30
  4406.5  311.05  4418.5  310.21  4423.8  311.47  4449.1  308.82  4454.5  309.62
  4479.8  307.47  4633.8  301.59  4653.2  301.99  4658.5  300.59  4714.5  300.48
    4736  299.07  4770.5   298.3  4775.8  297.02  4801.2  297.91  4806.5  296.35
  4831.8  296.63  4837.2  294.61  4974.9  293.39  4999.4  291.26  5002.2  290.76
  5005.4  291.26  5040.6  293.96    5192  296.36  5261.6  298.11  5501.1  304.23
  5516.2  304.78  5521.3  303.25  5548.4  306.84    5599  305.95  5704.4  309.54
#Mann= 7 ,-1 , 0
  4406.5     .08       0    4736     .05       0  4999.4     .04       0
  5005.4     .05       0    5192     .08       0  5261.6     .05       0
  5501.1     .08       0
Bank Sta=4999.4,5005.4
XS Rating Curve= 0 ,0
Exp/Cntr=0.3,0.1

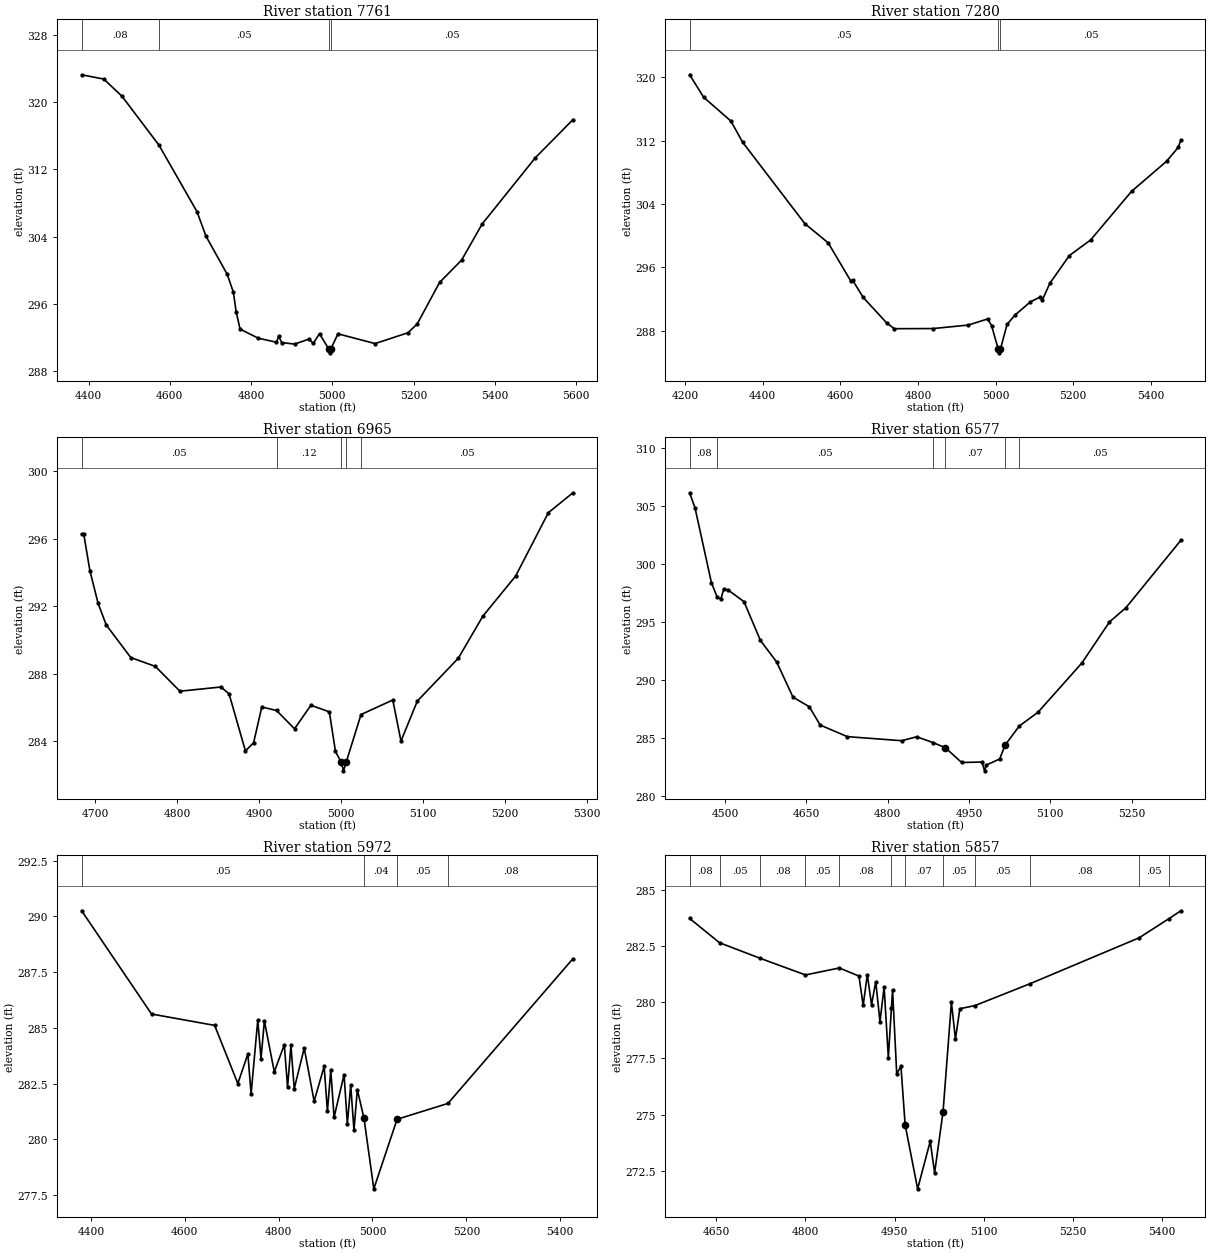
Type RM Length L Ch R = 1 ,7761    ,481,481,481
BEGIN DESCRIPTION:
UNT055 IN ROCK 16.0
END DESCRIPTION:
XS GIS Cut Line= 3
       3662632.4     10167252.76      3662127.15     10167000.14
      3661492.14     10166891.65
#Sta/Elev= 30
    4383  323.23  4437.5  322.72  4482.2  320.68  4573.3  314.86  4666.7  306.97
  4689.1  304.03  4741.1  299.52  4756.2  297.41  4763.5     295  4772.9  292.99
  4817.7  291.91  4862.4  291.43    4868  292.15  4875.3  291.39  4907.1  291.21
  4942.3   291.8    4953  291.29  4968.4  292.45  4990.6  290.67  4993.3  290.17
  4996.6  290.67  5013.9  292.43  5105.2  291.27  5186.3  292.56  5208.9  293.61
    5264  298.54  5318.2   301.2  5368.9   305.5  5499.4  313.35  5592.1  317.89
#Mann= 4 ,-1 , 0
    4383     .08       0  4573.3     .05       0  4990.6     .03       0
  4996.6     .05       0
Bank Sta=4990.6,4996.6
XS Rating Curve= 0 ,0
Exp/Cntr=0.3,0.1

Type RM Length L Ch R = 1 ,7280    ,315,315,315
BEGIN DESCRIPTION:
UNT055 IN ROCK 15.0
END DESCRIPTION:
XS GIS Cut Line= 3
      3662788.19     10166520.81      3661757.33     10166584.57
       3661525.3     10166595.12
#Sta/Elev= 30
  4212.1  320.34  4248.3   317.5  4318.4  314.49  4348.4  311.83  4508.8  301.53
  4568.9   299.1  4627.3  294.27  4632.3  294.35    4659  292.21  4719.2     289
  4739.2  288.25  4839.4  288.27  4929.6  288.71  4979.6  289.48  4989.7  288.65
  5006.7   285.7  5009.5   285.2  5012.7   285.7  5029.7   288.8  5049.8  289.96
  5089.9  291.65  5115.7  292.27  5120.7   291.9    5140     294    5190  297.49
  5244.9  299.47  5350.3  305.61  5440.4  309.41  5470.4  311.16  5477.2  312.07
#Mann= 3 ,-1 , 0
  4212.1     .05       0  5006.7     .03       0  5012.7     .05       0
Bank Sta=5006.7,5012.7
XS Rating Curve= 0 ,0
Exp/Cntr=0.3,0.1

Type RM Length L Ch R = 1 ,6965    ,388,388,388
BEGIN DESCRIPTION:
UNT055 IN ROCK 14.0
END DESCRIPTION:
XS GIS Cut Line= 3
      3662392.14     10166291.64      3662092.11     10166291.64
      3661792.14     10166291.64
#Sta/Elev= 30
  4683.2  296.28  4685.7  296.28  4693.2  294.11  4703.2  292.18  4713.2  290.89
  4743.2  288.96  4773.2  288.44  4803.2  286.97  4853.2  287.22  4863.2  286.82
  4883.2  283.44  4893.2  283.92  4903.2  286.04  4921.2  285.83  4943.2  284.75
  4963.2  286.14  4985.7  285.75  4993.2  283.41  5000.2  282.76    5003  282.26
  5006.2  282.76  5024.4  285.59  5063.2  286.45  5073.2  284.02  5093.2  286.39
  5143.2  288.92  5173.2  291.41  5213.2  293.78  5253.2  297.53  5283.2  298.71
#Mann= 5 ,-1 , 0
  4683.2     .05       0  4921.2     .12       0  5000.2     .07       0
  5006.2     .12       0  5024.4     .05       0
Bank Sta=5000.2,5006.2
XS Rating Curve= 0 ,0
Exp/Cntr=0.3,0.1

Type RM Length L Ch R = 1 ,6577    ,605,605,605
BEGIN DESCRIPTION:
UNT055 IN ROCK 13.0
END DESCRIPTION:
XS GIS Cut Line= 3
      3662592.14     10165891.64      3661992.11     10165941.64
      3661692.06     10165991.65
#Sta/Elev= 30
  4434.7  306.13  4444.8   304.8  4474.9  298.38  4485.7  297.11  4492.4  296.97
  4497.5   297.8    4505  297.77  4535.1  296.73  4565.2   293.4  4595.3  291.53
  4625.4   288.5  4655.5  287.67  4675.6  286.09  4725.7  285.09  4826.1  284.74
  4853.7  285.08  4883.7  284.58  4906.4  284.14  4936.5  282.86  4974.1   282.9
  4978.9  282.14  4982.1  282.64  5006.7  283.16  5016.7  284.36    5043  286.01
  5077.4  287.19  5158.5  291.45  5209.2  294.98  5239.6  296.21    5341  302.03
#Mann= 6 ,-1 , 0
  4434.7     .08       0  4485.7     .05       0  4883.7     .12       0
  4906.4     .07       0  5016.7     .12       0    5043     .05       0
Bank Sta=4906.4,5016.7
XS Rating Curve= 0 ,0
Exp/Cntr=0.3,0.1

Type RM Length L Ch R = 1 ,5972    ,115,115,115
BEGIN DESCRIPTION:
UNT055 IN ROCK 12.0
END DESCRIPTION:
XS GIS Cut Line= 3
      3662397.56     10165826.81       3661967.5     10165380.49
      3661655.83     10165088.47
#Sta/Elev= 30
  4380.2  290.25  4529.1  285.62  4663.6  285.11    4713   282.5  4734.4  283.83
  4741.3  282.04  4755.5  285.35  4762.4  283.62  4769.6  285.31  4790.7  283.03
  4812.1  284.24    4819  282.34  4826.2  284.21  4833.2  282.27  4854.5  284.09
  4875.6  281.71    4897  283.27  4903.9  281.26  4911.1   283.1  4918.1  280.99
  4939.4   282.9  4946.4   280.7  4953.6  282.42  4960.5  280.41  4967.7  282.23
  4981.9  280.94  5002.8  277.78  5052.4   280.9  5160.8  281.61  5427.1   288.1
#Mann= 4 ,-1 , 0
  4380.2     .05       0  4981.9     .04       0  5052.4     .05       0
  5160.8     .08       0
Bank Sta=4981.9,5052.4
XS Rating Curve= 0 ,0
Exp/Cntr=0.3,0.1

Type RM Length L Ch R = 1 ,5857    ,513,513,513
BEGIN DESCRIPTION:
UNT055 IN ROCK 11.0
END DESCRIPTION:
XS GIS Cut Line= 3
      3662319.51     10165577.44      3662039.85     10165297.92
      3661748.26     10164979.58
#Sta/Elev= 30
    4605  283.72  4655.4  282.64  4722.7  281.96  4800.1  281.21  4857.1  281.52
  4890.1  281.16  4897.2  279.86  4904.2  281.22  4911.3  279.89  4918.4  280.91
  4925.5  279.14  4932.5  280.67  4939.6  277.54  4944.8  279.74  4946.7  280.55
  4953.7  276.82  4960.8  277.15  4967.9  274.55  4988.9  271.71  5010.1  273.82
  5017.5  272.42  5031.7  275.13  5045.8  279.99  5052.6  278.36    5060  279.71
  5085.5  279.85  5178.1  280.82  5361.9  282.86  5411.4   283.7  5432.1  284.06
#Mann= 12 ,-1 , 0
    4605     .08       0  4655.4     .05       0  4722.7     .08       0
  4800.1     .05       0  4857.1     .08       0  4944.8     .05       0
  4967.9     .07       0  5031.7     .05       0  5085.5     .05       0
  5178.1     .08       0  5361.9     .05       0  5411.4     .08       0
Bank Sta=4967.9,5031.7
XS Rating Curve= 0 ,0
Exp/Cntr=0.3,0.1

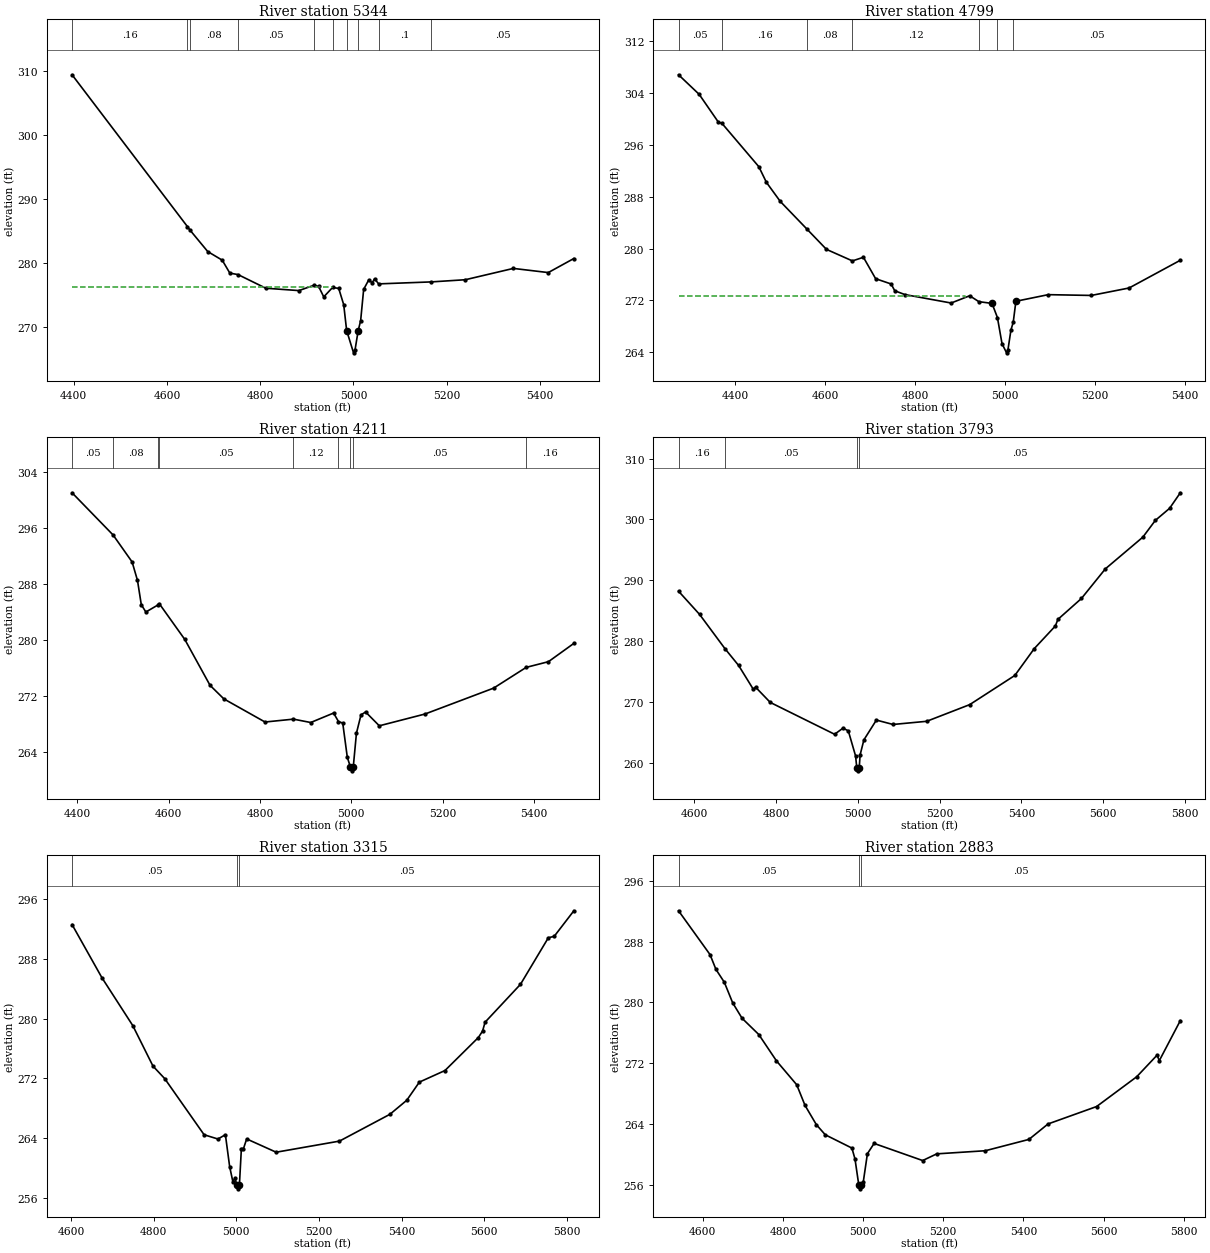
Type RM Length L Ch R = 1 ,5344    ,545,545,545
BEGIN DESCRIPTION:
UNT055 IN ROCK 10.0
END DESCRIPTION:
XS GIS Cut Line= 3
      3662792.06     10165041.63      3662310.78     10164875.44
      3661780.86      10164673.1
#Sta/Elev= 30
  4396.3  309.39  4643.7  285.64    4649  285.11  4687.3  281.73  4718.4  280.38
  4734.8  278.35  4752.1  278.13    4812  275.99  4882.9  275.62  4914.7  276.44
  4925.1  276.28  4936.2  274.64  4955.2  276.11  4968.3  275.96    4979  273.42
  4985.3  269.37  5000.1  265.88  5003.4  266.38    5010  269.34  5015.3   270.9
  5021.8  275.81  5032.5  277.27  5040.1  276.86  5045.4  277.47  5053.9  276.67
  5166.9  276.98  5239.9  277.32  5342.9  279.09  5417.8  278.44  5472.7  280.64
#Mann= 10 ,-1 , 0
  4396.3     .16       0  4643.7     .05       0    4649     .08       0
  4752.1     .05       0  4914.7      .1       0  4955.2     .05       0
  4985.3    .035       0    5010     .05       0  5053.9      .1       0
  5166.9     .05       0
#XS Ineff= 2 , 0
         4954.89  276.15
Permanent Ineff=
       F       F
Bank Sta=4985.3,5010
XS Rating Curve= 0 ,0
Exp/Cntr=0.3,0.1

Type RM Length L Ch R = 1 ,4799    ,588,588,588
BEGIN DESCRIPTION:
UNT055 IN ROCK 9.0
END DESCRIPTION:
XS GIS Cut Line= 3
      3662852.44     10164496.97      3662303.83      10164368.5
      3661766.38      10164240.2
#Sta/Elev= 30
  4274.2  306.83  4320.1  303.81  4362.6  299.54  4370.9  299.32  4452.7  292.65
  4469.7  290.22  4500.5  287.28  4560.5  282.96  4603.2  279.88  4660.9   278.1
  4685.4  278.66  4712.6  275.35    4747  274.54  4755.1  273.49  4777.8   272.9
  4880.5   271.6  4921.7  272.72  4942.2  271.81  4971.4  271.54  4983.4  269.36
  4993.6  265.34  5003.7  263.91  5006.9  264.41  5013.5  267.44  5018.6  268.64
  5024.5  271.87  5096.4  272.89  5192.2  272.77  5276.3  273.92  5390.2   278.2
#Mann= 7 ,-1 , 0
  4274.2     .05       0  4370.9     .16       0  4560.5     .08       0
  4660.9     .12       0  4942.2     .05       0  4983.4    .035       0
  5018.6     .05       0
#XS Ineff= 2 , 0
         4911.19  272.74
Permanent Ineff=
       F       F
Bank Sta=4971.4,5024.5
XS Rating Curve= 0 ,0
Exp/Cntr=0.3,0.1

Type RM Length L Ch R = 1 ,4211    ,418,418,418
BEGIN DESCRIPTION:
UNT055 IN ROCK 8.0
END DESCRIPTION:
XS GIS Cut Line= 3
      3662783.02     10163899.75      3662408.81     10163864.55
      3661686.48     10163830.34
#Sta/Elev= 30
  4388.4     301  4478.3  294.98  4519.9  291.14  4531.7   288.5    4540  285.05
    4550     284  4577.1  285.03  4579.2  285.21  4635.3  280.09  4690.6  273.55
  4720.8  271.62    4811  268.32  4873.3  268.73  4911.1  268.25  4961.2   269.6
  4971.9  268.38  4981.2  268.17  4991.2   263.3  4998.2  261.86    5001  261.36
  5004.2  261.86  5011.2  266.72  5021.2  269.34  5031.3  269.75  5061.3  267.78
  5161.4  269.46  5311.6  273.15    5383  276.11  5431.7  276.92  5487.4  279.53
#Mann= 9 ,-1 , 0
  4388.4     .05       0  4478.3     .08       0  4577.1     .16       0
  4579.2     .05       0  4873.3     .12       0  4971.9     .05       0
  4998.2    .035       0  5004.2     .05       0    5383     .16       0
Bank Sta=4998.2,5004.2
XS Rating Curve= 0 ,0
Exp/Cntr=0.3,0.1

Type RM Length L Ch R = 1 ,3793    ,478,478,478
BEGIN DESCRIPTION:
UNT055 IN ROCK 7.0
END DESCRIPTION:
XS GIS Cut Line= 3
      3662642.12     10163591.64      3662242.11     10163491.64
      3661442.07     10163341.64
#Sta/Elev= 30
  4561.9   288.2  4613.5  284.37  4675.3  278.76  4708.8  275.99  4744.9  272.05
    4750  272.44  4786.1  269.92  4943.3  264.69  4963.9   265.7  4976.8  265.25
  4994.6  261.12  4997.5  259.18  5000.3  258.68  5003.5  259.18  5005.6  261.28
  5014.9  263.77  5045.4  267.02  5086.1   266.3  5168.4  266.82  5273.5  269.56
  5383.7  274.35  5431.2  278.76  5482.9  282.49  5488.9  283.56  5546.5     287
    5605  291.87  5696.6  297.08  5727.1  299.83  5761.9  301.81  5788.2  304.37
#Mann= 4 ,-1 , 0
  4561.9     .16       0  4675.3     .05       0  4997.5     .03       0
  5003.5     .05       0
Bank Sta=4997.5,5003.5
XS Rating Curve= 0 ,0
Exp/Cntr=0.3,0.1

Type RM Length L Ch R = 1 ,3315    ,432,432,432
BEGIN DESCRIPTION:
UNT055 IN ROCK 6.0
END DESCRIPTION:
XS GIS Cut Line= 3
      3662742.15     10163191.65      3662342.11     10163091.64
      3661555.44     10162934.79
#Sta/Elev= 30
  4602.6  292.61  4674.8  285.49  4749.5  279.07  4798.5  273.63  4826.8  271.96
  4922.2  264.43  4955.7  263.86  4973.7  264.44    4984  260.16  4991.8  258.13
  4996.9  258.62  5001.6  257.68  5004.4  257.18  5007.6  257.68  5012.4  262.58
  5017.5  262.58  5025.2  263.87  5096.6  262.09  5249.8  263.58  5371.8  267.17
  5412.6  269.05  5443.2  271.49  5505.1  273.04    5586  277.47  5596.2  278.34
  5602.2  279.52  5687.9   284.6  5755.4  290.85  5769.5  291.03  5817.1  294.46
#Mann= 3 ,-1 , 0
  4602.6     .05       0  5001.6     .03       0  5007.6     .05       0
Bank Sta=5001.6,5007.6
XS Rating Curve= 0 ,0
Exp/Cntr=0.3,0.1

Type RM Length L Ch R = 1 ,2883    ,475,475,475
BEGIN DESCRIPTION:
UNT055 IN ROCK 5.0
END DESCRIPTION:
XS GIS Cut Line= 3
      3662842.09     10162941.63      3662492.11     10162691.64
      3661696.66      10162483.2
#Sta/Elev= 30
  4539.3  292.05  4617.9  286.29  4632.7  284.34  4653.6  282.65  4674.5  279.94
  4697.8  277.92  4739.6  275.78  4783.8  272.31  4834.2  269.18  4855.1  266.45
  4883.4  263.92  4905.5   262.6    4972  260.85  4979.7  259.42  4989.2  255.99
  4991.9  255.49  4995.2  255.99  5000.4   256.4  5010.7  260.11  5027.4  261.46
  5148.6  259.21  5183.8  260.09    5305   260.5  5413.9  261.99  5461.5  264.02
  5582.7  266.31  5682.7  270.22  5733.9  273.08  5739.1  272.33  5791.7  277.61
#Mann= 3 ,-1 , 0
  4539.3     .05       0  4989.2     .03       0  4995.2     .05       0
Bank Sta=4989.2,4995.2
XS Rating Curve= 0 ,0
Exp/Cntr=0.3,0.1

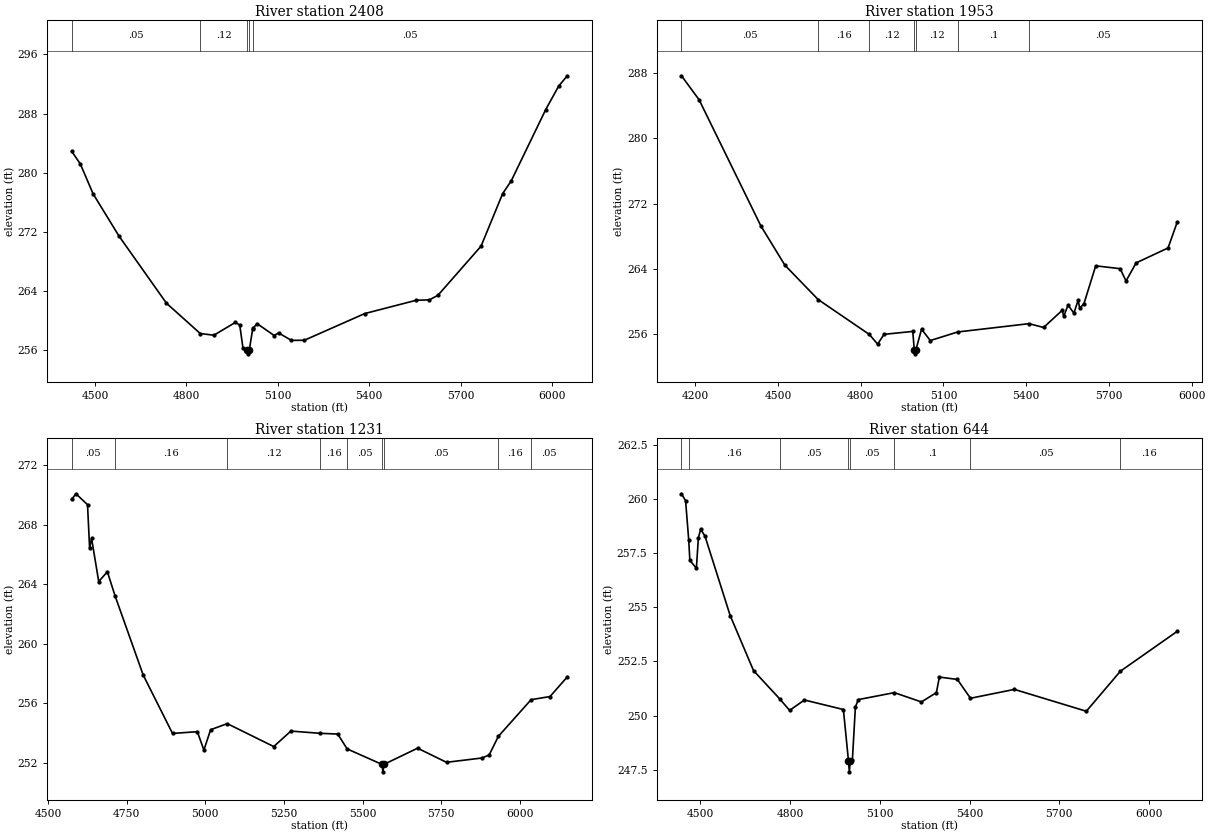
Type RM Length L Ch R = 1 ,2408    ,455,455,455
BEGIN DESCRIPTION:
UNT055 IN ROCK 4.0
END DESCRIPTION:
XS GIS Cut Line= 3
      3662992.13     10162641.67      3662592.11     10162241.64
      3661842.09     10161491.63
#Sta/Elev= 30
  4423.5   282.9  4451.8  281.19  4494.2  277.11  4579.1   271.4  4734.7  262.32
  4845.5  258.22  4890.2  257.99  4960.9  259.73  4975.1  259.36  4985.7  256.25
  5000.4  255.97  5003.1  255.47  5006.4  255.97  5017.5  258.83  5019.4  258.93
  5031.6  259.57  5088.2  257.95  5102.4   258.3  5144.8  257.29  5187.2  257.31
  5385.2  260.92  5554.9  262.73  5597.3  262.77  5625.6   263.4    5767  270.05
  5837.7  277.15    5866  278.89  5979.2  288.54  6021.6  291.71  6049.9  293.11
#Mann= 5 ,-1 , 0
  4423.5     .05       0  4845.5     .12       0  5000.4     .07       0
  5006.4     .12       0  5019.4     .05       0
Bank Sta=5000.4,5006.4
XS Rating Curve= 0 ,0
Exp/Cntr=0.3,0.1

Type RM Length L Ch R = 1 ,1953    ,722,722,722
BEGIN DESCRIPTION:
UNT055 IN ROCK 3.0
END DESCRIPTION:
XS GIS Cut Line= 3
      3663092.12     10162691.67      3662723.97     10161656.69
       3662130.2     10161288.63
#Sta/Elev= 30
  4150.3  287.67    4214  284.74    4438  269.27  4525.2  264.45  4645.7  260.24
  4831.3  255.96  4861.5  254.77  4884.7  255.97  4988.8  256.33  4994.4  254.08
  4997.2  253.58  5000.4  254.08  5020.7   256.6  5052.5  255.21  5151.6  256.26
  5410.6  257.28  5463.2  256.81  5530.5  258.91  5536.4  258.19  5551.8  259.55
  5573.1  258.57  5588.4  260.15  5594.3  259.15  5609.7  259.75  5652.2  264.37
  5740.8  264.02  5762.1  262.51  5798.7  264.73  5914.5  266.56  5947.4   269.7
#Mann= 7 ,-1 , 0
  4150.3     .05       0  4645.7     .16       0  4831.3     .12       0
  4994.4     .07       0  5000.4     .12       0  5151.6      .1       0
  5410.6     .05       0
Bank Sta=4994.4,5000.4
XS Rating Curve= 0 ,0
Exp/Cntr=0.3,0.1

Type RM Length L Ch R = 1 ,1231    ,587,587,587
BEGIN DESCRIPTION:
UNT055 IN ROCK 2.0
END DESCRIPTION:
XS GIS Cut Line= 3
      3663592.11     10161941.65      3663185.22     10161413.05
      3662296.56     10161224.52
#Sta/Elev= 30
  4575.1   269.7  4588.7  270.08  4625.6  269.35  4632.2  266.44  4638.5  267.08
  4661.2  264.18  4688.7  264.84  4712.8  263.24  4802.5   257.9  4895.8  253.97
  4974.7  254.09  4995.5  252.85  5016.8  254.22  5069.7  254.63  5217.5  253.09
    5272  254.13  5364.1  253.98  5420.9  253.93  5450.9  252.93  5561.7  251.89
  5564.5  251.39  5567.7  251.89  5674.7  252.98  5766.7  252.03  5879.1  252.32
  5902.1  252.52  5931.7  253.78  6035.5  256.24  6095.6  256.45  6150.6  257.77
#Mann= 9 ,-1 , 0
  4575.1     .05       0  4712.8     .16       0  5069.7     .12       0
  5364.1     .16       0  5450.9     .05       0  5561.7     .07       0
  5567.7     .05       0  5931.7     .16       0  6035.5     .05       0
Bank Sta=5561.7,5567.7
XS Rating Curve= 0 ,0
Exp/Cntr=0.3,0.1

Type RM Length L Ch R = 1 ,644     ,0,0,0
BEGIN DESCRIPTION:
UNT055 IN ROCK 1.0
END DESCRIPTION:
XS GIS Cut Line= 3
      3663792.08     10161441.62      3663540.37     10161153.94
      3662269.39     10161077.98
#Sta/Elev= 30
  4437.9  260.25  4451.6  259.93  4462.1  258.11  4465.9  257.17  4487.7  256.81
  4494.3  258.21  4501.9  258.61  4516.2   258.3  4600.6  254.62  4678.5  252.08
  4766.7  250.76    4799  250.24  4848.5  250.72  4978.7  250.28  4995.7   247.9
  4998.5   247.4  5001.7   247.9  5008.8  247.97  5018.8   250.4  5028.8  250.74
  5148.9  251.06  5239.2  250.63  5289.3  251.06  5299.3  251.78  5359.4  251.67
  5403.1   250.8  5549.7  251.21  5790.1   250.2  5903.8  252.05  6093.4  253.89
#Mann= 8 ,-1 , 0
  4437.9     .05       0  4462.1     .16       0  4766.7     .05       0
  4995.7     .03       0  5001.7     .05       0  5148.9      .1       0
  5403.1     .05       0  5903.8     .16       0
Bank Sta=4995.7,5001.7
XS Rating Curve= 0 ,0
Exp/Cntr=0.3,0.1

Chan Stop Cuts=-1
Use User Specified Reach Order=0
Composite Channel Slope=5