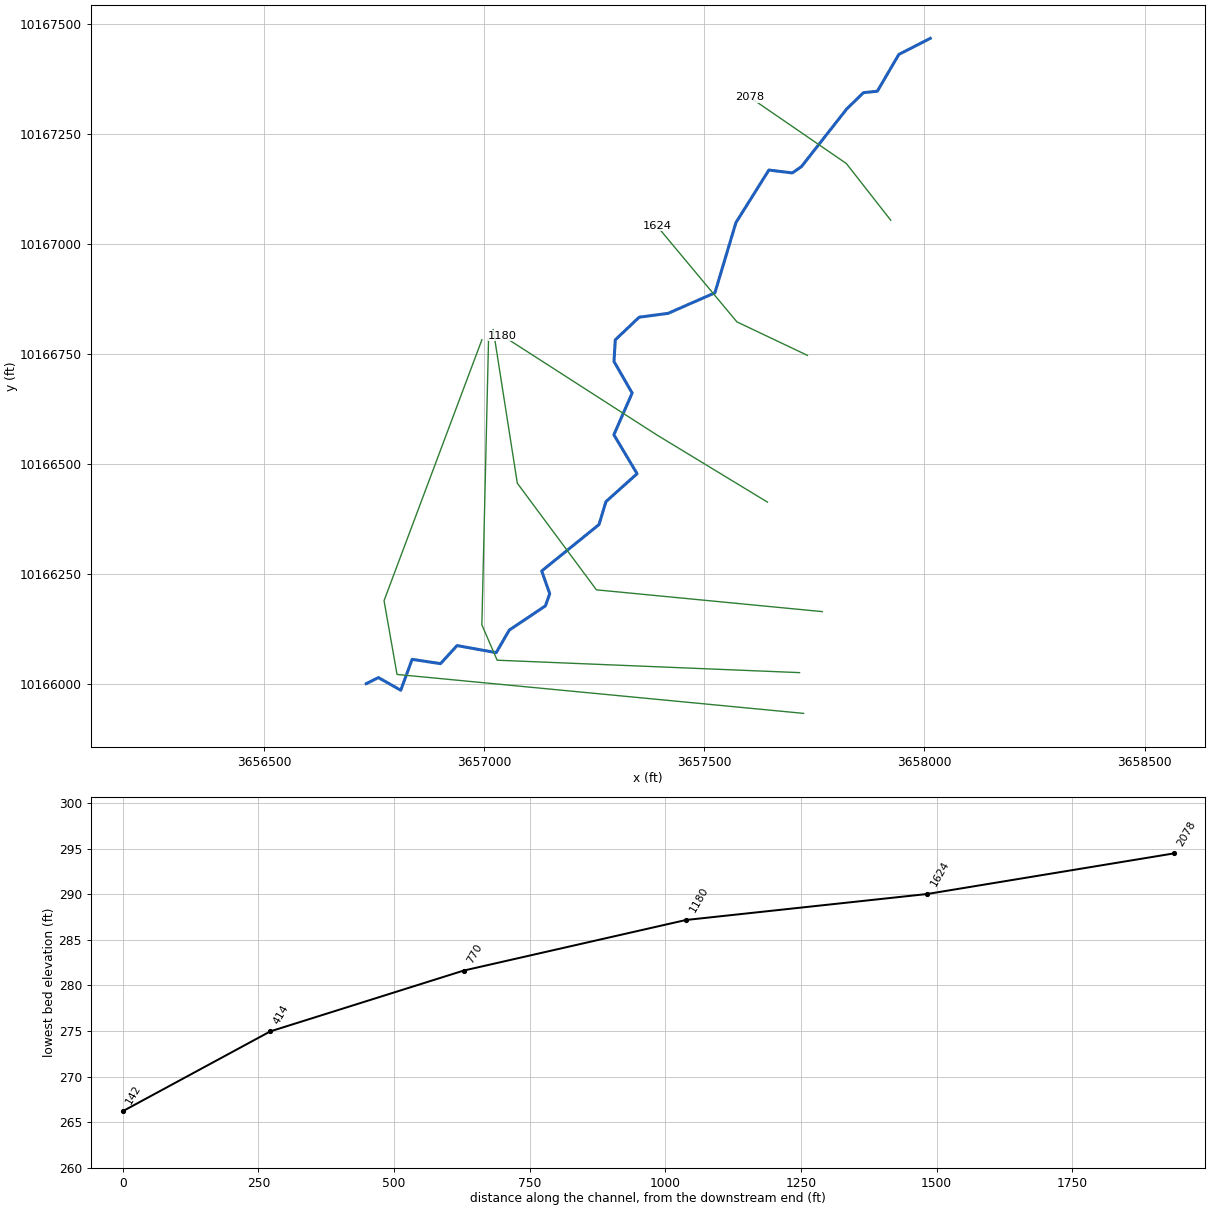
--- UNT057 IN ROCK.prj (project) ---

Proj Title=UNT057 IN ROCK Base Level Engineering
Current Plan=p01
Default Exp/Contr=0.3,0.1
English Units
Geom File=g01
Flow File=f01
Plan File=p01
Y Axis Title=Elevation
X Axis Title(PF)=Main Channel Distance
X Axis Title(XS)=Station
BEGIN DESCRIPTION:
UNT057 IN ROCK
END DESCRIPTION:
DSS Export Rating Curves= 0
DSS Export Rating Curve Sorted= 0
DSS Export Volume Flow Curves= 0
DXF OffsetX= 0
DXF OffsetY= 0
DXF ScaleX= 1
DXF ScaleY= 10

--- UNT057 IN ROCK.p01 (plan) ---

Plan Title=Multiple Run
Short Identifier=Multiple
Geom File=g01
Flow File=f01
Subcritical Flow
K Sum by GR= 0
Std Step Tol= 0.01
Critical Tol= 0.01
Num of Std Step Trials= 20
Max Error Tol= 0.3
Flow Tol Ratio= 0.001
Split Flow NTrial= 30
Split Flow Tol= 0.02
Split Flow Ratio= 0.02
Log Output Level= 0
Friction Slope Method= 1
Unsteady Friction Slope Method= 2
Unsteady Bridges Friction Slope Method= 1
Parabolic Critical Depth
Global Vel Dist=  1 , 1 , 1
Global Log Level= 0
CheckData=True
Encroach Param= -1, 0, 0, 0
BEGIN DESCRIPTION:
Multiple Run
END DESCRIPTION:

--- UNT057 IN ROCK.f01 (steady flow) ---

Flow Title=Multiple
Program Version=4.10
Number of Profiles= 7
Profile Names=10-year,25-year,50-year,1pct_min,100-year,1pct_plu,500-year
River Rch & RM=UNT057 IN ROCK,Reach-1         ,2078
     195     245     283     242     328     443     436
Boundary for River Rch & Prof#=UNT057 IN ROCK,Reach-1         , 1
Up Type= 0
Dn Type= 3
Dn Slope=0.005
Boundary for River Rch & Prof#=UNT057 IN ROCK,Reach-1         , 2
Up Type= 0
Dn Type= 3
Dn Slope=0.005
Boundary for River Rch & Prof#=UNT057 IN ROCK,Reach-1         , 3
Up Type= 0
Dn Type= 3
Dn Slope=0.005
Boundary for River Rch & Prof#=UNT057 IN ROCK,Reach-1         , 4
Up Type= 0
Dn Type= 3
Dn Slope=0.005
Boundary for River Rch & Prof#=UNT057 IN ROCK,Reach-1         , 5
Up Type= 0
Dn Type= 3
Dn Slope=0.005
Boundary for River Rch & Prof#=UNT057 IN ROCK,Reach-1         , 6
Up Type= 0
Dn Type= 3
Dn Slope=0.005
Boundary for River Rch & Prof#=UNT057 IN ROCK,Reach-1         , 7
Up Type= 0
Dn Type= 3
Dn Slope=0.005
DSS Import GetInterval= 0
DSS Import GetPeak= 0
DSS Import FillOption= 0

--- UNT057 IN ROCK.g01 (geometry) ---

Geom Title=Existing Conditions
Program Version=4.10

River Reach=UNT057 IN ROCK  ,Reach-1
Reach XY= 30
      3658013.32      10167467.5       3657941.8     10167430.89
      3657892.97     10167347.33       3657861.5     10167344.08
      3657823.52     10167307.19      3657720.44     10167175.89
      3657699.82     10167161.79      3657646.66      10167168.3
      3657571.79     10167048.94      3657524.04     10166889.44
      3657417.71     10166842.78      3657351.99     10166834.04
      3657297.73     10166782.58      3657294.82     10166733.43
      3657336.04     10166661.75      3657294.53     10166567.01
      3657347.25     10166478.51      3657276.49     10166415.07
      3657260.77     10166363.02       3657130.6     10166257.53
      3657148.84     10166205.89      3657139.01     10166178.32
      3657056.74     10166123.08      3657027.27     10166072.06
      3656938.27     10166088.11      3656900.83     10166047.15
      3656836.17     10166056.81      3656810.49     10165986.64
      3656759.76     10166015.36      3656732.11     10166001.64

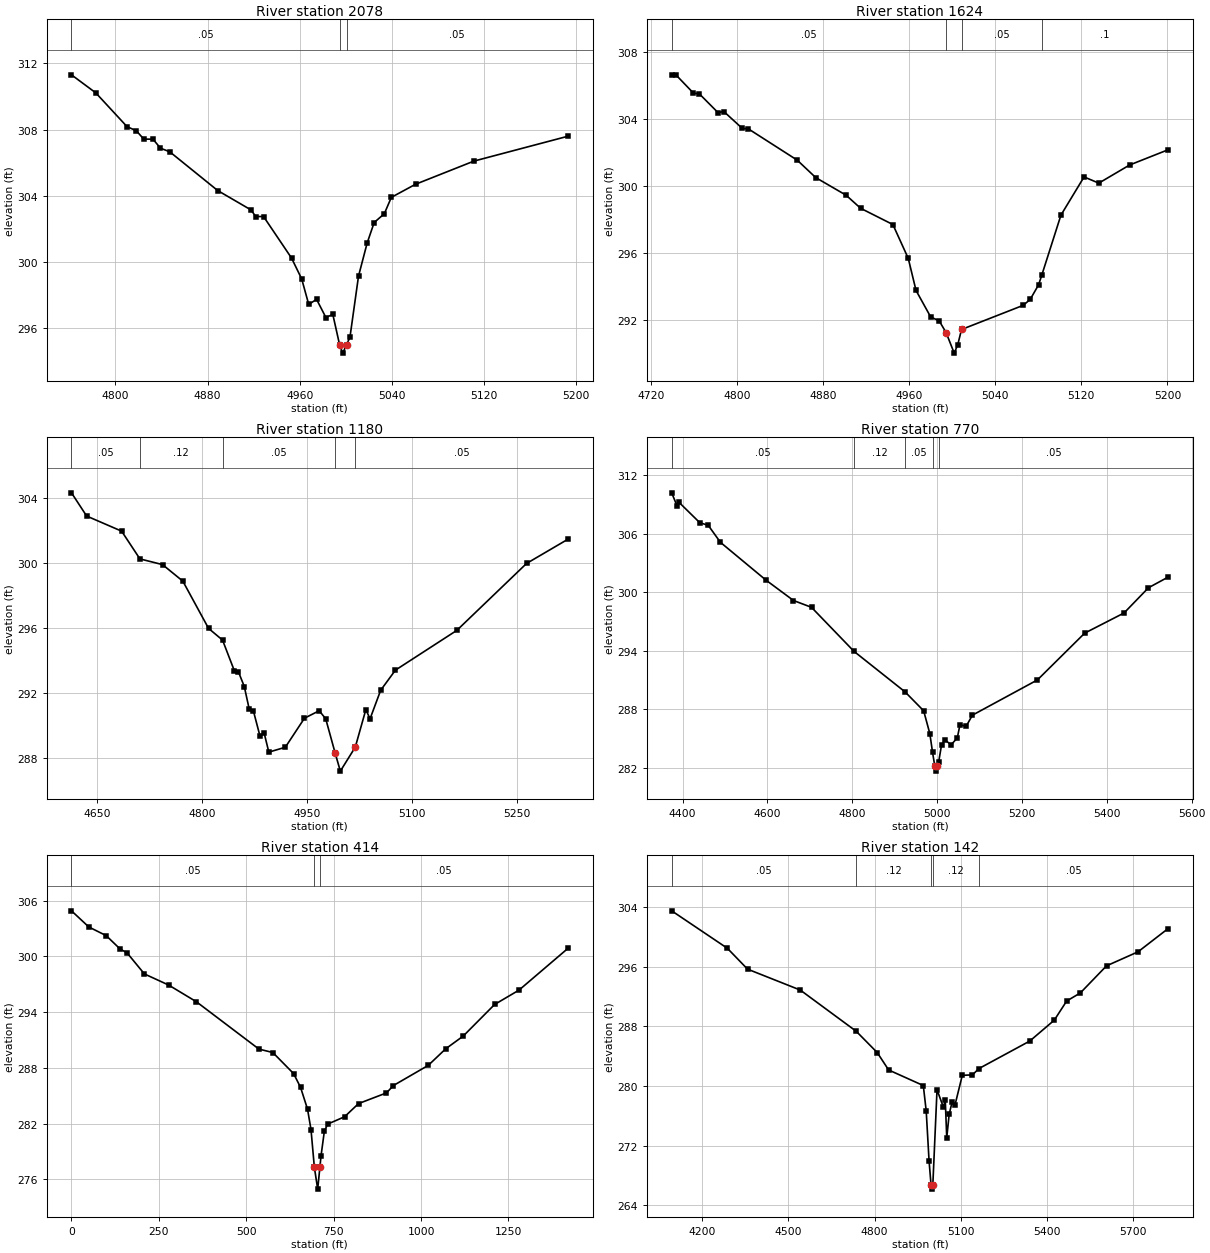
Type RM Length L Ch R = 1 ,2078    ,455,455,455
BEGIN DESCRIPTION:
UNT057 IN ROCK 4.0
END DESCRIPTION:
XS GIS Cut Line= 3
      3657923.44     10167054.33      3657822.63     10167183.14
      3657602.31     10167334.38
#Sta/Elev= 30
  4761.9  311.31    4783  310.22  4810.1  308.18  4818.2  307.93  4824.6  307.43
  4832.7  307.42  4839.1  306.88  4847.2  306.66  4888.8  304.32  4917.7  303.15
  4921.8  302.75  4928.6  302.75  4952.9  300.24  4961.7  298.98  4967.8  297.44
  4974.6  297.75  4982.7  296.65  4988.7  296.84  4994.6     295  4997.3   294.5
  5000.6     295  5003.6  295.47    5011  299.15  5018.5  301.15  5024.6  302.39
  5033.4  302.92  5039.5  303.91  5060.5   304.7  5111.2   306.1  5192.7   307.6
#Mann= 3 ,-1 , 0
  4761.9     .05       0  4994.6    .035       0  5000.6     .05       0
Bank Sta=4994.6,5000.6
XS Rating Curve= 0 ,0
Exp/Cntr=0.3,0.1

Type RM Length L Ch R = 1 ,1624    ,444,444,444
BEGIN DESCRIPTION:
UNT057 IN ROCK 3.0
END DESCRIPTION:
XS GIS Cut Line= 3
      3657734.16     10166747.37      3657574.01     10166823.41
       3657392.1     10167041.65
#Sta/Elev= 30
  4739.2  306.64  4743.1  306.64  4759.4  305.55    4765   305.5  4782.2  304.39
  4787.7  304.45  4804.9  303.44  4810.4  303.42  4855.9  301.55  4873.1  300.51
  4901.3  299.46  4914.8  298.68  4944.8  297.71  4959.1  295.69  4966.3  293.78
    4980  292.19  4987.8  291.97  4994.3  291.26  5001.8  290.04  5005.1  290.54
  5008.6  291.45  5065.9  292.89  5072.4  293.24  5080.2  294.11  5083.3  294.71
    5101  298.27  5122.5  300.55  5136.2  300.18  5164.8  301.26  5200.6  302.17
#Mann= 4 ,-1 , 0
  4739.2     .05       0  4994.3    .035       0  5008.6     .05       0
  5083.3      .1       0
Bank Sta=4994.3,5008.6
XS Rating Curve= 0 ,0
Exp/Cntr=0.3,0.1

Type RM Length L Ch R = 1 ,1180    ,410,410,410
BEGIN DESCRIPTION:
UNT057 IN ROCK 2.0
END DESCRIPTION:
XS GIS Cut Line= 3
      3657643.38     10166414.01      3657391.38     10166567.07
      3657042.09     10166791.65
#Sta/Elev= 30
  4613.2  304.33  4634.9   302.9  4684.9  301.97  4711.1  300.26  4743.4  299.91
  4772.5  298.89  4809.3  295.98  4829.3  295.26  4846.1  293.38    4852  293.31
  4860.4   292.4  4867.5     291  4873.3  290.92  4882.9  289.34  4888.8  289.54
  4895.5  288.36  4919.1  288.66  4946.5  290.45  4967.6  290.91  4976.9  290.41
  4990.4   288.3  4997.8  287.19  5019.2  288.67  5034.3  290.98  5040.3  290.41
  5055.5  292.17  5076.6  293.41  5164.5  295.86  5264.2  299.98  5323.3  301.47
#Mann= 5 ,-1 , 0
  4613.2     .05       0  4711.1     .12       0  4829.3     .05       0
  4990.4    .035       0  5019.2     .05       0
Bank Sta=4990.4,5019.2
XS Rating Curve= 0 ,0
Exp/Cntr=0.3,0.1

Type RM Length L Ch R = 1 ,770     ,356,356,356
BEGIN DESCRIPTION:
Mapping XS d0f270b0
END DESCRIPTION:
XS GIS Cut Line= 4
       3657767.9     10166165.26      3657254.89     10166214.74
       3657075.2     10166456.93      3657020.51      10166805.9
#Sta/Elev= 30
  4374.2  310.19  4386.8  308.85  4391.8   309.2  4440.3  307.13  4460.4  306.85
  4489.1  305.11  4596.5  301.23  4661.3  299.14  4703.8  298.44    4804  293.92
  4924.4  289.76  4968.2  287.82  4982.8  285.47  4989.1  283.57  4994.5  282.13
  4997.2  281.63  5000.5  282.13  5003.7   282.6  5010.3  284.31  5018.3  284.84
  5032.9  284.33  5047.5  285.04  5053.8  286.39  5068.4  286.23    5083  287.37
  5236.4  290.99  5347.8  295.79  5440.6  297.86  5498.2  300.45  5544.4  301.54
#Mann= 5 ,-1 , 0
  4374.2     .05       0    4804     .12       0  4924.4     .05       0
  4989.1    .035       0  5003.7     .05       0
Bank Sta=4994.5,5000.5
XS Rating Curve= 0 ,0
Exp/Cntr=0.3,0.1

Type RM Length L Ch R = 1 ,414     ,272,272,272
XS GIS Cut Line= 4
     3657716.249    10166026.667       3657029.4    10166054.879
     3656994.678    10166135.174     3657009.869    10166784.046
#Sta/Elev= 30
       0304.897549.65333303.158499.30666302.2304139.0293300.7925158.8907300.3788
 208.544 298.109278.0587296.9118 357.504295.1108 536.256290.0223575.9786289.6538
635.5626287.3815 655.424285.8982675.2853 283.558 685.216281.3683694.7778277.3266
704.3396274.9581  710.78  277.35713.9014278.5383723.4633281.2011733.0251281.9552
 781.254282.7428 821.181284.1595901.0349285.3088920.9983286.10181020.816288.2762
1070.724290.05811120.633291.42161210.469294.82181280.341296.36881420.085 300.853
#Mann= 3 , 0 , 0
       0     .05       0694.7778    .035       0  710.78     .05       0
Bank Sta=694.7778,710.78
XS Rating Curve= 0 ,0
Exp/Cntr=0.3,0.1

Type RM Length L Ch R = 1 ,142     ,0,0,0
BEGIN DESCRIPTION:
UNT057 IN ROCK 1.0
END DESCRIPTION:
XS GIS Cut Line= 4
      3657725.42     10165934.11      3656801.98     10166022.54
      3656772.46     10166190.07       3656994.7      10166782.7
#Sta/Elev= 30
  4092.8  303.46    4287  298.44  4357.3  295.65  4541.1  292.85  4736.2  287.33
  4809.4  284.48  4849.1  282.15  4970.1  280.06  4980.2  276.65  4990.2  269.94
  4997.2  266.69    5000  266.19  5003.2  266.69  5017.9   279.5  5039.9  277.18
  5046.7  278.07  5051.8  273.06  5060.2   276.2  5070.3  277.84  5080.5  277.45
    5106  281.43  5141.4  281.49  5163.8  282.33  5341.3  286.02  5426.8  288.82
  5469.9  291.38  5517.5  292.46  5608.8  296.09  5718.7  297.97  5823.5  301.08
#Mann= 5 ,-1 , 0
  4092.8     .05       0  4736.2     .12       0  4997.2     .07       0
  5003.2     .12       0  5163.8     .05       0
Bank Sta=4997.2,5003.2
XS Rating Curve= 0 ,0
Exp/Cntr=0.3,0.1
Stream Node=UNT057 IN ROCK  ,Reach-1         , 0 , 0 ,Upstream end
Stream Node=UNT057 IN ROCK  ,Reach-1         , 0 , 1 ,Downstream end

Chan Stop Cuts=-1
Use User Specified Reach Order=0
Composite Channel Slope=5