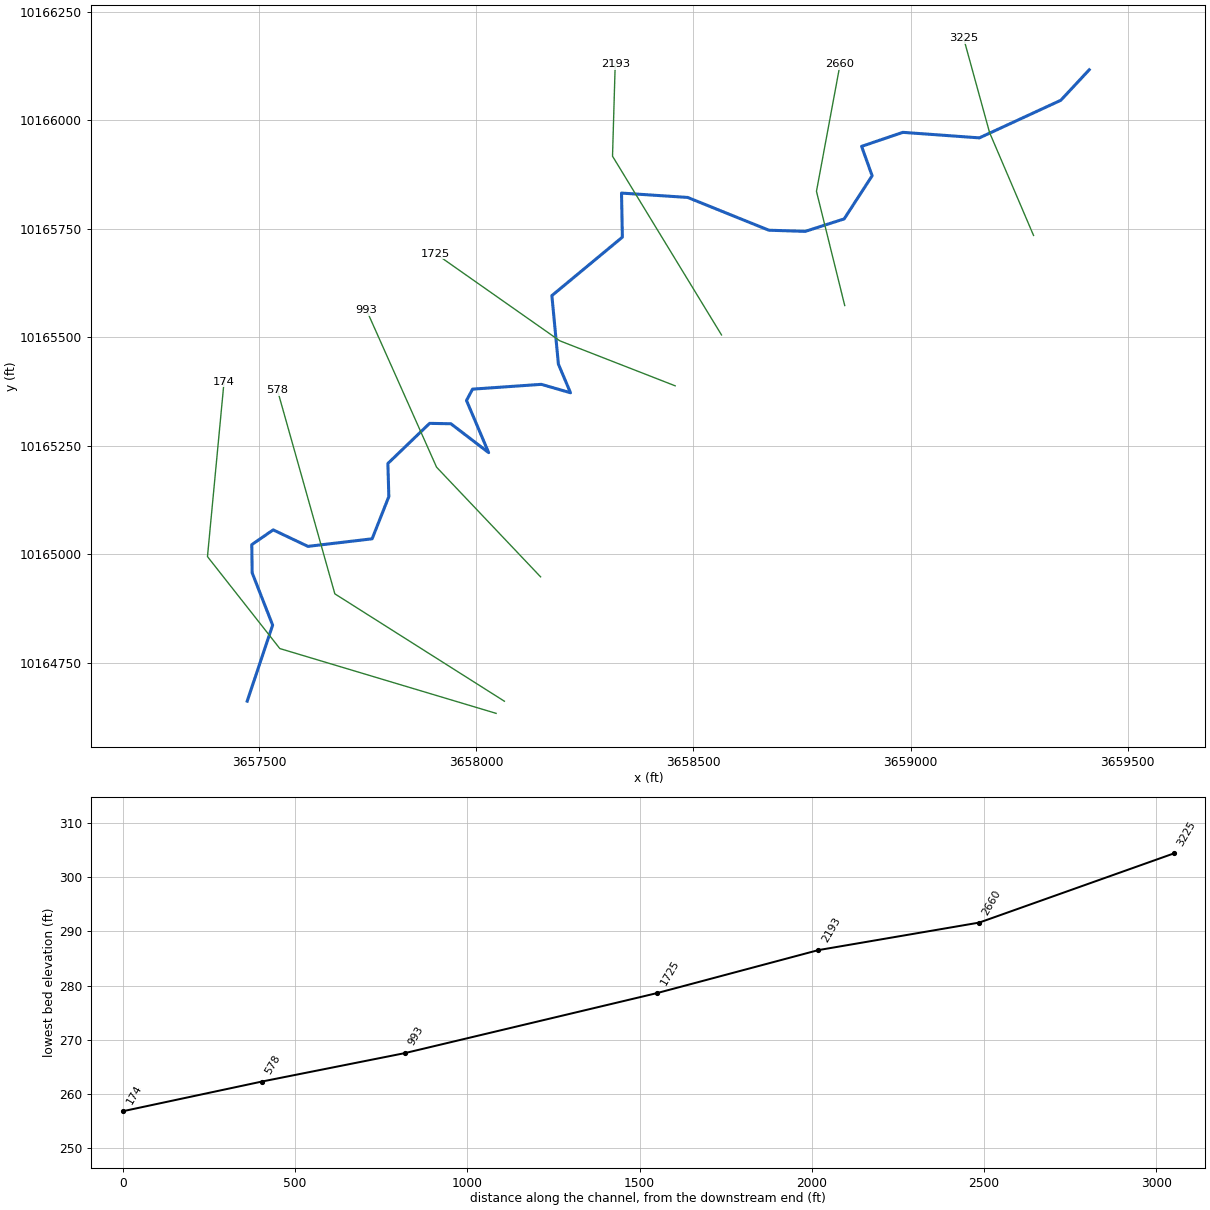
--- UNT058 IN ROCK.prj (project) ---

Proj Title=UNT058 IN ROCK Base Level Engineering
Current Plan=p01
Default Exp/Contr=0.3,0.1
English Units
Geom File=g01
Flow File=f01
Plan File=p01
Y Axis Title=Elevation
X Axis Title(PF)=Main Channel Distance
X Axis Title(XS)=Station
BEGIN DESCRIPTION:
UNT058 IN ROCK
END DESCRIPTION:
DSS Export Rating Curves= 0
DSS Export Rating Curve Sorted= 0
DSS Export Volume Flow Curves= 0
DXF OffsetX= 0
DXF OffsetY= 0
DXF ScaleX= 1
DXF ScaleY= 10

--- UNT058 IN ROCK.p01 (plan) ---

Plan Title=Multiple Run
Short Identifier=Multiple
Geom File=g01
Flow File=f01
Subcritical Flow
K Sum by GR= 0
Std Step Tol= 0.01
Critical Tol= 0.01
Num of Std Step Trials= 20
Max Error Tol= 0.3
Flow Tol Ratio= 0.001
Split Flow NTrial= 30
Split Flow Tol= 0.02
Split Flow Ratio= 0.02
Log Output Level= 0
Friction Slope Method= 1
Unsteady Friction Slope Method= 2
Unsteady Bridges Friction Slope Method= 1
Parabolic Critical Depth
Global Vel Dist=  1 , 1 , 1
Global Log Level= 0
CheckData=True
Encroach Param= -1, 0, 0, 0
BEGIN DESCRIPTION:
Multiple Run
END DESCRIPTION:

--- UNT058 IN ROCK.f01 (steady flow) ---

Flow Title=Multiple
Program Version=4.10
Number of Profiles= 7
Profile Names=10-year,25-year,50-year,1pct_min,100-year,1pct_plu,500-year
River Rch & RM=UNT058 IN ROCK,Reach-1         ,3225
     229     291     340     293     396     535     535
Boundary for River Rch & Prof#=UNT058 IN ROCK,Reach-1         , 1
Up Type= 0
Dn Type= 3
Dn Slope=0.005
Boundary for River Rch & Prof#=UNT058 IN ROCK,Reach-1         , 2
Up Type= 0
Dn Type= 3
Dn Slope=0.005
Boundary for River Rch & Prof#=UNT058 IN ROCK,Reach-1         , 3
Up Type= 0
Dn Type= 3
Dn Slope=0.005
Boundary for River Rch & Prof#=UNT058 IN ROCK,Reach-1         , 4
Up Type= 0
Dn Type= 3
Dn Slope=0.005
Boundary for River Rch & Prof#=UNT058 IN ROCK,Reach-1         , 5
Up Type= 0
Dn Type= 3
Dn Slope=0.005
Boundary for River Rch & Prof#=UNT058 IN ROCK,Reach-1         , 6
Up Type= 0
Dn Type= 3
Dn Slope=0.005
Boundary for River Rch & Prof#=UNT058 IN ROCK,Reach-1         , 7
Up Type= 0
Dn Type= 3
Dn Slope=0.005
DSS Import GetInterval= 0
DSS Import GetPeak= 0
DSS Import FillOption= 0

--- UNT058 IN ROCK.g01 (geometry) ---

Geom Title=Existing Conditions
Program Version=4.10

River Reach=UNT058 IN ROCK  ,Reach-1
Reach XY= 30
      3659411.65     10166115.94      3659346.12     10166045.62
      3659158.58     10165959.06      3658982.42     10165971.79
      3658887.32     10165939.53      3658911.58     10165871.79
      3658847.17     10165772.43      3658757.42     10165743.66
      3658673.56     10165746.39      3658486.63     10165821.86
       3658334.3     10165831.91      3658336.29     10165730.38
       3658173.9     10165595.71      3658188.95     10165437.83
      3658216.82     10165371.94       3658149.6     10165391.35
      3657991.18      10165380.3      3657977.26     10165354.15
      3658028.26     10165234.03      3657941.34     10165300.54
      3657892.33     10165301.51      3657796.15     10165209.06
      3657798.36     10165132.85      3657759.88     10165035.54
      3657612.03     10165018.13      3657531.93     10165056.13
      3657482.63     10165022.03      3657483.59     10164957.02
      3657530.73     10164836.77      3657472.11     10164661.64

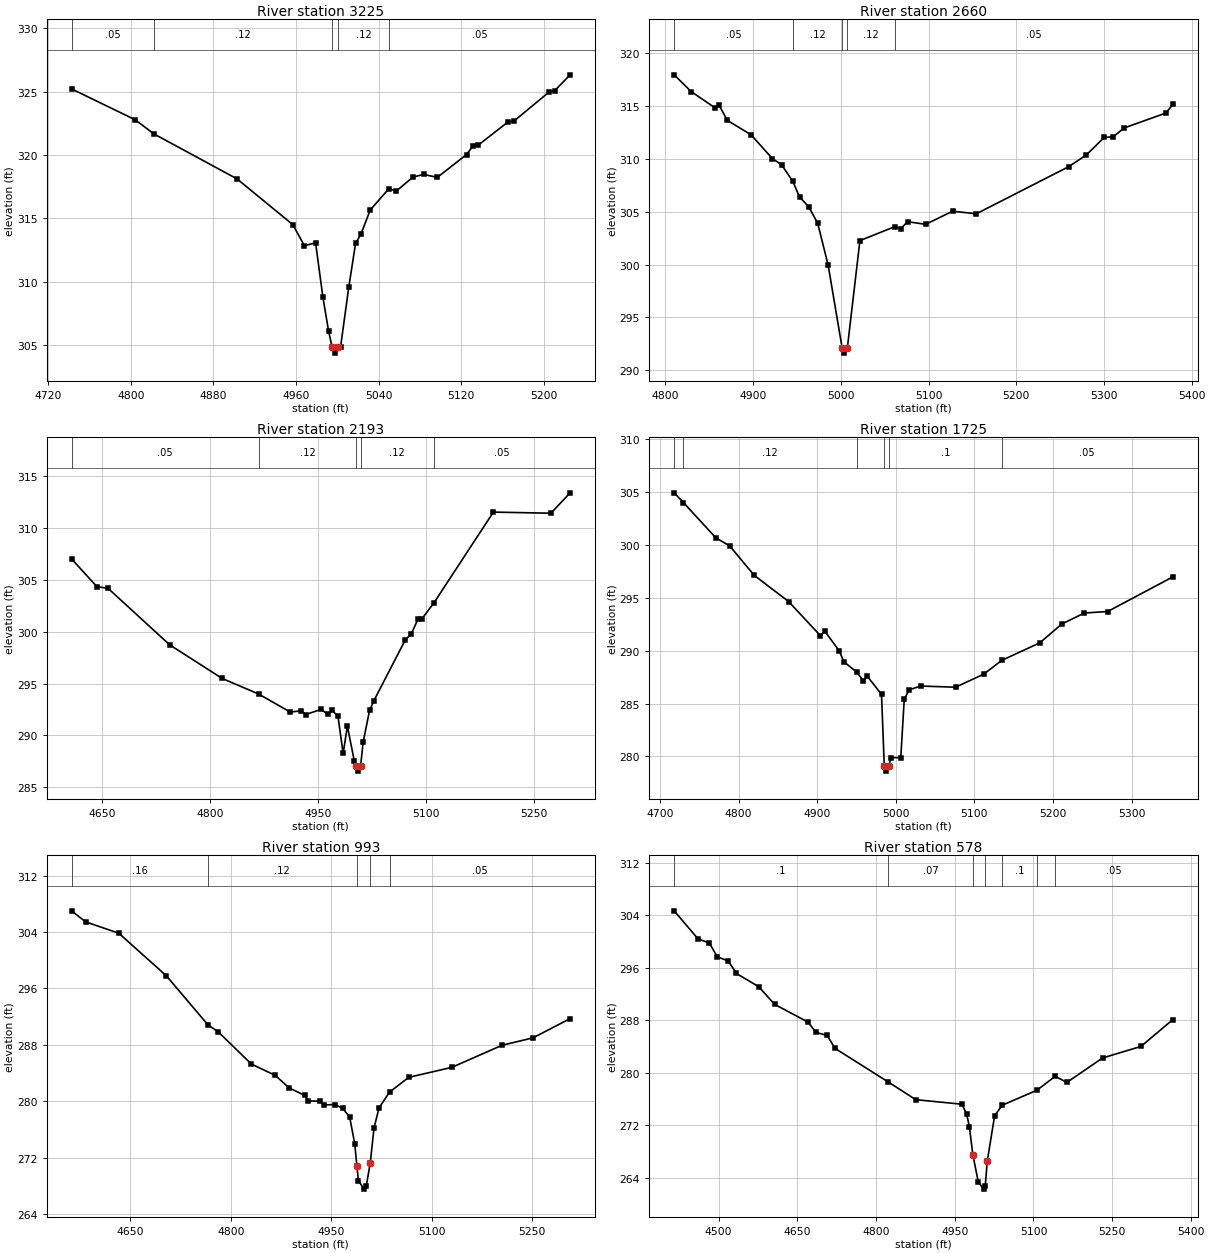
Type RM Length L Ch R = 1 ,3225    ,565,565,565
BEGIN DESCRIPTION:
UNT058 IN ROCK 6.0
END DESCRIPTION:
XS GIS Cut Line= 3
      3659283.36     10165734.34      3659182.05     10165971.41
      3659122.37     10166188.34
#Sta/Elev= 30
  4742.6  325.21  4804.4  322.77    4822  321.68  4902.8  318.12  4956.9  314.51
    4968  312.86  4978.9  313.08  4985.9  308.84  4991.4  306.16  4994.8  304.89
  4997.6  304.39  5000.8  304.89  5003.1  304.89    5011  309.57  5017.6  313.04
  5022.8  313.76  5031.8  315.67  5049.7  317.33  5057.2  317.17  5073.3  318.27
  5083.6  318.47  5096.8  318.24  5125.1  320.04  5131.2   320.7  5136.4  320.78
  5165.6  322.63  5170.8  322.66  5205.2  324.98  5210.4  325.07  5225.4  326.32
#Mann= 5 ,-1 , 0
  4742.6     .05       0    4822     .12       0  4994.8     .07       0
  5000.8     .12       0  5049.7     .05       0
Bank Sta=4994.8,5000.8
XS Rating Curve= 0 ,0
Exp/Cntr=0.3,0.1

Type RM Length L Ch R = 1 ,2660    ,467,467,467
BEGIN DESCRIPTION:
UNT058 IN ROCK 5.0
END DESCRIPTION:
XS GIS Cut Line= 3
      3658848.46     10165572.86      3658783.35     10165835.91
      3658837.71     10166128.41
#Sta/Elev= 30
  4809.9  317.96  4829.2  316.38  4856.1  314.86  4861.2  315.07  4870.5  313.65
  4897.5  312.29    4922  310.02  4932.3  309.46  4945.2  307.88  4952.9  306.39
  4963.2  305.49  4973.5  303.93  4985.5  299.94  5001.4  292.12  5004.1  291.62
  5007.4  292.12  5021.7  302.27  5061.5  303.59  5068.3   303.4  5076.1  304.06
  5096.6  303.81  5127.4  305.05  5154.5  304.81  5259.6  309.26    5280  310.38
  5300.3  312.04  5310.5  312.09    5323  312.93  5370.8  314.35  5378.4  315.16
#Mann= 5 ,-1 , 0
  4809.9     .05       0  4945.2     .12       0  5001.4     .07       0
  5007.4     .12       0  5061.5     .05       0
Bank Sta=5001.4,5007.4
XS Rating Curve= 0 ,0
Exp/Cntr=0.3,0.1

Type RM Length L Ch R = 1 ,2193    ,468,468,468
BEGIN DESCRIPTION:
UNT058 IN ROCK 4.0
END DESCRIPTION:
XS GIS Cut Line= 3
       3658564.6     10165505.18       3658313.6     10165916.81
      3658319.76      10166128.4
#Sta/Elev= 30
  4607.1  307.03  4642.3  304.35  4657.8  304.19  4743.5  298.74  4816.6  295.49
  4867.5  293.98  4911.5  292.24  4926.9  292.37  4932.8     292  4954.3   292.5
  4963.7  292.03  4969.6  292.41  4977.8  291.83    4985  288.25  4990.9  290.89
  5000.5  287.52  5003.3  287.04  5006.1  286.54  5009.3  287.04  5012.9  289.37
  5021.8  292.41  5027.7  293.33  5071.5  299.21  5079.9  299.81  5089.1   301.2
  5094.1   301.2  5111.1  302.76  5194.1  311.55  5274.1  311.44  5300.9  313.41
#Mann= 5 ,-1 , 0
  4607.1     .05       0  4867.5     .12       0  5003.3     .07       0
  5009.3     .12       0  5111.1     .05       0
Bank Sta=5003.3,5009.3
XS Rating Curve= 0 ,0
Exp/Cntr=0.3,0.1

Type RM Length L Ch R = 1 ,1725    ,732,732,732
BEGIN DESCRIPTION:
UNT058 IN ROCK 3.0
END DESCRIPTION:
XS GIS Cut Line= 3
      3658457.88     10165387.97      3658192.11     10165491.64
      3657906.45     10165692.19
#Sta/Elev= 30
  4718.1  304.94  4729.9  304.02    4771  300.69  4788.7  299.92    4820  297.13
  4863.8  294.65  4904.2  291.42  4909.6  291.86  4928.2  289.98  4934.1  288.95
  4950.8  287.95  4958.6  287.16    4964  287.57  4981.9  285.87  4985.4  279.11
  4988.2  278.61  4991.4  279.11  4993.8  279.89  5006.4  279.88  5010.8  285.39
  5016.9   286.3  5031.7  286.66  5076.1  286.55  5111.9  287.78  5134.7  289.08
  5183.3  290.75  5211.1  292.52    5240  293.57  5269.6  293.71  5352.4  296.98
#Mann= 6 ,-1 , 0
  4718.1     .16       0  4729.9     .12       0  4950.8      .1       0
  4985.4     .07       0  4991.4      .1       0  5134.7     .05       0
Bank Sta=4985.4,4991.4
XS Rating Curve= 0 ,0
Exp/Cntr=0.3,0.1

Type RM Length L Ch R = 1 ,993     ,415,415,415
BEGIN DESCRIPTION:
UNT058 IN ROCK 2.0
END DESCRIPTION:
XS GIS Cut Line= 3
      3658147.91     10164947.92      3657908.35     10165200.49
        3657747.     10165562.23
#Sta/Elev= 30
  4562.5  307.01  4583.3  305.45    4633  303.83  4703.8  297.81  4765.9  290.85
  4781.5  289.83  4830.8  285.28  4866.4  283.67  4887.4  281.88  4910.6  280.82
  4915.5  280.05  4933.3     280  4938.7  279.47  4955.7  279.53  4967.4  278.97
  4977.6  277.75  4985.2  273.94 4988.35  270.83  4990.7   268.7  4999.2  267.53
  5002.5  268.03  5008.4  271.29  5013.9  276.18  5021.4  279.05  5037.1  281.29
  5065.8  283.39    5130   284.8  5205.1  287.94  5251.3  288.99  5306.7  291.72
#Mann= 5 ,-1 , 0
  4562.5     .16       0  4765.9     .12       0 4988.35     .07       0
  5008.4     .12       0  5037.1     .05       0
Bank Sta=4988.35,5008.4
XS Rating Curve= 0 ,0
Exp/Cntr=0.3,0.1

Type RM Length L Ch R = 1 ,578     ,404,404,404
BEGIN DESCRIPTION:
UNT058 IN ROCK 1.0
END DESCRIPTION:
XS GIS Cut Line= 3
      3658064.57     10164661.45      3657673.98     10164908.82
      3657541.67     10165378.41
#Sta/Elev= 30
  4415.2  304.69  4460.9  300.39  4482.1  299.81  4497.4  297.68  4518.5  297.04
  4533.8  295.14  4576.2  293.14  4606.7  290.43  4670.2  287.74  4685.5  286.16
  4706.7   285.7  4721.9  283.72  4822.8  278.63  4875.7  275.91  4963.6  275.22
  4972.7  273.71  4977.9  271.75  4984.4  267.55  4994.7  263.42  5004.9  262.28
  5008.1  262.78  5011.9  266.52  5025.9  273.44  5040.3  275.06  5106.8  277.36
  5141.3  279.47  5163.6  278.54  5231.6  282.26  5304.9  284.03  5365.4   288.1
#Mann= 7 ,-1 , 0
  4415.2      .1       0  4822.8     .07       0  4984.4     .05       0
  5008.1     .07       0  5040.3      .1       0  5106.8     .12       0
  5141.3     .05       0
Bank Sta=4984.4,5011.9
XS Rating Curve= 0 ,0
Exp/Cntr=0.3,0.1

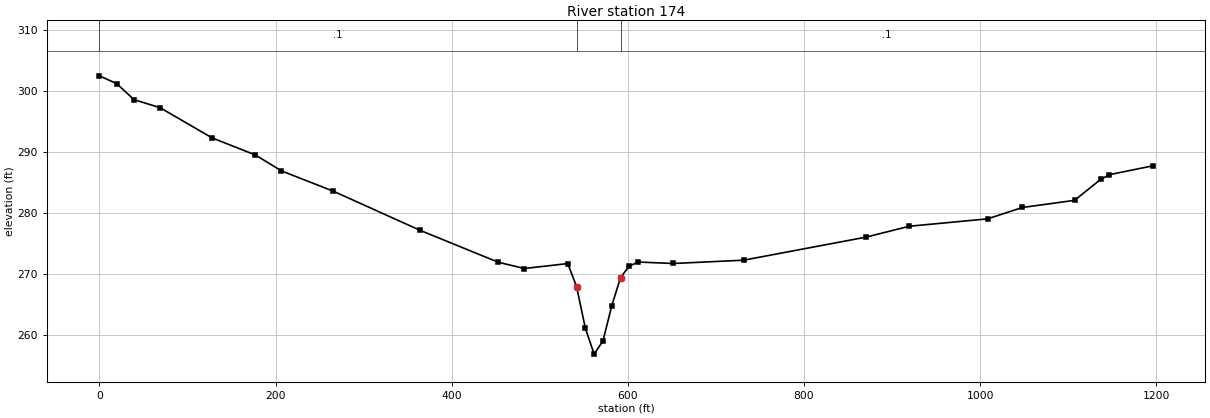
Type RM Length L Ch R = 1 ,174     ,0,0,0
XS GIS Cut Line= 5
     3658045.534    10164633.469      3657547.27    10164782.775
     3657380.603     10164994.58     3657418.798    10165397.358
3657418.7980115210165397.3581215
#Sta/Elev= 30
       0302.525119.69118301.245739.38235298.606168.91912297.2962127.9927292.3272
177.2206289.5187206.7574286.9032265.8309283.5571364.2868277.1284452.8971271.8975
482.4338270.8631531.7983271.6758541.7804267.8964551.7625261.0522561.7446256.7965
571.7267 258.949581.7089264.7081 591.691269.3854601.6731271.2536611.6552271.9303
651.5836271.6888731.4405272.2314870.2765276.0192919.6161  277.811008.427279.0222
1047.899280.89081107.107282.0652 1136.71 285.4961146.578286.27611195.918287.7355
#Mann= 3 , 0 , 0
       0      .1       0541.7804     .05       0 591.691      .1       0
Bank Sta=541.7804,591.691
XS Rating Curve= 0 ,0
Exp/Cntr=0.3,0.1

Chan Stop Cuts=-1
Use User Specified Reach Order=0
Composite Channel Slope=5