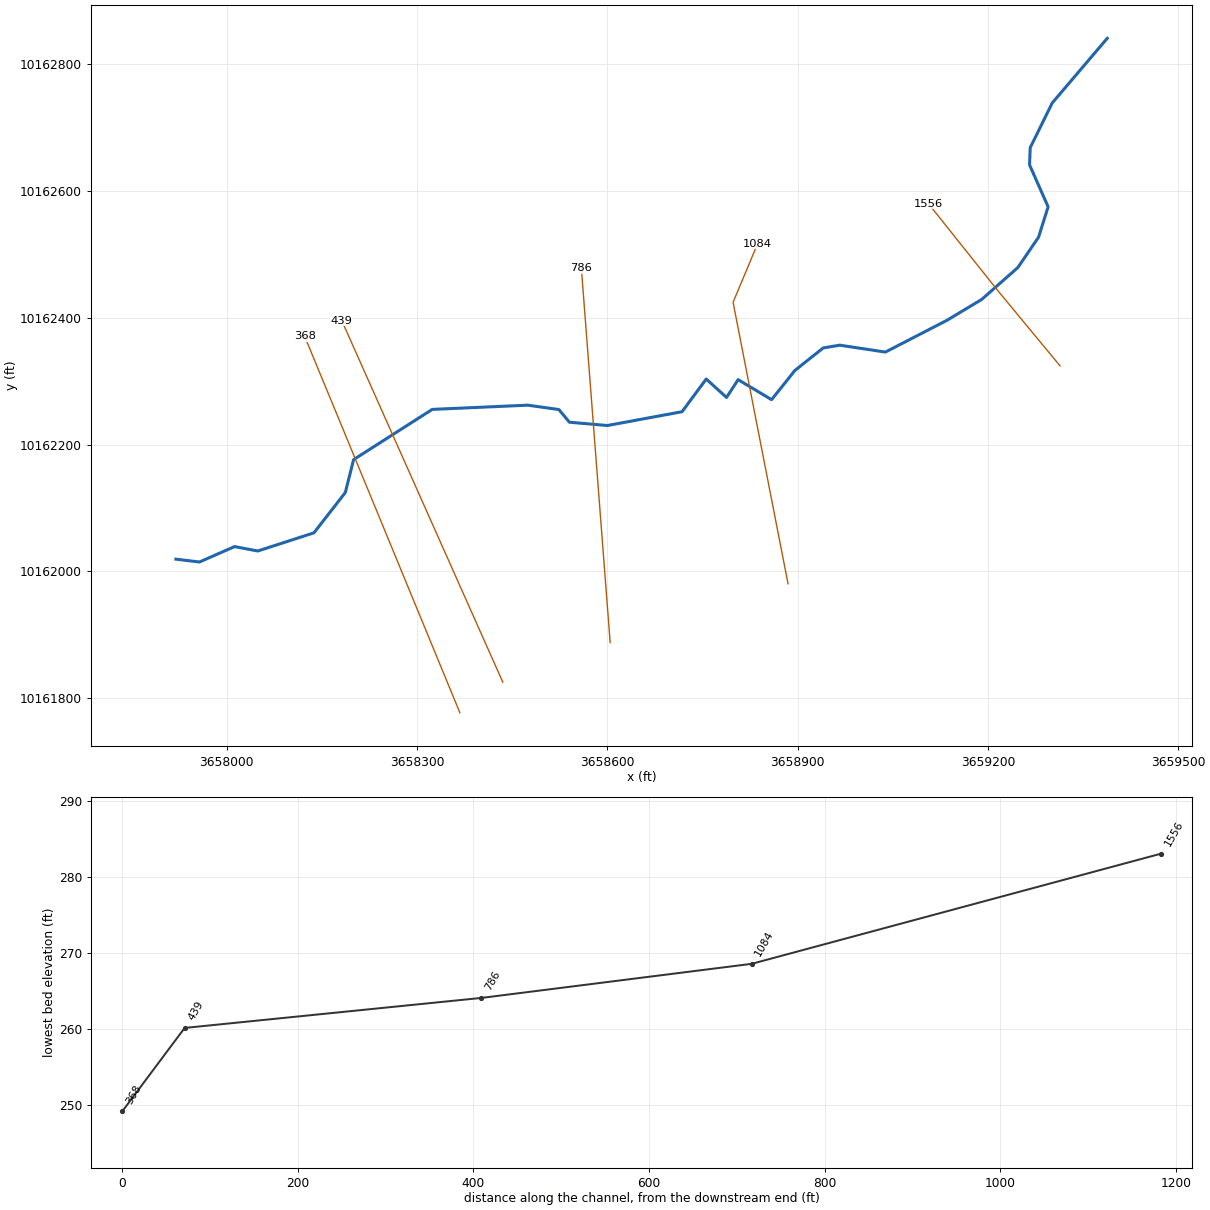
--- UNT059 IN ROCK.prj (project) ---

Proj Title=UNT059 IN ROCK Base Level Engineering
Current Plan=p01
Default Exp/Contr=0.3,0.1
English Units
Geom File=g01
Flow File=f01
Plan File=p01
Y Axis Title=Elevation
X Axis Title(PF)=Main Channel Distance
X Axis Title(XS)=Station
BEGIN DESCRIPTION:
UNT059 IN ROCK
END DESCRIPTION:
DSS Export Rating Curves= 0
DSS Export Rating Curve Sorted= 0
DSS Export Volume Flow Curves= 0
DXF OffsetX= 0
DXF OffsetY= 0
DXF ScaleX= 1
DXF ScaleY= 10

--- UNT059 IN ROCK.p01 (plan) ---

Plan Title=Multiple Run
Short Identifier=Multiple
Geom File=g01
Flow File=f01
Subcritical Flow
K Sum by GR= 0
Std Step Tol= 0.01
Critical Tol= 0.01
Num of Std Step Trials= 20
Max Error Tol= 0.3
Flow Tol Ratio= 0.001
Split Flow NTrial= 30
Split Flow Tol= 0.02
Split Flow Ratio= 0.02
Log Output Level= 0
Friction Slope Method= 1
Unsteady Friction Slope Method= 2
Unsteady Bridges Friction Slope Method= 1
Parabolic Critical Depth
Global Vel Dist=  1 , 1 , 1
Global Log Level= 0
CheckData=True
Encroach Param= -1, 0, 0, 0
BEGIN DESCRIPTION:
Multiple Run
END DESCRIPTION:

--- UNT059 IN ROCK.f01 (steady flow) ---

Flow Title=Multiple
Program Version=4.10
Number of Profiles= 7
Profile Names=10-year,25-year,50-year,1pct_min,100-year,1pct_plu,500-year
River Rch & RM=UNT059 IN ROCK,Reach-1         ,1556
     127     154     175     147     198     268     253
Boundary for River Rch & Prof#=UNT059 IN ROCK,Reach-1         , 1
Up Type= 0
Dn Type= 3
Dn Slope=0.005
Boundary for River Rch & Prof#=UNT059 IN ROCK,Reach-1         , 2
Up Type= 0
Dn Type= 3
Dn Slope=0.005
Boundary for River Rch & Prof#=UNT059 IN ROCK,Reach-1         , 3
Up Type= 0
Dn Type= 3
Dn Slope=0.005
Boundary for River Rch & Prof#=UNT059 IN ROCK,Reach-1         , 4
Up Type= 0
Dn Type= 3
Dn Slope=0.005
Boundary for River Rch & Prof#=UNT059 IN ROCK,Reach-1         , 5
Up Type= 0
Dn Type= 3
Dn Slope=0.005
Boundary for River Rch & Prof#=UNT059 IN ROCK,Reach-1         , 6
Up Type= 0
Dn Type= 3
Dn Slope=0.005
Boundary for River Rch & Prof#=UNT059 IN ROCK,Reach-1         , 7
Up Type= 0
Dn Type= 3
Dn Slope=0.005
DSS Import GetInterval= 0
DSS Import GetPeak= 0
DSS Import FillOption= 0

--- UNT059 IN ROCK.g01 (geometry) ---

Geom Title=Existing Conditions
Program Version=4.10

River Reach=UNT059 IN ROCK  ,Reach-1
Reach XY= 30
      3659388.22     10162840.76       3659301.5     10162738.81
      3659266.78     10162668.28      3659265.69     10162641.15
      3659294.99     10162574.96      3659279.86     10162526.97
      3659247.26     10162479.16      3659189.97     10162428.63
      3659135.28     10162395.82      3659038.41     10162345.82
      3658966.38      10162356.7      3658940.34     10162352.36
      3658895.55     10162316.66      3658858.98     10162270.76
      3658806.21     10162302.31      3658787.92     10162274.23
       3658755.9     10162303.31      3658717.78     10162251.73
      3658600.07     10162229.96      3658540.17     10162235.17
      3658523.68     10162255.14      3658474.36     10162262.05
       3658323.9     10162255.39      3658199.89     10162176.14
      3658186.82     10162124.23      3658137.39     10162060.69
      3658048.85     10162032.05      3658012.23     10162038.97
      3657956.84     10162014.69      3657919.76     10162019.15

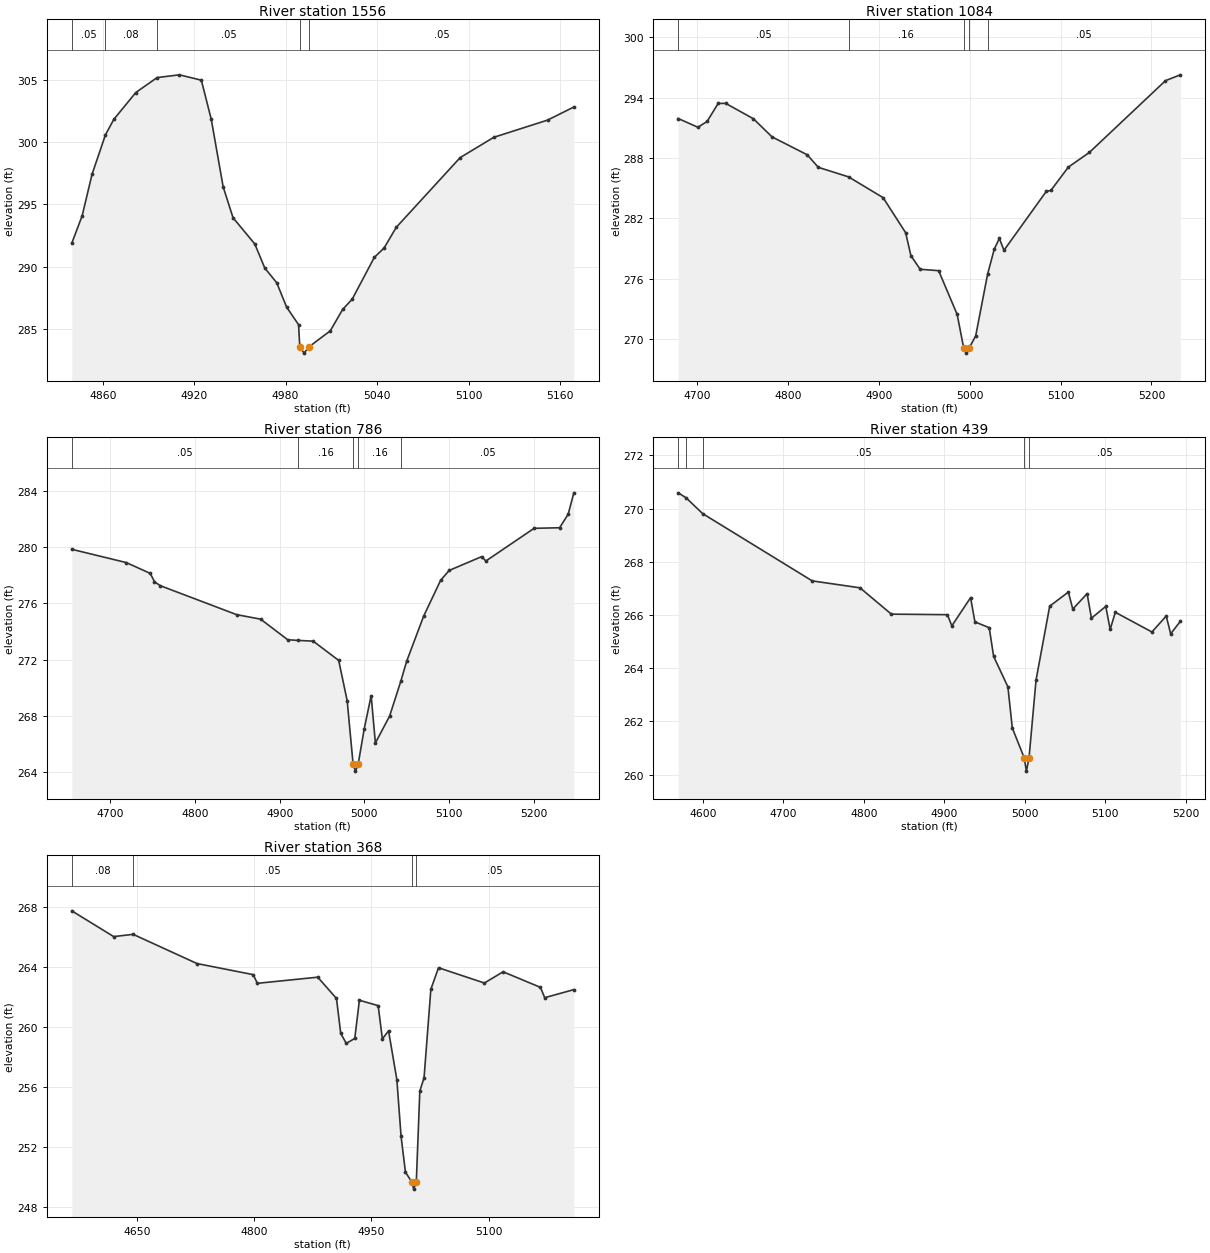
Type RM Length L Ch R = 1 ,1556    ,466,466,466
BEGIN DESCRIPTION:
UNT059 IN ROCK 3.0
END DESCRIPTION:
XS GIS Cut Line= 3
       3659313.7     10162324.13      3659215.78     10162442.59
      3659106.24     10162579.98
#Sta/Elev= 30
  4839.7  291.87  4846.5  294.07    4853   297.4  4861.8  300.57  4867.3  301.81
  4881.7  303.96  4895.7  305.16  4910.3  305.38  4924.7  304.95  4931.2  301.82
    4939  296.41  4945.5  293.92  4959.8  291.81  4966.3  289.89  4974.2   288.7
  4980.6  286.76  4988.5  285.34  4989.3  283.56  4992.1  283.06  4995.3  283.56
  5009.3  284.85  5017.4  286.56  5023.7  287.39  5038.2  290.74  5044.6  291.49
  5052.6  293.15  5094.5  298.74  5116.6  300.37  5151.9  301.75  5169.1   302.8
#Mann= 5 ,-1 , 0
  4839.7     .05       0  4861.8     .08       0  4895.7     .05       0
  4989.3     .04       0  4995.3     .05       0
Bank Sta=4989.3,4995.3
XS Rating Curve= 0 ,0
Exp/Cntr=0.3,0.1

Type RM Length L Ch R = 1 ,1084    ,308,308,308
BEGIN DESCRIPTION:
UNT059 IN ROCK 2.0
END DESCRIPTION:
XS GIS Cut Line= 3
      3658884.89      10161980.4      3658798.24     10162424.36
       3658836.9     10162516.66
#Sta/Elev= 30
  4679.4  291.93    4701  291.06  4711.2  291.64  4723.3  293.43  4731.6  293.44
  4762.2   291.9  4782.6   290.1  4821.3  288.32  4833.5  287.07  4866.8  286.12
  4904.8  284.05  4929.6  280.56  4935.4  278.27  4945.6  276.92  4965.9  276.78
  4986.3  272.42  4993.5  269.07  4996.3  268.57  4999.5  269.07  5006.7   270.3
  5019.8  276.44  5027.1  278.92  5032.7  279.99  5037.8  278.81  5084.3  284.67
  5089.4  284.77  5108.6  287.09  5131.7  288.55  5215.5   295.7  5231.8  296.28
#Mann= 5 ,-1 , 0
  4679.4     .05       0  4866.8     .16       0  4993.5     .07       0
  4999.5     .16       0  5019.8     .05       0
Bank Sta=4993.5,4999.5
XS Rating Curve= 0 ,0
Exp/Cntr=0.3,0.1

Type RM Length L Ch R = 1 ,786     ,338,338,338
BEGIN DESCRIPTION:
Mapping XS db0d5e95
END DESCRIPTION:
XS GIS Cut Line= 2
      3658604.45      10161887.6      3658559.01     10162478.36
#Sta/Elev= 30
  4654.7  279.83  4718.9  278.89  4747.3  278.12  4752.3  277.53    4759  277.25
  4849.3  275.19  4877.6  274.87  4909.5  273.41  4921.9  273.36  4939.6  273.31
  4969.7  271.94  4979.7  269.08  4986.7  264.58  4989.5  264.08  4992.7  264.58
  4999.8  267.07    5008  269.44    5013  266.08  5029.8  267.99  5043.1  270.48
  5049.9  271.88    5070  275.09    5090  277.63  5100.1  278.33  5138.4  279.31
  5143.4     279  5200.3  281.32  5230.4  281.36  5240.5  282.32  5247.2  283.84
#Mann= 5 ,-1 , 0
  4654.7     .05       0  4921.9     .16       0  4986.7     .07       0
  4992.7     .16       0  5043.1     .05       0
Bank Sta=4986.7,4992.7
XS Rating Curve= 0 ,0
Exp/Cntr=0.3,0.1

Type RM Length L Ch R = 1 ,439     ,71,71,71
BEGIN DESCRIPTION:
Mapping XS d9a1fb11
END DESCRIPTION:
XS GIS Cut Line= 2
      3658435.17     10161825.16      3658181.26     10162395.49
#Sta/Elev= 30
  4569.2  270.59  4579.1   270.4  4599.5  269.81  4735.8  267.28  4795.2  267.02
  4834.2  266.03  4903.9  266.01  4909.4  265.59  4932.7  266.65  4938.1  265.74
  4955.9  265.52  4961.4  264.44  4979.1   263.3  4984.6  261.75  4999.4  260.63
  5002.1  260.13  5005.4  260.63  5014.1  263.55  5031.1  266.33  5054.3  266.86
  5059.8  266.22  5077.6   266.8    5083  265.88  5100.8  266.32  5106.3  265.46
  5112.7   266.1  5158.2  265.36    5176  265.96  5181.5  265.29  5193.5  265.76
#Mann= 5 ,-1 , 0
  4569.2     .05       0  4579.1     .08       0  4599.5     .05       0
  4999.4     .04       0  5005.4     .05       0
Bank Sta=4999.4,5005.4
XS Rating Curve= 0 ,0
Exp/Cntr=0.3,0.1

Type RM Length L Ch R = 1 ,368     ,0,0,0
BEGIN DESCRIPTION:
UNT059 IN ROCK 1.0
END DESCRIPTION:
XS GIS Cut Line= 3
      3658367.47     10161776.97      3658178.67      10162235.3
      3658122.69     10162370.69
#Sta/Elev= 30
  4566.8  267.74  4620.4  266.02  4645.3  266.17    4727  264.22  4798.8  263.48
  4804.2   262.9  4881.4  263.31  4905.4  261.89  4910.8  259.56  4917.9  258.89
  4928.8  259.22  4934.7  261.77  4958.7  261.41  4964.1  259.19    4972  259.73
  4982.6  256.47    4988  252.69  4993.6  250.29  5001.5  249.66  5004.2  249.16
  5007.5  249.66    5012  255.71  5017.4  256.59  5026.1   262.5  5035.9  263.94
  5094.6  262.92  5118.5  263.67  5166.3  262.63  5171.7  261.94    5209  262.48
#Mann= 4 ,-1 , 0
  4566.8     .08       0  4645.3     .05       0  5001.5     .03       0
  5007.5     .05       0
Bank Sta=5001.5,5007.5
XS Rating Curve= 0 ,0
Exp/Cntr=0.3,0.1
Stream Node=UNT059 IN ROCK  ,Reach-1         , 0 , 0 ,Upstream end
Stream Node=UNT059 IN ROCK  ,Reach-1         , 0 , 1 ,Downstream end

Chan Stop Cuts=-1
Use User Specified Reach Order=0
Composite Channel Slope=5