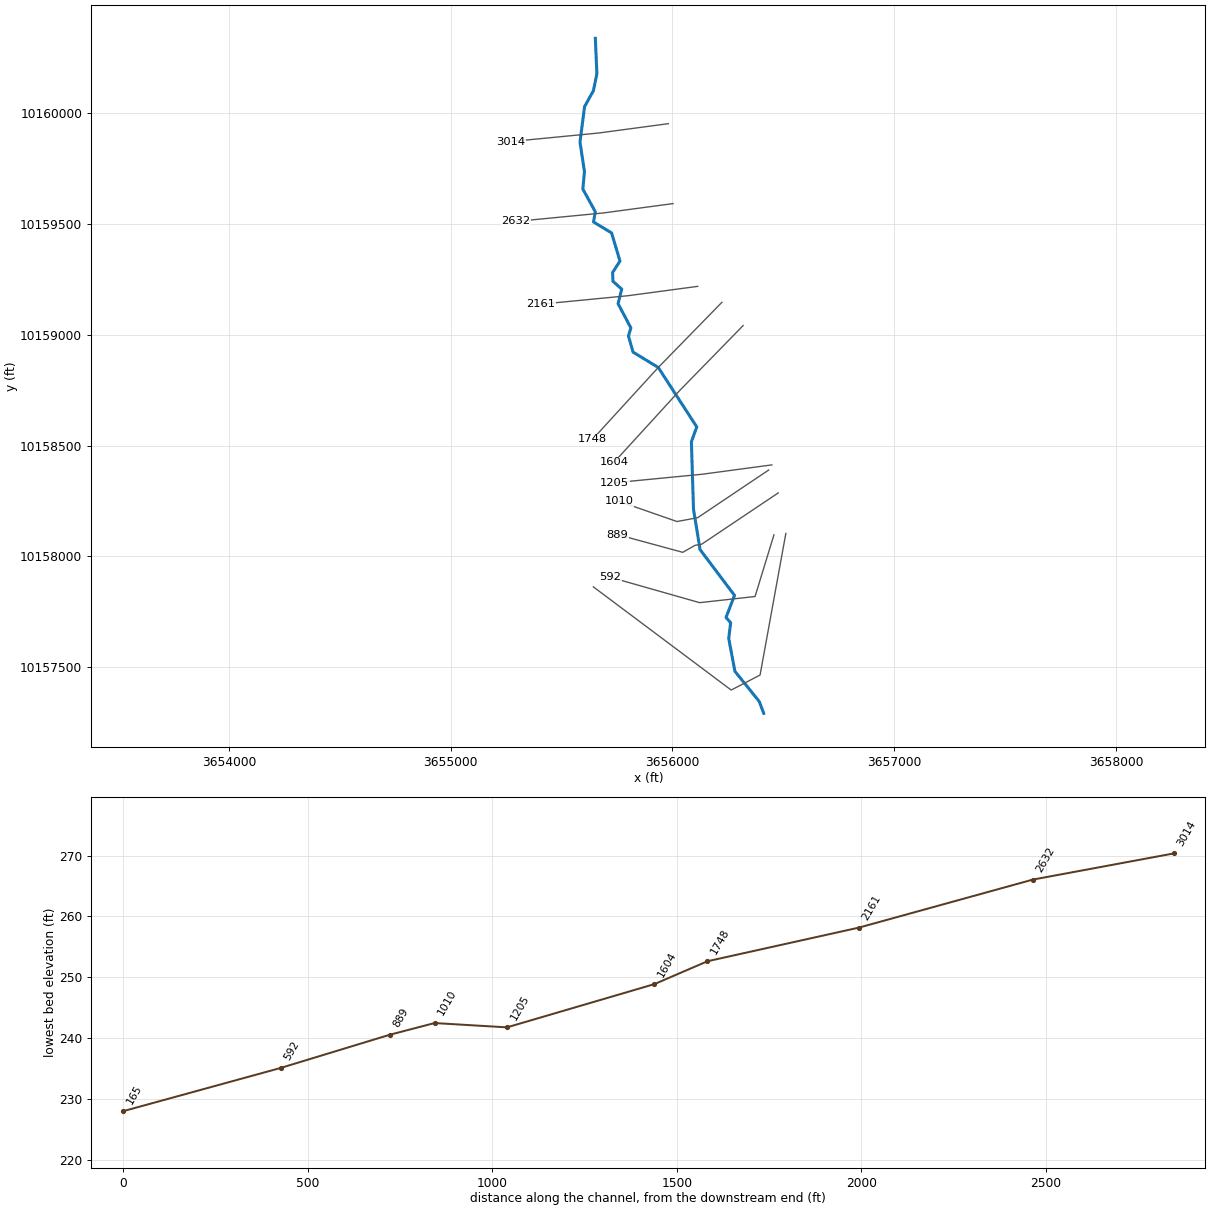
--- UNT060 IN ROCK.prj (project) ---

Proj Title=UNT060 IN ROCK Base Level Engineering
Current Plan=p01
Default Exp/Contr=0.3,0.1
English Units
Geom File=g01
Flow File=f01
Plan File=p01
Y Axis Title=Elevation
X Axis Title(PF)=Main Channel Distance
X Axis Title(XS)=Station
BEGIN DESCRIPTION:
UNT060 IN ROCK
END DESCRIPTION:
DSS Export Rating Curves= 0
DSS Export Rating Curve Sorted= 0
DSS Export Volume Flow Curves= 0
DXF OffsetX= 0
DXF OffsetY= 0
DXF ScaleX= 1
DXF ScaleY= 10

--- UNT060 IN ROCK.p01 (plan) ---

Plan Title=Multiple Run
Short Identifier=Multiple
Geom File=g01
Flow File=f01
Subcritical Flow
K Sum by GR= 0
Std Step Tol= 0.01
Critical Tol= 0.01
Num of Std Step Trials= 20
Max Error Tol= 0.3
Flow Tol Ratio= 0.001
Split Flow NTrial= 30
Split Flow Tol= 0.02
Split Flow Ratio= 0.02
Log Output Level= 0
Friction Slope Method= 1
Unsteady Friction Slope Method= 2
Unsteady Bridges Friction Slope Method= 1
Parabolic Critical Depth
Global Vel Dist=  1 , 1 , 1
Global Log Level= 0
CheckData=True
Encroach Param= -1, 0, 0, 0
BEGIN DESCRIPTION:
Multiple Run
END DESCRIPTION:

--- UNT060 IN ROCK.f01 (steady flow) ---

Flow Title=Multiple
Program Version=4.10
Number of Profiles= 7
Profile Names=10-year,25-year,50-year,1pct_min,100-year,1pct_plu,500-year
River Rch & RM=UNT060 IN ROCK,Reach-1         ,3014
     158     196     224     190     257     348     337
Boundary for River Rch & Prof#=UNT060 IN ROCK,Reach-1         , 1
Up Type= 0
Dn Type= 3
Dn Slope=0.005
Boundary for River Rch & Prof#=UNT060 IN ROCK,Reach-1         , 2
Up Type= 0
Dn Type= 3
Dn Slope=0.005
Boundary for River Rch & Prof#=UNT060 IN ROCK,Reach-1         , 3
Up Type= 0
Dn Type= 3
Dn Slope=0.005
Boundary for River Rch & Prof#=UNT060 IN ROCK,Reach-1         , 4
Up Type= 0
Dn Type= 3
Dn Slope=0.005
Boundary for River Rch & Prof#=UNT060 IN ROCK,Reach-1         , 5
Up Type= 0
Dn Type= 3
Dn Slope=0.005
Boundary for River Rch & Prof#=UNT060 IN ROCK,Reach-1         , 6
Up Type= 0
Dn Type= 3
Dn Slope=0.005
Boundary for River Rch & Prof#=UNT060 IN ROCK,Reach-1         , 7
Up Type= 0
Dn Type= 3
Dn Slope=0.005
DSS Import GetInterval= 0
DSS Import GetPeak= 0
DSS Import FillOption= 0

--- UNT060 IN ROCK.g01 (geometry) ---

Geom Title=Existing Conditions
Program Version=4.10

River Reach=UNT060 IN ROCK  ,Reach-1
Reach XY= 30
      3655652.47     10160336.36      3655659.41     10160176.64
      3655643.79     10160100.25      3655603.86      10160028.2
      3655583.27      10159868.4      3655603.33     10159736.11
      3655596.29     10159656.43      3655652.48     10159554.06
      3655644.15     10159508.23      3655725.78     10159458.71
      3655763.58     10159332.02      3655730.26     10159280.06
      3655732.02     10159240.41      3655771.49     10159205.19
        3655755.     10159139.65      3655812.72     10159030.49
      3655801.87     10158994.03      3655822.71     10158921.12
      3655936.32     10158851.99      3656109.93     10158583.76
      3656085.63     10158516.92      3656095.18      10158213.1
      3656124.69     10158030.81      3656280.07     10157824.21
      3656241.88     10157724.38      3656262.71     10157700.94
      3656254.03     10157629.76      3656282.02     10157481.54
      3656391.62     10157345.91      3656411.96     10157291.99

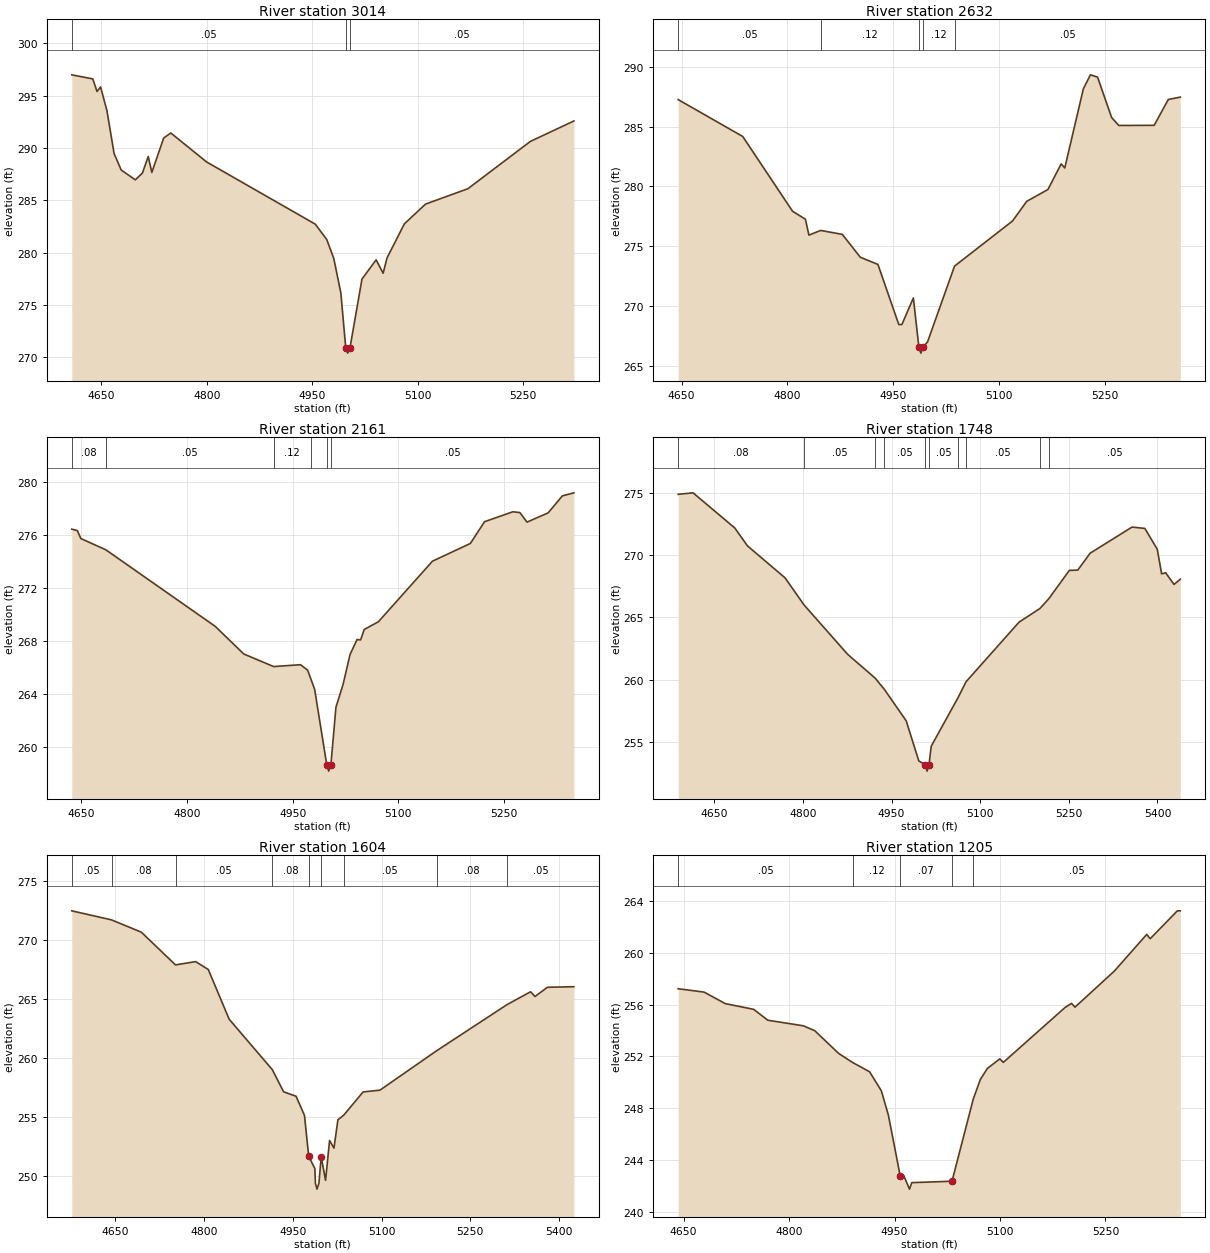
Type RM Length L Ch R = 1 ,3014    ,382,382,382
BEGIN DESCRIPTION:
UNT060 IN ROCK 7.0
END DESCRIPTION:
XS GIS Cut Line= 3
      3655981.74     10159951.55      3655667.16     10159909.35
      3655272.02     10159870.98
#Sta/Elev= 30
  4607.8  296.99  4637.7   296.6  4643.7   295.4  4648.8  295.83  4657.9  293.54
    4668  289.47  4678.1  287.89  4698.2  286.95  4708.3   287.6  4716.6  289.18
  4721.7  287.66  4738.6  290.95  4748.7  291.43  4799.6  288.66  4954.3  282.71
  4970.5  281.25  4980.5  279.45  4990.6  276.15  4997.6  270.88  5000.4  270.38
  5003.6  270.88  5020.7  277.46  5040.8   279.3  5050.8  278.02  5056.3  279.48
    5081  282.74  5111.1  284.63  5171.4   286.1  5260.2  290.62  5322.2  292.58
#Mann= 3 ,-1 , 0
  4607.8     .05       0  4997.6     .03       0  5003.6     .05       0
Bank Sta=4997.6,5003.6
XS Rating Curve= 0 ,0
Exp/Cntr=0.3,0.1

Type RM Length L Ch R = 1 ,2632    ,471,471,471
BEGIN DESCRIPTION:
UNT060 IN ROCK 6.0
END DESCRIPTION:
XS GIS Cut Line= 3
      3656002.94     10159591.05       3655688.4     10159548.85
      3655295.21     10159510.68
#Sta/Elev= 30
  4645.1  287.25  4736.7  284.17  4807.4  277.92  4825.6  277.26  4830.6  275.93
  4847.2  276.32    4878  275.99  4903.5  274.08  4928.5  273.48  4958.1  268.46
  4962.5  268.46  4978.8  270.68  4986.6  266.57  4989.4  266.07  4992.6  266.57
  4998.9  267.01  5037.2  273.34  5119.5  277.11  5139.6  278.75  5169.7  279.74
  5188.5  281.88  5193.6  281.54    5220  288.16    5230  289.32  5240.1  289.13
  5260.1  285.75  5270.2  285.09  5320.4   285.1  5340.5  287.26  5357.5  287.46
#Mann= 5 ,-1 , 0
  4645.1     .05       0  4847.2     .12       0  4986.6     .07       0
  4992.6     .12       0  5037.2     .05       0
Bank Sta=4986.6,4992.6
XS Rating Curve= 0 ,0
Exp/Cntr=0.3,0.1

Type RM Length L Ch R = 1 ,2161    ,410,410,410
BEGIN DESCRIPTION:
UNT060 IN ROCK 5.0
END DESCRIPTION:
XS GIS Cut Line= 3
      3656114.11     10159217.79      3655799.52     10159175.59
      3655405.78     10159137.36
#Sta/Elev= 30
  4636.4  276.43  4644.3  276.32  4649.3  275.72  4684.8  274.87  4840.2  269.09
  4880.6  267.01    4923  266.06  4961.3   266.2  4971.3  265.79  4976.1  265.09
  4981.3  264.34  4998.4  258.67  5001.2  258.17  5004.4  258.67  5011.5  262.99
  5021.5  264.69  5031.6  266.98  5041.5   268.1  5046.5  268.07  5051.7  268.86
  5071.8  269.44  5148.5  274.01  5202.4  275.35  5222.5  276.99  5262.7  277.74
  5272.7  277.68  5282.8  276.96  5312.9  277.66    5333  278.94  5349.4  279.17
#Mann= 6 ,-1 , 0
  4636.4     .08       0  4684.8     .05       0    4923     .12       0
  4976.1     .05       0  4998.4     .03       0  5004.4     .05       0
Bank Sta=4998.4,5004.4
XS Rating Curve= 0 ,0
Exp/Cntr=0.3,0.1

Type RM Length L Ch R = 1 ,1748    ,144,144,144
BEGIN DESCRIPTION:
UNT060 IN ROCK 4.0
END DESCRIPTION:
XS GIS Cut Line= 3
      3656223.38     10159145.99      3655936.32     10158851.99
      3655640.28     10158528.36
#Sta/Elev= 30
  4589.1  274.88  4614.3     275    4685  272.17  4706.3  270.74  4769.9  268.17
  4802.1  265.99  4875.9  262.02  4922.4  260.11  4937.9  259.21  4974.9  256.68
  4996.2  253.46  5007.4  253.14  5010.2  252.64  5013.4  253.14  5017.2  254.64
  5063.1  258.59  5076.1  259.82  5165.8  264.61  5201.2  265.71  5216.4  266.51
  5250.9  268.77  5265.1  268.79  5286.1  270.15    5357  272.25  5378.6  272.14
  5399.6  270.47    5407  268.49  5413.8  268.58  5427.9  267.64  5438.6  268.06
#Mann= 10 ,-1 , 0
  4589.1     .08       0  4802.1     .05       0  4922.4     .08       0
  4937.9     .05       0  5007.4     .04       0  5013.4     .05       0
  5063.1     .08       0  5076.1     .05       0  5201.2     .08       0
  5216.4     .05       0
Bank Sta=5007.4,5013.4
XS Rating Curve= 0 ,0
Exp/Cntr=0.3,0.1

Type RM Length L Ch R = 1 ,1604    ,399,399,399
BEGIN DESCRIPTION:
UNT060 IN ROCK 3.0
END DESCRIPTION:
XS GIS Cut Line= 3
      3656318.98     10159040.97      3656031.94     10158746.99
      3655736.49     10158424.01
#Sta/Elev= 30
  4576.4  272.49  4643.6  271.72  4693.9  270.68  4751.7   267.9  4785.8  268.18
  4807.1  267.51  4842.4  263.29  4915.3  259.01  4934.4  257.13  4955.5  256.75
  4969.7  255.12  4976.8  251.66  4987.3   250.6  4988.1  249.37  4990.8  248.87
  4994.1  249.37  4997.9  251.61  5005.3  249.62  5012.1     253  5019.5  252.35
  5026.2  254.76  5035.7  255.13  5068.8  257.12  5097.2  257.27  5193.5  260.63
    5312  264.53  5351.8  265.62  5359.3  265.22  5380.2     266    5425  266.05
#Mann= 9 ,-1 , 0
  4576.4     .05       0  4643.6     .08       0  4751.7     .05       0
  4915.3     .08       0  4976.8     .07       0  4997.9     .08       0
  5035.7     .05       0  5193.5     .08       0    5312     .05       0
Bank Sta=4976.8,4997.9
XS Rating Curve= 0 ,0
Exp/Cntr=0.3,0.1

Type RM Length L Ch R = 1 ,1205    ,196,196,196
BEGIN DESCRIPTION:
UNT060 IN ROCK 2.0
END DESCRIPTION:
XS GIS Cut Line= 3
       3656448.6     10158412.64        3656134.     10158370.44
      3655738.87     10158332.08
#Sta/Elev= 30
  4642.2  257.22    4679  256.96  4709.3  256.07  4749.6  255.63  4769.8  254.79
  4820.3  254.36  4836.6  253.98  4870.7  252.22  4890.7  251.52  4914.6  250.81
  4931.3  249.34  4941.3  247.46    4958  242.81  4963.1  242.81  4971.3  241.76
  4974.6  242.26  5031.8  242.37    5062   248.7    5072  250.21  5082.1  251.07
  5099.8  251.81  5104.8  251.54  5192.6  255.77  5201.8  256.09  5206.8   255.8
  5262.9  258.59  5308.8  261.41  5313.8  261.08  5352.4  263.23  5356.6  263.23
#Mann= 5 ,-1 , 0
  4642.2     .05       0  4890.7     .12       0    4958     .07       0
  5031.8     .12       0    5062     .05       0
Bank Sta=4958,5031.8
XS Rating Curve= 0 ,0
Exp/Cntr=0.3,0.1

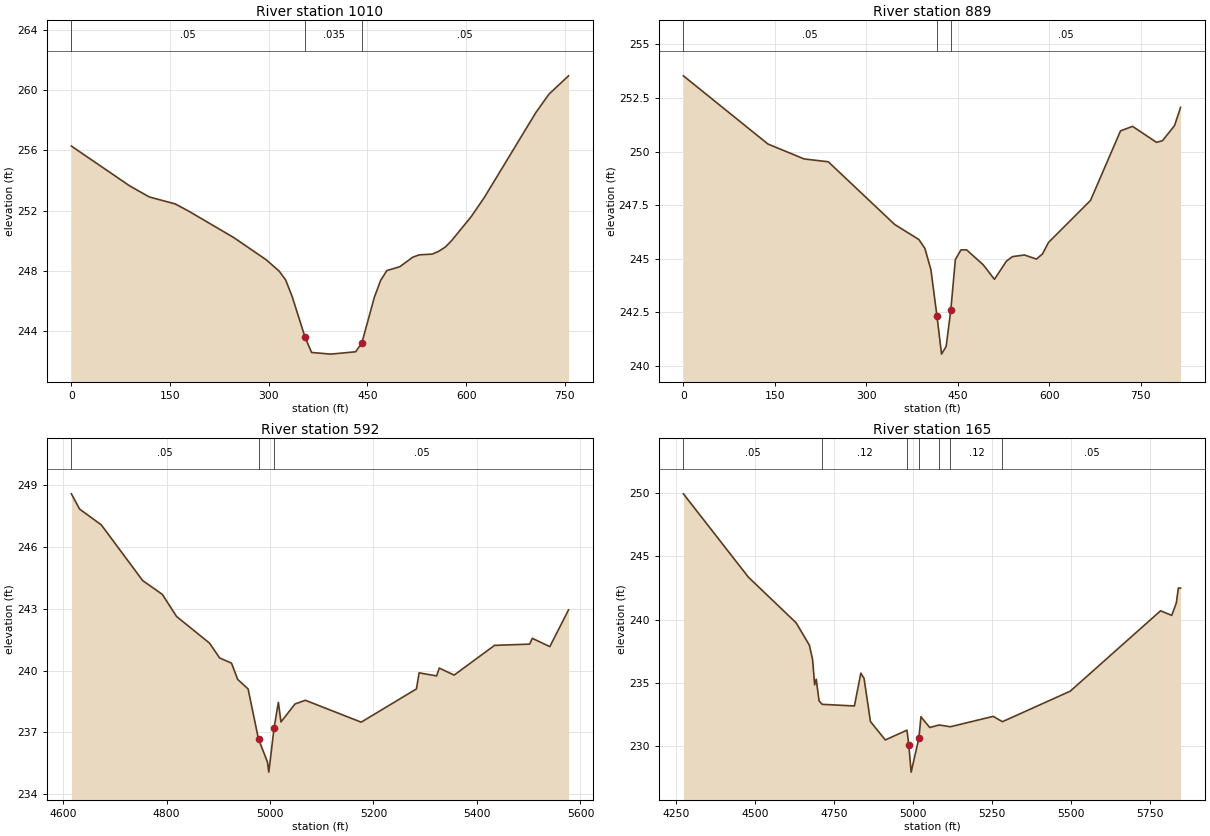
Type RM Length L Ch R = 1 ,1010    ,121,121,121
XS GIS Cut Line= 4
     3656434.077    10158389.387     3656113.982    10158174.543
     3656020.666    10158157.182     3655759.164    10158248.328
#Sta/Elev= 30
       0256.290588.80592253.6414118.4079252.9111157.8772252.4458177.6118251.9864
246.6831250.2166296.0197248.7418315.7544247.9886325.6217247.4065 335.489246.3091
355.2237243.5898 365.091242.5805394.2917242.4686432.1562 242.625441.6223 243.228
460.5546246.2451470.0207247.3563479.4868248.0179499.2209248.2766 518.955248.9085
 528.822249.0646548.5562249.1134558.4232249.3011568.2902249.5782578.1573250.0177
607.7584251.6038627.4925 252.861706.4288258.5424726.1629259.7486 755.764260.9583
#Mann= 3 , 0 , 0
       0     .05       0355.2237    .035       0441.6223     .05       0
Bank Sta=355.2237,441.6223
XS Rating Curve= 0 ,0
Exp/Cntr=0.3,0.1

Type RM Length L Ch R = 1 ,889     ,296,296,296
XS GIS Cut Line= 5
      3656477.48    10158286.305     3656132.428    10158055.185
     3656102.046     10158049.76     3656046.707    10158018.293
     3655751.568    10158098.588
#Sta/Elev= 30
       0253.5341138.6118250.3536198.0169249.6562237.6202249.5242346.5295246.5994
386.1329245.8984396.0337245.4881405.9345244.4954415.8354242.3427 423.399240.5504
430.9625240.9096 438.526242.5878446.0896244.9677455.2446245.4132464.3995 245.418
491.8645244.7159510.1744244.0402 529.869244.8891539.7162245.0995559.4107245.1763
579.1052244.9839588.9525245.2248598.7997  245.76667.7306247.7206716.9669250.9653
736.6614251.1765776.0504250.4306785.8977250.5107805.5922251.2142815.4395252.0616
#Mann= 3 , 0 , 0
       0     .05       0415.8354    .035       0 438.526     .05       0
Bank Sta=415.8354,438.526
XS Rating Curve= 0 ,0
Exp/Cntr=0.3,0.1

Type RM Length L Ch R = 1 ,592     ,427,427,427
BEGIN DESCRIPTION:
Mapping XS ed13de8c
END DESCRIPTION:
XS GIS Cut Line= 4
      3656457.87     10158096.83      3656372.81     10157819.07
      3656122.81      10157791.3      3655720.02     10157905.88
#Sta/Elev= 30
  4616.2  248.56  4632.1  247.82  4673.9  247.06  4753.9  244.36  4791.9  243.69
  4819.4  242.62  4883.1  241.33  4902.7  240.61  4925.6  240.36  4937.6  239.57
  4957.7  239.11  4977.8  236.68    4995  235.58  4997.7  235.08    5008  237.24
  5016.2  238.46  5021.2  237.51  5048.3  238.38  5068.4  238.56  5176.2   237.5
    5283  239.11  5288.2  239.89    5322  239.74  5327.2  240.12  5355.9  239.78
    5434  241.22  5501.8  241.28    5507  241.56  5540.8  241.16    5577  242.94
#Mann= 3 , 0 , 0
  4616.2     .05       0  4977.8    .035       0    5008     .05       0
Bank Sta=4977.8,5008
XS Rating Curve= 0 ,0
Exp/Cntr=0.3,0.1

Type RM Length L Ch R = 1 ,165     ,0,0,0
BEGIN DESCRIPTION:
UNT060 IN ROCK 1.0
END DESCRIPTION:
XS GIS Cut Line= 4
      3656511.69     10158103.75      3656395.38     10157464.91
      3656265.17      10157397.2      3655643.64     10157862.48
#Sta/Elev= 30
  4273.2  249.92  4478.6  243.35  4629.9  239.74  4671.8  237.97  4681.9  236.82
  4688.3  234.85  4693.4  235.29  4702.3  233.58  4712.3  233.31  4814.1  233.18
  4834.4  235.77  4844.6  235.36  4864.9  231.95  4911.8   230.5  4980.4  231.27
    4986  230.12  4993.6  227.96 5018.18  230.66  5024.6  232.33  5052.3  231.48
  5082.2  231.68  5117.6  231.54  5253.1  232.36  5282.3  231.94  5496.9  234.35
  5782.4  240.69  5817.8  240.33  5832.4  241.31  5838.7  242.49  5845.7  242.48
#Mann= 7 ,-1 , 0
  4273.2     .05       0  4712.3     .12       0  4980.4     .05       0
 5018.18     .12       0  5082.2     .07       0  5117.6     .12       0
  5282.3     .05       0
Bank Sta=4986,5018.18
XS Rating Curve= 0 ,0
Exp/Cntr=0.3,0.1
Stream Node=UNT060 IN ROCK  ,Reach-1         , 0 , 0 ,Upstream end
Stream Node=UNT060 IN ROCK  ,Reach-1         , 0 , 1 ,Downstream end

Chan Stop Cuts=-1
Use User Specified Reach Order=0
Composite Channel Slope=5