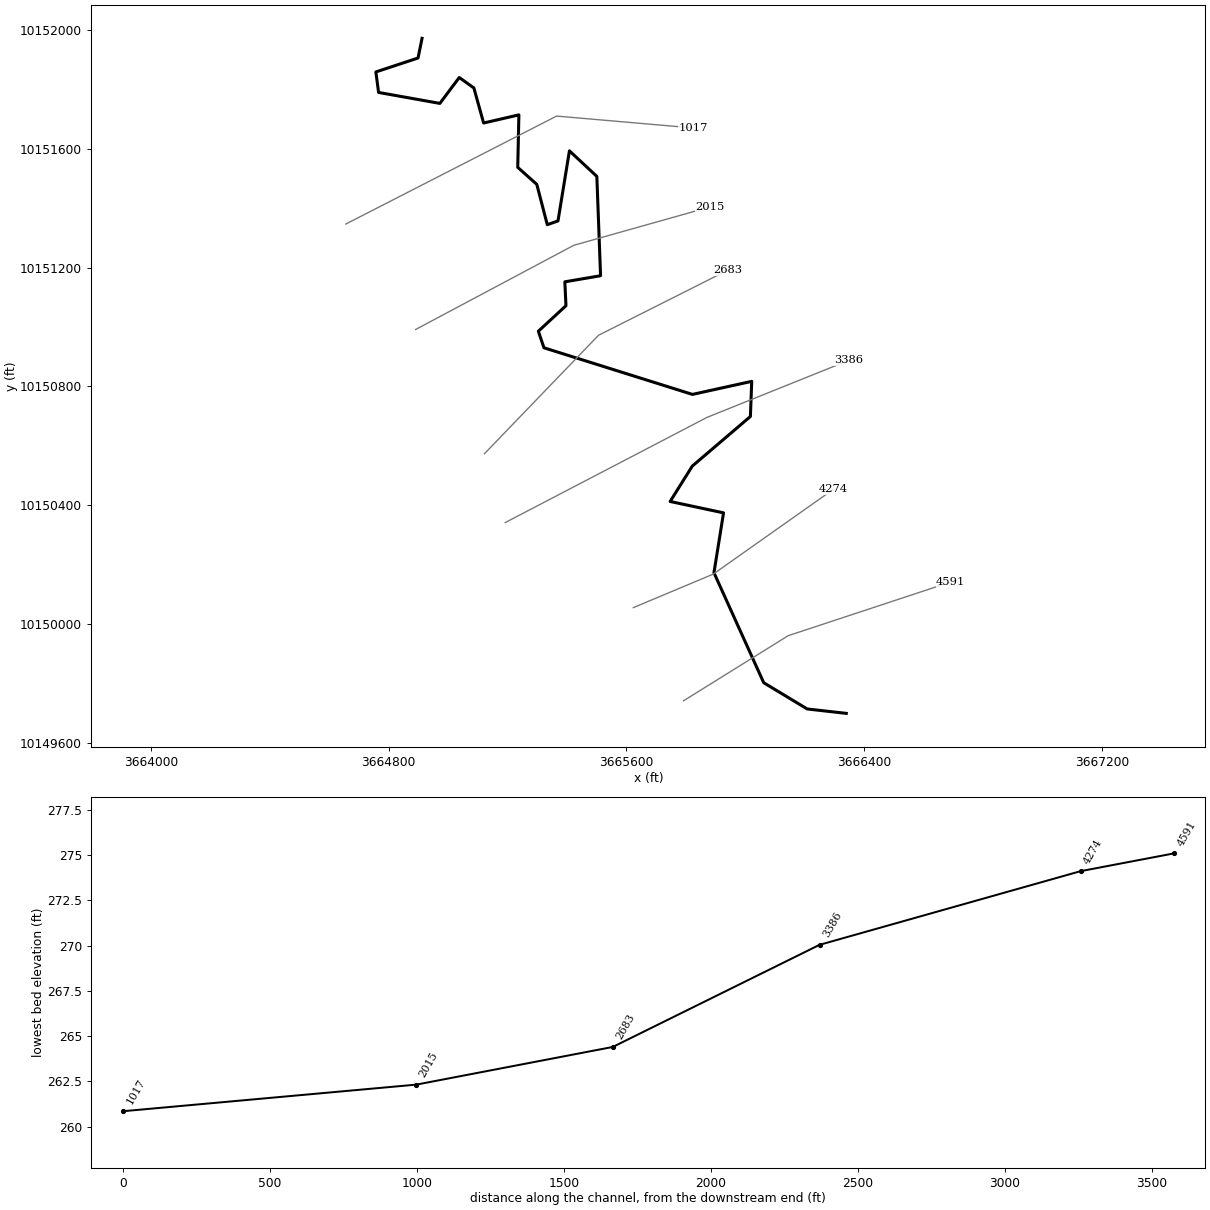
--- UNT061 IN ROCK.prj (project) ---

Proj Title=UNT061 IN ROCK Base Level Engineering
Current Plan=p01
Default Exp/Contr=0.3,0.1
English Units
Geom File=g01
Flow File=f01
Plan File=p01
BEGIN DESCRIPTION:
UNT061 IN ROCK
END DESCRIPTION:

--- UNT061 IN ROCK.p01 (plan) ---

Plan Title=Multiple Run
Short Identifier=Multiple
Geom File=g01
Flow File=f01
Subcritical Flow
K Sum by GR= 0
Std Step Tol= 0.01
Critical Tol= 0.01
Num of Std Step Trials= 20
Max Error Tol= 0.3
Flow Tol Ratio= 0.001
Split Flow NTrial= 30
Split Flow Tol= 0.02
Split Flow Ratio= 0.02
Log Output Level= 0
Friction Slope Method= 1
Unsteady Friction Slope Method= 2
Unsteady Bridges Friction Slope Method= 1
Parabolic Critical Depth
Global Vel Dist=  1 , 1 , 1
Global Log Level= 0
CheckData=True
Encroach Param= -1, 0, 0, 0
BEGIN DESCRIPTION:
Multiple Run
END DESCRIPTION:

--- UNT061 IN ROCK.f01 (steady flow) ---

Flow Title=Multiple
Number of Profiles=7
Profile Names=10-year,25-year,50-year,1pct_min,100-year,1pct_plu,500-year
River Rch & RM= UNT061 IN ROCK,Reach-1,4591
    1016    1406    1734    1566    2118    2864    3158
Boundary for River Rch & Prof#=UNT061 IN ROCK,Reach-1,1
Up Type=0
Dn Type=3
Dn Slope=0.005
Boundary for River Rch & Prof#=UNT061 IN ROCK,Reach-1,2
Up Type=0
Dn Type=3
Dn Slope=0.005
Boundary for River Rch & Prof#=UNT061 IN ROCK,Reach-1,3
Up Type=0
Dn Type=3
Dn Slope=0.005
Boundary for River Rch & Prof#=UNT061 IN ROCK,Reach-1,4
Up Type=0
Dn Type=3
Dn Slope=0.005
Boundary for River Rch & Prof#=UNT061 IN ROCK,Reach-1,5
Up Type=0
Dn Type=3
Dn Slope=0.005
Boundary for River Rch & Prof#=UNT061 IN ROCK,Reach-1,6
Up Type=0
Dn Type=3
Dn Slope=0.005
Boundary for River Rch & Prof#=UNT061 IN ROCK,Reach-1,7
Up Type=0
Dn Type=3
Dn Slope=0.005

--- UNT061 IN ROCK.g01 (geometry) ---

Geom Title=Existing Conditions

River Reach=UNT061 IN ROCK,Reach-1
Reach XY= 30
      3666340.11     10149699.41      3666208.54     10149714.26
      3666062.19     10149802.58      3665894.67     10150172.87
      3665926.93     10150374.36      3665747.22     10150412.69
      3665821.86     10150531.89      3666017.32     10150698.72
      3666021.86     10150817.02      3665822.33     10150773.07
      3665322.43     10150930.02      3665303.61     10150985.72
      3665396.54     10151071.69      3665392.76     10151152.05
      3665513.03     10151172.56      3665500.44     10151506.89
      3665408.20     10151592.95      3665369.69     10151357.04
      3665333.68     10151344.37      3665298.35     10151480.05
      3665234.19     10151537.36      3665238.06     10151714.00
      3665119.33     10151686.59      3665086.58     10151804.59
      3665037.33     10151839.76      3664972.03     10151752.61
      3664765.79     10151789.51      3664756.68     10151858.52
      3664898.60     10151905.40      3664912.11     10151971.64

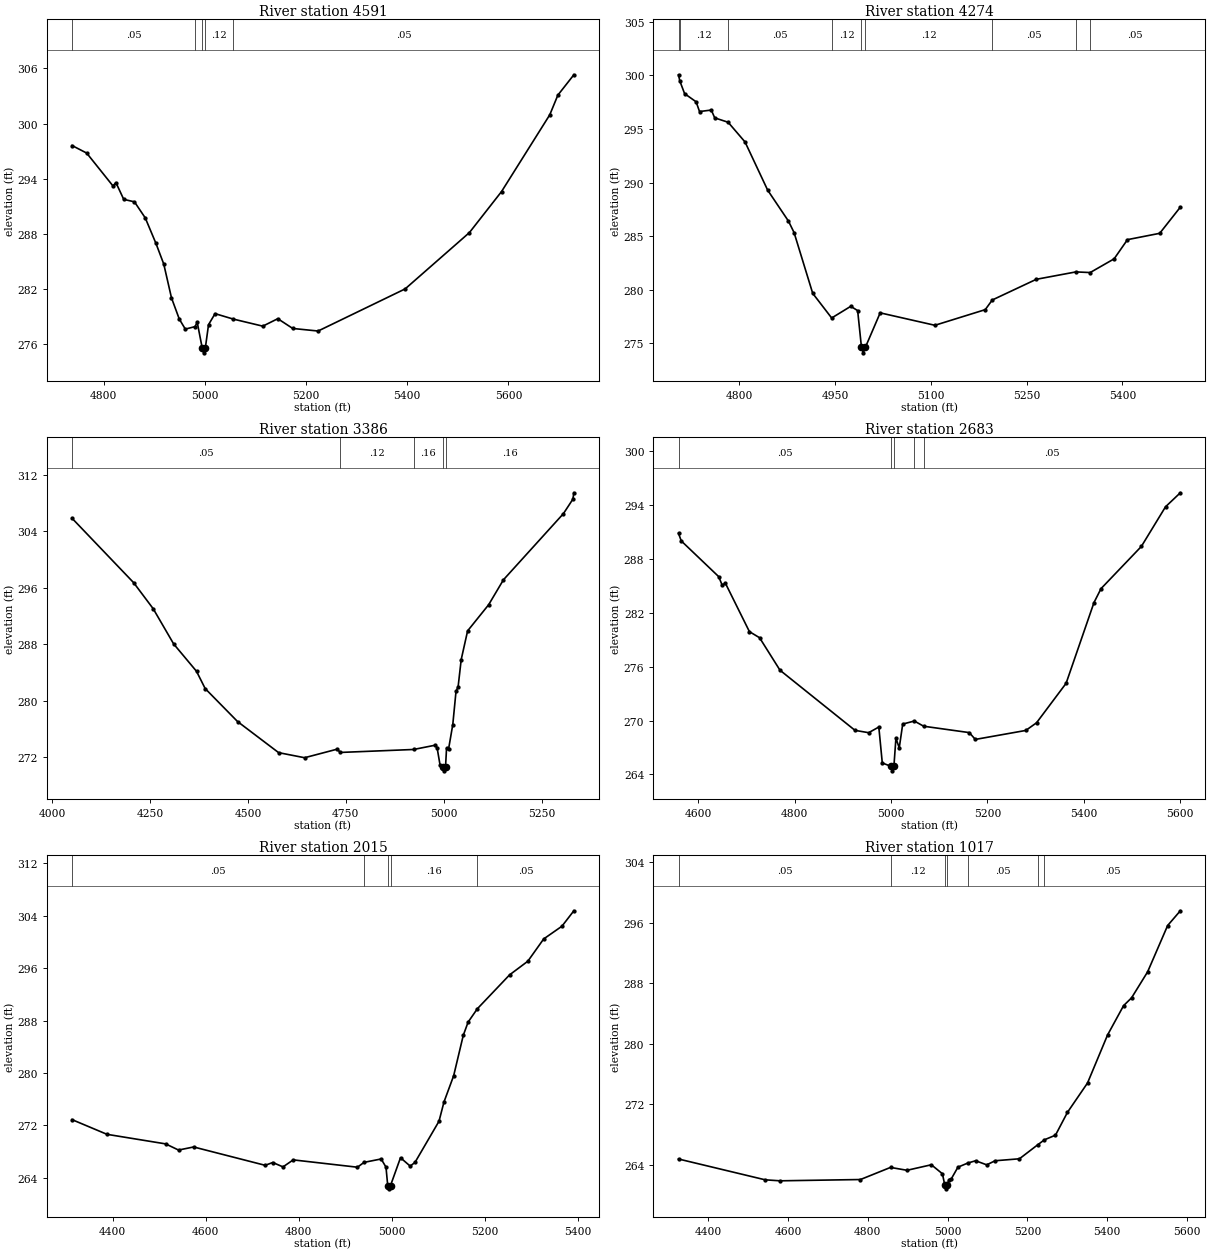
Type RM Length L Ch R = 1,4591,317,317,317
BEGIN DESCRIPTION:
UNT061 IN ROCK 7.0
END DESCRIPTION:
XS GIS Cut Line= 3
      3665792.12     10149741.65      3666144.43     10149960.86
      3666692.12     10150141.65
#Sta/Elev= 30
  4737.5  297.62  4766.4  296.80  4818.3  293.23  4824.2  293.59  4839.6  291.77
  4860.8  291.50  4882.1  289.76  4903.3  286.98  4918.7  284.74  4934.0  281.06
  4949.4  278.76  4961.3  277.67  4980.6  277.94  4984.8  278.42  4994.8  275.59
  4997.5  275.09  5000.8  275.59  5007.2  278.15  5020.1  279.35  5056.0  278.76
  5114.4  277.99  5144.1  278.80  5173.6  277.74  5223.7  277.46  5395.8  282.04
  5522.8  288.16  5586.3  292.62  5681.6  300.96  5697.6  303.10  5729.2  305.31
#Mann=5,-1,0
  4737.5    0.05       0  4980.6    0.12       0  4994.8    0.07       0
  5000.8    0.12       0  5056.0    0.05       0
Bank Sta=4994.8,5000.8
Exp/Cntr=0.3,0.1

Type RM Length L Ch R = 1,4274,888,888,888
BEGIN DESCRIPTION:
UNT061 IN ROCK 6.0
END DESCRIPTION:
XS GIS Cut Line= 3
      3665623.33     10150055.34      3665892.11     10150168.07
      3666296.21     10150453.33
#Sta/Elev= 30
  4704.5  300.05  4706.4  299.49  4714.0  298.29  4732.0  297.53  4737.4  296.62
  4755.8  296.76  4761.2  296.03  4782.2  295.62  4808.7  293.78  4844.1  289.29
  4876.7  286.40  4885.5  285.33  4914.7  279.66  4944.4  277.36  4974.3  278.45
  4985.1  278.05  4991.1  274.61  4993.9  274.11  4997.1  274.61  5020.4  277.84
  5106.1  276.68  5185.0  278.14  5196.0  279.04  5265.0  280.97  5327.0  281.66
  5349.4  281.60  5386.9  282.88  5407.8  284.67  5458.3  285.26  5490.6  287.70
#Mann=9,-1,0
  4704.5    0.05       0  4706.4    0.12       0  4782.2    0.05       0
  4944.4    0.12       0  4991.1    0.07       0  4997.1    0.12       0
  5196.0    0.05       0  5327.0    0.16       0  5349.4    0.05       0
Bank Sta=4991.1,4997.1
Exp/Cntr=0.3,0.1

Type RM Length L Ch R = 1,3386,703,703,703
BEGIN DESCRIPTION:
UNT061 IN ROCK 4.0
END DESCRIPTION:
XS GIS Cut Line= 3
      3665192.07     10150341.62      3665871.47     10150695.80
      3666348.83     10150887.80
#Sta/Elev= 30
  4051.2  305.86  4208.5  296.72  4258.3  293.03  4310.6  288.03  4368.8  284.16
  4390.9  281.71  4473.6  277.03  4578.4  272.62  4644.7  271.90  4727.5  273.11
  4736.1  272.65  4922.9  273.07  4977.4  273.67  4982.8  273.33  4990.5  270.83
  4998.3  270.54  5001.0  270.04  5004.3  270.54  5007.0  273.25  5012.3  273.18
  5022.9  276.61  5031.1  281.30  5036.5  281.97  5044.4  285.83  5060.7  289.89
  5114.4  293.60  5152.2  297.14  5305.2  306.52  5329.4  308.57  5331.9  309.48
#Mann=5,-1,0
  4051.2    0.05       0  4736.1    0.12       0  4922.9    0.16       0
  4998.3    0.07       0  5004.3    0.16       0
Bank Sta=4998.3,5004.3
Exp/Cntr=0.3,0.1

Type RM Length L Ch R = 1,2683,668,668,668
BEGIN DESCRIPTION:
UNT061 IN ROCK 3.0
END DESCRIPTION:
XS GIS Cut Line= 3
      3665122.31     10150573.55      3665506.14     10150972.13
      3665942.15     10151191.66
#Sta/Elev= 30
  4558.9  290.86  4564.5  290.02  4642.2  286.04  4649.4  285.10  4656.3  285.29
  4706.0  279.91  4727.1  279.23  4769.5  275.61  4925.2  268.91  4953.5  268.65
  4974.6  269.28  4981.8  265.28  4999.9  264.90  5002.6  264.40  5005.9  264.90
  5010.1  268.03  5017.0  266.96  5024.2  269.61  5048.3  269.95  5067.7  269.37
  5162.4  268.66  5174.9  267.90  5279.6  268.90  5301.9  269.75  5363.3  274.15
  5421.2  283.15  5435.8  284.70  5519.5  289.40  5569.7  293.82  5600.4  295.38
#Mann=5,-1,0
  4558.9    0.05       0  4999.9    0.03       0  5005.9    0.05       0
  5048.3    0.16       0  5067.7    0.05       0
Bank Sta=4999.9,5005.9
Exp/Cntr=0.3,0.1

Type RM Length L Ch R = 1,2015,998,998,998
BEGIN DESCRIPTION:
UNT061 IN ROCK 2.0
END DESCRIPTION:
XS GIS Cut Line= 3
      3664890.39     10150991.56      3665422.93     10151275.01
      3665880.98     10151403.83
#Sta/Elev= 30
  4312.5  272.88  4387.6  270.64  4513.8  269.18  4541.4  268.24  4574.0  268.71
  4727.8  265.91  4744.1  266.34  4766.1  265.67  4788.1  266.74  4926.2  265.62
  4940.4  266.36  4977.2  266.88  4987.6  265.63  4991.3  262.82  4994.0  262.32
  4997.3  262.82  5018.8  267.07  5039.6  265.79  5050.0  266.36  5101.6  272.64
  5112.3  275.58  5133.1  279.58  5153.8  285.75  5164.2  287.77  5184.1  289.81
  5253.4  294.98  5292.6  297.06  5326.7  300.46  5365.9  302.40  5391.6  304.76
#Mann=5,-1,0
  4312.5    0.05       0  4940.4    0.16       0  4991.3    0.07       0
  4997.3    0.16       0  5184.1    0.05       0
Bank Sta=4991.3,4997.3
Exp/Cntr=0.3,0.1

Type RM Length L Ch R = 1,1017,0,0,0
BEGIN DESCRIPTION:
UNT061 IN ROCK 1.0
END DESCRIPTION:
XS GIS Cut Line= 3
      3664655.60     10151346.56      3665364.97     10151709.95
      3665823.81     10151670.11
#Sta/Elev= 30
  4325.7  264.79  4543.0  262.04  4580.2  261.91  4781.6  262.08  4857.0  263.68
  4898.3  263.30  4959.3  264.03  4987.1  262.84  4992.9  261.35  4995.7  260.85
  4998.9  261.35  5003.7  262.08  5009.3  262.17  5025.9  263.71  5050.3  264.25
  5070.3  264.56  5098.1  264.02  5119.1  264.56  5180.1  264.82  5226.2  266.68
  5242.8  267.33  5270.4  267.94  5300.5  270.96  5350.7  274.83  5400.9  281.17
  5441.1  285.05  5461.1  286.08  5501.3  289.51  5551.5  295.63  5583.3  297.58
#Mann=7,-1,0
  4325.7    0.05       0  4857.0    0.12       0  4992.9    0.07       0
  4998.9    0.12       0  5050.3    0.05       0  5226.2    0.12       0
  5242.8    0.05       0
Bank Sta=4992.9,4998.9
Exp/Cntr=0.3,0.1

Chan Stop Cuts=-1