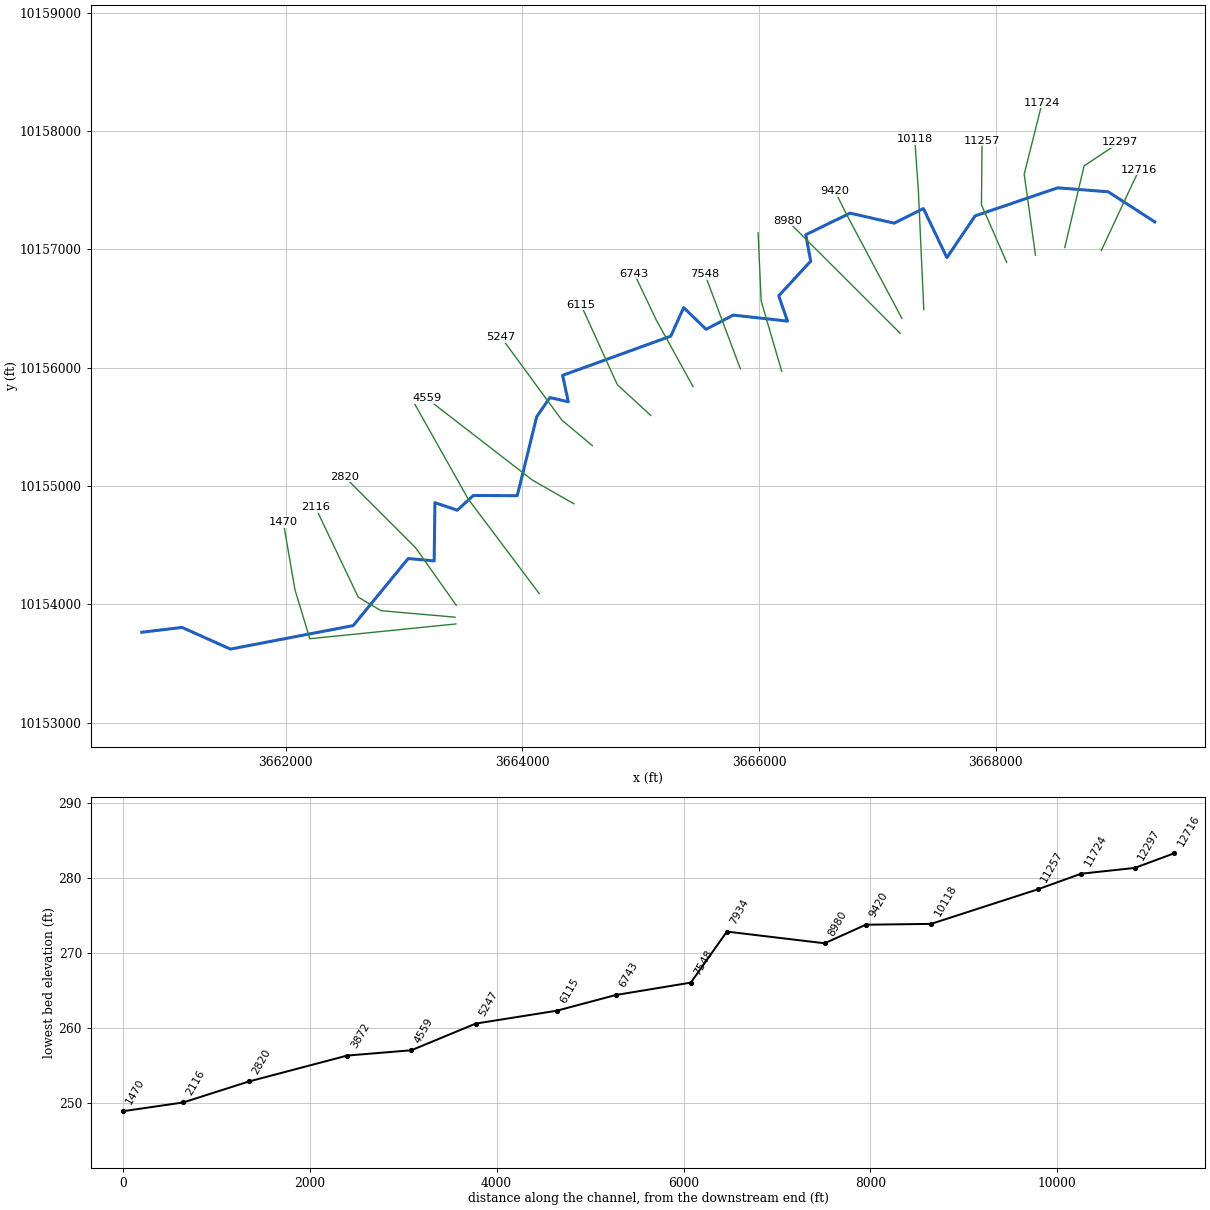
--- UNT063 IN ROCK.prj (project) ---

Proj Title=UNT063 IN ROCK Base Level Engineering
Current Plan=p01
Default Exp/Contr=0.3,0.1
English Units
Geom File=g01
Flow File=f01
Plan File=p01
Y Axis Title=Elevation
X Axis Title(PF)=Main Channel Distance
X Axis Title(XS)=Station
BEGIN DESCRIPTION:
UNT063 IN ROCK
END DESCRIPTION:
DSS Export Rating Curves= 0
DSS Export Rating Curve Sorted= 0
DSS Export Volume Flow Curves= 0
DXF OffsetX= 0
DXF OffsetY= 0
DXF ScaleX= 1
DXF ScaleY= 10

--- UNT063 IN ROCK.p01 (plan) ---

Plan Title=Multiple Run
Short Identifier=Multiple
Geom File=g01
Flow File=f01
Subcritical Flow
K Sum by GR= 0
Std Step Tol= 0.01
Critical Tol= 0.01
Num of Std Step Trials= 20
Max Error Tol= 0.3
Flow Tol Ratio= 0.001
Split Flow NTrial= 30
Split Flow Tol= 0.02
Split Flow Ratio= 0.02
Log Output Level= 0
Friction Slope Method= 1
Unsteady Friction Slope Method= 2
Unsteady Bridges Friction Slope Method= 1
Parabolic Critical Depth
Global Vel Dist=  1 , 1 , 1
Global Log Level= 0
CheckData=True
Encroach Param= -1, 0, 0, 0
BEGIN DESCRIPTION:
Multiple Run
END DESCRIPTION:

--- UNT063 IN ROCK.f01 (steady flow) ---

Flow Title=Multiple
Program Version=4.10
Number of Profiles= 7
Profile Names=10-year,25-year,50-year,1pct_min,100-year,1pct_plu,500-year
River Rch & RM=UNT063 IN ROCK,Reach-1         ,12716
    1292    1799    2226    2013    2723    3682    4075
Boundary for River Rch & Prof#=UNT063 IN ROCK,Reach-1         , 1
Up Type= 0
Dn Type= 3
Dn Slope=0.003
Boundary for River Rch & Prof#=UNT063 IN ROCK,Reach-1         , 2
Up Type= 0
Dn Type= 3
Dn Slope=0.003
Boundary for River Rch & Prof#=UNT063 IN ROCK,Reach-1         , 3
Up Type= 0
Dn Type= 3
Dn Slope=0.003
Boundary for River Rch & Prof#=UNT063 IN ROCK,Reach-1         , 4
Up Type= 0
Dn Type= 3
Dn Slope=0.003
Boundary for River Rch & Prof#=UNT063 IN ROCK,Reach-1         , 5
Up Type= 0
Dn Type= 3
Dn Slope=0.003
Boundary for River Rch & Prof#=UNT063 IN ROCK,Reach-1         , 6
Up Type= 0
Dn Type= 3
Dn Slope=0.003
Boundary for River Rch & Prof#=UNT063 IN ROCK,Reach-1         , 7
Up Type= 0
Dn Type= 3
Dn Slope=0.003
DSS Import GetInterval= 0
DSS Import GetPeak= 0
DSS Import FillOption= 0

--- UNT063 IN ROCK.g01 (geometry) ---

Geom Title=Existing Conditions
Program Version=4.10

River Reach=UNT063 IN ROCK  ,Reach-1
Reach XY= 30
      3669343.52      10157233.4      3668950.52     10157487.76
      3668522.76     10157521.23       3667825.7     10157283.96
      3667587.29     10156931.52       3667389.1     10157345.74
      3667141.52     10157222.46      3666769.25     10157307.18
      3666394.95      10157124.7      3666436.62     10156901.61
      3666166.65     10156608.21      3666240.44     10156394.67
      3665782.11     10156444.98      3665552.73     10156325.36
      3665363.24     10156509.01       3665254.7      10156267.2
      3664340.47     10155935.72      3664388.81     10155712.34
      3664233.21       10155748.      3664122.17     10155586.77
      3663957.33     10154918.43      3663586.38     10154920.12
      3663450.96     10154795.99      3663261.73     10154859.36
      3663255.65     10154367.17      3663036.03     10154387.14
      3662571.62      10153820.3       3661534.3     10153621.51
      3661125.44     10153804.67      3660785.52     10153763.93

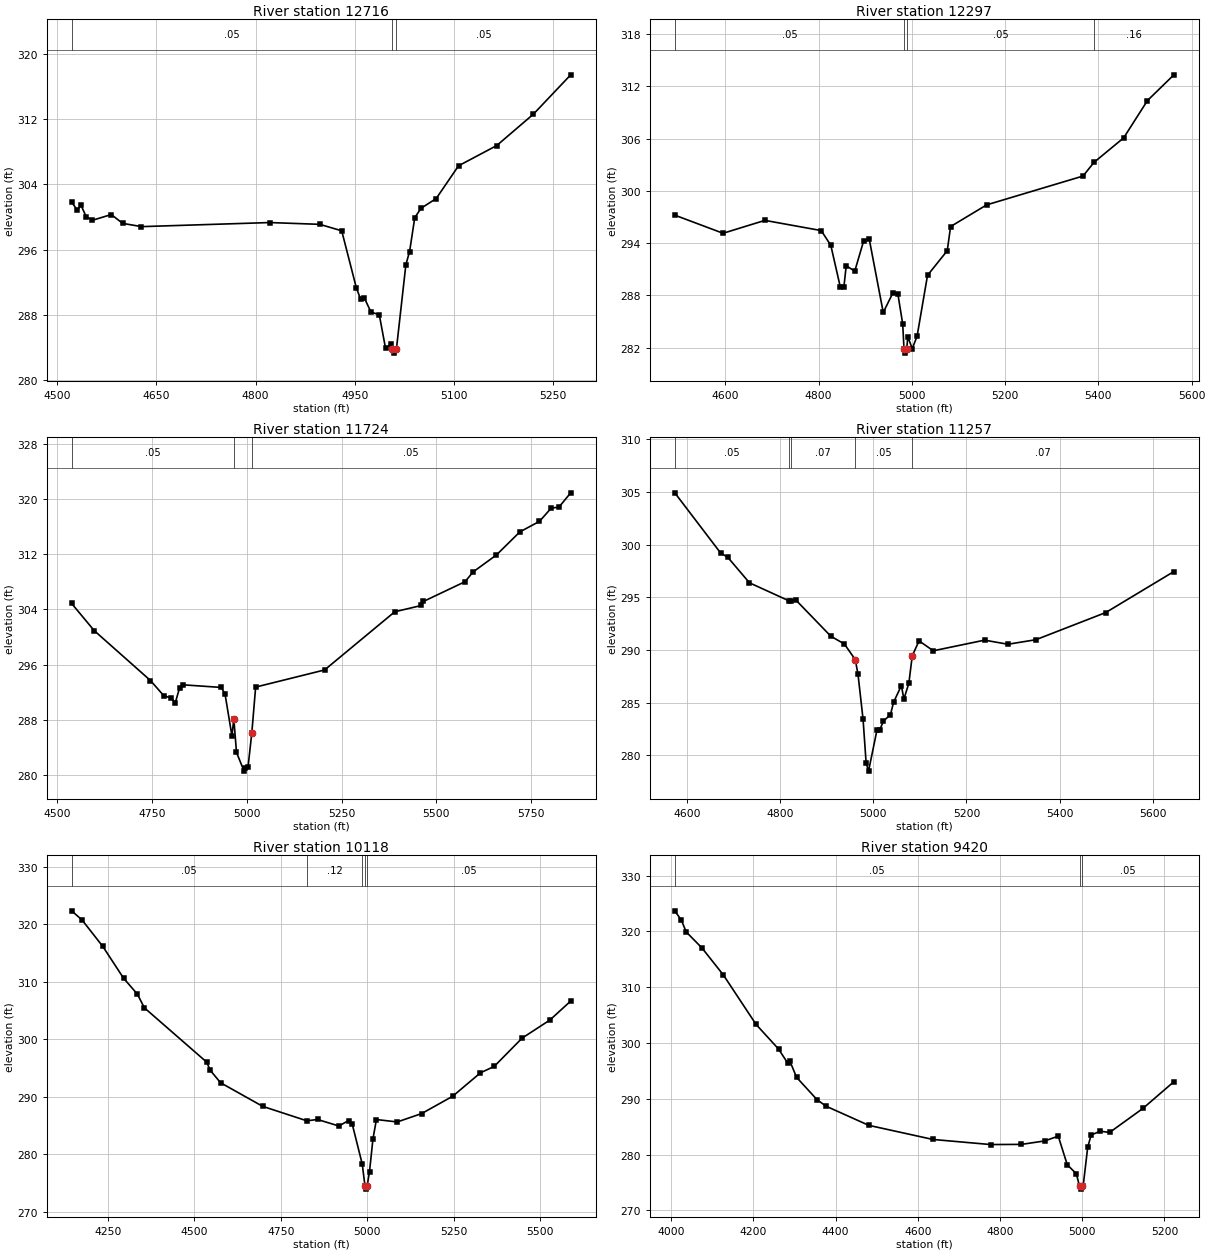
Type RM Length L Ch R = 1 ,12716   ,419,419,419
BEGIN DESCRIPTION:
UNT063 IN ROCK 22.0
END DESCRIPTION:
XS GIS Cut Line= 3
      3668892.13     10156991.68      3669163.81     10157573.93
       3669213.8     10157673.92
#Sta/Elev= 30
  4521.9  301.82  4530.5  300.82    4536  301.45  4543.9  300.02  4553.4  299.59
  4581.8  300.29  4599.1  299.21  4627.5  298.81  4821.4  299.31    4897  299.09
  4930.1   298.3  4952.2  291.32  4958.6  289.94  4964.1  290.11  4974.3  288.35
  4986.9  288.02  4996.4  283.89  5004.3  284.43  5006.8  283.82  5009.5  283.32
  5012.8  283.82  5027.1  294.17  5032.7  295.76  5040.5  299.91    5050  301.06
  5072.9  302.25  5106.7  306.26  5164.4  308.74  5219.9  312.59  5276.2   317.4
#Mann= 3 ,-1 , 0
  4521.9     .05       0  5006.8    .035       0  5012.8     .05       0
Bank Sta=5006.8,5012.8
XS Rating Curve= 0 ,0
Exp/Cntr=0.3,0.1

Type RM Length L Ch R = 1 ,12297   ,573,573,573
BEGIN DESCRIPTION:
UNT063 IN ROCK 21.0
END DESCRIPTION:
XS GIS Cut Line= 3
      3668583.22     10157016.16      3668746.45     10157706.57
      3669046.45     10157906.57
#Sta/Elev= 30
  4491.9  297.22  4595.4  295.14  4685.1  296.62  4805.8  295.45  4826.4  293.75
  4846.9  288.93  4854.3  288.92  4859.4  291.41  4877.7  290.79  4896.6  294.23
  4908.6  294.52  4938.8  286.05  4959.9  288.34  4970.2  288.16  4980.5  284.73
  4983.3  281.88    4986  281.38  4989.3  281.88  4991.4  283.27    5001   281.9
  5011.3  283.31  5033.7  290.31    5076  293.14  5083.2  295.91  5160.5   298.4
  5367.1  301.71  5390.6  303.28  5454.2  306.09  5505.3  310.38  5561.9  313.33
#Mann= 4 ,-1 , 0
  4491.9     .05       0  4983.3     .03       0  4989.3     .05       0
  5390.6     .16       0
Bank Sta=4983.3,4989.3
XS Rating Curve= 0 ,0
Exp/Cntr=0.3,0.1

Type RM Length L Ch R = 1 ,11724   ,467,467,467
BEGIN DESCRIPTION:
UNT063 IN ROCK 20.0
END DESCRIPTION:
XS GIS Cut Line= 3
      3668335.82     10156951.06      3668240.34      10157636.8
      3668392.09     10158241.59
#Sta/Elev= 30
  4538.3  304.87  4597.9  300.94  4746.2  293.72  4781.2  291.53  4801.4  291.17
  4811.5  290.47  4822.8  292.63  4831.7   293.1  4932.7  292.72  4942.7  291.79
    4961  285.71    4966  288.18    4973  283.32    4993  280.61  4996.2  281.11
  5003.3  281.14  5013.4  286.15  5023.5  292.77  5205.3  295.25  5390.3  303.67
  5460.6  304.58  5465.8  305.16  5575.9  308.03  5596.5  309.42  5658.4  311.89
  5720.2  315.23  5771.8  316.75  5802.7  318.66  5823.3  318.82  5854.2  320.88
#Mann= 3 , 0 , 0
  4538.3     .05       0    4966    .035       0  5013.4     .05       0
Bank Sta=4966,5013.4
XS Rating Curve= 0 ,0
Exp/Cntr=0.3,0.1

Type RM Length L Ch R = 1 ,11257   ,1139,1139,1139
BEGIN DESCRIPTION:
UNT063 IN ROCK 19.0
END DESCRIPTION:
XS GIS Cut Line= 3
      3668092.12     10156891.61      3667879.28     10157377.83
      3667884.42     10157917.74
#Sta/Elev= 30
  4574.3  304.92  4672.6  299.21  4687.8  298.81  4734.5  296.38  4818.8  294.68
  4823.5   294.7  4833.5  294.77  4909.1  291.31    4938  290.58  4961.4   289.1
  4967.3  287.71  4978.2  283.43  4984.7  279.32  4989.9  278.51  5008.1  282.42
  5013.6  282.39  5021.9  283.25    5037  283.88  5043.7  285.05  5060.4  286.63
  5065.8  285.34  5076.5  286.87  5083.7  289.45  5098.3  290.87  5128.9  289.93
  5238.9  290.94  5288.9  290.55  5348.9  290.98  5498.9  293.56    5645  297.45
#Mann= 5 ,-1 , 0
  4574.3     .05       0  4818.8     .12       0  4823.5     .07       0
  4961.4     .05       0  5083.7     .07       0
Bank Sta=4961.4,5083.7
XS Rating Curve= 0 ,0
Exp/Cntr=0.3,0.1

Type RM Length L Ch R = 1 ,10118   ,698,698,698
BEGIN DESCRIPTION:
UNT063 IN ROCK 17.0
END DESCRIPTION:
XS GIS Cut Line= 3
      3667392.11     10156491.64      3667346.24     10157497.91
      3667315.86     10157931.93
#Sta/Elev= 30
  4145.1   322.3  4175.1  320.72  4235.2  316.11  4295.3  310.58  4335.3   307.8
  4355.3  305.44  4535.5  295.99  4545.5  294.59  4575.5  292.41  4697.4   288.3
  4824.9  285.79  4855.8  286.02  4917.3  284.89  4945.9  285.84  4955.9  285.26
  4985.1  278.24    4993  274.41  4995.7  273.91    4999  274.41    5006  276.94
    5016  282.65    5026  286.01  5086.1  285.59  5156.8  287.05  5246.4  290.06
  5326.6  294.13  5366.7  295.26  5446.9  300.16  5527.1   303.3  5587.5  306.61
#Mann= 5 ,-1 , 0
  4145.1     .05       0  4824.9     .12       0  4985.1     .05       0
    4993     .03       0    4999     .05       0
Bank Sta=4993,4999
XS Rating Curve= 0 ,0
Exp/Cntr=0.3,0.1

Type RM Length L Ch R = 1 ,9420    ,440,440,440
BEGIN DESCRIPTION:
UNT063 IN ROCK 16.0
END DESCRIPTION:
XS GIS Cut Line= 3
      3667207.35     10156417.18      3666742.11     10157291.64
      3666642.12     10157491.61
#Sta/Elev= 30
    4009  323.68  4025.3  321.95  4036.7   319.9  4074.9  317.04  4127.3  312.17
  4206.7  303.32  4261.3  298.92  4283.3  296.43  4288.9  296.75  4305.2  293.84
  4354.9  289.84  4376.8  288.67    4481  285.23  4637.1   282.7  4777.3  281.79
  4852.3  281.82  4909.1  282.44  4941.8   283.3  4963.7  278.17  4985.7  276.56
  4993.7   274.3  4996.4   273.8  4999.7   274.3  5002.3   274.3  5013.5  281.33
  5021.9   283.5  5044.2  284.19  5066.6  283.95  5147.7  288.26  5223.1  293.05
#Mann= 3 ,-1 , 0
    4009     .05       0  4993.7     .03       0  4999.7     .05       0
Bank Sta=4993.7,4999.7
XS Rating Curve= 0 ,0
Exp/Cntr=0.3,0.1

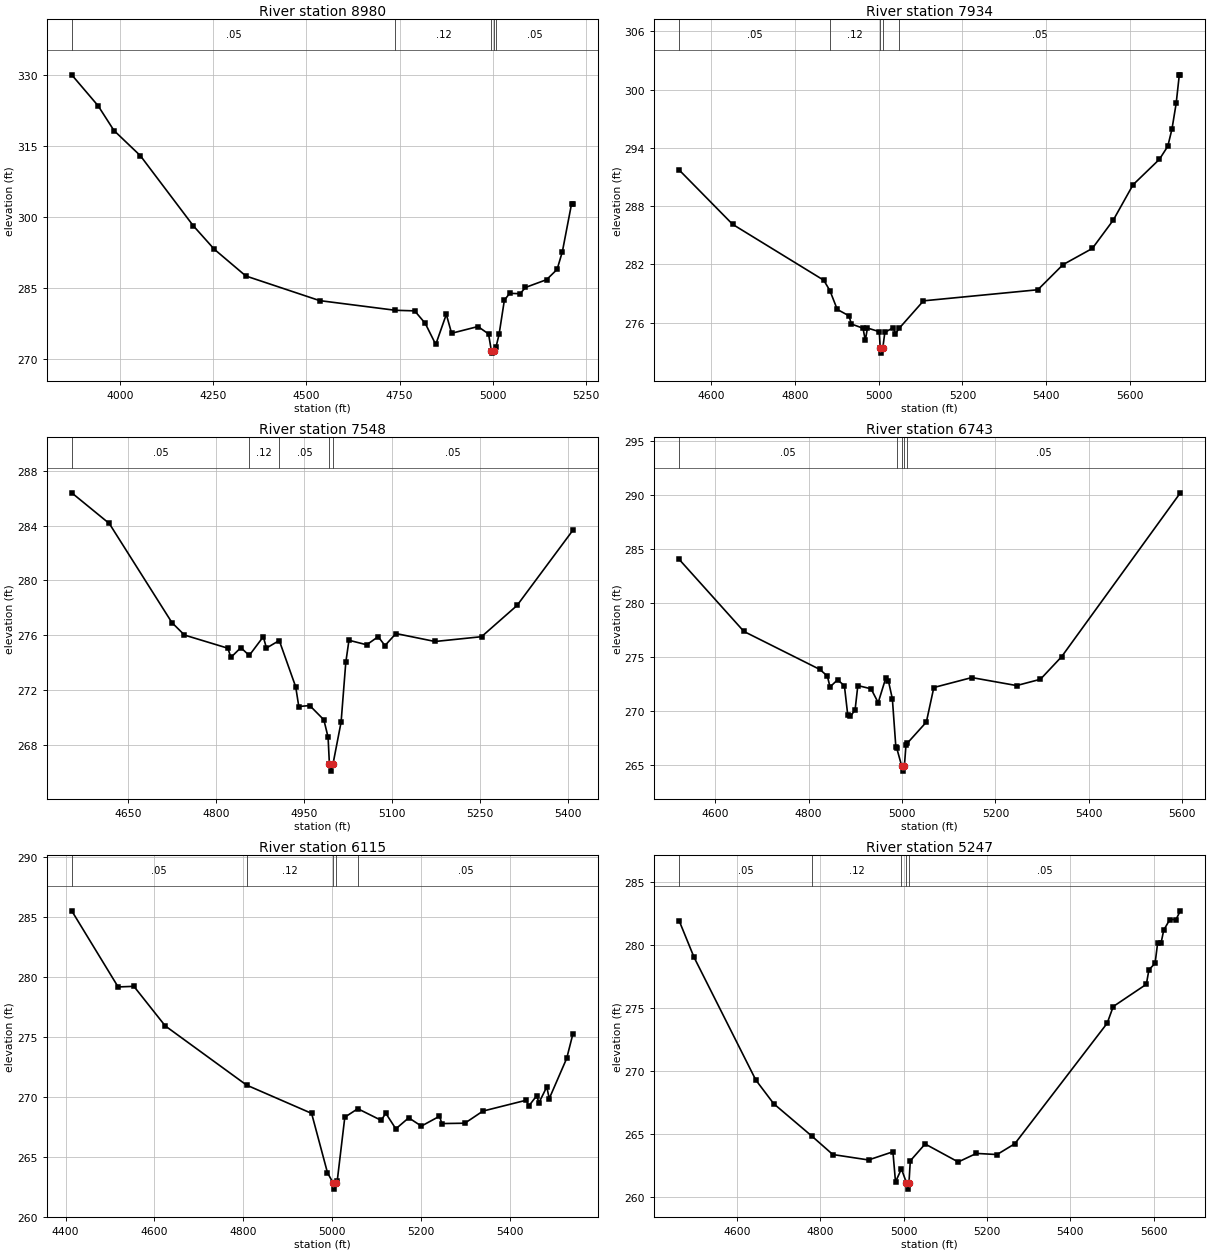
Type RM Length L Ch R = 1 ,8980    ,1046,1046,1046
BEGIN DESCRIPTION:
UNT063 IN ROCK 15.0
END DESCRIPTION:
XS GIS Cut Line= 3
      3667192.13     10156291.62      3666392.11     10157091.64
      3666242.13     10157241.62
#Sta/Elev= 30
  3870.9  330.05  3941.6  323.52  3984.1   318.3  4054.8  312.99  4196.2  298.25
  4252.8  293.26  4337.6   287.6  4535.6   282.4  4738.5  280.36  4790.2  280.24
  4818.5   277.6  4846.7  273.15    4875   279.5  4889.2  275.51  4959.9  276.93
  4988.2  275.37  4995.8  271.82  4998.5  271.32  5001.8  271.82    5008  272.53
  5016.4  275.26  5030.6  282.47  5044.7  283.94    5073  283.86  5087.2  285.18
  5143.7  286.82    5172  288.99  5186.1  292.73  5210.9  302.89  5214.4  302.89
#Mann= 5 ,-1 , 0
  3870.9     .05       0  4738.5     .12       0  4995.8     .07       0
  5001.8     .12       0    5008     .05       0
Bank Sta=4995.8,5001.8
XS Rating Curve= 0 ,0
Exp/Cntr=0.3,0.1

Type RM Length L Ch R = 1 ,7934    ,386,386,386
BEGIN DESCRIPTION:
UNT063 IN ROCK 13.0
END DESCRIPTION:
XS GIS Cut Line= 3
      3666191.72     10155970.14      3666018.11     10156564.75
      3665992.11     10157141.62
#Sta/Elev= 30
  4523.6  291.72  4651.3  286.13  4868.9  280.38  4883.6  279.31  4901.1  277.38
  4929.4  276.71  4934.6  275.88  4962.7  275.44  4968.1  274.19  4973.3  275.46
  5001.5  275.09  5003.8  273.38  5006.5  272.88  5009.8  273.38  5014.8  275.02
    5035   275.5  5040.2  274.88  5049.2  275.44  5107.1  278.26  5380.2   279.4
  5440.2  281.98  5510.3  283.65  5560.4  286.57  5607.5   290.2  5670.5  292.82
  5690.5  294.16  5700.5  295.94  5710.5  298.57    5718  301.51  5720.5  301.51
#Mann= 5 ,-1 , 0
  4523.6     .05       0  4883.6     .12       0  5003.8     .07       0
  5009.8     .12       0  5049.2     .05       0
Bank Sta=5003.8,5009.8
XS Rating Curve= 0 ,0
Exp/Cntr=0.3,0.1

Type RM Length L Ch R = 1 ,7548    ,805,805,805
BEGIN DESCRIPTION:
UNT063 IN ROCK 12.0
END DESCRIPTION:
XS GIS Cut Line= 3
      3665842.09     10155991.67      3665692.11     10156391.64
      3665542.09     10156791.67
#Sta/Elev= 30
  4553.8   286.4  4617.8  284.16  4724.6  276.92    4746  276.01  4819.9  275.05
  4825.2  274.38  4842.1  275.09  4856.4  274.52  4880.4  275.89  4885.7  275.06
  4907.6  275.61  4935.6  272.23  4940.9  270.79  4959.6  270.86  4983.6  269.82
  4990.8  268.55  4993.1  266.57  4995.8  266.07  4999.1  266.57    5013  269.65
    5021  274.01  5026.4  275.63  5056.6   275.3  5076.2  275.89  5087.8  275.24
  5106.5  276.12  5173.2  275.54  5252.4  275.89  5312.9  278.17  5408.2  283.67
#Mann= 5 ,-1 , 0
  4553.8     .05       0  4856.4     .12       0  4907.6     .05       0
  4993.1     .03       0  4999.1     .05       0
Bank Sta=4993.1,4999.1
XS Rating Curve= 0 ,0
Exp/Cntr=0.3,0.1

Type RM Length L Ch R = 1 ,6743    ,628,628,628
BEGIN DESCRIPTION:
UNT063 IN ROCK 10.0
END DESCRIPTION:
XS GIS Cut Line= 3
      3665442.11     10155841.63      3665131.04     10156405.75
      3664946.57     10156793.73
#Sta/Elev= 30
  4522.5  284.01  4661.2  277.34    4824  273.82    4840  273.21  4845.7   272.2
  4861.8  272.86  4876.5  272.32  4883.6  269.64  4889.3  269.48  4899.4  270.07
  4905.3  272.33  4933.6  272.03  4948.9  270.75    4965     273  4970.7  272.79
  4979.3   271.1  4986.7  266.67  4988.6  266.55  4999.1  264.91  5001.9  264.41
  5005.1  264.91  5008.5  266.86  5011.6  267.01  5052.1  268.95  5068.1  272.15
  5149.5  273.07  5245.5  272.33  5296.4  272.91  5341.9     275  5596.3  290.17
#Mann= 5 ,-1 , 0
  4522.5     .05       0  4988.6     .12       0  4999.1     .07       0
  5005.1     .12       0  5011.6     .05       0
Bank Sta=4999.1,5005.1
XS Rating Curve= 0 ,0
Exp/Cntr=0.3,0.1

Type RM Length L Ch R = 1 ,6115    ,868,868,868
BEGIN DESCRIPTION:
UNT063 IN ROCK 9.0
END DESCRIPTION:
XS GIS Cut Line= 3
      3665084.93     10155596.89      3664802.84     10155857.29
      3664494.68     10156534.36
#Sta/Elev= 30
    4414  285.54  4518.4  279.19  4553.9  279.24  4624.4  275.94  4807.5     271
  4953.8  268.64  4989.5  263.69  5002.4  262.82  5005.2  262.32  5008.4  262.82
  5011.4  262.99  5028.5  268.32  5057.7  269.03  5110.3  268.06  5120.7  268.65
  5143.3  267.35  5172.3  268.27  5200.8  267.58  5241.5   268.4    5247  267.79
  5298.6  267.82  5339.2  268.83  5436.9  269.74  5442.4  269.25    5460   270.1
  5465.5  269.54    5483  270.85  5488.5  269.87  5527.8  273.23  5541.8  275.28
#Mann= 5 ,-1 , 0
    4414     .05       0  4807.5     .12       0  5002.4     .07       0
  5008.4     .12       0  5057.7     .05       0
Bank Sta=5002.4,5008.4
XS Rating Curve= 0 ,0
Exp/Cntr=0.3,0.1

Type RM Length L Ch R = 1 ,5247    ,688,688,688
BEGIN DESCRIPTION:
UNT063 IN ROCK 7.0
END DESCRIPTION:
XS GIS Cut Line= 3
      3664592.09     10155341.66      3664333.74     10155557.93
      3663821.93      10156256.6
#Sta/Elev= 30
  4461.1  281.94  4496.9  279.03  4645.2  269.27  4688.1  267.39  4779.8  264.81
  4829.9  263.35  4915.6  262.92  4974.2  263.57  4980.4  261.17  4994.6  262.21
  5006.7   261.1  5009.5   260.6  5012.7   261.1  5015.9  262.85  5051.5  264.19
  5130.9  262.76  5174.5  263.44  5224.1  263.35  5266.8  264.21  5488.4  273.79
    5503  275.12  5582.5  276.89  5588.7  278.05  5603.4  278.55  5609.6  280.18
    5618   280.2  5624.2   281.2  5638.9  282.04  5653.6  282.04  5664.1  282.73
#Mann= 5 ,-1 , 0
  4461.1     .05       0  4779.8     .12       0  4994.6     .05       0
  5006.7     .03       0  5012.7     .05       0
Bank Sta=5006.7,5012.7
XS Rating Curve= 0 ,0
Exp/Cntr=0.3,0.1

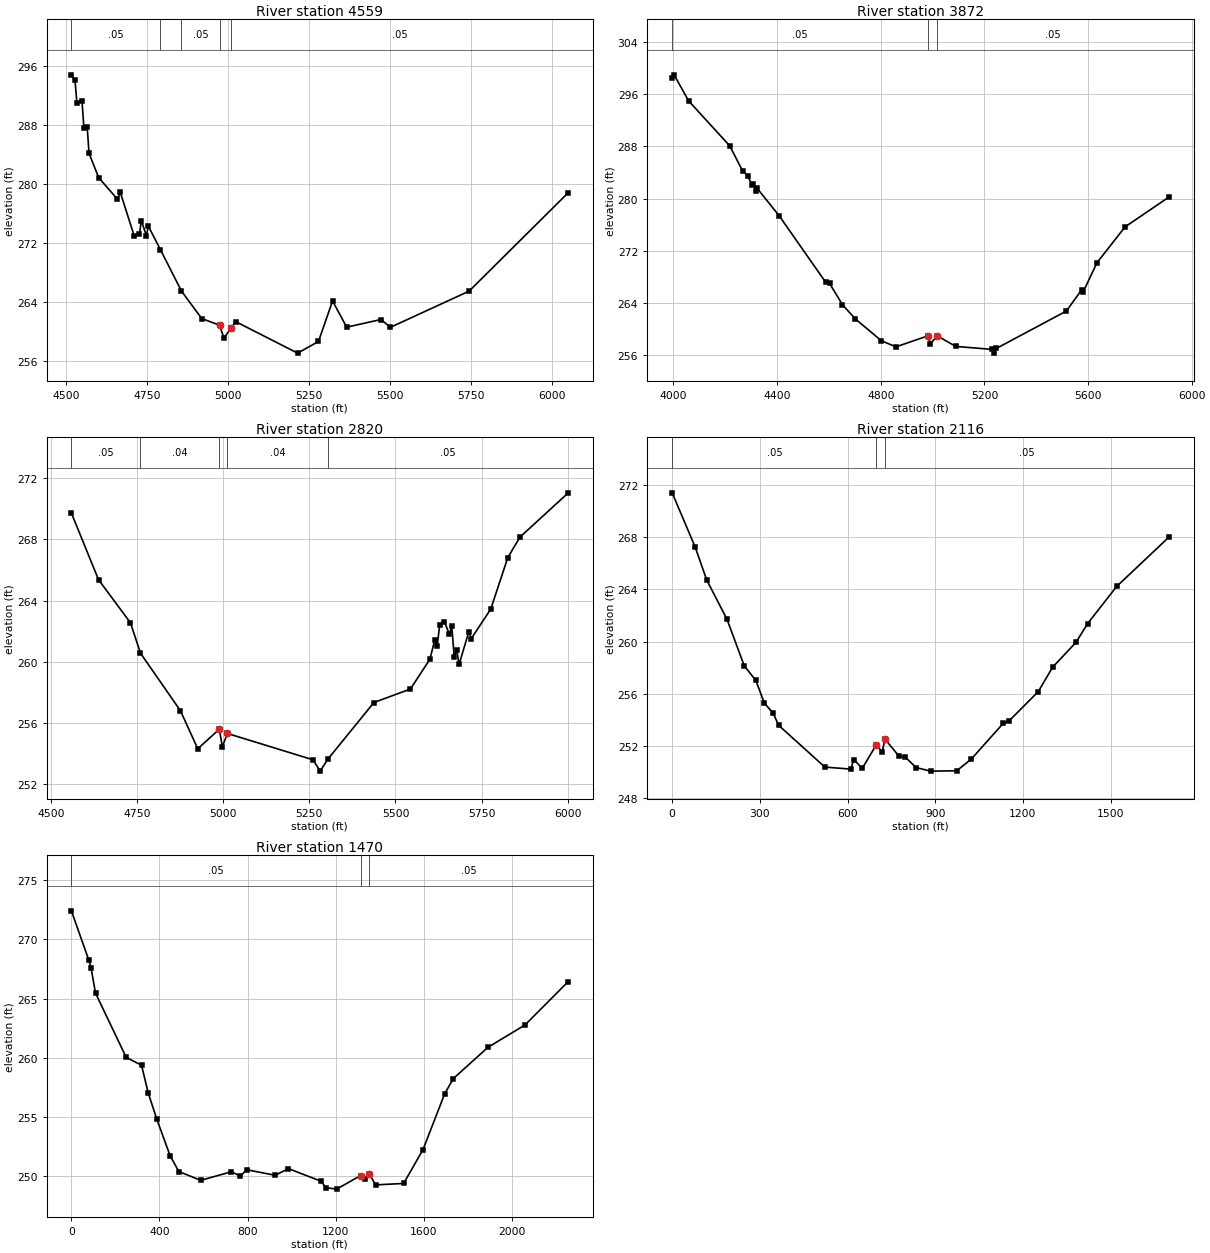
Type RM Length L Ch R = 1 ,4559    ,687,687,687
BEGIN DESCRIPTION:
UNT063 IN ROCK 5.0
END DESCRIPTION:
XS GIS Cut Line= 3
      3664435.29     10154850.17      3664085.33     10155050.15
      3663192.09     10155741.66
#Sta/Elev= 30
  4517.1  294.79  4528.3  294.03  4534.1  290.94  4549.9  291.25  4555.7   287.6
  4565.8  287.77  4571.5  284.14  4601.4  280.84    4659  277.93    4668  278.85
  4711.2  272.89    4727  273.17  4732.8  275.02  4748.6  272.96  4754.4  274.27
  4791.8  271.07  4856.6  265.46  4919.1  261.73  4974.1  260.83  4987.5  259.09
  5009.5  260.41  5023.9  261.31  5214.9  257.04  5279.2  258.62  5322.7  264.12
  5366.2  260.56  5472.1   261.6  5501.1  260.54  5743.8  265.45  6049.8  278.81
#Mann= 5 ,-1 , 0
  4517.1     .05       0  4791.8     .12       0  4856.6     .05       0
  4974.1    .035       0  5009.5     .05       0
Bank Sta=4974.1,5009.5
XS Rating Curve= 0 ,0
Exp/Cntr=0.3,0.1

Type RM Length L Ch R = 1 ,3872    ,1052,1052,1052
BEGIN DESCRIPTION:
UNT063 IN ROCK 4.0
END DESCRIPTION:
XS GIS Cut Line= 3
      3664142.11     10154091.63      3663542.11     10154891.64
       3663092.1     10155691.65
#Sta/Elev= 30
    3995  298.48  4002.3  298.97  4058.6  294.97  4216.9   288.1  4266.9  284.24
  4287.7  283.44  4302.3  282.12  4308.6  282.31  4316.9   281.2  4323.1  281.58
  4408.6  277.34  4587.7  267.17  4602.3  267.02  4652.3  263.74  4702.3  261.56
  4802.3  258.23  4858.6  257.29  4981.5  258.97  4991.9  257.79    5018  258.97
  5089.7  257.36  5229.9   256.9  5235.7  256.33  5245.8  257.04  5516.1  262.77
  5575.4  266.02  5581.1  265.69  5634.7  270.19    5743  275.67  5912.9  280.26
#Mann= 3 ,-1 , 0
    3995     .05       0  4981.5    .035       0    5018     .05       0
Bank Sta=4981.5,5018
XS Rating Curve= 0 ,0
Exp/Cntr=0.3,0.1

Type RM Length L Ch R = 1 ,2820    ,704,704,704
BEGIN DESCRIPTION:
UNT063 IN ROCK 2.0
END DESCRIPTION:
XS GIS Cut Line= 3
      3663442.13     10153991.61      3663098.53     10154478.45
      3662499.45     10155077.52
#Sta/Elev= 30
  4558.9  269.72  4637.7  265.37  4730.3  262.56  4759.6  260.57  4875.4  256.82
  4925.9  254.33  4988.6  255.61  4997.3  254.45  5011.8  255.33  5260.6  253.61
  5281.5  252.87    5303  253.63  5437.4  257.35  5543.4  258.23    5600  260.17
  5614.1  261.43  5621.2  261.03  5628.3  262.38  5642.4  262.62  5656.6  261.81
  5663.6  262.32  5670.7  260.32  5677.8  260.81  5684.8  259.84  5713.1  261.97
  5720.2  261.52  5776.8  263.45  5826.3  266.81  5861.6  268.15    6002  271.04
#Mann= 5 ,-1 , 0
  4558.9     .05       0  4759.6     .04       0  4988.6    .035       0
  5011.8     .04       0    5303     .05       0
Bank Sta=4988.6,5011.8
XS Rating Curve= 0 ,0
Exp/Cntr=0.3,0.1

Type RM Length L Ch R = 1 ,2116    ,646,646,646
XS GIS Cut Line= 4
      3663431.49    10153891.449      3662806.49    10153946.137
     3662613.781     10154060.72     3662251.802    10154821.137
#Sta/Elev= 30
       0271.4065  78.896267.2355 118.344264.7127 187.378261.7201  246.55258.1446
 285.998257.0272 315.584255.2811  345.17254.5198 364.894253.5674 522.686250.3738
 611.444250.2214 621.306250.9501650.5665250.2782699.0626252.1053718.4611251.5175
728.1603252.5242776.6564 251.198796.0549251.1721834.8518250.3395884.1184250.0655
973.7228250.09041023.503250.9868 1133.02253.73421152.932253.91911252.492256.1562
1302.272258.04381381.921  259.941421.745261.38181521.305264.23221700.514 268.021
#Mann= 3 , 0 , 0
       0     .05       0699.0626    .035       0728.1603     .05       0
Bank Sta=699.0626,728.1603
XS Rating Curve= 0 ,0
Exp/Cntr=0.3,0.1

Type RM Length L Ch R = 1 ,1470    ,0,0,0
XS GIS Cut Line= 4
     3663439.302    10153834.158     3662204.927    10153709.158
     3662079.927    10154120.616     3661980.969    10154693.533
#Sta/Elev= 30
       0272.406379.65276268.213589.60936267.5503109.5225 265.461248.9149260.0271
318.6111 259.363348.4808257.0512388.3072254.7835448.0468251.7371487.8732250.3827
587.4391249.6407726.8315250.3663766.6578249.9999796.5276250.5353925.9634250.0661
985.7029250.63041135.052249.55761154.965249.02221204.748248.89781313.126250.0379
1332.712249.78131352.299   250.21381.678249.25761508.989249.37581597.127252.2401
 1695.18256.94151734.597258.23551892.265260.88112059.787262.75712256.872266.4354
#Mann= 3 , 0 , 0
       0     .05       01313.126    .035       01352.299     .05       0
Bank Sta=1313.126,1352.299
XS Rating Curve= 0 ,0
Exp/Cntr=0.3,0.1

Chan Stop Cuts=-1
Use User Specified Reach Order=0
Composite Channel Slope=5