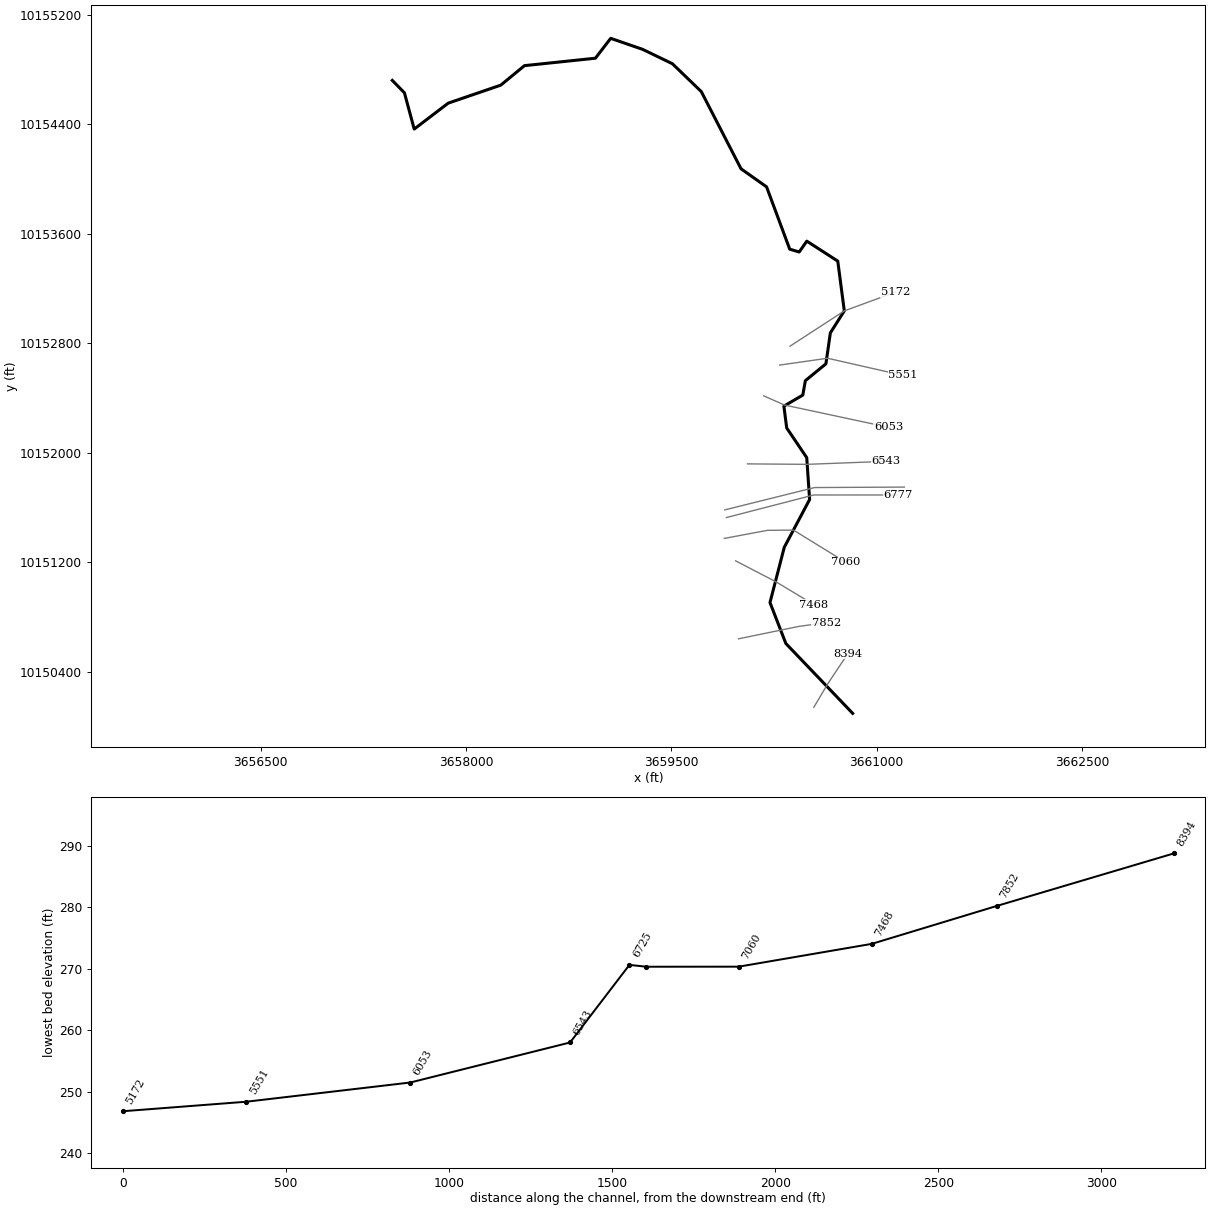
--- UNT064 IN ROCK.prj (project) ---

Proj Title=UNT064 IN ROCK Base Level Engineering
Current Plan=p01
Default Exp/Contr=0.3,0.1
English Units
Geom File=g01
Flow File=f01
Plan File=p01
BEGIN DESCRIPTION:
UNT064 IN ROCK
END DESCRIPTION:

--- UNT064 IN ROCK.p01 (plan) ---

Plan Title=Multiple Run
Short Identifier=Multiple
Geom File=g01
Flow File=f01
Subcritical Flow
K Sum by GR= 0
Std Step Tol= 0.01
Critical Tol= 0.01
Num of Std Step Trials= 20
Max Error Tol= 0.3
Flow Tol Ratio= 0.001
Split Flow NTrial= 30
Split Flow Tol= 0.02
Split Flow Ratio= 0.02
Log Output Level= 0
Friction Slope Method= 1
Unsteady Friction Slope Method= 2
Unsteady Bridges Friction Slope Method= 1
Parabolic Critical Depth
Global Vel Dist=  1 , 1 , 1
Global Log Level= 0
CheckData=True
Encroach Param= -1, 0, 0, 0
BEGIN DESCRIPTION:
Multiple Run
END DESCRIPTION:

--- UNT064 IN ROCK.f01 (steady flow) ---

Flow Title=Multiple
Number of Profiles=7
Profile Names=10-year,25-year,50-year,1pct_min,100-year,1pct_plu,500-year
River Rch & RM= UNT064 IN ROCK,Reach-1,8394
     497     660     792     698     944    1277    1341
Boundary for River Rch & Prof#=UNT064 IN ROCK,Reach-1,1
Up Type=0
Dn Type=3
Dn Slope=0.005
Boundary for River Rch & Prof#=UNT064 IN ROCK,Reach-1,2
Up Type=0
Dn Type=3
Dn Slope=0.005
Boundary for River Rch & Prof#=UNT064 IN ROCK,Reach-1,3
Up Type=0
Dn Type=3
Dn Slope=0.005
Boundary for River Rch & Prof#=UNT064 IN ROCK,Reach-1,4
Up Type=0
Dn Type=3
Dn Slope=0.005
Boundary for River Rch & Prof#=UNT064 IN ROCK,Reach-1,5
Up Type=0
Dn Type=3
Dn Slope=0.005
Boundary for River Rch & Prof#=UNT064 IN ROCK,Reach-1,6
Up Type=0
Dn Type=3
Dn Slope=0.005
Boundary for River Rch & Prof#=UNT064 IN ROCK,Reach-1,7
Up Type=0
Dn Type=3
Dn Slope=0.005

--- UNT064 IN ROCK.g01 (geometry) ---

Geom Title=Existing Conditions

River Reach=UNT064 IN ROCK,Reach-1
Reach XY= 30
      3660825.86     10150096.83      3660337.55     10150607.52
      3660221.67     10150906.62      3660325.91     10151310.06
      3660511.22     10151659.38      3660490.09     10151965.47
      3660343.72     10152182.27      3660323.21     10152341.53
      3660461.34     10152422.40      3660480.06     10152527.84
      3660630.15     10152650.69      3660662.69     10152876.83
      3660764.68     10153037.64      3660716.84     10153401.33
      3660490.59     10153547.34      3660435.12     10153467.85
      3660365.79     10153488.61      3660196.53     10153944.08
      3660010.20     10154075.56      3659719.63     10154640.01
      3659508.53     10154843.48      3659290.74     10154948.64
      3659057.66     10155029.04      3658946.10     10154883.84
      3658427.66     10154829.43      3658254.65     10154687.03
      3657870.56     10154555.48      3657622.09     10154366.05
      3657550.65     10154631.13      3657462.11     10154721.64

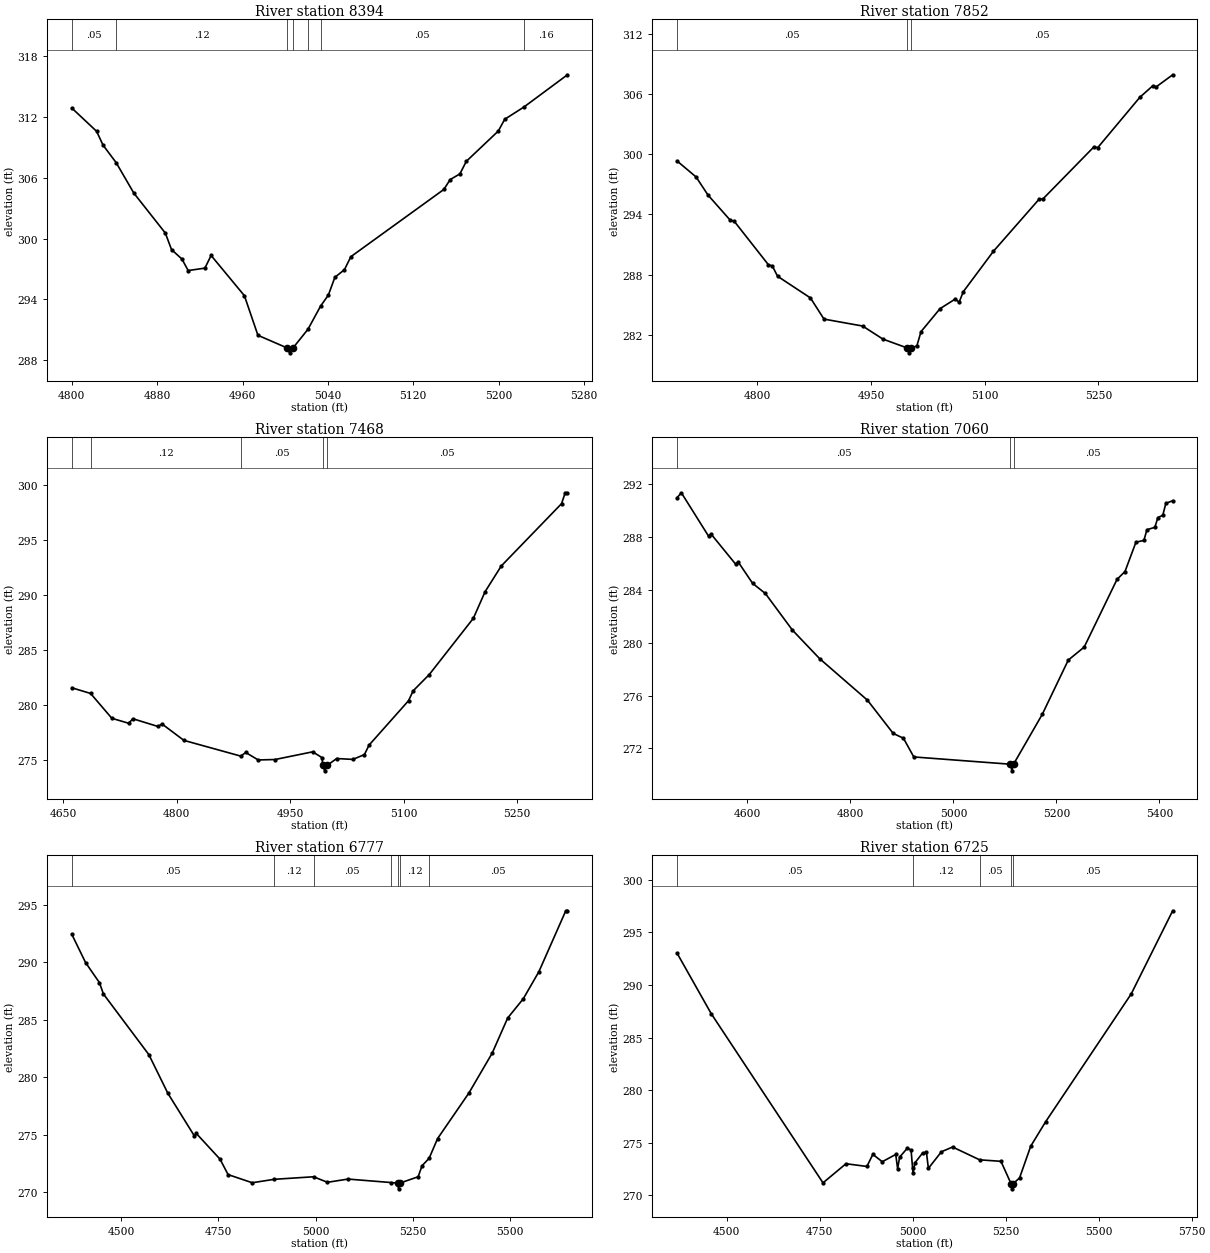
Type RM Length L Ch R = 1,8394,542,542,542
BEGIN DESCRIPTION:
UNT064 IN ROCK 8.0
END DESCRIPTION:
XS GIS Cut Line= 3
      3660542.09     10150141.62      3660644.46     10150314.10
      3660790.85     10150533.83
#Sta/Elev= 30
  4799.9  312.89  4823.2  310.59  4829.2  309.23  4841.5  307.50  4858.1  304.49
  4887.6  300.55  4893.4  298.92  4903.2  297.98  4909.0  296.85  4924.7  297.09
  4930.5  298.34  4961.7  294.37  4974.4  290.46  5001.4  289.23  5004.1  288.73
  5007.4  289.23  5021.3  291.06  5033.1  293.34  5040.4  294.43  5046.5  296.18
  5055.5  296.94  5061.5  298.22  5148.6  304.85  5154.6  305.83  5163.7  306.39
  5169.7  307.63  5199.7  310.62  5205.7  311.78  5223.6  312.98  5264.5  316.17
#Mann=7,-1,0
  4799.9    0.05       0  4841.5    0.12       0  5001.4    0.07       0
  5007.4    0.12       0  5021.3    0.16       0  5033.1    0.05       0
  5223.6    0.16       0
Bank Sta=5001.4,5007.4
Exp/Cntr=0.3,0.1

Type RM Length L Ch R = 1,7852,384,384,384
BEGIN DESCRIPTION:
UNT064 IN ROCK 7.0
END DESCRIPTION:
XS GIS Cut Line= 3
      3659992.09     10150641.64      3660433.65     10150732.53
      3660635.07     10150760.01
#Sta/Elev= 30
  4694.0  299.32  4719.2  297.72  4734.9  295.92  4764.4  293.40  4769.5  293.31
  4814.7  288.97  4819.8  288.86  4826.7  287.83  4870.1  285.67  4888.0  283.56
  4939.0  282.87  4965.7  281.57  4997.3  280.70  5000.1  280.20  5003.3  280.70
  5010.5  280.88  5016.0  282.31  5041.1  284.60  5061.2  285.56  5066.3  285.24
  5071.8  286.29  5111.6  290.32  5171.9  295.51  5176.9  295.53  5244.2  300.72
  5249.2  300.64  5304.7  305.65  5321.5  306.78  5326.6  306.71  5348.1  307.90
#Mann=3,-1,0
  4694.0    0.05       0  4997.3    0.03       0  5003.3    0.05       0
Bank Sta=4997.3,5003.3
Exp/Cntr=0.3,0.1

Type RM Length L Ch R = 1,7468,408,408,408
BEGIN DESCRIPTION:
UNT064 IN ROCK 6.0
END DESCRIPTION:
XS GIS Cut Line= 3
      3659970.47     10151211.29      3660261.05     10151060.58
      3660542.14     10150891.62
#Sta/Elev= 30
  4661.4  281.58  4686.3  281.06  4714.4  278.80  4736.6  278.35  4742.2  278.76
  4775.2  278.06  4780.8  278.28  4809.7  276.79  4884.8  275.36  4891.4  275.69
  4907.9  275.01  4930.1  275.05  4979.9  275.75  4992.3  275.22  4993.1  274.52
  4995.8  274.02  4999.1  274.52  5011.6  275.14  5033.0  275.06  5048.3  275.50
  5054.4  276.36  5106.6  280.40  5112.7  281.30  5134.0  282.78  5192.3  287.90
  5207.9  290.33  5229.2  292.66  5308.9  298.33  5313.7  299.32  5316.7  299.32
#Mann=5,-1,0
  4661.4    0.05       0  4686.3    0.12       0  4884.8    0.05       0
  4993.1    0.03       0  4999.1    0.05       0
Bank Sta=4993.1,4999.1
Exp/Cntr=0.3,0.1

Type RM Length L Ch R = 1,7060,283,283,283
BEGIN DESCRIPTION:
UNT064 IN ROCK 5.0
END DESCRIPTION:
XS GIS Cut Line= 4
      3659887.78     10151375.26      3660203.75     10151434.29
      3660392.99     10151436.03      3660777.79     10151199.24
#Sta/Elev= 30
  4463.1  290.94  4471.6  291.32  4524.3  288.05  4529.3  288.20  4576.9  285.93
  4582.0  286.09  4609.9  284.48  4634.7  283.71  4687.3  280.94  4740.0  278.79
  4832.9  275.65  4882.9  273.14  4902.9  272.77  4922.9  271.36  5110.6  270.81
  5113.4  270.31  5116.6  270.81  5172.4  274.58  5222.9  278.68  5253.8  279.66
  5317.6  284.78  5333.0  285.37  5354.3  287.59  5369.7  287.72  5375.6  288.53
  5391.0  288.71  5396.9  289.45  5406.4  289.62  5412.3  290.52  5425.6  290.72
#Mann=3,-1,0
  4463.1    0.05       0  5110.6    0.03       0  5116.6    0.05       0
Bank Sta=5110.6,5116.6
Exp/Cntr=0.3,0.1

Type RM Length L Ch R = 1,6777,52,52,52
BEGIN DESCRIPTION:
Mapping XS aa3696a6
END DESCRIPTION:
XS GIS Cut Line= 3
      3659903.37     10151527.60      3660541.43     10151692.54
      3661155.60     10151692.54
#Sta/Elev= 30
  4373.7  292.46  4409.2  289.99  4444.7  288.25  4455.0  287.26  4571.7  281.98
  4620.3  278.63  4688.5  274.91  4693.6  275.12  4754.6  272.88  4775.2  271.54
  4837.2  270.83  4893.8  271.13  4994.7  271.35  5030.5  270.87  5083.4  271.15
  5192.9  270.85  5210.4  270.80  5213.2  270.30  5216.4  270.80  5263.4  271.35
  5273.4  272.31  5291.6  272.96  5313.4  274.68  5393.4  278.62  5453.4  282.10
  5493.4  285.17  5533.4  286.84  5573.4  289.19  5642.6  294.50  5646.9  294.50
#Mann=7,-1,0
  4373.7    0.05       0  4893.8    0.12       0  4994.7    0.05       0
  5192.9    0.12       0  5210.4    0.03       0  5216.4    0.12       0
  5291.6    0.05       0
Bank Sta=5210.4,5216.4
Exp/Cntr=0.3,0.1

Type RM Length L Ch R = 1,6725,182,182,182
BEGIN DESCRIPTION:
Mapping XS aa6fab16
END DESCRIPTION:
XS GIS Cut Line= 3
      3659891.21     10151583.58      3660547.50     10151746.79
      3661203.71     10151750.26
#Sta/Elev= 30
  4366.5  293.04  4458.5  287.27  4759.0  271.17  4820.8  272.99  4877.0  272.73
  4893.0  273.88  4918.3  273.18  4954.5  273.87  4959.6  272.53  4965.1  273.62
  4985.7  274.47  4995.8  274.29  4999.7  272.62  5000.9  272.11  5006.3  273.08
  5026.9  274.02  5037.1  274.06  5042.3  272.55  5077.4  274.13  5107.4  274.58
  5180.1  273.36  5237.4  273.22  5264.4  271.10  5267.1  270.60  5270.4  271.10
  5287.4  271.64  5317.4  274.66  5357.4  276.98  5587.4  289.14  5699.0  297.06
#Mann=5,-1,0
  4366.5    0.05       0  4999.7    0.12       0  5180.1    0.05       0
  5264.4    0.07       0  5270.4    0.05       0
Bank Sta=5264.4,5270.4
Exp/Cntr=0.3,0.1

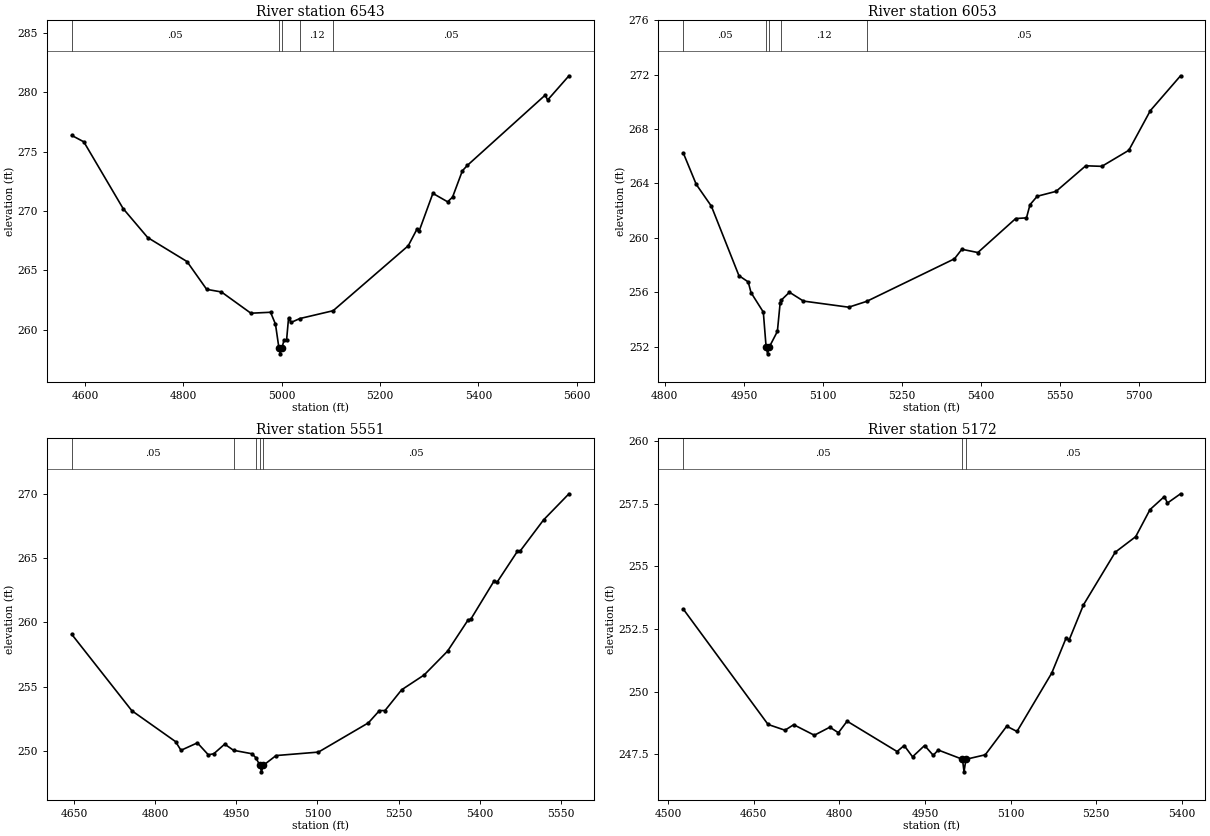
Type RM Length L Ch R = 1,6543,490,490,490
BEGIN DESCRIPTION:
UNT064 IN ROCK 4.0
END DESCRIPTION:
XS GIS Cut Line= 3
      3660057.47     10151919.78      3660492.11     10151916.34
      3661068.84     10151938.36
#Sta/Elev= 30
  4572.6  276.37  4597.2  275.83  4677.2  270.21  4727.2  267.77  4807.2  265.75
  4847.2  263.41  4877.2  263.19  4937.2  261.40  4977.2  261.48  4987.2  260.48
  4994.2  258.48  4997.0  257.98  5000.2  258.48  5004.7  259.13  5009.8  259.13
  5013.8  260.99  5018.8  260.62  5036.7  260.95  5104.5  261.61  5257.4  267.08
  5274.9  268.46  5279.9  268.36  5307.5  271.49  5337.5  270.78  5347.5  271.17
  5367.5  273.39  5377.5  273.84  5536.0  279.76  5541.0  279.35  5584.4  281.39
#Mann=5,-1,0
  4572.6    0.05       0  4994.2    0.03       0  5000.2    0.05       0
  5036.7    0.12       0  5104.5    0.05       0
Bank Sta=4994.2,5000.2
Exp/Cntr=0.3,0.1

Type RM Length L Ch R = 1,6053,502,502,502
BEGIN DESCRIPTION:
UNT064 IN ROCK 3.0
END DESCRIPTION:
XS GIS Cut Line= 3
      3660175.55     10152416.99      3660326.95     10152349.93
      3661088.18     10152187.24
#Sta/Elev= 30
  4835.0  266.24  4859.6  263.93  4888.3  262.33  4940.6  257.22  4958.2  256.76
  4963.6  255.97  4986.9  254.54  4992.2  251.97  4995.0  251.47  4998.2  251.97
  5013.6  253.12  5018.8  255.20  5021.2  255.43  5036.5  256.00  5063.1  255.35
  5149.0  254.90  5183.2  255.33  5349.8  258.46  5363.8  259.16  5394.2  258.92
  5466.0  261.42  5486.5  261.47  5493.2  262.44  5506.9  263.06  5542.7  263.42
  5599.0  265.30  5629.6  265.26  5680.8  266.44  5721.7  269.36  5779.0  271.92
#Mann=5,-1,0
  4835.0    0.05       0  4992.2    0.03       0  4998.2    0.05       0
  5021.2    0.12       0  5183.2    0.05       0
Bank Sta=4992.2,4998.2
Exp/Cntr=0.3,0.1

Type RM Length L Ch R = 1,5551,379,379,379
BEGIN DESCRIPTION:
UNT064 IN ROCK 2.0
END DESCRIPTION:
XS GIS Cut Line= 3
      3660292.11     10152641.64      3660642.11     10152691.64
      3661193.72     10152566.39
#Sta/Elev= 30
  4645.8  259.08  4756.9  253.12  4837.7  250.71  4847.8  250.03  4878.1  250.61
  4898.3  249.68  4908.4  249.76  4928.6  250.51  4944.9  250.03  4979.1  249.76
  4986.0  249.46  4993.8  248.85  4996.6  248.35  4999.8  248.85  5023.5  249.62
  5101.9  249.89  5194.2  252.17  5214.7  253.13  5224.9  253.13  5255.7  254.75
  5297.4  255.91  5340.5  257.76  5378.4  260.19  5383.6  260.26  5426.6  263.24
  5431.8  263.12  5469.7  265.55  5474.9  265.58  5518.0  268.00  5565.0  270.04
#Mann=5,-1,0
  4645.8    0.05       0  4944.9    0.12       0  4986.0    0.05       0
  4993.8    0.03       0  4999.8    0.05       0
Bank Sta=4993.8,4999.8
Exp/Cntr=0.3,0.1

Type RM Length L Ch R = 1,5172,0,0,0
BEGIN DESCRIPTION:
UNT064 IN ROCK 1.0
END DESCRIPTION:
XS GIS Cut Line= 3
      3660367.59     10152779.54      3660764.68     10153037.64
      3661137.96     10153174.86
#Sta/Elev= 30
  4526.4  253.29  4674.9  248.69  4704.6  248.46  4719.8  248.68  4756.0  248.26
  4783.1  248.58  4798.2  248.36  4813.4  248.82  4901.0  247.61  4913.4  247.85
  4928.1  247.40  4949.2  247.85  4964.3  247.46  4973.1  247.67  5015.6  247.30
  5018.3  246.80  5021.6  247.30  5055.5  247.48  5093.1  248.62  5111.1  248.41
  5172.0  250.74  5197.2  252.14  5202.5  252.06  5227.6  253.46  5283.3  255.56
  5319.1  256.18  5344.2  257.26  5369.4  257.78  5374.7  257.52  5397.7  257.89
#Mann=3,-1,0
  4526.4    0.05       0  5015.6    0.03       0  5021.6    0.05       0
Bank Sta=5015.6,5021.6
Exp/Cntr=0.3,0.1

Chan Stop Cuts=-1