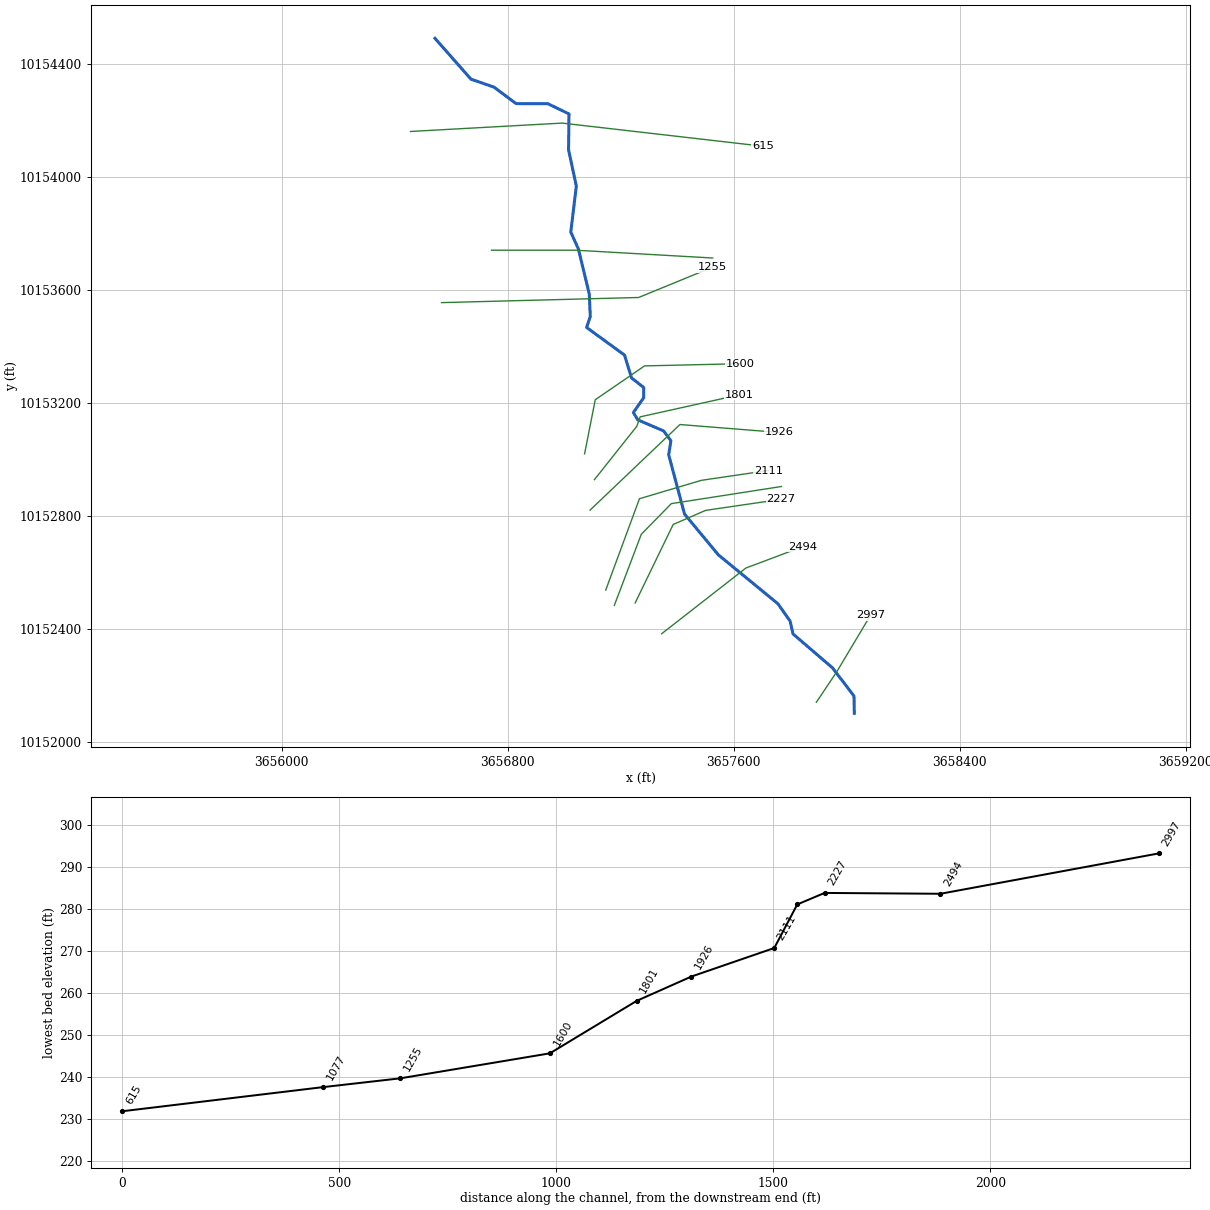
--- UNT065 IN ROCK.prj (project) ---

Proj Title=UNT065 IN ROCK Base Level Engineering
Current Plan=p01
Default Exp/Contr=0.3,0.1
English Units
Geom File=g01
Flow File=f01
Plan File=p01
Y Axis Title=Elevation
X Axis Title(PF)=Main Channel Distance
X Axis Title(XS)=Station
BEGIN DESCRIPTION:
UNT065 IN ROCK
END DESCRIPTION:
DSS Export Rating Curves= 0
DSS Export Rating Curve Sorted= 0
DSS Export Volume Flow Curves= 0
DXF OffsetX= 0
DXF OffsetY= 0
DXF ScaleX= 1
DXF ScaleY= 10

--- UNT065 IN ROCK.p01 (plan) ---

Plan Title=Multiple Run
Short Identifier=Multiple
Geom File=g01
Flow File=f01
Subcritical Flow
K Sum by GR= 0
Std Step Tol= 0.01
Critical Tol= 0.01
Num of Std Step Trials= 20
Max Error Tol= 0.3
Flow Tol Ratio= 0.001
Split Flow NTrial= 30
Split Flow Tol= 0.02
Split Flow Ratio= 0.02
Log Output Level= 0
Friction Slope Method= 1
Unsteady Friction Slope Method= 2
Unsteady Bridges Friction Slope Method= 1
Parabolic Critical Depth
Global Vel Dist=  1 , 1 , 1
Global Log Level= 0
CheckData=True
Encroach Param= -1, 0, 0, 0
BEGIN DESCRIPTION:
Multiple Run
END DESCRIPTION:

--- UNT065 IN ROCK.f01 (steady flow) ---

Flow Title=Multiple
Program Version=4.10
Number of Profiles= 7
Profile Names=10-year,25-year,50-year,1pct_min,100-year,1pct_plu,500-year
River Rch & RM=UNT065 IN ROCK,Reach-1         ,2997
     107     129     145     121     163     221     207
River Rch & RM=UNT065 IN ROCK,Reach-1         ,1255
     342     450     537     472     639     864     901
Boundary for River Rch & Prof#=UNT065 IN ROCK,Reach-1         , 1
Up Type= 0
Dn Type= 3
Dn Slope=0.005
Boundary for River Rch & Prof#=UNT065 IN ROCK,Reach-1         , 2
Up Type= 0
Dn Type= 3
Dn Slope=0.005
Boundary for River Rch & Prof#=UNT065 IN ROCK,Reach-1         , 3
Up Type= 0
Dn Type= 3
Dn Slope=0.005
Boundary for River Rch & Prof#=UNT065 IN ROCK,Reach-1         , 4
Up Type= 0
Dn Type= 3
Dn Slope=0.005
Boundary for River Rch & Prof#=UNT065 IN ROCK,Reach-1         , 5
Up Type= 0
Dn Type= 3
Dn Slope=0.005
Boundary for River Rch & Prof#=UNT065 IN ROCK,Reach-1         , 6
Up Type= 0
Dn Type= 3
Dn Slope=0.005
Boundary for River Rch & Prof#=UNT065 IN ROCK,Reach-1         , 7
Up Type= 0
Dn Type= 3
Dn Slope=0.005
DSS Import GetInterval= 0
DSS Import GetPeak= 0
DSS Import FillOption= 0

--- UNT065 IN ROCK.g01 (geometry) ---

Geom Title=Existing Conditions
Program Version=4.10

River Reach=UNT065 IN ROCK  ,Reach-1
Reach XY= 30
      3658026.47     10152102.24      3658025.16     10152163.61
       3657949.2     10152263.44      3657809.43     10152383.43
      3657799.01     10152429.01      3657756.04     10152490.21
      3657545.11     10152663.38      3657425.31     10152807.91
      3657369.32     10153017.55      3657377.14     10153067.03
      3657351.09     10153102.18      3657259.95     10153141.25
      3657244.32     10153167.29      3657280.78     10153219.37
      3657280.78     10153255.83      3657237.81     10153289.69
      3657213.07     10153370.41      3657078.68     10153468.32
      3657091.83     10153506.92      3657088.22     10153586.68
      3657049.85     10153745.73      3657022.78     10153805.66
      3657042.41     10153968.63      3657014.88     10154097.17
      3657016.57     10154224.01      3656941.59     10154260.35
      3656829.39      10154260.5      3656751.04     10154318.92
      3656669.36     10154347.19      3656542.11     10154491.64

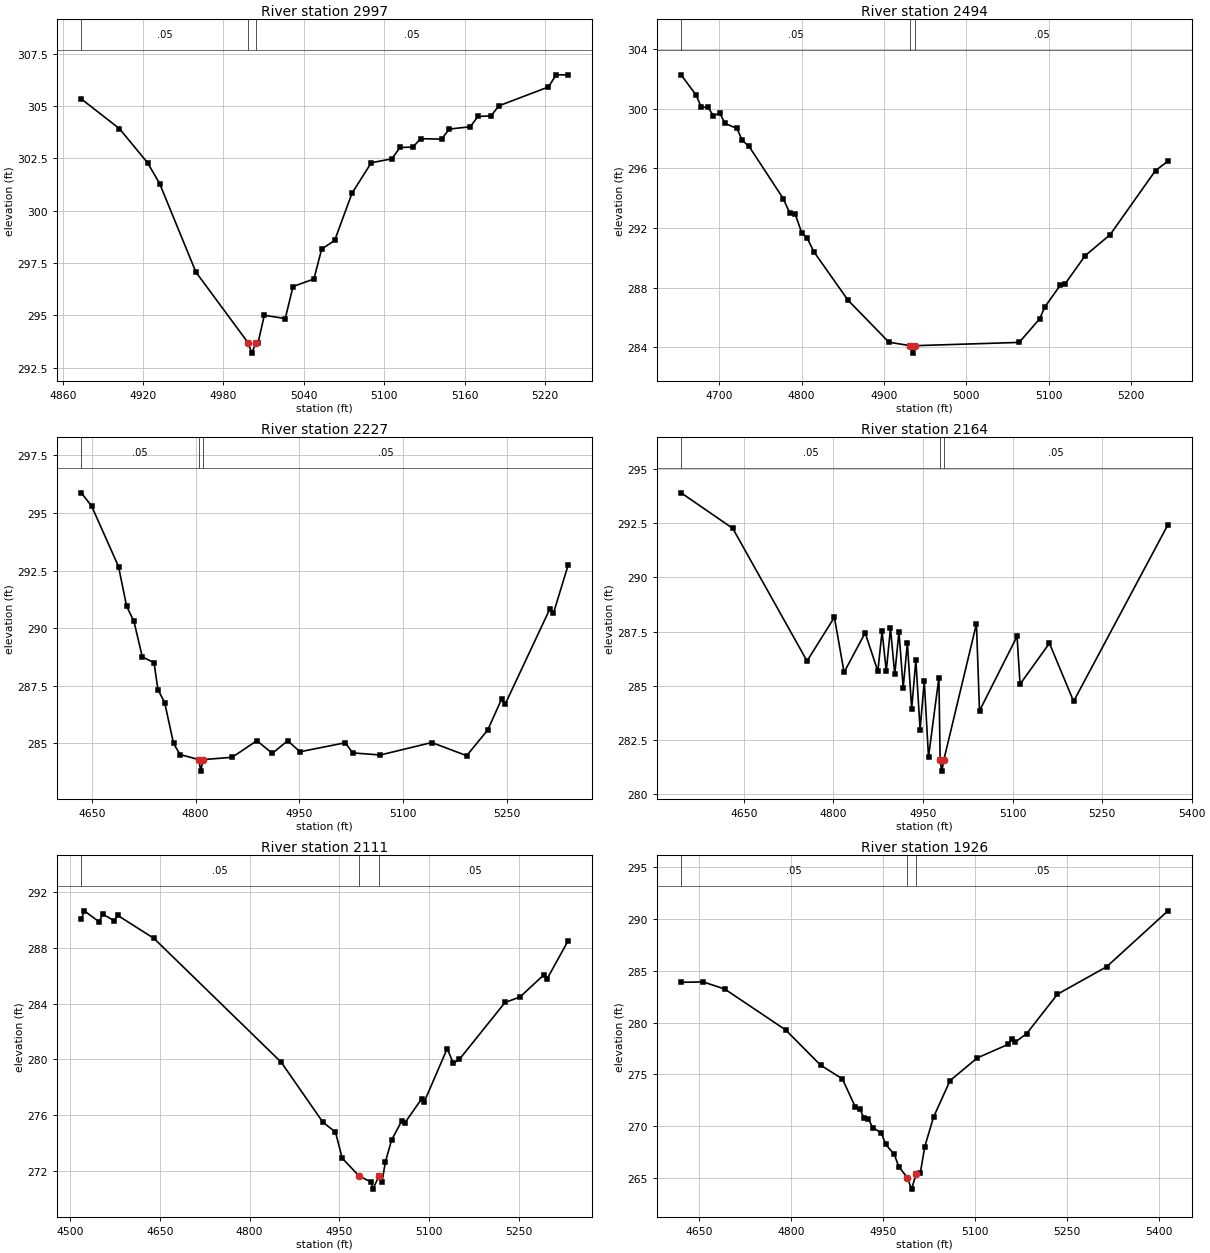
Type RM Length L Ch R = 1 ,2997    ,503,503,503
BEGIN DESCRIPTION:
UNT065 IN ROCK 6.0
END DESCRIPTION:
XS GIS Cut Line= 3
      3657892.11     10152141.65      3657963.73     10152248.63
      3658084.12     10152450.17
#Sta/Elev= 30
  4873.8  305.34  4902.3  303.92  4923.3  302.29  4932.3   301.3  4959.4  297.07
  4998.3   293.7  5001.1   293.2  5004.3   293.7  5005.8   293.7  5010.5  295.01
  5026.1  294.85  5031.9  296.38  5047.5  296.74  5053.3  298.17    5063  298.58
  5075.9  300.83  5090.3  302.29  5105.8  302.48  5111.7  303.02  5121.4  303.04
  5127.2  303.44  5142.8  303.42  5148.6   303.9  5164.2  304.01    5170   304.5
  5179.8  304.53  5185.6  305.01  5222.6  305.91  5228.4  306.49  5237.3  306.49
#Mann= 3 ,-1 , 0
  4873.8     .05       0  4998.3     .03       0  5004.3     .05       0
Bank Sta=4998.3,5004.3
XS Rating Curve= 0 ,0
Exp/Cntr=0.3,0.1

Type RM Length L Ch R = 1 ,2494    ,267,267,267
BEGIN DESCRIPTION:
UNT065 IN ROCK 5.0
END DESCRIPTION:
XS GIS Cut Line= 3
       3657344.5     10152384.16      3657642.55     10152616.68
      3657842.11     10152691.64
#Sta/Elev= 30
  4653.6  302.27  4671.7  300.92  4678.1   300.1  4686.2  300.09  4692.6  299.54
  4700.7  299.68    4707  299.01  4721.5  298.67  4727.8  297.87    4736  297.48
  4777.6  293.97  4785.7  292.97  4792.1  292.93  4800.2  291.66  4806.5  291.34
  4814.7  290.41  4856.3  287.15    4906  284.33    4932   284.1  4934.7   283.6
    4938   284.1  5064.2  284.32  5089.1  285.91  5095.2  286.69    5114  288.15
  5119.4  288.21  5144.3  290.14  5174.5  291.54  5229.7  295.85  5244.8  296.48
#Mann= 3 ,-1 , 0
  4653.6     .05       0    4932     .03       0    4938     .05       0
Bank Sta=4932,4938
XS Rating Curve= 0 ,0
Exp/Cntr=0.3,0.1

Type RM Length L Ch R = 1 ,2227    ,63,63,63
BEGIN DESCRIPTION:
Mapping XS 6570bd24
END DESCRIPTION:
XS GIS Cut Line= 4
      3657250.67      10152493.1      3657385.23      10152770.9
      3657500.25     10152820.81      3657767.16     10152859.87
#Sta/Elev= 30
  4634.6  295.87  4649.5   295.3  4688.5  292.67  4700.2  290.95  4710.8  290.29
  4722.8  288.76  4739.8   288.5  4745.4  287.34  4755.2  286.77    4768     285
  4777.4  284.52  4804.6   284.3  4807.3   283.8  4810.6   284.3  4852.7   284.4
  4888.5  285.12  4910.8  284.57    4933  285.12  4950.8  284.64  5016.2  285.03
  5027.1  284.59  5066.9   284.5  5141.3  285.04  5191.8  284.47  5222.1  285.58
  5242.2  286.92  5247.2  286.69  5312.1  290.84  5317.1  290.64  5338.4  292.73
#Mann= 3 ,-1 , 0
  4634.6     .05       0  4804.6     .03       0  4810.6     .05       0
Bank Sta=4804.6,4810.6
XS Rating Curve= 0 ,0
Exp/Cntr=0.3,0.1

Type RM Length L Ch R = 1 ,2164    ,53,53,53
BEGIN DESCRIPTION:
Mapping XS db8d6785
END DESCRIPTION:
XS GIS Cut Line= 4
      3657176.91     10152484.48      3657272.38     10152736.17
      3657378.72     10152844.68      3657768.21     10152905.27
#Sta/Elev= 30
    4545   293.9  4631.5  292.26  4755.9  286.14  4801.7  288.16  4817.9  285.62
  4853.2  287.44  4874.5  285.67  4881.5  287.51  4888.6  285.68  4895.6  287.65
  4902.8  285.52  4909.8   287.5  4916.9  284.91  4923.9  286.97  4931.1  283.93
  4938.1  286.18  4945.2  282.98  4952.2  285.21  4959.3  281.71  4976.7  285.37
  4978.8  281.56  4981.6  281.06  4984.8  281.56  5039.6  287.86  5044.7  283.84
  5107.6  287.28  5112.6  285.07  5161.8  286.96  5202.3  284.28  5360.3  292.43
#Mann= 3 ,-1 , 0
    4545     .05       0  4978.8     .03       0  4984.8     .05       0
Bank Sta=4978.8,4984.8
XS Rating Curve= 0 ,0
Exp/Cntr=0.3,0.1

Type RM Length L Ch R = 1 ,2111    ,191,191,191
BEGIN DESCRIPTION:
Mapping XS 5c98eb05
END DESCRIPTION:
XS GIS Cut Line= 4
      3657146.53     10152538.73      3657265.87     10152862.04
      3657485.06     10152927.15      3657721.64     10152961.87
#Sta/Elev= 30
  4519.1  290.04  4524.2  290.65  4549.2  289.85  4554.6  290.41  4574.3  289.94
  4579.7  290.33  4640.5  288.67  4852.7   279.8  4922.4  275.49  4943.3  274.79
  4954.5  272.92  4982.5  271.65  5002.9   271.2  5005.6   270.7  5015.7  271.61
  5020.9  271.21  5026.7  272.67  5037.1  274.24  5054.1   275.6  5059.4  275.47
  5087.4  277.19  5091.5  276.96  5129.8  280.78  5139.9  279.72    5150     280
  5226.2  284.08  5251.1  284.47    5291  286.06    5296  285.74  5331.5   288.5
#Mann= 3 , 0 , 0
  4519.1     .05       0  4982.5    .035       0  5015.7     .05       0
Bank Sta=4982.5,5015.7
XS Rating Curve= 0 ,0
Exp/Cntr=0.3,0.1

Type RM Length L Ch R = 1 ,1926    ,126,126,126
BEGIN DESCRIPTION:
UNT065 IN ROCK 4.0
END DESCRIPTION:
XS GIS Cut Line= 3
      3657091.06     10152821.69       3657409.1     10153124.63
      3657761.45     10153096.53
#Sta/Elev= 30
  4621.2   283.9  4657.3  283.94  4692.5  283.24  4791.6  279.29  4848.2   275.9
  4883.8  274.56  4904.8  271.86  4912.1  271.67    4919  270.79  4926.2  270.68
  4933.1  269.86  4947.3  269.34  4954.2  268.24  4968.3  267.27  4975.6  266.08
  4989.7  265.01  4996.4  263.91  5003.9  265.36  5010.8  265.51    5018  268.03
  5032.2  270.87  5059.1   274.4  5103.6   276.6  5153.7   277.9  5159.8  278.43
  5164.8   278.1  5183.8  278.94    5234  282.75  5314.2  285.41  5413.9  290.81
#Mann= 3 , 0 , 0
  4621.2     .05       0  4989.7    .035       0  5003.9     .05       0
Bank Sta=4989.7,5003.9
XS Rating Curve= 0 ,0
Exp/Cntr=0.3,0.1

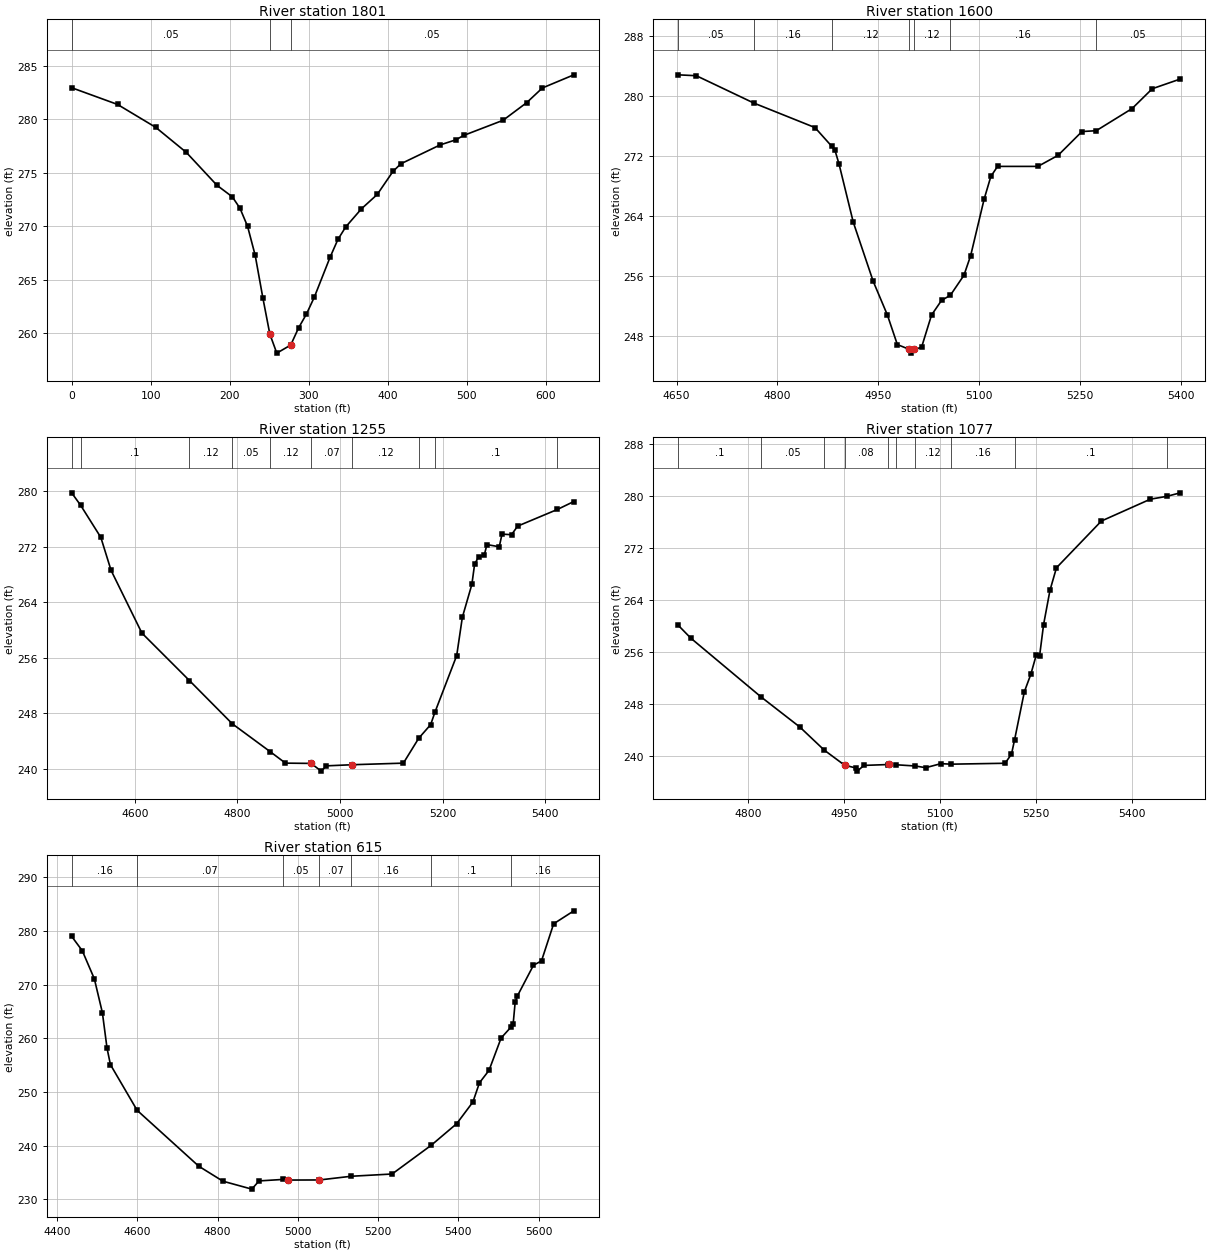
Type RM Length L Ch R = 1 ,1801    ,200,200,200
XS GIS Cut Line= 4
     3657106.493     10152929.57     3657256.493    10153118.459
     3657268.298    10153151.792     3657618.993     10153229.57
#Sta/Elev= 30
       0 282.95658.04458281.3925106.4151279.2458145.1115276.9007183.8078273.8285
 203.156272.7545212.8301 271.694222.5042269.9945232.1783267.2693241.8524263.2997
250.6644259.9156259.4763258.1288277.1002258.8837287.0481260.4905296.9959261.7837
306.9438263.3624326.8396267.0909336.7875268.7623346.7354269.9403366.6311271.6335
386.5269272.9707406.4226275.1238416.3705275.8393466.1099277.6063486.0056278.0833
495.9535278.4959545.6929279.9088575.5366281.5571595.4323282.9332635.2239284.1627
#Mann= 3 , 0 , 0
       0     .05       0250.6644    .035       0277.1002     .05       0
Bank Sta=250.6644,277.1002
XS Rating Curve= 0 ,0
Exp/Cntr=0.3,0.1

Type RM Length L Ch R = 1 ,1600    ,345,345,345
BEGIN DESCRIPTION:
UNT065 IN ROCK 3.0
END DESCRIPTION:
XS GIS Cut Line= 4
      3657071.67     10153020.96      3657109.43     10153212.39
      3657283.91     10153332.18      3657623.77     10153339.99
#Sta/Elev= 30
  4652.4  282.85  4679.5  282.73  4764.9  279.08  4855.9   275.8    4881  273.28
  4885.7  272.74  4891.8  270.88  4912.8  263.16  4942.5  255.24  4963.5  250.76
  4978.4  246.79  4996.4  246.15  4999.1  245.65  5002.4  246.15  5014.3  246.41
  5029.2  250.74  5044.1   252.7  5057.2  253.38  5077.4  256.06  5087.4  258.69
  5107.4  266.23  5117.4  269.27  5127.4  270.61  5187.4  270.61  5217.4  272.09
  5252.9  275.27  5274.1  275.38  5327.4  278.34  5357.4  280.99  5399.1  282.29
#Mann= 7 ,-1 , 0
  4652.4     .05       0  4764.9     .16       0    4881     .12       0
  4996.4     .07       0  5002.4     .12       0  5057.2     .16       0
  5274.1     .05       0
Bank Sta=4996.4,5002.4
XS Rating Curve= 0 ,0
Exp/Cntr=0.3,0.1

Type RM Length L Ch R = 1 ,1255    ,178,178,178
BEGIN DESCRIPTION:
Mapping XS cec2a808
END DESCRIPTION:
XS GIS Cut Line= 3
      3656565.19     10153556.14      3657263.08     10153574.36
      3657523.51     10153681.14
#Sta/Elev= 30
  4476.5  279.75    4494  277.96  4533.4  273.34  4553.4  268.59  4613.5  259.57
  4706.3  252.73  4789.9  246.51  4863.6  242.51  4893.6  240.85  4943.6  240.81
  4963.3   239.7  4973.6  240.46  5023.6  240.62  5123.6  240.85  5153.6  244.44
  5176.8  246.39    5185  248.15  5227.6  256.33  5238.6  261.83  5257.2  266.58
  5262.6  269.52  5270.8  270.57  5281.2  270.75  5286.6   272.3  5310.6  271.99
    5316  273.81  5334.5  273.72  5346.5  274.96  5424.1  277.36  5456.1   278.5
#Mann= 10 ,-1 , 0
  4476.5     .05       0    4494      .1       0  4706.3     .12       0
  4789.9     .05       0  4863.6     .12       0  4943.6     .07       0
  5023.6     .12       0  5153.6     .05       0    5185      .1       0
  5424.1     .05       0
Bank Sta=4943.6,5023.6
XS Rating Curve= 0 ,0
Exp/Cntr=0.3,0.1

Type RM Length L Ch R = 1 ,1077    ,462,462,462
BEGIN DESCRIPTION:
UNT065 IN ROCK 2.0
END DESCRIPTION:
XS GIS Cut Line= 3
      3656742.12     10153741.64      3657042.11     10153741.64
      3657525.13     10153714.05
#Sta/Elev= 30
    4691  260.06    4711  258.05  4820.5  249.02    4881  244.39  4919.1  240.84
    4951  238.51    4968  238.11  4970.7  237.61    4981  238.49  5017.9  238.62
  5020.1  238.64  5031.1  238.59  5061.1   238.4  5077.4  238.14  5101.2  238.76
    5117  238.68  5201.3  238.82  5211.3  240.22  5216.1  242.41  5231.4  249.82
  5241.4  252.48  5250.2  255.55  5255.2  255.36  5261.4  260.15  5271.4  265.43
  5281.5  268.89  5351.6  276.08    5428  279.44  5453.3  279.87  5474.8  280.42
#Mann= 10 ,-1 , 0
    4691      .1       0  4820.5     .05       0  4919.1     .12       0
    4951     .08       0  5017.9     .12       0  5031.1     .08       0
  5061.1     .12       0    5117     .16       0  5216.1      .1       0
  5453.3     .05       0
Bank Sta=4951,5020.1
XS Rating Curve= 0 ,0
Exp/Cntr=0.3,0.1

Type RM Length L Ch R = 1 ,615     ,0,0,0
BEGIN DESCRIPTION:
UNT065 IN ROCK 1.0
END DESCRIPTION:
XS GIS Cut Line= 3
       3656455.6     10154161.97      3656992.11     10154191.64
      3657702.19     10154109.88
#Sta/Elev= 30
  4435.9  279.01  4462.4  276.33  4492.5  271.09  4512.5  264.79  4524.1  258.17
  4532.6  255.09  4599.2  246.57  4752.9  236.15    4813  233.36  4885.1  231.88
  4903.1  233.41  4963.2  233.69  4975.7  233.57  5053.8  233.59    5133  234.28
  5234.9   234.7  5332.6  240.07    5396  244.09  5436.3  248.12  5452.7  251.71
  5476.5  254.02  5506.7  260.06  5532.1  262.16  5536.7  262.68  5541.7  266.74
    5547  267.86  5587.3  273.62  5607.4  274.44  5637.6  281.35    5688  283.77
#Mann= 7 ,-1 , 0
  4435.9     .16       0  4599.2     .07       0  4963.2     .05       0
  5053.8     .07       0    5133     .16       0  5332.6      .1       0
  5532.1     .16       0
Bank Sta=4975.7,5053.8
XS Rating Curve= 0 ,0
Exp/Cntr=0.3,0.1
Stream Node=UNT065 IN ROCK  ,Reach-1         , 0 , 0 ,Upstream end
Stream Node=UNT065 IN ROCK  ,Reach-1         , 0 , 1 ,Downstream end

Chan Stop Cuts=-1
Use User Specified Reach Order=0
Composite Channel Slope=5