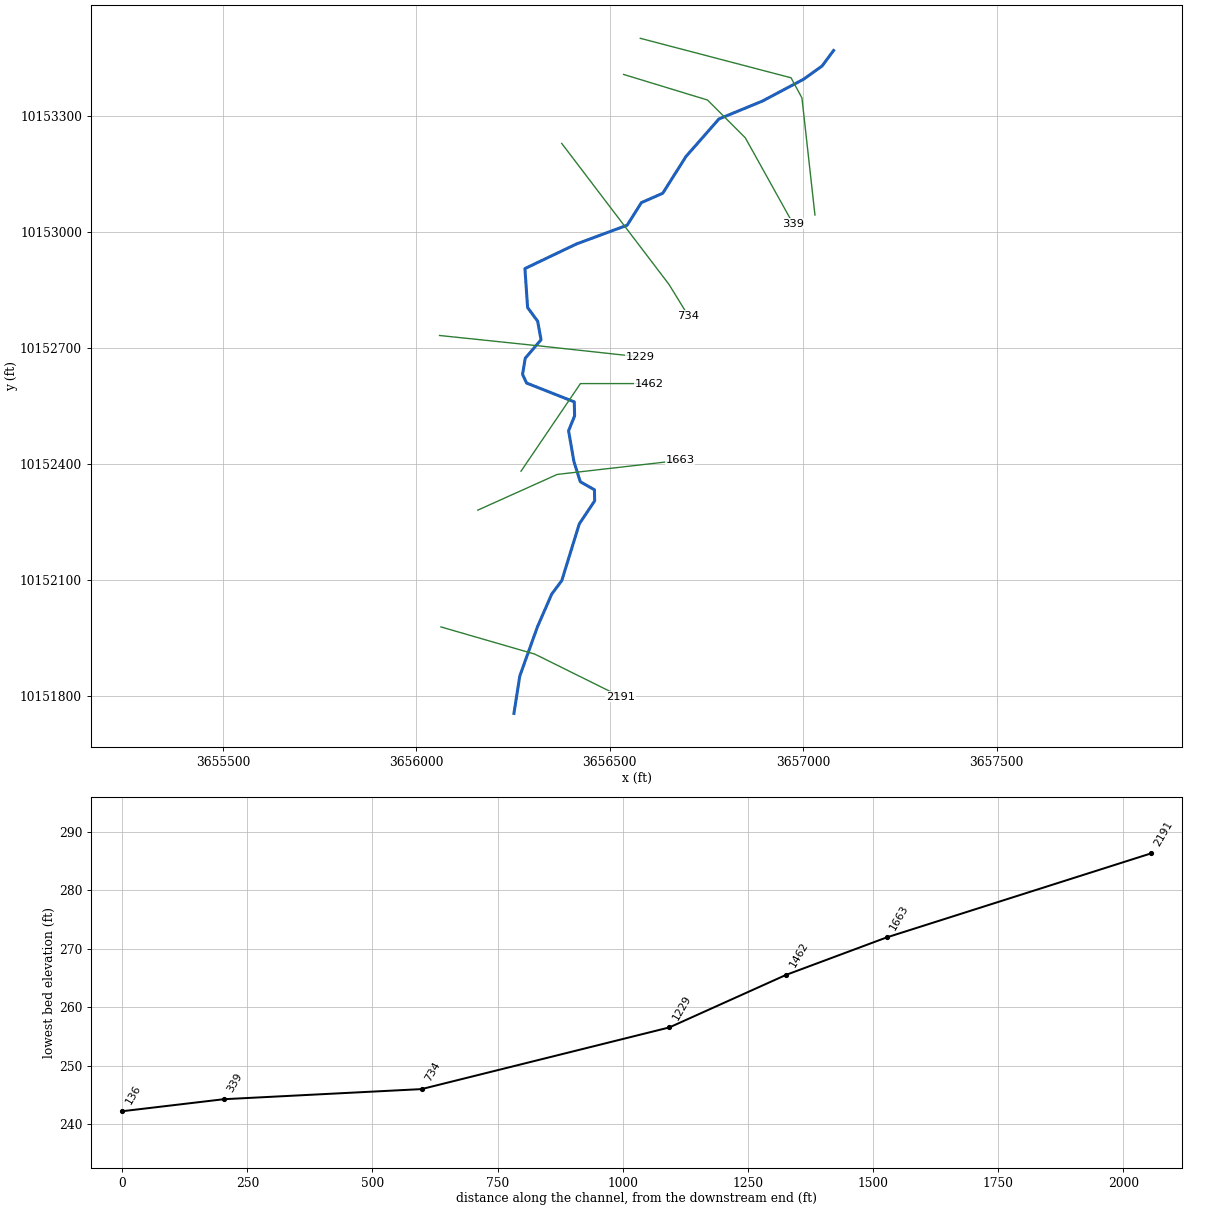
--- UNT066 IN ROCK.prj (project) ---

Proj Title=UNT066 IN ROCK Base Level Engineering
Current Plan=p01
Default Exp/Contr=0.3,0.1
English Units
Geom File=g01
Flow File=f01
Plan File=p01
Y Axis Title=Elevation
X Axis Title(PF)=Main Channel Distance
X Axis Title(XS)=Station
BEGIN DESCRIPTION:
UNT066 IN ROCK
END DESCRIPTION:
DSS Export Rating Curves= 0
DSS Export Rating Curve Sorted= 0
DSS Export Volume Flow Curves= 0
DXF OffsetX= 0
DXF OffsetY= 0
DXF ScaleX= 1
DXF ScaleY= 10

--- UNT066 IN ROCK.p01 (plan) ---

Plan Title=Multiple Run
Short Identifier=Multiple
Geom File=g01
Flow File=f01
Subcritical Flow
K Sum by GR= 0
Std Step Tol= 0.01
Critical Tol= 0.01
Num of Std Step Trials= 20
Max Error Tol= 0.3
Flow Tol Ratio= 0.001
Split Flow NTrial= 30
Split Flow Tol= 0.02
Split Flow Ratio= 0.02
Log Output Level= 0
Friction Slope Method= 1
Unsteady Friction Slope Method= 2
Unsteady Bridges Friction Slope Method= 1
Parabolic Critical Depth
Global Vel Dist=  1 , 1 , 1
Global Log Level= 0
CheckData=True
Encroach Param= -1, 0, 0, 0
BEGIN DESCRIPTION:
Multiple Run
END DESCRIPTION:

--- UNT066 IN ROCK.f01 (steady flow) ---

Flow Title=Multiple
Program Version=4.10
Number of Profiles= 7
Profile Names=10-year,25-year,50-year,1pct_min,100-year,1pct_plu,500-year
River Rch & RM=UNT066 IN ROCK,Reach-1         ,2191
     247     318     375     326     440     595     606
Boundary for River Rch & Prof#=UNT066 IN ROCK,Reach-1         , 1
Up Type= 0
Dn Type= 3
Dn Slope=0.005
Boundary for River Rch & Prof#=UNT066 IN ROCK,Reach-1         , 2
Up Type= 0
Dn Type= 3
Dn Slope=0.005
Boundary for River Rch & Prof#=UNT066 IN ROCK,Reach-1         , 3
Up Type= 0
Dn Type= 3
Dn Slope=0.005
Boundary for River Rch & Prof#=UNT066 IN ROCK,Reach-1         , 4
Up Type= 0
Dn Type= 3
Dn Slope=0.005
Boundary for River Rch & Prof#=UNT066 IN ROCK,Reach-1         , 5
Up Type= 0
Dn Type= 3
Dn Slope=0.005
Boundary for River Rch & Prof#=UNT066 IN ROCK,Reach-1         , 6
Up Type= 0
Dn Type= 3
Dn Slope=0.005
Boundary for River Rch & Prof#=UNT066 IN ROCK,Reach-1         , 7
Up Type= 0
Dn Type= 3
Dn Slope=0.005
DSS Import GetInterval= 0
DSS Import GetPeak= 0
DSS Import FillOption= 0

--- UNT066 IN ROCK.g01 (geometry) ---

Geom Title=Existing Conditions
Program Version=4.10

River Reach=UNT066 IN ROCK  ,Reach-1
Reach XY= 30
      3656252.17     10151754.36      3656267.34     10151851.11
      3656312.92     10151978.07      3656349.81      10152062.7
      3656375.91     10152097.75      3656421.09     10152244.16
      3656460.86     10152303.74      3656460.34     10152332.45
      3656423.79     10152353.18       3656407.3     10152405.27
      3656393.41     10152485.13      3656409.04     10152523.32
      3656408.17     10152559.78      3656284.91     10152608.39
      3656274.49     10152630.96      3656281.43     10152672.63
      3656322.23     10152720.37      3656313.55     10152768.11
      3656287.51     10152803.71      3656280.57      10152904.4
      3656413.64     10152967.93      3656544.98     10153016.55
      3656581.65     10153074.88      3656636.91     10153099.14
      3656697.08     10153194.29       3656782.2      10153291.2
      3656894.44     10153337.38      3657001.17     10153394.01
      3657048.99     10153428.29      3657078.68     10153468.32

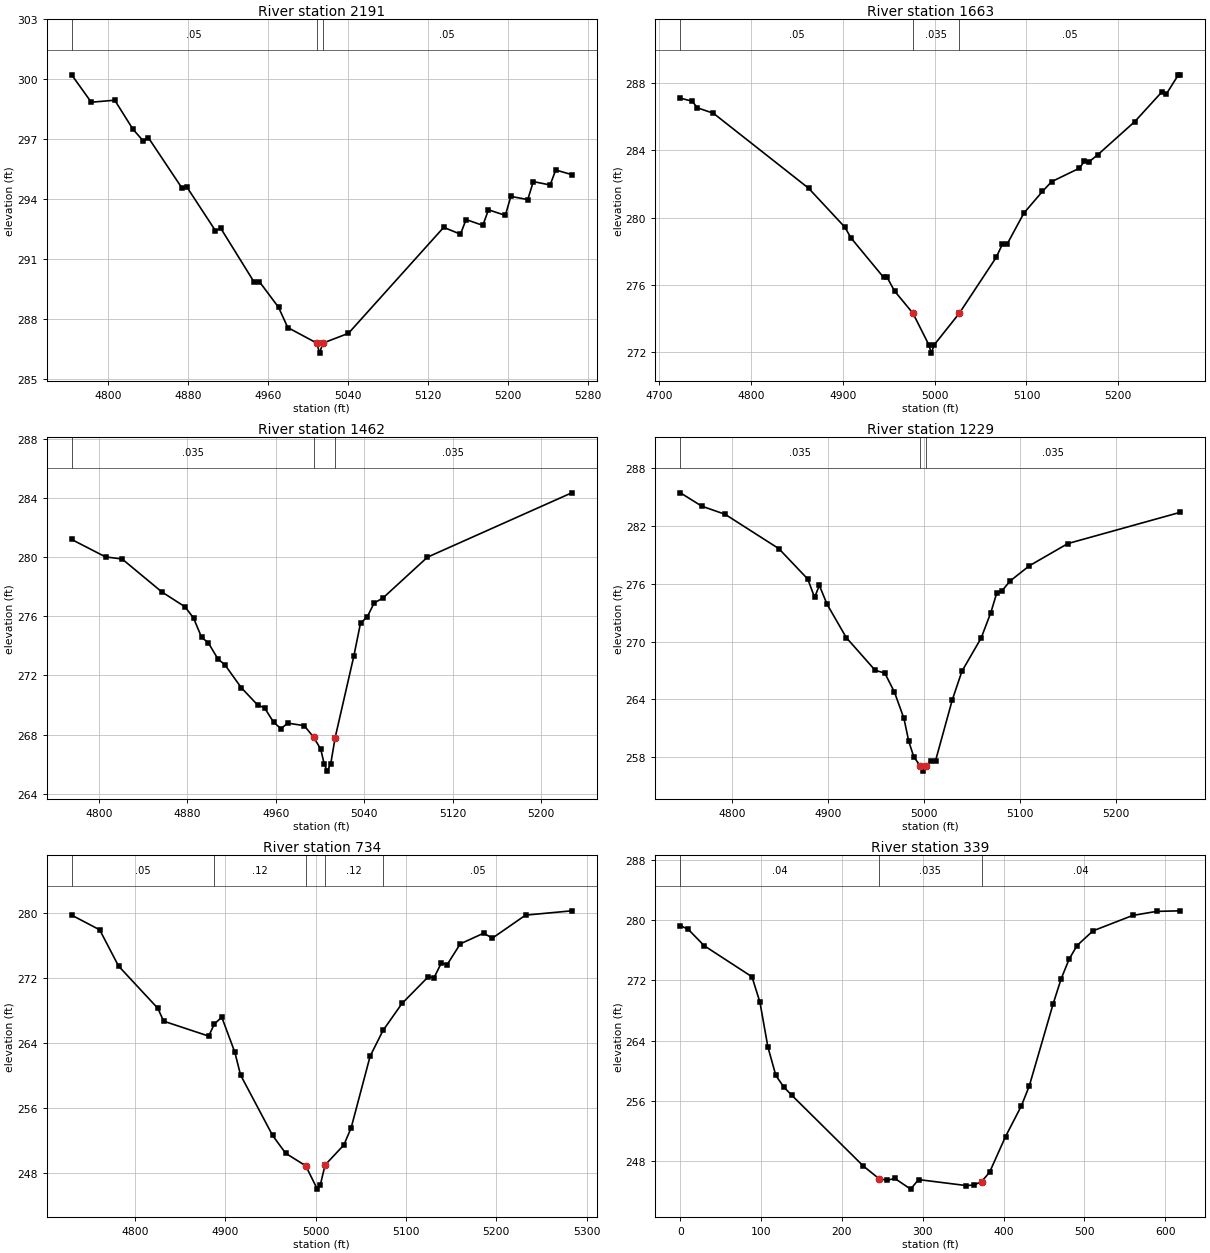
Type RM Length L Ch R = 1 ,2191    ,528,528,528
BEGIN DESCRIPTION:
UNT066 IN ROCK 5.0
END DESCRIPTION:
XS GIS Cut Line= 3
      3656063.25     10151977.95      3656306.29     10151907.51
      3656527.85     10151797.74
#Sta/Elev= 30
  4763.8  300.22  4783.4  298.85  4806.9  298.95  4825.1   297.5  4835.3  296.92
  4840.5  297.08  4874.1  294.56  4879.3  294.59  4907.7  292.42  4912.9  292.55
  4946.5  289.84  4951.7  289.87  4970.8  288.59    4980  287.58  5009.1   286.8
  5011.8   286.3  5015.1   286.8  5040.7  287.29    5136  292.59  5152.8  292.25
  5158.4  292.98  5175.2  292.69  5180.8  293.47  5197.7  293.19  5203.2  294.14
  5220.1  293.98  5225.7  294.88  5242.5  294.71  5248.1  295.46  5264.1  295.23
#Mann= 3 ,-1 , 0
  4763.8     .05       0  5009.1     .03       0  5015.1     .05       0
Bank Sta=5009.1,5015.1
XS Rating Curve= 0 ,0
Exp/Cntr=0.3,0.1

Type RM Length L Ch R = 1 ,1663    ,201,201,201
BEGIN DESCRIPTION:
UNT066 IN ROCK 4.0
END DESCRIPTION:
XS GIS Cut Line= 3
      3656158.75     10152279.83      3656364.02     10152372.14
      3656681.37      10152408.5
#Sta/Elev= 30
  4723.1  287.11    4736  286.93  4741.5  286.54  4759.1  286.21  4862.7  281.75
  4902.2  279.43    4909  278.78  4944.4  276.44  4948.2  276.44  4956.3  275.63
  4976.4   274.3  4993.6  272.43  4996.3  271.93  4999.6  272.43  5026.8   274.3
    5067  277.63  5073.8  278.42  5078.9  278.42  5097.2  280.27  5117.4  281.56
  5127.4  282.14  5157.6  282.94    5163  283.35  5168.1  283.32  5177.8  283.75
    5218  285.72  5247.2  287.47  5252.3  287.36  5265.4   288.5  5267.6   288.5
#Mann= 3 , 0 , 0
  4723.1     .05       0  4976.4    .035       0  5026.8     .05       0
Bank Sta=4976.4,5026.8
XS Rating Curve= 0 ,0
Exp/Cntr=0.3,0.1

Type RM Length L Ch R = 1 ,1462    ,233,233,233
BEGIN DESCRIPTION:
Mapping XS 7b6ced4a
END DESCRIPTION:
XS GIS Cut Line= 3
      3656270.47     10152380.47      3656424.13     10152607.05
      3656602.56     10152607.05
#Sta/Elev= 30
  4775.4  281.21    4806  280.03    4821  279.89  4856.9  277.66  4877.9  276.65
  4885.6  275.89  4892.9  274.58  4898.9  274.22  4907.8   273.1  4913.8  272.74
  4928.8  271.17  4943.7  269.99  4949.8  269.81  4958.1  268.82  4964.7   268.4
  4970.8  268.77  4985.7   268.6  4994.3  267.81  5000.7     267  5003.7  266.02
  5006.5  265.52  5009.7  266.02 5013.64  267.78  5030.5  273.29  5036.6  275.54
  5042.7  275.97  5048.9   276.9  5057.1  277.26  5097.1  280.01  5227.6  284.37
#Mann= 3 , 0 , 0
  4775.4    .035       0  4994.3     .03       0 5013.64    .035       0
Bank Sta=4994.3,5013.64
XS Rating Curve= 0 ,0
Exp/Cntr=0.3,0.1

Type RM Length L Ch R = 1 ,1229    ,495,495,495
BEGIN DESCRIPTION:
UNT066 IN ROCK 3.0
END DESCRIPTION:
XS GIS Cut Line= 3
      3656059.83     10152731.41      3656322.57     10152703.95
      3656578.89     10152676.05
#Sta/Elev= 30
  4745.7  285.45  4768.1  284.06  4792.4  283.22  4848.5  279.65  4878.7  276.49
  4885.8  274.59  4890.8  275.83  4898.8  273.88  4918.9  270.41  4949.1  267.01
  4959.1  266.73  4969.2  264.74  4979.1  262.01  4984.1  259.64  4989.3  258.04
  4996.3  257.04  4999.1  256.54  5002.3  257.04  5007.1  257.63  5012.1  257.63
  5029.5  263.92  5039.6  266.91  5059.7  270.37  5069.8  273.01  5076.1  275.09
  5081.1  275.23  5089.9  276.29    5110  277.87  5150.2  280.18  5267.7  283.43
#Mann= 3 , 0 , 0
  4745.7    .035       0  4996.3     .03       0  5002.3    .035       0
Bank Sta=4996.3,5002.3
XS Rating Curve= 0 ,0
Exp/Cntr=0.3,0.1

Type RM Length L Ch R = 1 ,734     ,395,395,395
BEGIN DESCRIPTION:
UNT066 IN ROCK 2.0
END DESCRIPTION:
XS GIS Cut Line= 3
      3656375.76     10153227.98      3656653.22     10152863.24
       3656703.2     10152781.95
#Sta/Elev= 30
  4729.9  279.74  4760.9  277.93  4781.8  273.47  4825.4  268.25  4831.7  266.68
  4881.6  264.84  4887.9  266.33  4896.1  267.17  4910.6  262.84  4916.9  260.05
  4952.3  252.62  4966.8  250.41  4989.1  248.86  5001.9  245.99  5005.2  246.49
  5010.5  248.96  5031.3  251.43  5039.4  253.55  5060.4  262.37  5074.7  265.54
  5095.7  268.86  5124.8  272.15  5131.1  272.02  5139.3  273.86  5145.6  273.63
  5160.2   276.2    5186  277.51  5195.8  276.91  5232.5  279.74  5283.6  280.27
#Mann= 5 ,-1 , 0
  4729.9     .05       0  4887.9     .12       0  4989.1     .07       0
  5010.5     .12       0  5074.7     .05       0
Bank Sta=4989.1,5010.5
XS Rating Curve= 0 ,0
Exp/Cntr=0.3,0.1

Type RM Length L Ch R = 1 ,339     ,203,203,203
XS GIS Cut Line= 4
      3656535.67    10153406.367     3656752.684    10153340.177
      3656850.34    10153242.521     3656974.038    10153020.082
#Sta/Elev= 30
       0279.27019.849206278.752729.54762 276.58688.64285 272.46498.49206 269.084
108.3413263.1439118.1905259.3534128.0397257.8189137.8889256.7334226.5317247.3217
246.0421 245.638255.7973245.4407265.5525245.6722285.0629244.2604294.8181245.5275
353.3492244.7401363.1043244.7939372.9463245.2645382.7882246.5105402.4721251.2329
422.1559255.3247431.9979257.9934461.5237268.8963471.3656272.1963481.2075274.8003
491.0495276.6145510.7333278.5621 559.943 280.612589.4688281.1506618.9946281.2249
#Mann= 3 , 0 , 0
       0     .04       0246.0421    .035       0372.9463     .04       0
Bank Sta=246.0421,372.9463
XS Rating Curve= 0 ,0
Exp/Cntr=0.3,0.1

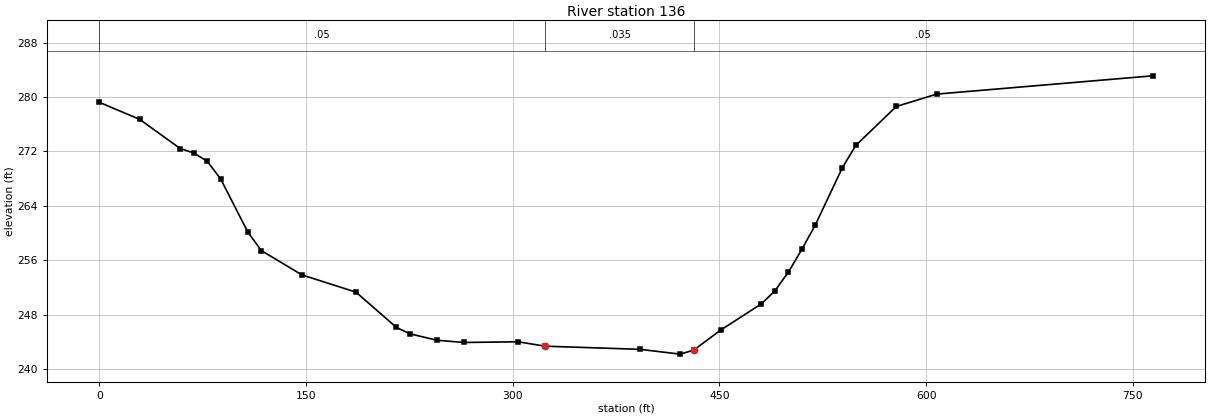
Type RM Length L Ch R = 1 ,136     ,0,0,0
XS GIS Cut Line= 4
     3656579.073    10153499.683     3656968.613    10153397.686
     3656996.825    10153345.603     3657030.462    10153042.868
#Sta/Elev= 30
       0279.222329.41318276.702858.82637272.415668.63076271.768378.43516270.5388
88.23956267.9076107.8483260.1336117.6527257.4199147.0659253.8512186.2835251.3171
215.6967246.1231225.5011245.1871245.1099244.2415264.7187243.9189303.9362244.0182
 323.545243.3723392.1758 242.911   421.6242.2049431.4099242.8034451.0296245.7563
480.4261249.5882490.2193251.4917500.0125254.2549509.8058257.5909519.5991261.1925
539.1855269.5951548.9788 272.885578.3586278.6057607.7383280.4241764.4304283.1089
#Mann= 3 , 0 , 0
       0     .05       0 323.545    .035       0431.4099     .05       0
Bank Sta=323.545,431.4099
XS Rating Curve= 0 ,0
Exp/Cntr=0.3,0.1

Chan Stop Cuts=-1
Use User Specified Reach Order=0
Composite Channel Slope=5