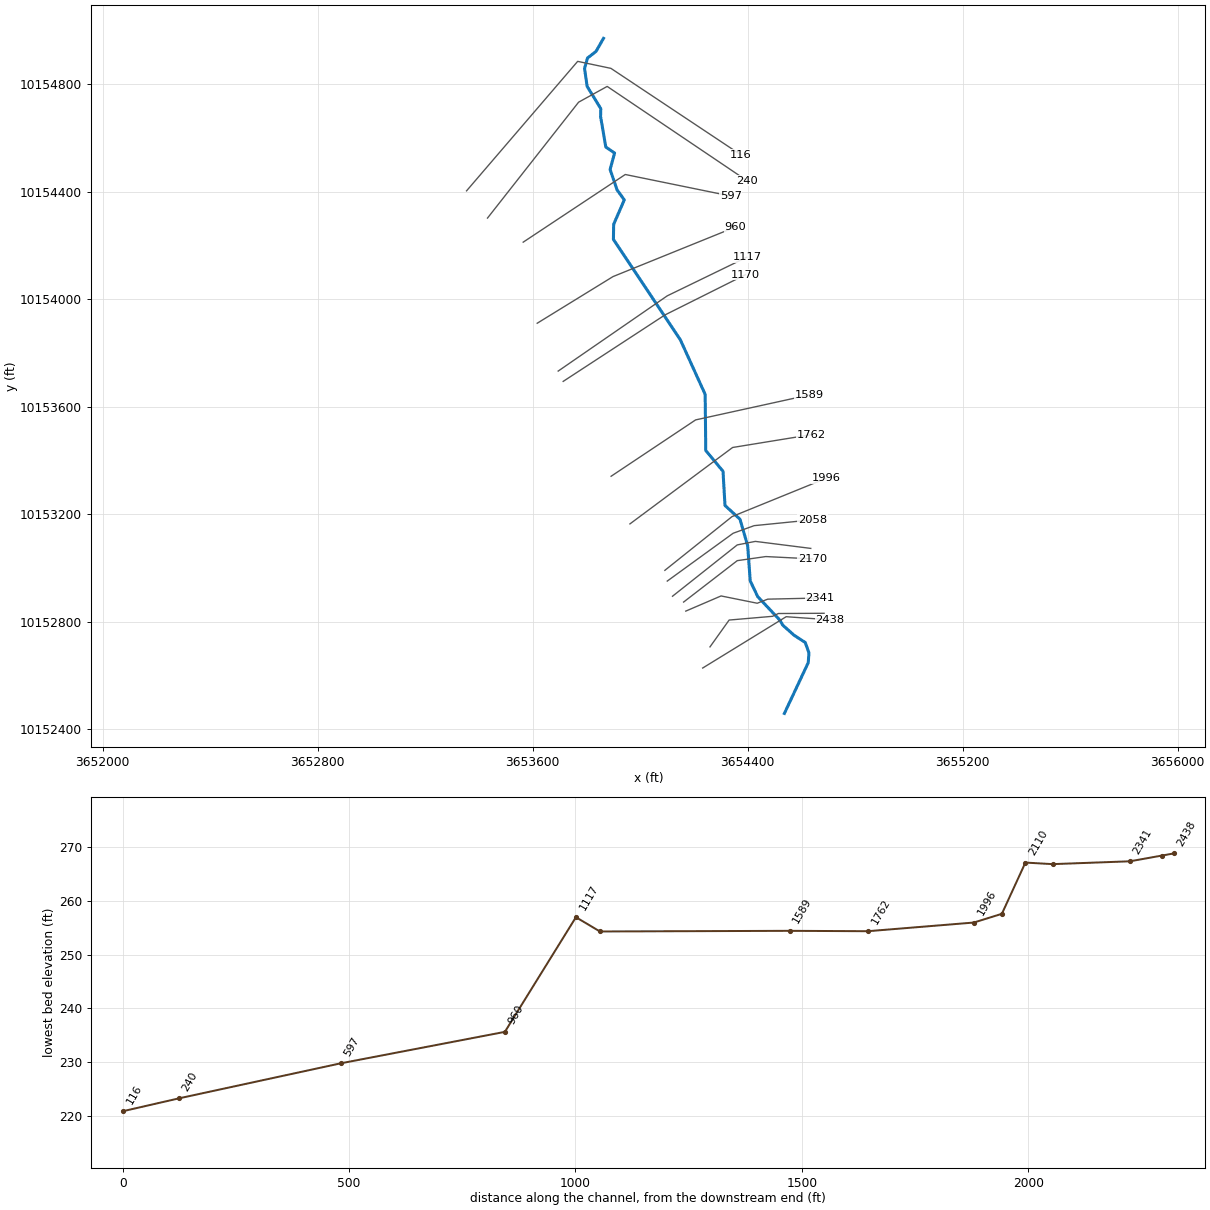
--- UNT067 IN ROCK.prj (project) ---

Proj Title=UNT067 IN ROCK Base Level Engineering
Current Plan=p01
Default Exp/Contr=0.3,0.1
English Units
Geom File=g01
Flow File=f01
Plan File=p01
Y Axis Title=Elevation
X Axis Title(PF)=Main Channel Distance
X Axis Title(XS)=Station
BEGIN DESCRIPTION:
UNT067 IN ROCK
END DESCRIPTION:
DSS Export Rating Curves= 0
DSS Export Rating Curve Sorted= 0
DSS Export Volume Flow Curves= 0
DXF OffsetX= 0
DXF OffsetY= 0
DXF ScaleX= 1
DXF ScaleY= 10

--- UNT067 IN ROCK.p01 (plan) ---

Plan Title=Multiple Run
Short Identifier=Multiple
Geom File=g01
Flow File=f01
Subcritical Flow
K Sum by GR= 0
Std Step Tol= 0.01
Critical Tol= 0.01
Num of Std Step Trials= 20
Max Error Tol= 0.3
Flow Tol Ratio= 0.001
Split Flow NTrial= 30
Split Flow Tol= 0.02
Split Flow Ratio= 0.02
Log Output Level= 0
Friction Slope Method= 1
Unsteady Friction Slope Method= 2
Unsteady Bridges Friction Slope Method= 1
Parabolic Critical Depth
Global Vel Dist=  1 , 1 , 1
Global Log Level= 0
CheckData=True
Encroach Param= -1, 0, 0, 0
BEGIN DESCRIPTION:
Multiple Run
END DESCRIPTION:

--- UNT067 IN ROCK.f01 (steady flow) ---

Flow Title=Multiple
Number of Profiles=7
Profile Names=10-year,25-year,50-year,1pct_min,100-year,1pct_plu,500-year
River Rch & RM= UNT067 IN ROCK,Reach-1,2438
     216     274     319     274     370     501     498
Boundary for River Rch & Prof#=UNT067 IN ROCK,Reach-1,1
Up Type=0
Dn Type=3
Dn Slope=0.005
Boundary for River Rch & Prof#=UNT067 IN ROCK,Reach-1,2
Up Type=0
Dn Type=3
Dn Slope=0.005
Boundary for River Rch & Prof#=UNT067 IN ROCK,Reach-1,3
Up Type=0
Dn Type=3
Dn Slope=0.005
Boundary for River Rch & Prof#=UNT067 IN ROCK,Reach-1,4
Up Type=0
Dn Type=3
Dn Slope=0.005
Boundary for River Rch & Prof#=UNT067 IN ROCK,Reach-1,5
Up Type=0
Dn Type=3
Dn Slope=0.005
Boundary for River Rch & Prof#=UNT067 IN ROCK,Reach-1,6
Up Type=0
Dn Type=3
Dn Slope=0.005
Boundary for River Rch & Prof#=UNT067 IN ROCK,Reach-1,7
Up Type=0
Dn Type=3
Dn Slope=0.005

--- UNT067 IN ROCK.g01 (geometry) ---

Geom Title=Existing Conditions
Program Version=4.10

River Reach=UNT067 IN ROCK  ,Reach-1
Reach XY= 30
      3654536.88     10152459.47      3654625.56     10152648.13
      3654628.16     10152684.59      3654614.52     10152723.08
      3654572.06     10152750.73      3654530.39     10152788.06
      3654520.85     10152805.42      3654437.51     10152893.96
      3654409.74     10152952.12      3654400.19      10153083.2
      3654371.66     10153181.67      3654315.83     10153232.98
      3654308.47     10153360.13      3654244.24     10153437.48
      3654242.08     10153646.27      3654149.69     10153849.39
      3653900.72      10154222.6       3653901.6     10154278.91
      3653941.18     10154369.88       3653914.1     10154407.38
       3653888.4     10154483.08      3653905.07     10154544.19
      3653872.43     10154566.41      3653852.99      10154679.6
      3653853.68     10154709.46      3653802.99      10154792.1
      3653793.27     10154858.77      3653804.38     10154897.66
      3653836.32     10154922.66      3653863.82     10154970.92

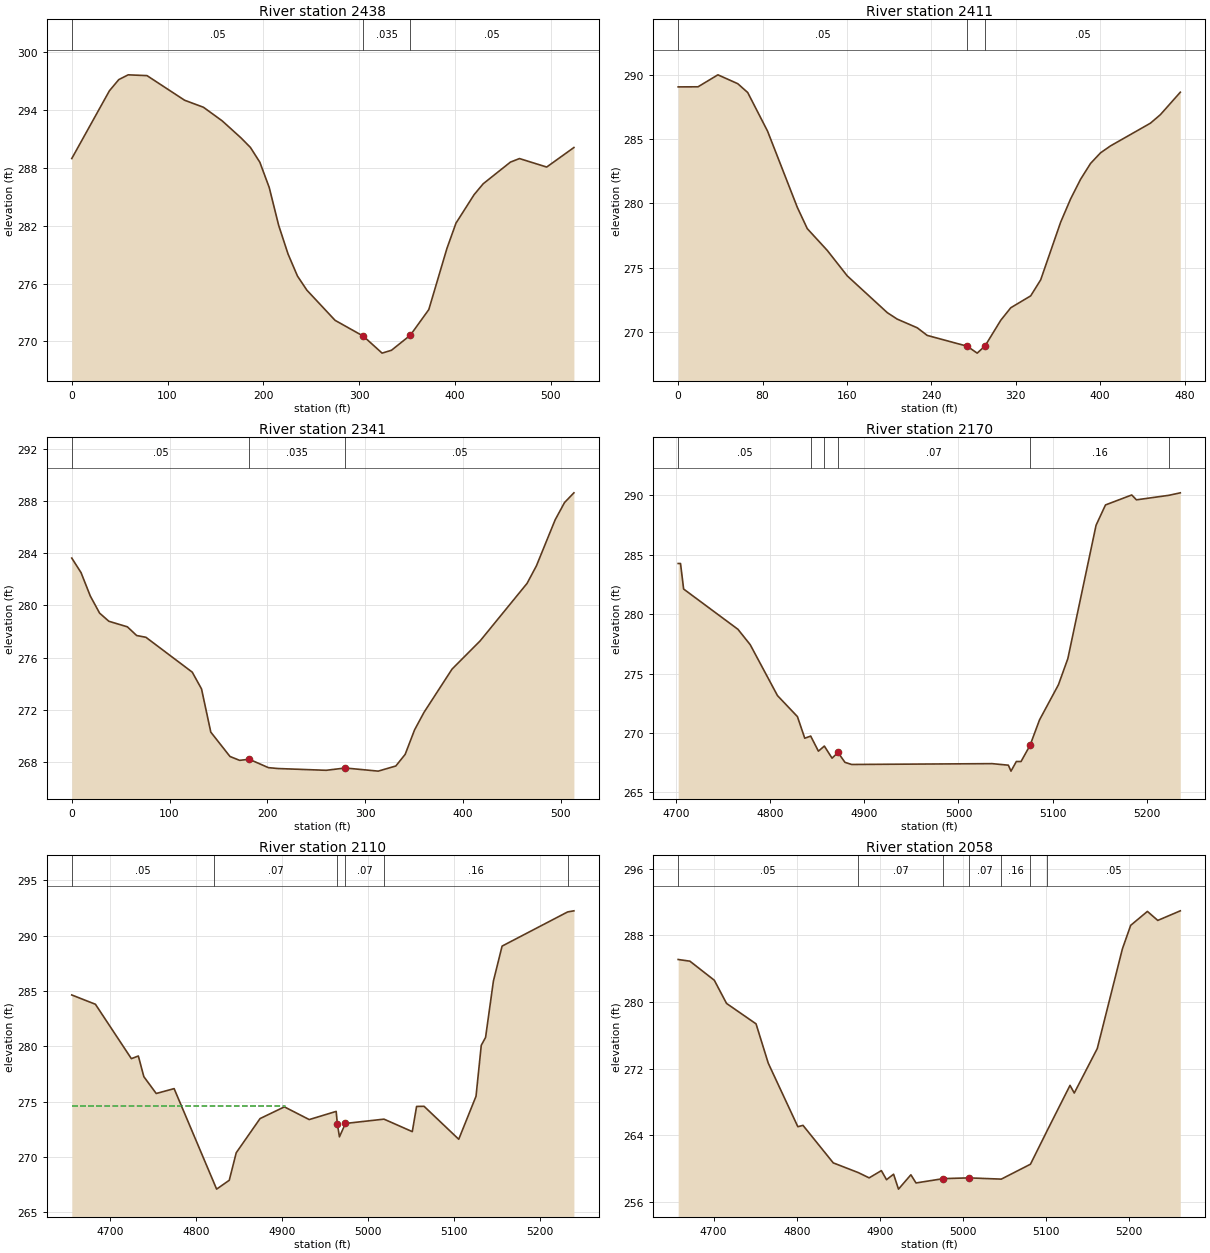
Type RM Length L Ch R = 1 ,2438    ,27,27,27
BEGIN DESCRIPTION:
UNT067 IN ROCK 6.0
END DESCRIPTION:
XS GIS Cut Line= 3
     3654232.864    10152628.199     3654543.381      10152819.1
     3654707.073     10152807.55
#Sta/Elev= 30
       0288.984639.27295296.012449.09119297.176958.90942 297.673 78.5459297.5906
117.8188295.0336137.4553294.3078157.0918292.8916176.7283291.1232186.5465290.1331
196.3647288.5995 206.183285.9703216.0012 282.052225.8195279.0705235.6377276.7855
245.4559275.3201274.9106272.1869304.3654270.5458324.0018268.7827333.8201269.0805
353.4565270.6411372.7445273.2992391.6841279.6477401.1539282.2787420.0934285.2369
429.5632286.3642457.9726288.6113467.4424288.9806495.8517288.0994 524.261290.1263
#Mann= 3 , 0 , 0
       0     .05       0304.3654    .035       0353.4565     .05       0
Bank Sta=304.3654,353.4565
XS Rating Curve= 0 ,0
Exp/Cntr=0.3,0.1

Type RM Length L Ch R = 1 ,2411    ,70,70,70
XS GIS Cut Line= 5
     3654260.025    10152706.856     3654331.205    10152806.682
     3654492.664    10152820.571     3654514.365    10152830.988
     3654684.504    10152831.856
#Sta/Elev= 30
       0 289.04718.82829289.054637.65658289.984156.48487289.295365.89902288.6113
84.72731285.6097112.9697279.6844122.3839278.0388 141.327276.3477160.2702274.3712
198.1565271.5205207.6281271.0146226.5712270.3422236.0428269.7501273.9291268.9116
283.4007268.3747290.8549268.9349305.7635270.9295 315.216271.8973334.1209 272.822
343.5734274.0654362.4784278.5394371.9308280.3482381.3833281.8733390.8358283.1023
400.2883283.9269409.7408284.4646447.5507286.2271457.0031286.8883475.9081288.6332
#Mann= 3 , 0 , 0
       0     .05       0273.9291    .035       0290.8549     .05       0
Bank Sta=273.9291,290.8549
XS Rating Curve= 0 ,0
Exp/Cntr=0.3,0.1

Type RM Length L Ch R = 1 ,2341    ,171,171,171
XS GIS Cut Line= 5
      3654169.91     10152839.94     3654301.203    10152896.363
     3654435.752    10152869.236     3654474.814    10152884.427
     3654669.042    10152888.768
#Sta/Elev= 30
       0283.6226 9.47718282.510918.95436280.718528.43154279.413137.90872278.7875
56.86309278.361466.34026 277.69775.81744277.5609123.2034274.8911132.6805273.6099
142.1577270.3029161.8086268.4368 171.634268.1424181.4595 268.225201.1103267.5834
210.9358267.5162 260.063267.3803279.7138267.5575313.3467267.3175331.3405267.7098
340.9261268.5997350.5117270.4708360.0974271.8046388.8542275.1253417.6109277.2876
465.5389281.6833475.1245283.0268494.2957286.5501503.8813 287.872513.4669288.6166
#Mann= 3 , 0 , 0
       0     .05       0181.4595    .035       0279.7138     .05       0
Bank Sta=181.4595,279.7138
XS Rating Curve= 0 ,0
Exp/Cntr=0.3,0.1

Type RM Length L Ch R = 1 ,2170    ,60,60,60
BEGIN DESCRIPTION:
Mapping XS 33248eec
END DESCRIPTION:
XS GIS Cut Line= 4
      3654161.83      10152873.6       3654361.5      10153027.7
      3654467.84     10153042.89      3654641.48     10153034.21
#Sta/Elev= 30
  4702.2  284.27  4704.7  284.27    4708  282.12  4765.7  278.73  4778.7  277.44
  4807.7  273.15  4828.9  271.38  4836.7  269.56    4843  269.74  4851.2  268.47
  4857.5   268.9  4865.7  267.88    4872  268.36  4879.4  267.53  4886.5  267.35
  5035.8  267.42    5053  267.29  5055.8  266.79  5061.5   267.6  5066.5   267.6
  5076.1  268.97  5086.1   271.1  5106.2  274.06  5116.2  276.26  5146.2  287.49
  5156.2   289.2  5184.1  290.04  5189.1  289.63  5223.5  290.01  5235.7  290.22
#Mann= 6 ,-1 , 0
  4702.2     .05       0    4843     .07       0  4857.5     .16       0
    4872     .07       0  5076.1     .16       0  5223.5     .05       0
Bank Sta=4872,5076.1
XS Rating Curve= 0 ,0
Exp/Cntr=0.3,0.1

Type RM Length L Ch R = 1 ,2110    ,52,52,52
BEGIN DESCRIPTION:
Mapping XS bdee29ab
END DESCRIPTION:
XS GIS Cut Line= 4
      3654120.59     10152895.29       3654361.5     10153086.29
      3654428.78     10153099.31      3654634.97     10153073.27
#Sta/Elev= 30
  4655.9  284.64  4683.4   283.8  4725.2  278.88  4733.3  279.12  4739.7  277.25
  4754.1  275.73  4774.9  276.17  4821.6  267.58  4824.3  267.08    4839  267.88
  4847.1  270.37  4874.8  273.46  4903.1  274.52    4932  273.37  4963.3  274.11
 4964.68  272.99  4967.1  271.81  4974.1  273.02  5018.9  273.41  5051.8  272.28
  5056.8  274.56  5065.5  274.57  5105.8  271.59  5125.9  275.48    5132  280.09
    5137   280.8  5146.1  285.89  5156.2  289.06  5232.4  292.15  5239.7  292.25
#Mann= 6 ,-1 , 0
  4655.9     .05       0  4821.6     .07       0 4964.68    .035       0
  4974.1     .07       0  5018.9     .16       0  5232.4     .05       0
#XS Ineff= 2 , 0
         4903.47  274.61
Permanent Ineff=
       F       F
Bank Sta=4964.68,4974.1
XS Rating Curve= 0 ,0
Exp/Cntr=0.3,0.1

Type RM Length L Ch R = 1 ,2058    ,62,62,62
BEGIN DESCRIPTION:
Mapping XS e803000c
END DESCRIPTION:
XS GIS Cut Line= 4
      3654101.06     10152951.72      3654346.31     10153129.69
      3654424.44      10153157.9      3654641.47     10153179.61
#Sta/Elev= 30
  4657.3  285.11  4671.4  284.91  4700.8  282.62  4715.5  279.84    4751  277.39
  4765.7  272.67  4801.3  265.05  4807.5  265.21  4843.9  260.71  4874.1  259.54
  4887.1  258.91  4901.8  259.78    4908  258.69  4916.5  259.35  4922.4  257.56
  4937.3  259.28  4943.5   258.3  4976.3  258.82    5007  258.91  5046.1  258.76
  5081.2  260.55  5101.3  264.58  5128.8  270.01  5133.9  269.09  5161.6  274.43
  5191.8  286.38  5201.8  289.21  5221.9  290.88  5234.4   289.8  5261.5  290.95
#Mann= 7 ,-1 , 0
  4657.3     .05       0  4874.1     .07       0  4976.3    .035       0
    5007     .07       0  5046.1     .16       0  5081.2     .07       0
  5101.3     .05       0
Bank Sta=4976.3,5007
XS Rating Curve= 0 ,0
Exp/Cntr=0.3,0.1

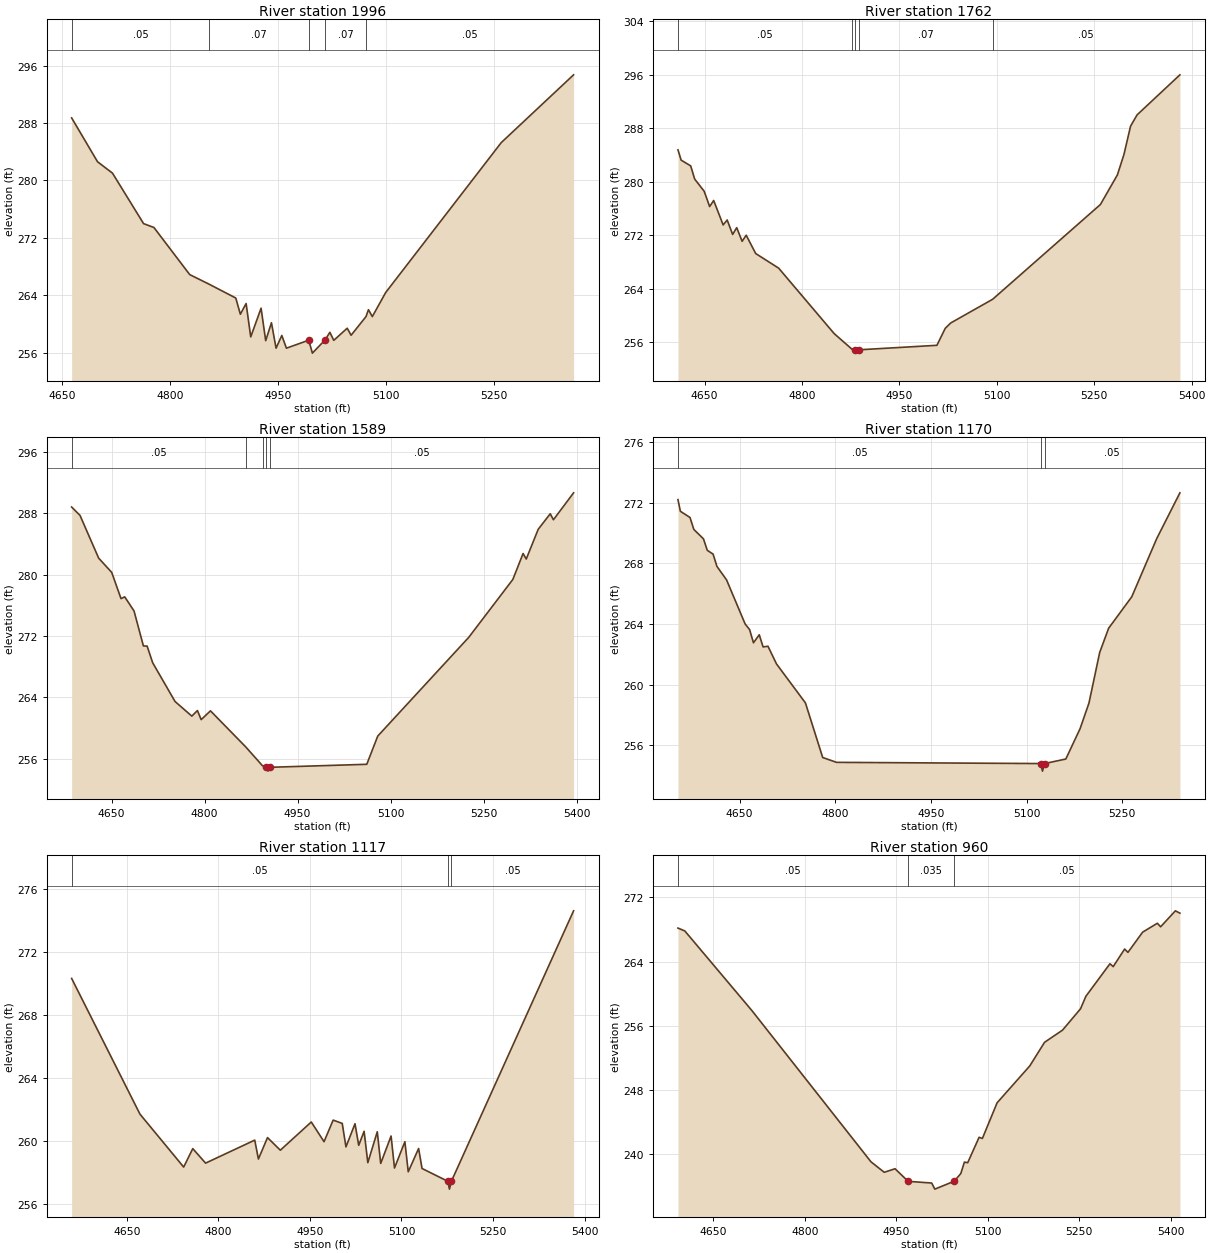
Type RM Length L Ch R = 1 ,1996    ,234,234,234
BEGIN DESCRIPTION:
UNT067 IN ROCK 5.0
END DESCRIPTION:
XS GIS Cut Line= 3
      3654092.11     10152991.65      3654342.11     10153191.64
      3654691.73     10153333.89
#Sta/Elev= 30
  4663.4  288.71  4699.4   282.6  4720.2  281.01  4763.4  273.98  4777.8  273.44
  4827.5  266.88  4854.3  265.55  4891.5  263.62  4897.9  261.36  4905.9  262.85
  4912.3   258.2  4926.7   262.2  4933.1  257.68  4941.1  260.17  4947.5  256.63
  4955.5   258.4  4961.9  256.63  4992.9  257.74    4998  255.94  5015.9  257.81
  5022.3  258.84  5027.7  257.72  5046.4  259.41  5051.8  258.43  5072.5  261.03
  5075.9  261.99  5081.3  261.03  5099.9  264.39  5260.5  285.27    5361  294.71
#Mann= 5 ,-1 , 0
  4663.4     .05       0  4854.3     .07       0  4992.9     .07       0
  5015.9     .07       0  5072.5     .05       0
Bank Sta=4992.9,5015.9
XS Rating Curve= 0 ,0
Exp/Cntr=0.3,0.1

Type RM Length L Ch R = 1 ,1762    ,173,173,173
BEGIN DESCRIPTION:
Mapping XS 0af343a0
END DESCRIPTION:
XS GIS Cut Line= 3
      3653962.18      10153164.4      3654344.14      10153448.7
      3654637.12     10153496.45
#Sta/Elev= 30
    4609  284.76  4613.9  283.22  4628.6  282.36  4634.8  280.38  4649.4  278.56
  4657.8  276.27    4664  277.18  4678.6  273.52  4684.8  274.26  4693.2   272.1
  4699.5  273.11  4707.8  271.07  4714.1  271.98  4728.7  269.24  4764.1  267.05
  4849.6  257.25  4877.1  254.91  4882.1  254.83  4884.8  254.33  4888.1  254.83
  5007.8   255.5  5020.6  258.04    5029  258.84  5093.6  262.39  5259.6  276.58
  5285.7     281  5295.9  284.09    5306   288.3    5316  289.99    5382  295.99
#Mann= 5 ,-1 , 0
    4609     .05       0  4877.1     .07       0  4882.1     .07       0
  4888.1     .07       0  5093.6     .05       0
Bank Sta=4882.1,4888.1
XS Rating Curve= 0 ,0
Exp/Cntr=0.3,0.1

Type RM Length L Ch R = 1 ,1589    ,419,419,419
BEGIN DESCRIPTION:
UNT067 IN ROCK 4.0
END DESCRIPTION:
XS GIS Cut Line= 3
      3653892.12     10153341.65      3654206.51     10153551.32
      3654627.77     10153643.85
#Sta/Elev= 30
  4585.7  288.83  4599.2  287.74  4629.3  282.16  4650.3  280.31  4665.3  276.89
  4671.3  277.12  4686.3  275.28  4701.4  270.72  4707.4   270.7  4716.4  268.52
  4752.4  263.48  4779.5  261.57  4788.5   262.3  4794.5  261.11  4809.5  262.26
  4866.1  257.58  4893.4   255.1  4899.7   254.9  4902.4   254.4  4905.7   254.9
  5061.5  255.29  5079.2  258.97  5225.9  271.84    5297  279.39  5313.5  282.77
  5318.6  282.05  5337.9  285.93  5357.3  287.95  5362.4  287.17  5394.9  290.68
#Mann= 5 ,-1 , 0
  4585.7     .05       0  4866.1     .07       0  4893.4     .05       0
  4899.7    .033       0  4905.7     .05       0
Bank Sta=4899.7,4905.7
XS Rating Curve= 0 ,0
Exp/Cntr=0.3,0.1

Type RM Length L Ch R = 1 ,1170    ,53,53,53
BEGIN DESCRIPTION:
UNT067 IN ROCK 3.0
END DESCRIPTION:
XS GIS Cut Line= 3
      3653713.85      10153694.6      3654092.11     10153941.64
      3654392.11     10154091.65
#Sta/Elev= 30
  4553.2  272.22    4557  271.45  4572.1  271.04  4578.1  270.25  4593.2  269.63
  4599.2  268.87  4608.3  268.62  4614.3  267.81  4629.4  266.92  4658.6     264
  4665.6  263.63  4671.6  262.76  4680.7  263.29  4686.7  262.49  4694.4  262.53
  4707.8  261.36  4753.1  258.79  4780.2  255.18  4801.9  254.86  5122.2  254.78
  5124.9  254.28  5128.2  254.78  5161.5  255.08  5183.9  257.09  5197.8  258.78
  5214.6  262.12  5228.6  263.72  5264.9   265.8  5304.1  269.65  5340.4  272.67
#Mann= 3 ,-1 , 0
  4553.2     .05       0  5122.2    .033       0  5128.2     .05       0
Bank Sta=5122.2,5128.2
XS Rating Curve= 0 ,0
Exp/Cntr=0.3,0.1

Type RM Length L Ch R = 1 ,1117    ,157,157,157
BEGIN DESCRIPTION:
Mapping XS 6fe0fe98
END DESCRIPTION:
XS GIS Cut Line= 3
      3653695.23     10153732.96      3654101.09     10154012.94
      3654397.09     10154156.65
#Sta/Elev= 30
  4559.8   270.3  4671.7  261.69  4743.3  258.33  4758.2   259.5  4779.2  258.58
  4859.7  260.04  4865.7  258.84  4880.6   260.2  4901.6   259.4  4952.3  261.19
  4973.2  259.94  4988.1  261.31    5003   261.1  5009.1  259.61  5023.9  261.08
    5030  259.71  5038.8   260.6  5044.9  258.61  5060.4  260.57    5066  258.56
    5083   260.3  5088.6  258.27  5105.6  259.94  5111.1  258.03  5128.1  259.51
  5133.7  258.24  5175.8  257.43  5178.6  256.93  5181.8  257.43  5381.9  274.59
#Mann= 3 ,-1 , 0
  4559.8     .05       0  5175.8     .03       0  5181.8     .05       0
Bank Sta=5175.8,5181.8
XS Rating Curve= 0 ,0
Exp/Cntr=0.3,0.1

Type RM Length L Ch R = 1 ,960     ,363,363,363
BEGIN DESCRIPTION:
UNT067 IN ROCK 2.0
END DESCRIPTION:
XS GIS Cut Line= 3
      3653617.17     10153910.96      3653899.26     10154084.55
      3654355.02     10154269.03
#Sta/Elev= 30
  4592.1  268.17  4603.4  267.81  4713.4  257.88  4908.6  239.03  4930.3  237.73
    4948  238.17  4969.5   236.6  5008.1  236.39  5013.2  235.63  5045.1  236.62
  5055.8  237.57  5061.7     239  5067.1  238.92  5085.8  242.09  5091.2  241.95
  5115.3  246.39  5168.9  250.99  5193.1  253.93  5222.6  255.45  5252.1  258.11
  5260.8  259.66  5300.3  263.72  5305.7  263.37  5324.4  265.56  5329.8  265.14
  5353.9  267.66    5378  268.77  5383.4  268.33  5407.6  270.32    5415  270.03
#Mann= 3 , 0 , 0
  4592.1     .05       0  4969.5    .035       0  5045.1     .05       0
Bank Sta=4969.5,5045.1
XS Rating Curve= 0 ,0
Exp/Cntr=0.3,0.1

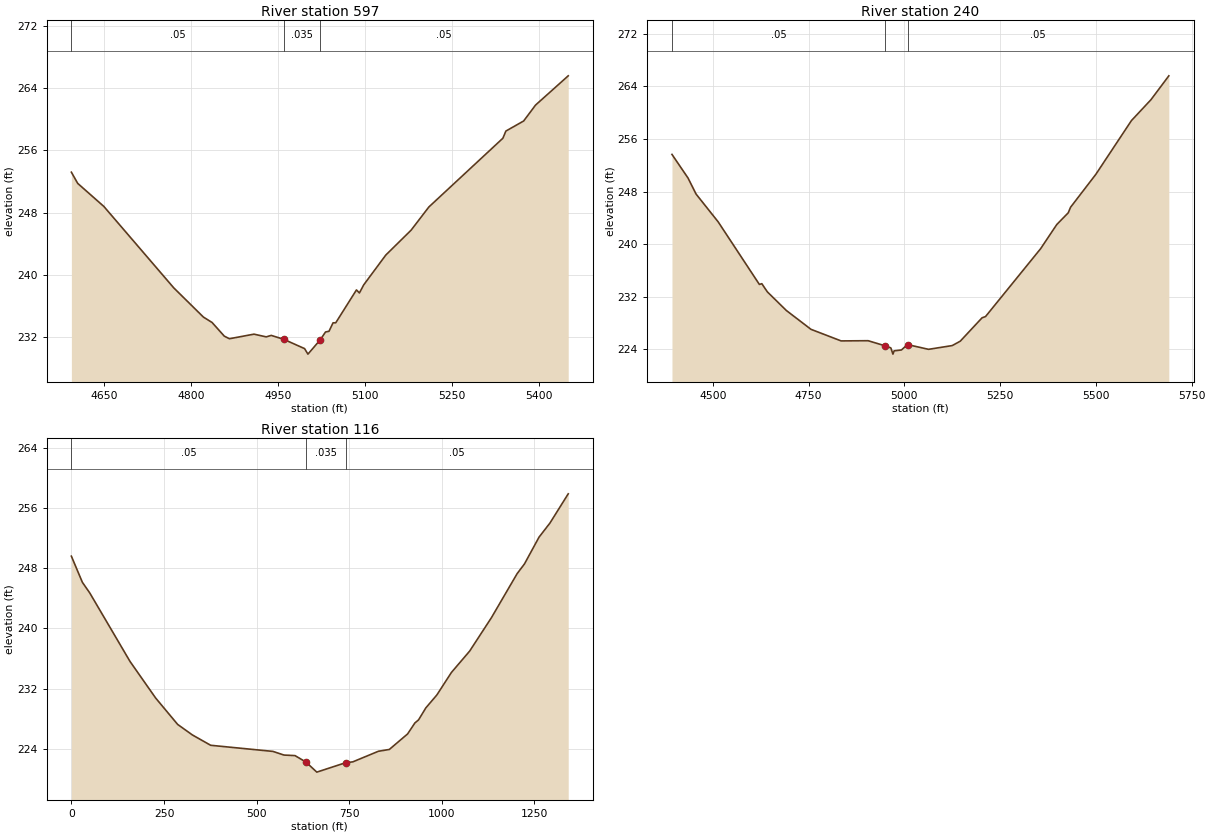
Type RM Length L Ch R = 1 ,597     ,357,357,357
BEGIN DESCRIPTION:
Mapping XS c6045685
END DESCRIPTION:
XS GIS Cut Line= 3
      3653565.06     10154212.59      3653944.84     10154464.33
      3654337.38     10154384.08
#Sta/Elev= 30
  4593.4  253.19  4604.3  251.75  4649.4  248.78  4769.8  238.31  4820.9  234.55
  4835.9  233.85    4857  232.09  4865.8  231.76  4908.1  232.35  4929.2     232
  4937.8  232.19  4959.3  231.69  4995.3  230.49  5001.1  229.78  5022.4  231.63
  5031.4  232.63  5037.4  232.72  5044.4  233.81    5049  233.81  5084.7  238.04
  5089.8  237.65  5097.3   238.7  5135.2  242.52  5178.9  245.73  5209.6  248.72
  5337.1  257.56  5342.2  258.48  5372.9  259.78  5393.3  261.82  5449.7  265.59
#Mann= 3 , 0 , 0
  4593.4     .05       0  4959.3    .035       0  5022.4     .05       0
Bank Sta=4959.3,5022.4
XS Rating Curve= 0 ,0
Exp/Cntr=0.3,0.1

Type RM Length L Ch R = 1 ,240     ,124,124,124
BEGIN DESCRIPTION:
UNT067 IN ROCK 1.0
END DESCRIPTION:
XS GIS Cut Line= 4
      3653432.26     10154302.22      3653771.23     10154733.43
      3653877.56     10154792.02      3654397.24     10154441.56
#Sta/Elev= 30
  4393.7  253.65  4435.7  250.05  4456.6  247.62  4514.3  243.39  4621.8  233.88
  4628.2  233.99  4642.6  232.75  4692.3  229.91  4756.5  227.05  4835.1  225.29
  4905.6  225.32  4948.9  224.56  4964.9  224.23  4970.4  223.28  4973.6  223.78
  4992.4  223.91  5008.5  224.73  5063.3  224.01  5125.1  224.58  5146.1  225.25
  5203.1  228.81    5212  228.99  5355.9  239.32    5398  242.99  5427.9  244.77
  5433.9  245.61  5499.9  250.62  5592.8  258.79  5643.8  261.97  5690.4   265.6
#Mann= 3 , 0 , 0
  4393.7     .05       0  4948.9    .035       0  5008.5     .05       0
Bank Sta=4948.9,5008.5
XS Rating Curve= 0 ,0
Exp/Cntr=0.3,0.1

Type RM Length L Ch R = 1 ,116     ,0,0,0
XS GIS Cut Line= 5
       3653354.3    10154403.481     3653767.712    10154885.252
      3653891.41     10154859.21     3654374.266     10154538.03
3654374.2661016410154538.0299324
#Sta/Elev= 30
       0249.620429.68605246.143849.47675244.7397158.3256 235.611 227.593230.7394
286.9651227.2301326.5465225.8377376.0233224.4577544.2442223.6429573.9302223.1576
603.6163223.0863633.3024222.2236662.4738220.8868740.2642222.1396759.7118 222.254
828.6943223.6622858.2582223.9042907.5314225.9679927.2407227.4316937.0954227.8377
956.8047229.4352986.3687231.14481025.787234.1466 1075.06236.99111134.188241.4667
1203.171 247.293 1222.88248.57831262.299252.15031291.863254.03351341.136257.9169
#Mann= 3 , 0 , 0
       0     .05       0633.3024    .035       0740.2642     .05       0
Bank Sta=633.3024,740.2642
XS Rating Curve= 0 ,0
Exp/Cntr=0.3,0.1

Chan Stop Cuts=-1
Use User Specified Reach Order=0
Composite Channel Slope=5