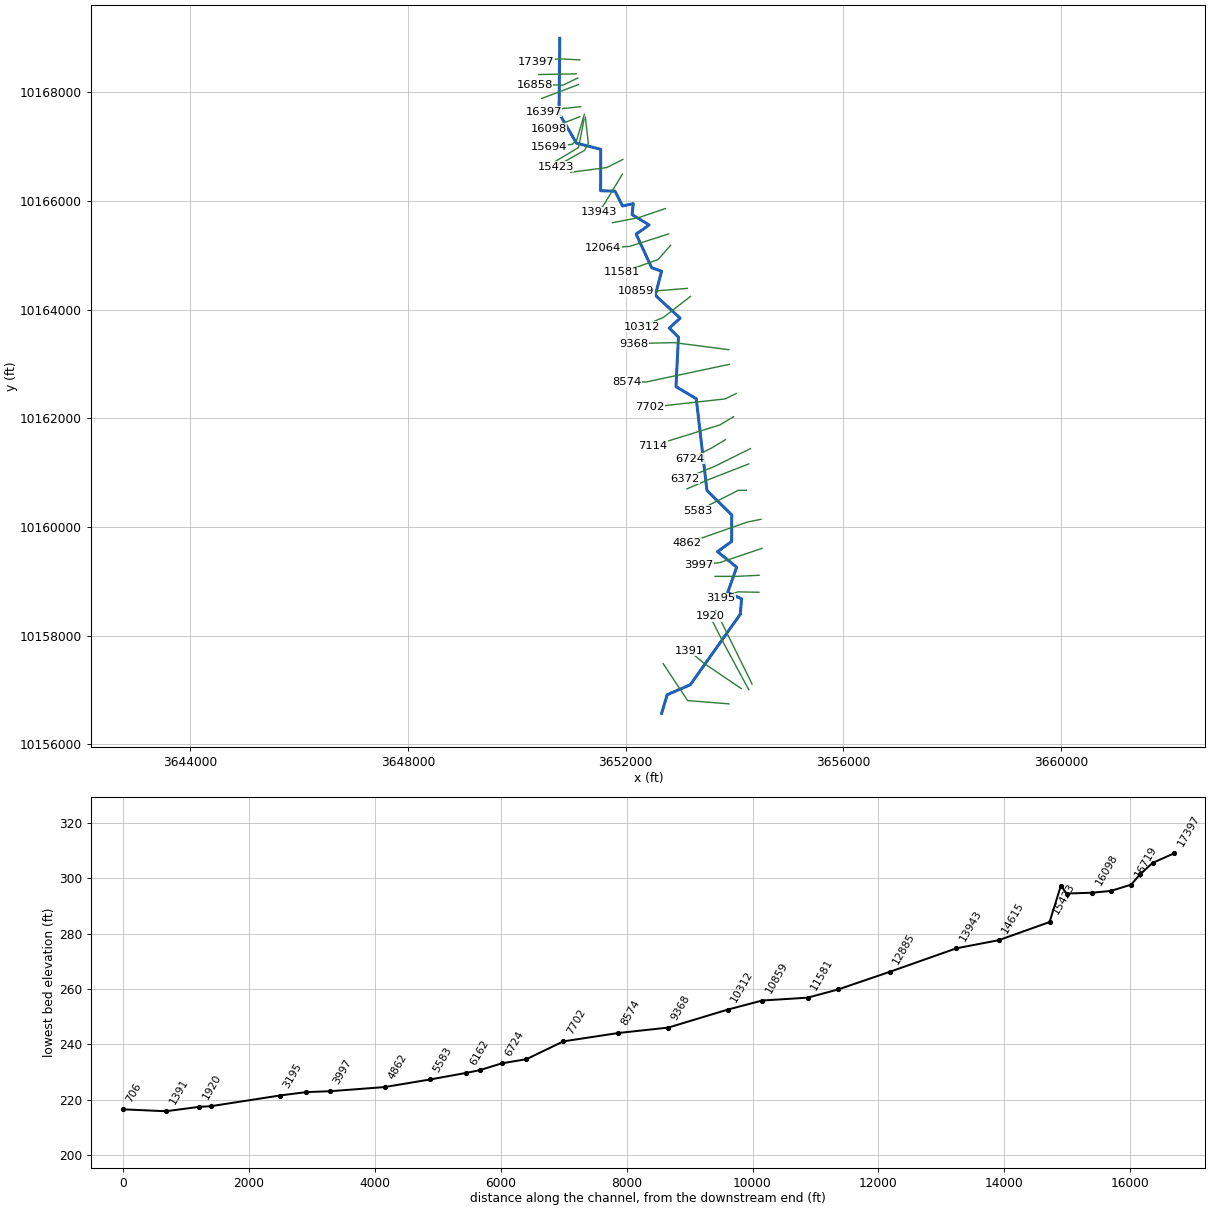
--- UNT068 IN ROCK.prj (project) ---

Proj Title=UNT068 IN ROCK Base Level Engineering
Current Plan=p01
Default Exp/Contr=0.3,0.1
English Units
Geom File=g01
Flow File=f01
Plan File=p01
Y Axis Title=Elevation
X Axis Title(PF)=Main Channel Distance
X Axis Title(XS)=Station
BEGIN DESCRIPTION:
UNT068 IN ROCK
END DESCRIPTION:
DSS Export Rating Curves= 0
DSS Export Rating Curve Sorted= 0
DSS Export Volume Flow Curves= 0
DXF OffsetX= 0
DXF OffsetY= 0
DXF ScaleX= 1
DXF ScaleY= 10

--- UNT068 IN ROCK.p01 (plan) ---

Plan Title=Multiple Run
Short Identifier=Multiple
Geom File=g01
Flow File=f01
Subcritical Flow
K Sum by GR= 0
Std Step Tol= 0.01
Critical Tol= 0.01
Num of Std Step Trials= 20
Max Error Tol= 0.3
Flow Tol Ratio= 0.001
Split Flow NTrial= 30
Split Flow Tol= 0.02
Split Flow Ratio= 0.02
Log Output Level= 0
Friction Slope Method= 1
Unsteady Friction Slope Method= 2
Unsteady Bridges Friction Slope Method= 1
Parabolic Critical Depth
Global Vel Dist=  1 , 1 , 1
Global Log Level= 0
CheckData=True
Encroach Param= -1, 0, 0, 0
BEGIN DESCRIPTION:
Multiple Run
END DESCRIPTION:

--- UNT068 IN ROCK.f01 (steady flow) ---

Flow Title=Multiple
Program Version=4.10
Number of Profiles= 7
Profile Names=10-year,25-year,50-year,1pct_min,100-year,1pct_plu,500-year
River Rch & RM=UNT068 IN ROCK,Reach-1         ,17397
     367     482     574     503     680     919     953
River Rch & RM=UNT068 IN ROCK,Reach-1         ,14615
     594     802     973     867    1172    1585    1701
River Rch & RM=UNT068 IN ROCK,Reach-1         ,10859
     764    1048    1285    1155    1562    2112    2310
River Rch & RM=UNT068 IN ROCK,Reach-1         ,9368
    1043    1445    1783    1611    2178    2946    3255
River Rch & RM=UNT068 IN ROCK,Reach-1         ,8574
    1043    1445    1783    1611    2178    2946    3255
Boundary for River Rch & Prof#=UNT068 IN ROCK,Reach-1         , 1
Up Type= 0
Dn Type= 3
Dn Slope=0.005
Boundary for River Rch & Prof#=UNT068 IN ROCK,Reach-1         , 2
Up Type= 0
Dn Type= 3
Dn Slope=0.005
Boundary for River Rch & Prof#=UNT068 IN ROCK,Reach-1         , 3
Up Type= 0
Dn Type= 3
Dn Slope=0.005
Boundary for River Rch & Prof#=UNT068 IN ROCK,Reach-1         , 4
Up Type= 0
Dn Type= 3
Dn Slope=0.005
Boundary for River Rch & Prof#=UNT068 IN ROCK,Reach-1         , 5
Up Type= 0
Dn Type= 3
Dn Slope=0.005
Boundary for River Rch & Prof#=UNT068 IN ROCK,Reach-1         , 6
Up Type= 0
Dn Type= 3
Dn Slope=0.005
Boundary for River Rch & Prof#=UNT068 IN ROCK,Reach-1         , 7
Up Type= 0
Dn Type= 3
Dn Slope=0.005
DSS Import GetInterval= 0
DSS Import GetPeak= 0
DSS Import FillOption= 0

--- UNT068 IN ROCK.g01 (geometry) ---

Geom Title=Existing Conditions
Program Version=4.10

River Reach=UNT068 IN ROCK  ,Reach-1
Reach XY= 30
       3650789.6     10168988.95      3650776.38     10167613.76
      3651095.49      10167060.4      3651542.78     10166948.18
      3651540.39     10166185.62      3651805.09     10166177.13
      3651943.54     10165904.95      3652140.09      10165947.9
      3652119.89      10165745.7      3652432.23      10165556.3
      3652194.01     10165387.24      3652478.21     10164770.35
      3652661.53     10164705.12       3652545.2     10164262.93
      3653002.11     10163841.64      3652801.81     10163657.98
      3652971.11     10163492.42      3652926.06     10162582.33
      3653298.65     10162360.49      3653494.96     10160672.39
      3653950.85     10160222.21      3653948.57     10159733.18
      3653689.57     10159546.92      3654041.13     10159260.46
       3653876.2     10158794.32      3654131.41     10158678.86
      3654108.84     10158396.75      3653188.81     10157097.89
      3652764.22     10156914.98      3652662.11     10156571.64

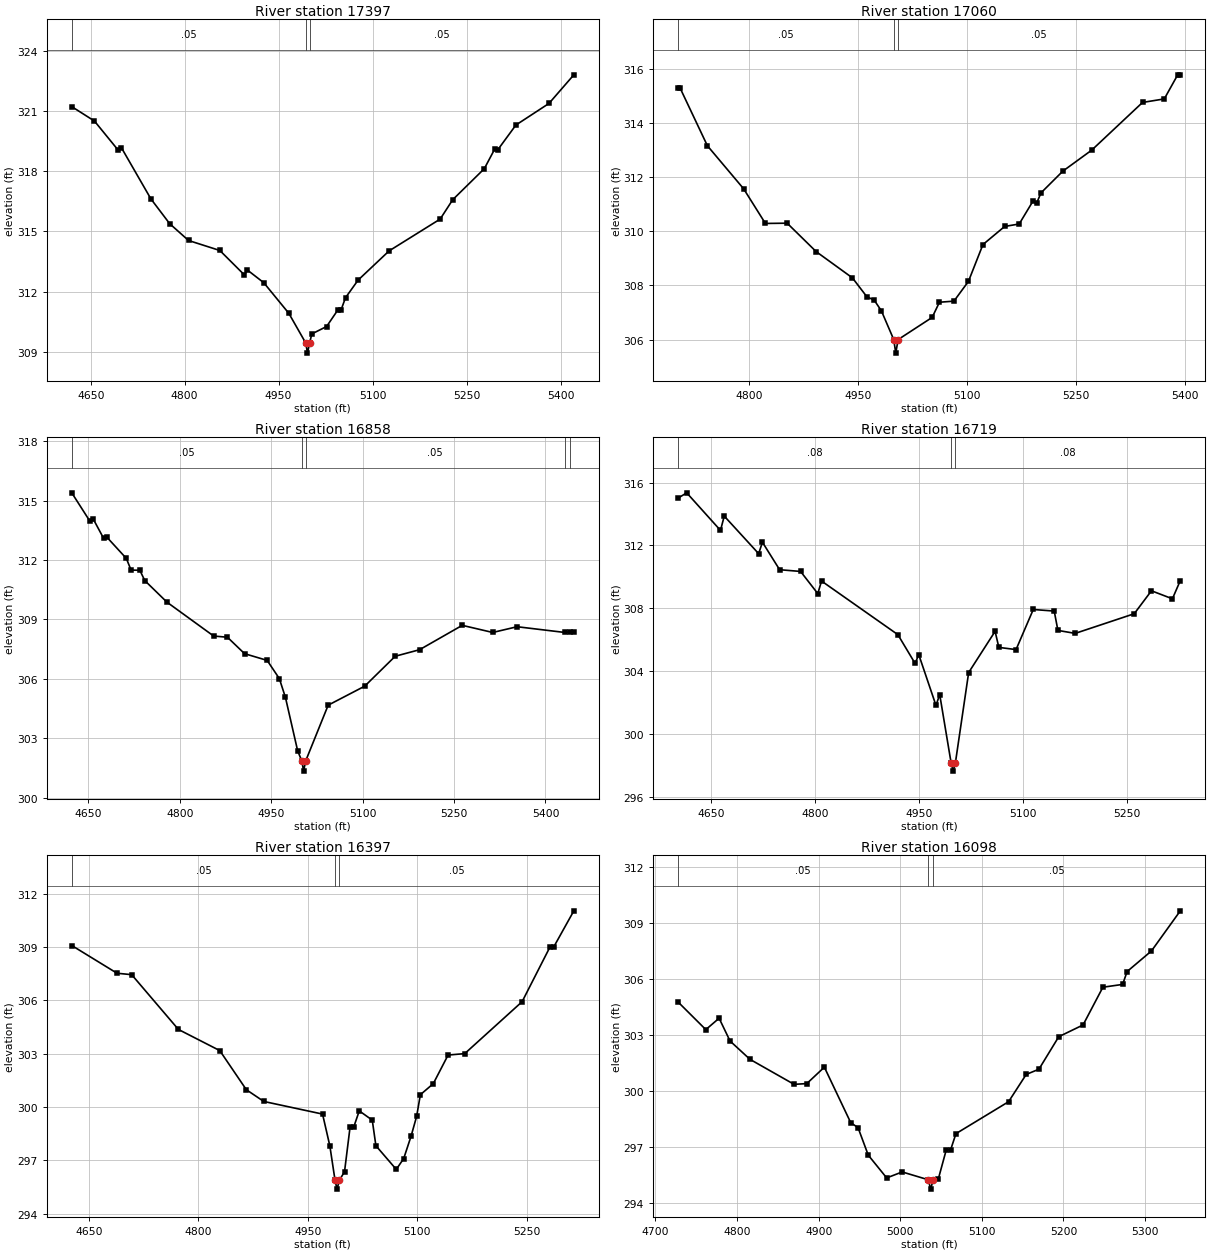
Type RM Length L Ch R = 1 ,17397   ,337,337,337
BEGIN DESCRIPTION:
UNT068 IN ROCK 35.0
END DESCRIPTION:
XS GIS Cut Line= 3
      3651158.23     10168592.82      3650773.94     10168611.84
      3650360.25     10168561.53
#Sta/Elev= 30
  4619.8  321.24    4656  320.52    4694  319.06    4699  319.19  4746.1  316.63
  4776.1  315.39  4806.2  314.55  4856.2  314.05  4895.3  312.83  4900.3  313.07
  4926.3  312.44  4966.3  310.91  4993.4  309.42  4996.1  308.92  4999.4  309.42
    5003  309.88  5026.6  310.25  5044.6  311.08  5049.7  311.08  5056.8  311.69
  5076.9  312.57  5126.4  314.03  5207.9  315.62    5228  316.59  5278.4  318.14
  5294.8  319.11  5299.8  319.08  5328.8  320.32  5381.6   321.4  5421.3  322.83
#Mann= 3 ,-1 , 0
  4619.8     .05       0  4993.4     .03       0  4999.4     .05       0
Bank Sta=4993.4,4999.4
XS Rating Curve= 0 ,0
Exp/Cntr=0.3,0.1

Type RM Length L Ch R = 1 ,17060   ,202,202,202
BEGIN DESCRIPTION:
Mapping XS e4d3197f
END DESCRIPTION:
XS GIS Cut Line= 2
      3651092.27     10168335.91      3650399.99     10168322.89
#Sta/Elev= 30
  4701.8  315.29  4704.4  315.29    4742  313.16    4792  311.57    4822  310.29
    4852   310.3    4892  309.25    4942  308.28    4962  307.58    4972  307.46
    4982  307.06    4999     306  5001.8   305.5    5005     306    5052  306.82
    5062  307.38    5082  307.42    5102  308.15    5122  309.51    5152  310.18
    5172  310.27  5190.9  311.11  5195.9  311.03  5202.1  311.42  5232.1  312.22
  5272.1     313  5342.1  314.76  5372.1  314.89  5390.6  315.78  5394.2  315.78
#Mann= 3 ,-1 , 0
  4701.8     .05       0    4999     .03       0    5005     .05       0
Bank Sta=4999,5005
XS Rating Curve= 0 ,0
Exp/Cntr=0.3,0.1

Type RM Length L Ch R = 1 ,16858   ,139,139,139
BEGIN DESCRIPTION:
UNT068 IN ROCK 34.0
END DESCRIPTION:
XS GIS Cut Line= 3
      3651122.67     10168259.97      3650851.72     10168128.83
      3650329.04     10168139.09
#Sta/Elev= 30
  4622.8  315.39  4652.3  313.97  4657.8  314.08  4674.9   313.1  4680.4  313.15
  4712.3  312.08  4720.1  311.49  4734.5  311.48  4742.6  310.96    4779  309.87
  4855.6  308.16  4878.2   308.1  4906.3  307.27  4943.4  306.93  4963.4  306.01
  4973.4  305.06  4993.4  302.37  5000.4  301.84  5003.2  301.34  5006.4  301.84
  5043.5  304.67  5103.5  305.63  5153.5  307.14  5193.5  307.47  5263.5   308.7
  5313.5  308.34  5353.5  308.63  5431.9  308.34  5441.1  308.37  5446.6  308.37
#Mann= 5 ,-1 , 0
  4622.8     .05       0  5000.4     .03       0  5006.4     .05       0
  5431.9     .08       0  5441.1     .05       0
Bank Sta=5000.4,5006.4
XS Rating Curve= 0 ,0
Exp/Cntr=0.3,0.1

Type RM Length L Ch R = 1 ,16719   ,322,322,322
BEGIN DESCRIPTION:
Mapping XS 8108e6c1
END DESCRIPTION:
XS GIS Cut Line= 2
       3651133.5     10168138.43      3650456.78      10167882.5
#Sta/Elev= 30
  4603.1  315.02  4615.3  315.35    4664  312.96  4669.4  313.87    4719  311.48
  4724.4  312.21  4749.2  310.46  4779.4  310.35  4804.2  308.94  4809.6  309.74
  4919.6  306.33  4944.4   304.5  4949.7  305.06  4974.5  301.83  4979.9  302.52
  4996.4  298.15  4999.1  297.65  5002.4  298.15  5021.6  303.92  5059.7  306.54
  5065.1  305.52  5089.9  305.38  5114.7  307.93  5144.9  307.83  5150.2   306.6
  5175.1  306.41  5260.2  307.66    5285  309.12  5315.2  308.61  5326.6  309.77
#Mann= 3 ,-1 , 0
  4603.1     .08       0  4996.4     .07       0  5002.4     .08       0
Bank Sta=4996.4,5002.4
XS Rating Curve= 0 ,0
Exp/Cntr=0.3,0.1

Type RM Length L Ch R = 1 ,16397   ,299,299,299
BEGIN DESCRIPTION:
UNT068 IN ROCK 33.0
END DESCRIPTION:
XS GIS Cut Line= 3
       3651173.8     10167731.76      3650792.11     10167691.64
      3650492.14     10167641.65
#Sta/Elev= 30
  4626.6  309.08  4688.6  307.52  4708.7  307.44  4772.7  304.36  4829.4  303.17
  4865.8  300.97  4889.7  300.31  4970.2   299.6  4980.2  297.81  4987.3  295.88
    4990  295.38  4993.3  295.88  5000.3  296.36  5007.9  298.87  5012.9  298.87
  5020.5  299.78  5038.3  299.26  5043.3  297.82  5071.2  296.49  5081.4   297.1
  5091.5  298.36  5099.1  299.47  5104.2  300.69  5121.9  301.31  5142.2  302.92
    5165     303  5243.6  305.92  5281.6  308.98  5286.7  308.98  5314.5  311.03
#Mann= 3 ,-1 , 0
  4626.6     .05       0  4987.3     .03       0  4993.3     .05       0
Bank Sta=4987.3,4993.3
XS Rating Curve= 0 ,0
Exp/Cntr=0.3,0.1

Type RM Length L Ch R = 1 ,16098   ,404,404,404
BEGIN DESCRIPTION:
Mapping XS 8c31892f
END DESCRIPTION:
XS GIS Cut Line= 2
      3651158.68     10167549.03       3650586.4     10167322.72
#Sta/Elev= 30
  4727.9  304.74  4761.7  303.27    4778  303.88  4791.4  302.66  4815.8  301.68
  4869.9  300.34  4885.5  300.38    4907  301.26  4939.3  298.29  4948.3  298.02
  4960.8  296.55  4983.4  295.33  5002.4  295.65  5034.5  295.23  5037.2  294.73
  5040.5  295.23  5046.8  295.29  5056.4  296.83  5061.8  296.84  5068.3   297.7
  5132.8  299.41  5154.4  300.87    5170  301.15  5194.3  302.89  5224.1  303.52
  5248.4  305.54  5272.6  305.69  5278.1  306.38  5307.9  307.48  5343.3  309.63
#Mann= 3 ,-1 , 0
  4727.9     .05       0  5034.5     .03       0  5040.5     .05       0
Bank Sta=5034.5,5040.5
XS Rating Curve= 0 ,0
Exp/Cntr=0.3,0.1

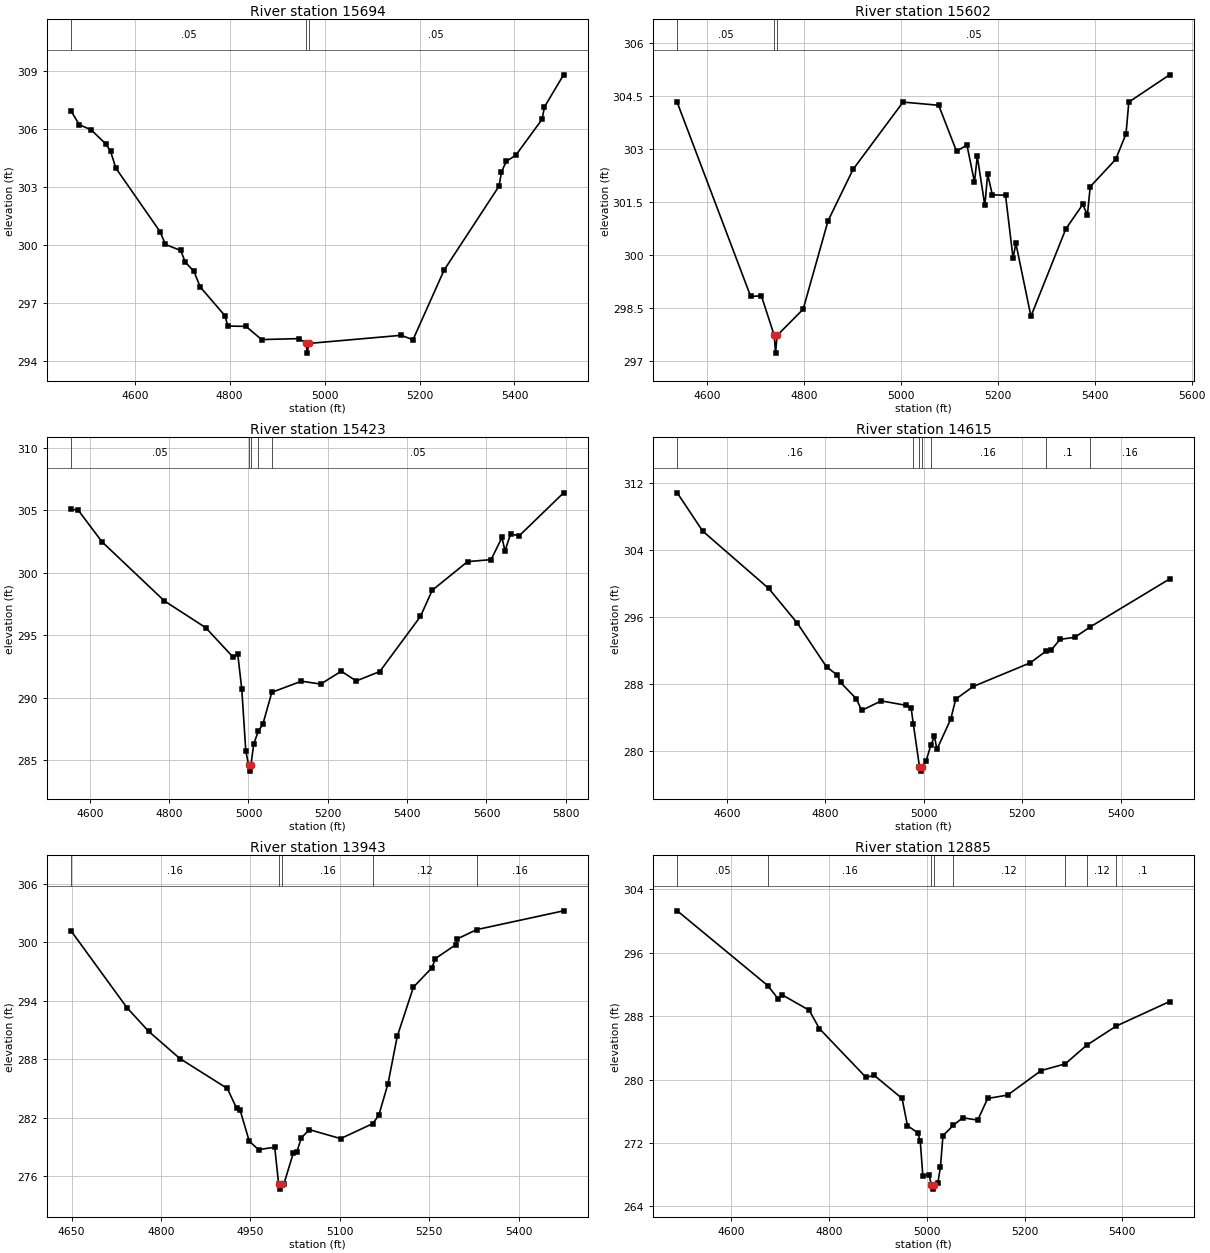
Type RM Length L Ch R = 1 ,15694   ,92,92,92
BEGIN DESCRIPTION:
UNT068 IN ROCK 31.0
END DESCRIPTION:
XS GIS Cut Line= 4
      3651242.11     10167591.66      3651098.77     10167114.13
      3651015.44      10167038.6      3650592.08     10166991.64
#Sta/Elev= 30
  4466.4  306.92    4483  306.23  4508.2  305.96  4539.5  305.22  4549.1  304.85
  4560.4  303.98  4653.4   300.7  4664.8  300.04  4696.9  299.73  4706.6  299.13
  4724.8  298.65  4737.9  297.85  4790.1  296.36  4796.1  295.83  4834.4  295.81
  4867.4  295.13  4946.7  295.18  4960.7  294.93  4963.4  294.43  4966.7  294.93
  5161.3  295.35  5186.2  295.12  5251.8  298.72  5367.4  303.05  5372.6  303.78
  5382.6  304.33  5402.8  304.65  5458.1   306.5  5463.1  307.14  5503.4   308.8
#Mann= 3 ,-1 , 0
  4466.4     .05       0  4960.7    .033       0  4966.7     .05       0
Bank Sta=4960.7,4966.7
XS Rating Curve= 0 ,0
Exp/Cntr=0.3,0.1

Type RM Length L Ch R = 1 ,15602   ,179,179,179
BEGIN DESCRIPTION:
Mapping XS 4f4619d9
END DESCRIPTION:
XS GIS Cut Line= 3
      3651236.79     10167502.15      3651135.23     10166981.31
      3650718.52     10166731.29
#Sta/Elev= 30
  4537.7  304.31  4689.4  298.83  4711.4  298.85    4738  297.73  4740.7  297.23
    4744  297.73  4797.7  298.47  4849.2  300.97  4900.8  302.42    5004  304.32
  5077.6  304.23  5114.5  302.93  5135.9  303.11  5151.5  302.06  5157.3  302.79
  5172.9   301.4  5178.7  302.28  5188.4   301.7  5215.6  301.69  5231.2  299.91
    5237  300.33  5268.1  298.27  5340.2  300.74  5375.2  301.43  5384.7  301.13
  5390.5  301.93    5443   302.7  5464.4  303.42  5470.2  304.32  5554.3  305.09
#Mann= 3 ,-1 , 0
  4537.7     .05       0    4738     .03       0    4744     .05       0
Bank Sta=4738,4744
XS Rating Curve= 0 ,0
Exp/Cntr=0.3,0.1

Type RM Length L Ch R = 1 ,15423   ,808,808,808
BEGIN DESCRIPTION:
Mapping XS 43d4a471
END DESCRIPTION:
XS GIS Cut Line= 4
      3651260.23      10167538.6      3651314.91     10167062.04
      3651247.21     10166929.23      3650713.33     10166629.74
#Sta/Elev= 30
  4553.4  305.07  4570.5  305.02  4630.9  302.47    4788  297.75  4892.6   295.6
  4961.3  293.25  4973.1  293.47  4983.2  290.69  4993.2  285.78  5000.3  284.64
    5003  284.14  5006.3  284.64  5013.4  286.33    5025  287.34  5036.1  287.87
  5058.9  290.44  5133.6  291.33  5182.2   291.1    5234  292.13  5271.6  291.35
  5330.9   292.1  5433.6  296.51  5463.2   298.6  5552.3  300.89  5611.6  301.05
    5639  302.82  5646.6  301.75  5660.7   303.1  5682.4  302.95  5794.3  306.39
#Mann= 5 ,-1 , 0
  4553.4     .05       0  5000.3     .03       0  5006.3     .05       0
    5025      .1       0  5058.9     .05       0
Bank Sta=5000.3,5006.3
XS Rating Curve= 0 ,0
Exp/Cntr=0.3,0.1

Type RM Length L Ch R = 1 ,14615   ,672,672,672
BEGIN DESCRIPTION:
UNT068 IN ROCK 30.0
END DESCRIPTION:
XS GIS Cut Line= 3
      3651950.48     10166761.11      3651650.44     10166611.09
      3650991.47     10166525.16
#Sta/Elev= 30
  4499.4  310.88    4551  306.31  4685.2  299.44  4743.5  295.28  4802.6  290.06
  4824.9  289.07  4831.1   288.2  4863.4  286.23  4873.9  284.85  4913.8  285.99
  4964.3  285.46  4974.4  285.18  4978.9  283.27  4991.5  278.09  4994.3  277.59
  4997.5  278.09  5004.6  278.75  5014.4  280.66  5021.8  281.76  5026.9   280.2
    5055  283.81  5065.1   286.2  5100.8  287.72  5216.4  290.54  5248.1  291.93
  5258.8  292.05  5276.9  293.35  5307.1   293.6    5338  294.83  5499.4  300.57
#Mann= 7 ,-1 , 0
  4499.4     .16       0  4978.9      .1       0  4991.5     .07       0
  4997.5      .1       0  5014.4     .16       0  5248.1      .1       0
    5338     .16       0
Bank Sta=4991.5,4997.5
XS Rating Curve= 0 ,0
Exp/Cntr=0.3,0.1

Type RM Length L Ch R = 1 ,13943   ,1058,1058,1058
BEGIN DESCRIPTION:
UNT068 IN ROCK 29.0
END DESCRIPTION:
XS GIS Cut Line= 3
      3651942.09     10166491.62      3651607.38     10165939.91
      3651507.37     10165789.89
#Sta/Elev= 30
  4649.5  301.16    4743  293.29  4779.4  290.86  4831.7  288.07  4911.2     285
  4926.7  282.98  4932.5   282.8    4948  279.58  4963.5  278.72  4990.7  278.96
  4997.3  275.16  5000.1  274.66  5003.3  275.16  5006.2  275.22  5021.7  278.34
  5027.5  278.43  5035.4  279.94  5048.8  280.77  5101.2  279.85  5155.1  281.39
  5165.2  282.25  5180.7   285.5  5196.1  290.34  5223.3  295.41  5254.3   297.4
  5260.2  298.35  5294.8  299.79    5297  300.37  5329.5  301.32  5475.1  303.25
#Mann= 5 ,-1 , 0
  4649.5     .16       0  4997.3     .07       0  5003.3     .16       0
  5155.1     .12       0  5329.5     .16       0
Bank Sta=4997.3,5003.3
XS Rating Curve= 0 ,0
Exp/Cntr=0.3,0.1

Type RM Length L Ch R = 1 ,12885   ,821,821,821
BEGIN DESCRIPTION:
UNT068 IN ROCK 27.0
END DESCRIPTION:
XS GIS Cut Line= 3
      3652727.57     10165856.75      3652242.11     10165691.64
      3651756.99     10165596.66
#Sta/Elev= 30
  4489.4  301.28  4674.5  291.85  4695.9  290.17  4704.1  290.68  4759.2  288.74
  4780.4  286.41  4875.4  280.28  4892.4  280.52  4949.4  277.61  4960.4  274.17
  4981.1  273.29  4986.5  272.28  4991.8  267.85  5004.7  267.94  5009.4  266.67
  5012.1  266.17  5015.4  266.67  5022.6  266.99  5027.9  268.99    5033  272.91
  5054.5  274.24  5073.5  275.17  5104.1  274.88  5124.5  277.61  5165.2  278.03
  5233.9  281.13  5283.1  281.97  5326.7  284.31  5387.7  286.75  5496.5  289.83
#Mann= 8 ,-1 , 0
  4489.4     .05       0  4674.5     .16       0  5009.4     .07       0
  5015.4     .16       0  5054.5     .12       0  5283.1     .16       0
  5326.7     .12       0  5387.7      .1       0
Bank Sta=5009.4,5015.4
XS Rating Curve= 0 ,0
Exp/Cntr=0.3,0.1

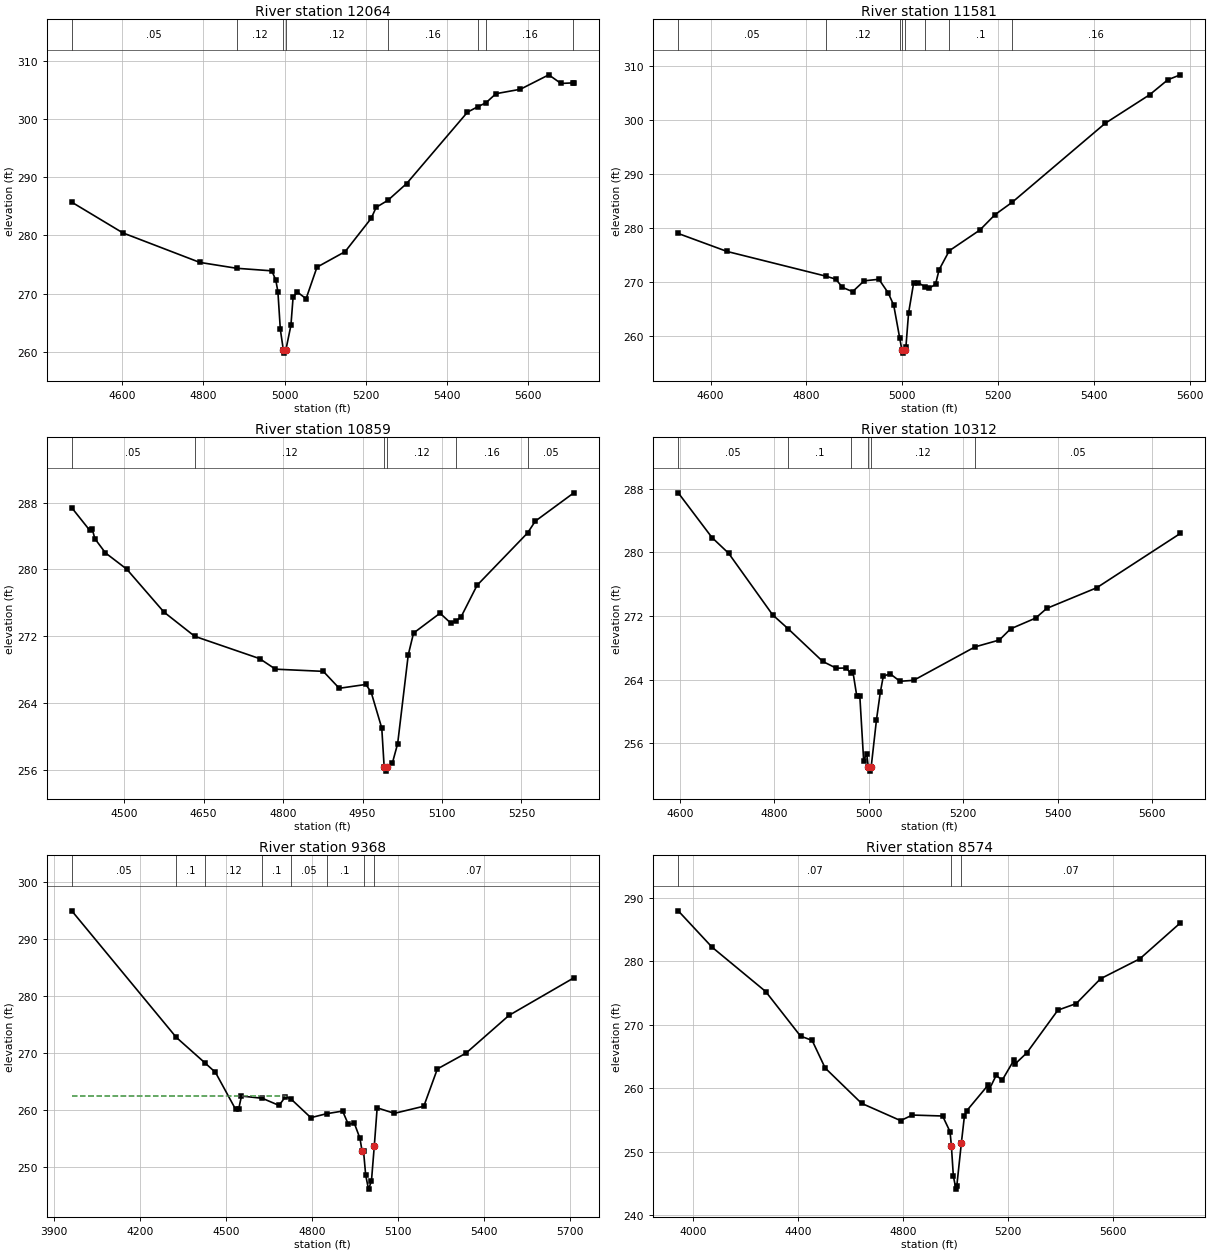
Type RM Length L Ch R = 1 ,12064   ,483,483,483
BEGIN DESCRIPTION:
UNT068 IN ROCK 26.0
END DESCRIPTION:
XS GIS Cut Line= 3
      3652792.13     10165391.65      3652076.55     10165162.32
      3651590.42     10165127.59
#Sta/Elev= 30
  4475.1  285.72  4601.1  280.45  4790.9  275.38    4882  274.37  4968.7  273.93
  4978.5  272.34  4983.7  270.35  4989.7  263.86  4997.2   260.3  4999.9   259.8
  5003.2   260.3  5015.8  264.57  5021.2  269.42  5031.7  270.29  5053.2  269.14
  5080.1  274.56  5149.6  277.23  5213.9  282.95  5226.2  284.84  5255.1  286.04
  5301.2  288.91  5451.5  301.18  5476.2  302.09  5496.9  302.78  5521.7  304.35
  5581.9  305.11  5652.1  307.59  5682.1  306.11  5712.8  306.21  5713.9  306.21
#Mann= 8 ,-1 , 0
  4475.1     .05       0    4882     .12       0  4997.2     .07       0
  5003.2     .12       0  5255.1     .16       0  5476.2     .05       0
  5496.9     .16       0  5712.8      .1       0
Bank Sta=4997.2,5003.2
XS Rating Curve= 0 ,0
Exp/Cntr=0.3,0.1

Type RM Length L Ch R = 1 ,11581   ,722,722,722
BEGIN DESCRIPTION:
UNT068 IN ROCK 24.0
END DESCRIPTION:
XS GIS Cut Line= 3
      3652826.81     10165180.56      3652597.39     10164919.26
      3651937.71      10164684.9
#Sta/Elev= 30
  4532.4     279  4634.4  275.67    4840  271.11  4861.2  270.54  4875.2  269.01
  4896.3  268.23  4920.4  270.23  4951.2  270.52  4970.6  267.99  4982.1  265.72
  4994.7  259.58  4999.3  257.34  5002.1  256.84  5005.3  257.34  5007.6  258.05
  5013.1  264.27  5023.7  269.86  5033.2  269.91    5048  269.06  5055.5  268.85
  5069.3  269.57  5076.8  272.28    5098   275.8  5161.9  279.64  5193.5  282.49
  5229.6   284.8  5423.6  299.42  5516.2   304.7  5554.3  307.48  5580.2  308.39
#Mann= 8 ,-1 , 0
  4532.4     .05       0    4840     .12       0  4994.7      .1       0
  4999.3     .07       0  5005.3      .1       0    5048     .12       0
    5098      .1       0  5229.6     .16       0
Bank Sta=4999.3,5005.3
XS Rating Curve= 0 ,0
Exp/Cntr=0.3,0.1

Type RM Length L Ch R = 1 ,10859   ,547,547,547
BEGIN DESCRIPTION:
UNT068 IN ROCK 23.0
END DESCRIPTION:
XS GIS Cut Line= 3
      3653135.55     10164389.74      3652542.11     10164341.64
      3652189.42     10164337.66
#Sta/Elev= 30
  4400.9  287.38  4434.4  284.71  4439.4  284.87  4444.5  283.67  4464.5  281.97
  4504.7  280.02  4574.9  274.88  4633.1  271.97  4755.5   269.3  4785.6  268.03
  4875.9  267.77    4906  265.74  4956.2   266.2  4966.2  265.28  4986.3  260.97
  4990.8  256.31  4993.5  255.81  4996.8  256.31  5006.3  256.77  5016.3  259.11
  5036.3  269.75  5046.3  272.36  5096.3  274.74  5116.3  273.57  5126.6   273.8
  5136.3  274.33  5166.3  278.09  5261.6  284.36  5276.3  285.78    5349  289.17
#Mann= 6 ,-1 , 0
  4400.9     .05       0  4633.1     .12       0  4990.8     .07       0
  4996.8     .12       0  5126.6     .16       0  5261.6     .05       0
Bank Sta=4990.8,4996.8
XS Rating Curve= 0 ,0
Exp/Cntr=0.3,0.1

Type RM Length L Ch R = 1 ,10312   ,944,944,944
BEGIN DESCRIPTION:
UNT068 IN ROCK 22.0
END DESCRIPTION:
XS GIS Cut Line= 3
      3653192.07     10164241.61      3652698.16       10163857.
      3652295.32     10163687.36
#Sta/Elev= 30
  4596.8  287.47  4668.2  281.86  4703.5  279.88  4796.7  272.15    4829  270.43
  4902.6  266.31  4931.5  265.45  4952.3  265.48  4962.2  264.83  4966.8  264.95
  4974.9  261.94  4981.3  261.95  4989.4  253.85  4995.8  254.72  4999.3  253.03
  5002.1  252.53  5005.3  253.03  5016.6     259  5024.7  262.43    5031  264.45
  5045.5  264.75  5066.3  263.81  5095.3  263.93  5225.3  268.13  5276.7  268.99
  5300.5  270.39  5353.4  271.74  5377.1  272.96  5482.9  275.55  5659.9  282.37
#Mann= 6 ,-1 , 0
  4596.8     .05       0    4829      .1       0  4962.2     .12       0
  4999.3     .07       0  5005.3     .12       0  5225.3     .05       0
Bank Sta=4999.3,5005.3
XS Rating Curve= 0 ,0
Exp/Cntr=0.3,0.1

Type RM Length L Ch R = 1 ,9368    ,794,794,794
BEGIN DESCRIPTION:
UNT068 IN ROCK 20.0
END DESCRIPTION:
XS GIS Cut Line= 3
      3653899.51     10163261.27      3652892.11     10163391.64
      3652155.91     10163374.15
#Sta/Elev= 30
  3962.5  294.99  4327.3  272.73  4427.4  268.24    4464  266.57  4534.6  260.05
  4544.7  260.07  4554.8  262.41  4627.4  262.02  4685.9  260.76  4708.3   262.3
  4727.4   261.9  4796.8  258.61  4851.5   259.3  4907.7  259.77  4927.9  257.41
  4948.1  257.69  4968.2  254.98  4975.8  252.69  4980.8  252.69  4988.3  248.47
  4998.1  246.04  5008.3  247.43  5018.3  253.63  5028.3  260.34  5088.3  259.37
  5191.1  260.62  5238.4  267.18  5338.4  269.96  5488.4   276.6  5714.7   283.2
#Mann= 8 ,-1 , 0
  3962.5     .05       0  4327.3      .1       0  4427.4     .12       0
  4627.4      .1       0  4727.4     .05       0  4851.5      .1       0
  4980.8     .07       0  5018.3     .07       0
#XS Ineff= 2 , 0
         4711.65  262.45
Permanent Ineff=
       F       F
Bank Sta=4975.8,5018.3
XS Rating Curve= 0 ,0
Exp/Cntr=0.3,0.1

Type RM Length L Ch R = 1 ,8574    ,872,872,872
BEGIN DESCRIPTION:
UNT068 IN ROCK 18.0
END DESCRIPTION:
XS GIS Cut Line= 3
      3653908.16     10162992.18      3652377.87     10162667.68
      3652027.89     10162667.68
#Sta/Elev= 30
  3942.2  287.96  4071.1  282.23  4275.5  275.24  4408.4  268.21  4452.7  267.53
  4502.3  263.18  4641.1  257.61  4790.1  254.88  4834.6  255.76  4950.2  255.61
  4978.5  253.14  4983.6  250.92  4991.1  246.18    5001  244.08  5004.3  244.58
  5021.7  251.35  5033.3  255.59  5042.2  256.44  5122.4  260.42  5127.5  259.76
  5154.6  262.03  5177.1  261.24  5221.7  264.39  5226.8  263.82  5271.3  265.57
  5389.7   272.3  5459.8  273.34  5552.3  277.25  5702.3   280.4  5856.5  286.05
#Mann= 3 , 0 , 0
  3942.2     .07       0  4983.6     .05       0  5021.7     .07       0
Bank Sta=4983.6,5021.7
XS Rating Curve= 0 ,0
Exp/Cntr=0.3,0.1

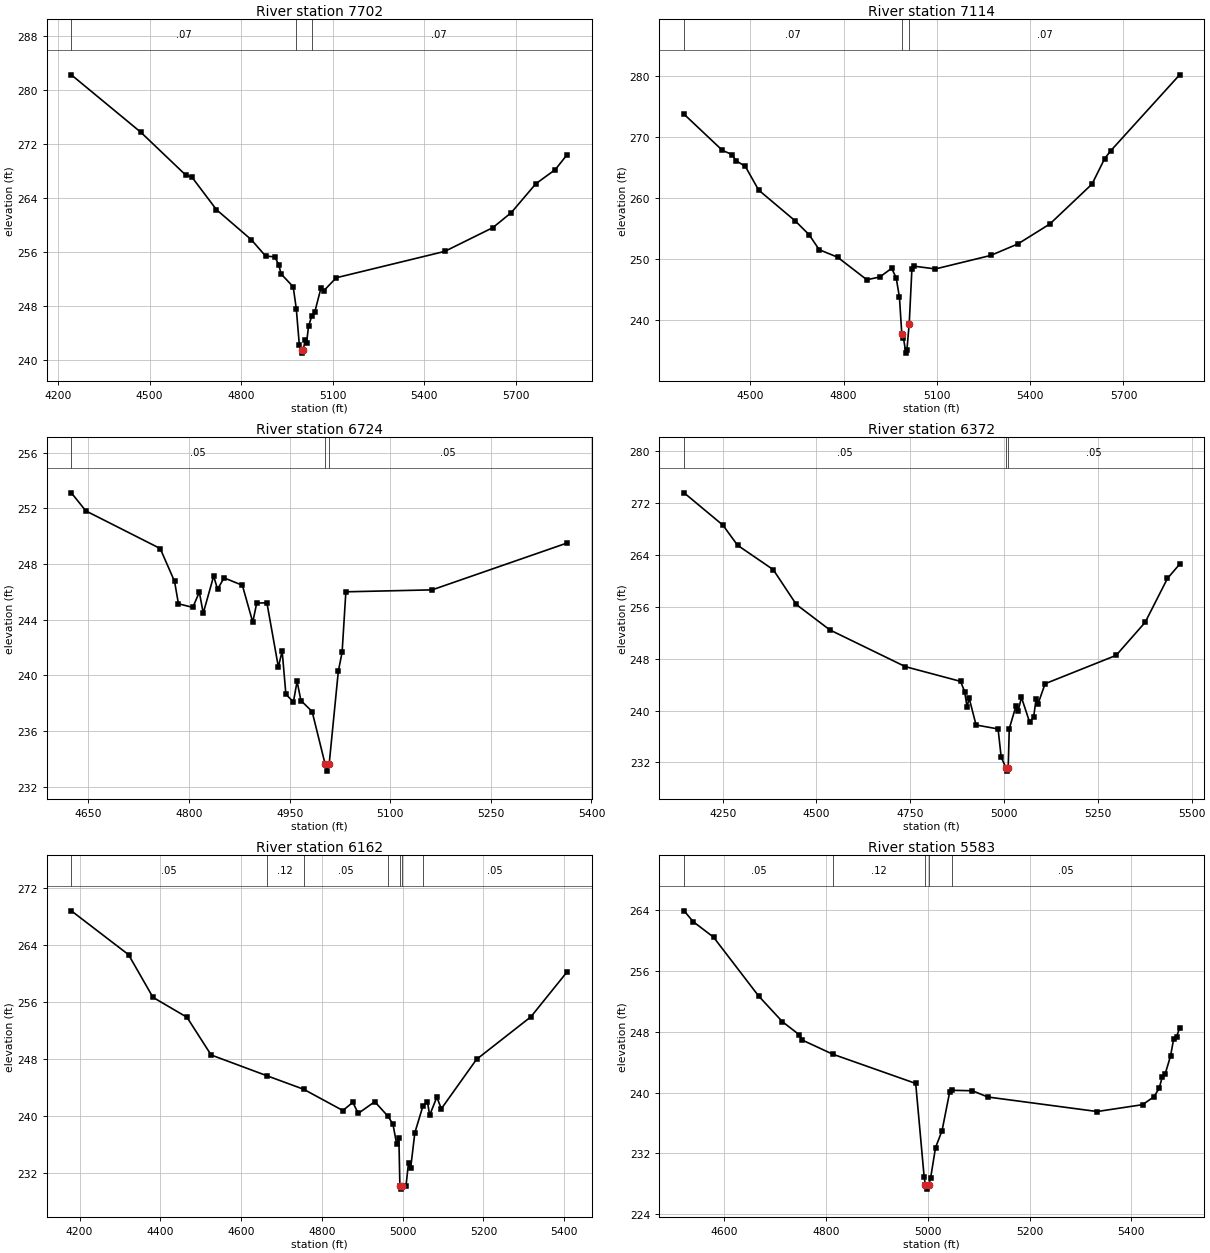
Type RM Length L Ch R = 1 ,7702    ,588,588,588
BEGIN DESCRIPTION:
UNT068 IN ROCK 17.0
END DESCRIPTION:
XS GIS Cut Line= 3
      3654032.34      10162456.9      3653832.38     10162356.92
      3652441.12     10162202.25
#Sta/Elev= 30
  4243.3   282.2  4470.8  273.72  4618.1  267.38  4638.2  267.09  4718.7  262.27
  4832.9  257.83  4879.7  255.41  4909.9  255.29  4923.4  254.07    4930  252.79
  4970.2  250.86  4980.3  247.62  4990.3  242.24  4997.4  241.56  5000.2  241.06
  5003.4  241.56  5008.9  242.93  5013.9  242.58  5020.5  245.05  5030.6  246.48
  5040.7  247.11  5060.8  250.63  5070.8   250.3  5111.1   252.2  5466.6   256.1
  5624.2  259.61  5684.6  261.83  5765.1   266.1  5828.7  268.19  5866.7  270.35
#Mann= 3 ,-1 , 0
  4243.3     .07       0  4980.3     .07       0  5030.6     .07       0
Bank Sta=4997.4,5003.4
XS Rating Curve= 0 ,0
Exp/Cntr=0.3,0.1

Type RM Length L Ch R = 1 ,7114    ,390,390,390
BEGIN DESCRIPTION:
UNT068 IN ROCK 16.0
END DESCRIPTION:
XS GIS Cut Line= 3
      3653984.78     10162028.77      3653734.81      10161878.8
      3652492.13     10161491.65
#Sta/Elev= 30
  4287.4  273.73  4410.6  267.81  4441.7  267.13  4453.8  266.15  4484.4  265.18
  4527.2  261.31  4644.6  256.27  4689.4     254  4721.9  251.55  4780.7  250.33
    4875  246.63  4916.9  247.09  4954.8  248.51  4969.3  246.94  4979.8  243.75
  4987.3  237.77  4992.5  237.17  5000.5  234.62  5003.7  235.12  5011.2  239.46
  5019.8  248.37    5025  248.87  5095.3   248.4    5273  250.61  5360.7   252.5
  5463.5  255.77  5598.9   262.3  5639.6  266.47  5658.7  267.73  5880.5  280.18
#Mann= 3 , 0 , 0
  4287.4     .07       0  4987.3     .07       0  5011.2     .07       0
Bank Sta=4987.3,5011.2
XS Rating Curve= 0 ,0
Exp/Cntr=0.3,0.1

Type RM Length L Ch R = 1 ,6724    ,352,352,352
BEGIN DESCRIPTION:
UNT068 IN ROCK 15.0
END DESCRIPTION:
XS GIS Cut Line= 3
      3653837.47      10161606.8      3653587.43     10161456.78
      3653187.43     10161256.78
#Sta/Elev= 30
  4624.5  253.12  4646.2  251.82    4757  249.12  4778.4  246.76  4784.2  245.15
  4805.7  244.89  4815.3  245.99  4821.2  244.48  4836.7  247.14  4842.5   246.2
  4852.3  247.01  4879.5  246.48    4895  243.83  4900.9   245.2  4916.1  245.22
  4933.2   240.6  4938.8  241.77  4944.4  238.65  4955.6   238.1  4961.1  239.58
  4966.8   238.2  4983.5  237.41  5002.9  233.63  5005.6  233.13  5008.9  233.63
  5022.6  240.32  5028.2  241.66  5033.8  246.01  5162.4  246.15  5363.3  249.51
#Mann= 3 ,-1 , 0
  4624.5     .05       0  5002.9     .03       0  5008.9     .05       0
Bank Sta=5002.9,5008.9
XS Rating Curve= 0 ,0
Exp/Cntr=0.3,0.1

Type RM Length L Ch R = 1 ,6372    ,210,210,210
BEGIN DESCRIPTION:
UNT068 IN ROCK 14.0
END DESCRIPTION:
XS GIS Cut Line= 3
      3654292.12     10161441.65      3653650.62      10161121.2
      3653092.13     10160891.65
#Sta/Elev= 30
  4147.1  273.55  4250.6  268.57  4289.7  265.47  4384.8  261.71  4446.3  256.34
  4535.7  252.42    4737  246.76  4884.2  244.49    4895  242.89  4901.4  240.54
  4906.9  241.93  4925.4  237.77  4984.1  237.16  4992.3  232.83  5005.1  231.16
  5007.9  230.66  5011.1  231.16  5013.9  237.21  5032.1  240.74  5037.5  239.93
  5046.4  242.02    5068  238.24  5078.8  238.95  5085.4   241.8  5090.8  241.06
  5109.4  244.13  5298.7   248.5    5376  253.58  5435.6  260.36    5468  262.55
#Mann= 3 ,-1 , 0
  4147.1     .05       0  5005.1     .03       0  5011.1     .05       0
Bank Sta=5005.1,5011.1
XS Rating Curve= 0 ,0
Exp/Cntr=0.3,0.1

Type RM Length L Ch R = 1 ,6162    ,579,579,579
BEGIN DESCRIPTION:
UNT068 IN ROCK 13.0
END DESCRIPTION:
XS GIS Cut Line= 3
      3654264.02     10161160.57      3653499.62     10160862.66
      3653126.96     10160700.54
#Sta/Elev= 30
  4179.6  268.75  4321.2   262.6  4381.7  256.61  4465.9  253.81  4525.7  248.52
    4663  245.62  4754.6  243.71  4851.9  240.72  4876.4  241.87    4890  240.32
  4930.8  241.96  4963.8   239.9  4975.9   238.8  4985.1  235.97  4990.5  236.88
    4993  230.19  4995.7  229.69    4999  230.19  5008.2  230.19  5014.4  233.39
  5019.8   232.7    5030   237.6  5050.1  241.36  5061.2  241.95  5066.7  240.06
  5084.5   242.6  5095.6  240.97  5182.7   247.9  5317.4  253.88  5406.4  260.14
#Mann= 7 ,-1 , 0
  4179.6     .05       0    4663     .12       0  4754.6     .05       0
  4963.8     .12       0    4993     .07       0    4999     .12       0
  5050.1     .05       0
Bank Sta=4993,4999
XS Rating Curve= 0 ,0
Exp/Cntr=0.3,0.1

Type RM Length L Ch R = 1 ,5583    ,721,721,721
BEGIN DESCRIPTION:
UNT068 IN ROCK 12.0
END DESCRIPTION:
XS GIS Cut Line= 3
      3654219.91     10160673.93      3654069.88     10160673.93
      3653336.14     10160301.67
#Sta/Elev= 30
  4521.9  263.88  4539.7  262.46  4579.7  260.42  4668.3  252.68    4715   249.3
  4747.9   247.6  4753.9  246.89  4813.6  245.04  4976.6  241.19  4993.2  228.88
  4995.8   227.8  4998.6   227.3  5001.8   227.8  5005.8  228.73  5015.5  232.75
  5028.3  234.98  5043.4   240.1  5047.8  240.29  5087.9  240.23    5118  239.41
  5332.8   237.5  5421.9   238.4  5444.1  239.43  5454.4  240.53  5460.8  242.09
  5466.4  242.46  5476.8  244.78  5483.1  247.08  5488.7  247.34  5494.7  248.48
#Mann= 5 ,-1 , 0
  4521.9     .05       0  4813.6     .12       0  4995.8     .07       0
  5001.8     .12       0  5047.8     .05       0
Bank Sta=4995.8,5001.8
XS Rating Curve= 0 ,0
Exp/Cntr=0.3,0.1

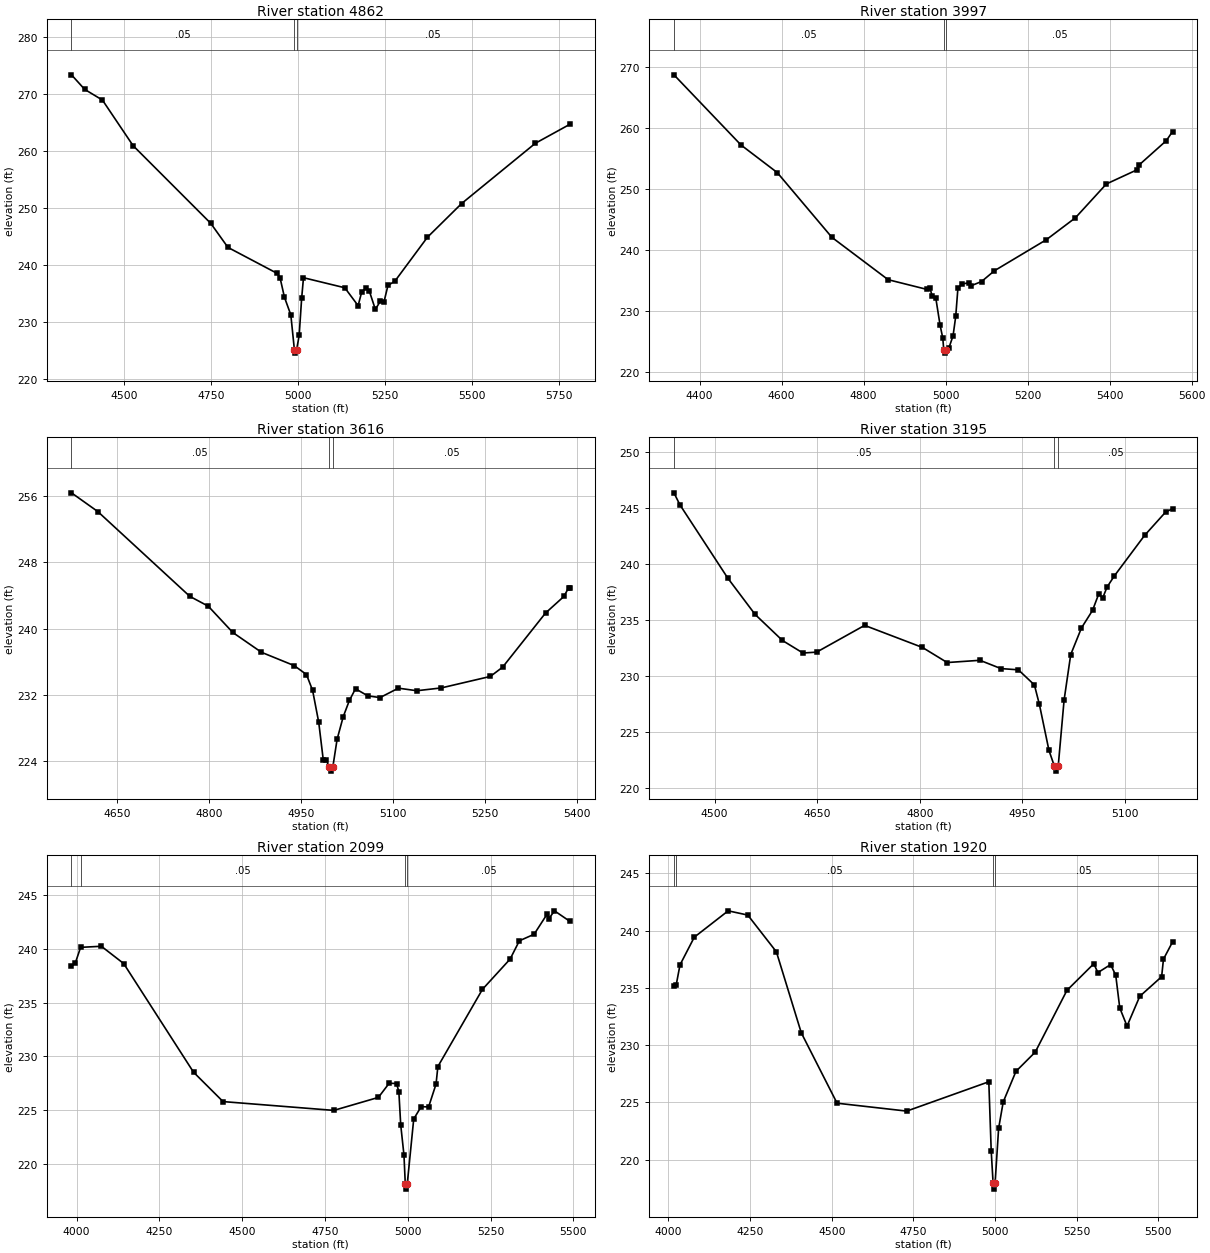
Type RM Length L Ch R = 1 ,4862    ,865,865,865
BEGIN DESCRIPTION:
UNT068 IN ROCK 11.0
END DESCRIPTION:
XS GIS Cut Line= 3
      3654489.36     10160141.65      3654239.33     10160091.64
      3653126.99     10159702.28
#Sta/Elev= 30
  4348.9  273.31  4386.9  270.76  4437.9  268.89    4526  260.91  4749.3   247.3
  4798.8  243.08    4940  238.54  4948.6  237.77  4961.2  234.36  4979.6  231.26
    4990  225.06  4992.7  224.56    4996  225.06  5003.6  227.66  5010.7  234.14
    5016  237.77  5134.8  236.01  5173.1  232.87  5183.7  235.35  5196.8  235.89
  5204.9  235.51  5222.6  232.23  5236.6  233.61  5247.2  233.48  5258.9  236.41
    5279  237.18  5372.4  244.86  5470.8  250.77  5682.7  261.32  5782.4  264.66
#Mann= 3 ,-1 , 0
  4348.9     .05       0    4990     .03       0    4996     .05       0
Bank Sta=4990,4996
XS Rating Curve= 0 ,0
Exp/Cntr=0.3,0.1

Type RM Length L Ch R = 1 ,3997    ,381,381,381
BEGIN DESCRIPTION:
UNT068 IN ROCK 10.0
END DESCRIPTION:
XS GIS Cut Line= 3
       3654507.1     10159606.76      3653735.86      10159346.5
      3653337.03     10159296.65
#Sta/Elev= 30
  4337.4  268.74    4501  257.22  4589.3   252.7  4722.6  242.07  4859.8  235.12
  4954.8  233.52  4961.7   233.8    4967  232.46  4975.9  232.15  4986.5  227.64
  4993.1  225.52  4995.4  223.57  4998.2  223.07  5001.4  223.57  5007.6  223.86
  5018.1  225.91  5024.6   229.1  5029.9   233.7  5039.2   234.4  5056.1  234.61
  5061.4  234.11  5087.6  234.82    5119  236.59  5245.8  241.69  5316.5  245.28
    5392  250.83  5467.6  253.18  5472.7     254  5538.1  257.93  5553.3  259.43
#Mann= 3 ,-1 , 0
  4337.4     .05       0  4995.4     .03       0  5001.4     .05       0
Bank Sta=4995.4,5001.4
XS Rating Curve= 0 ,0
Exp/Cntr=0.3,0.1

Type RM Length L Ch R = 1 ,3616    ,421,421,421
BEGIN DESCRIPTION:
UNT068 IN ROCK 8.0
END DESCRIPTION:
XS GIS Cut Line= 3
      3654455.02     10159111.97      3654042.11     10159091.64
      3653642.12     10159091.64
#Sta/Elev= 30
  4575.2  256.42  4618.2  254.15  4768.3  243.89  4798.4   242.7  4838.4  239.52
  4885.2  237.12  4938.6  235.51  4958.6  234.43  4968.6  232.51  4978.6  228.65
  4986.1  224.04  4991.1  224.04  4995.6  223.24  4998.4  222.74  5001.6  223.24
  5008.6   226.6  5018.6  229.33  5028.6  231.29  5038.6  232.71  5058.6  231.85
  5078.6  231.64  5108.6  232.78  5138.6  232.47  5178.6  232.81  5258.6   234.2
  5278.6  235.32  5348.6  241.87  5378.6  243.88  5386.1   244.9  5388.6   244.9
#Mann= 3 ,-1 , 0
  4575.2     .05       0  4995.6     .03       0  5001.6     .05       0
Bank Sta=4995.6,5001.6
XS Rating Curve= 0 ,0
Exp/Cntr=0.3,0.1

Type RM Length L Ch R = 1 ,3195    ,1096,1096,1096
BEGIN DESCRIPTION:
UNT068 IN ROCK 7.0
END DESCRIPTION:
XS GIS Cut Line= 3
      3654450.71     10158799.47      3654064.08     10158807.12
      3653742.07     10158691.63
#Sta/Elev= 30
  4440.6  246.37  4449.2  245.31  4519.2  238.76  4559.2  235.51  4599.2  233.18
  4629.2  232.06  4649.2  232.14  4719.3  234.53  4803.8  232.56    4840  231.21
  4887.9  231.41  4918.6  230.67  4944.1  230.56  4967.5  229.21  4974.8  227.47
  4988.8  223.36  4996.4  222.01  4999.1  221.51  5002.4  222.01  5010.9  227.85
  5020.6  231.92  5036.3   234.3  5052.5  235.87  5061.7  237.36  5067.1  236.94
  5073.7  237.95  5084.4  238.95  5128.5  242.56  5159.3  244.65  5169.4  244.95
#Mann= 3 ,-1 , 0
  4440.6     .05       0  4996.4     .03       0  5002.4     .05       0
Bank Sta=4996.4,5002.4
XS Rating Curve= 0 ,0
Exp/Cntr=0.3,0.1

Type RM Length L Ch R = 1 ,2099    ,179,179,179
BEGIN DESCRIPTION:
UNT068 IN ROCK 5.0
END DESCRIPTION:
XS GIS Cut Line= 3
      3654324.81     10157111.11      3653792.11     10158191.64
      3653656.75     10158460.26
#Sta/Elev= 30
  3984.6   238.4  3996.3   238.7  4012.2  240.15  4074.9  240.25  4142.3  238.64
  4353.1  228.53  4442.3  225.79  4776.8  224.97  4911.4  226.18    4944   227.5
  4966.3  227.47  4973.2  226.71  4978.8  223.63  4988.6  220.82  4992.6  218.14
  4995.4  217.64  4998.6  218.14  5018.1  224.17  5040.6  225.32    5063  225.29
  5085.5  227.42    5091  229.05  5225.6  236.24  5309.2  239.06  5337.1  240.76
  5381.7  241.37  5420.8  243.24  5426.3  242.82  5443.1  243.55  5490.1  242.56
#Mann= 4 ,-1 , 0
  3984.6     .08       0  4012.2     .05       0  4992.6     .03       0
  4998.6     .05       0
Bank Sta=4992.6,4998.6
XS Rating Curve= 0 ,0
Exp/Cntr=0.3,0.1

Type RM Length L Ch R = 1 ,1920    ,529,529,529
BEGIN DESCRIPTION:
UNT068 IN ROCK 4.0
END DESCRIPTION:
XS GIS Cut Line= 3
      3654264.05     10157006.95      3653797.14     10157871.98
      3653552.26     10158356.74
#Sta/Elev= 30
    4017  235.14  4024.1  235.28  4035.5     237  4079.3  239.42    4183  241.72
    4243  241.35  4330.6  238.14  4406.8  231.07  4516.3  224.93  4729.5  224.24
  4980.8   226.8  4988.2  220.72    4994  217.93  4996.7  217.43    5000  217.93
  5010.8  222.73  5024.9  225.04  5063.9  227.71  5122.9  229.39    5220  234.78
  5302.1   237.1  5314.7  236.33  5353.7  237.03  5369.3   236.1  5381.6  233.25
  5403.9  231.66  5442.9  234.26  5509.8  235.97  5515.4   237.5  5543.1     239
#Mann= 4 ,-1 , 0
    4017     .08       0  4024.1     .05       0    4994     .03       0
    5000     .05       0
Bank Sta=4994,5000
XS Rating Curve= 0 ,0
Exp/Cntr=0.3,0.1

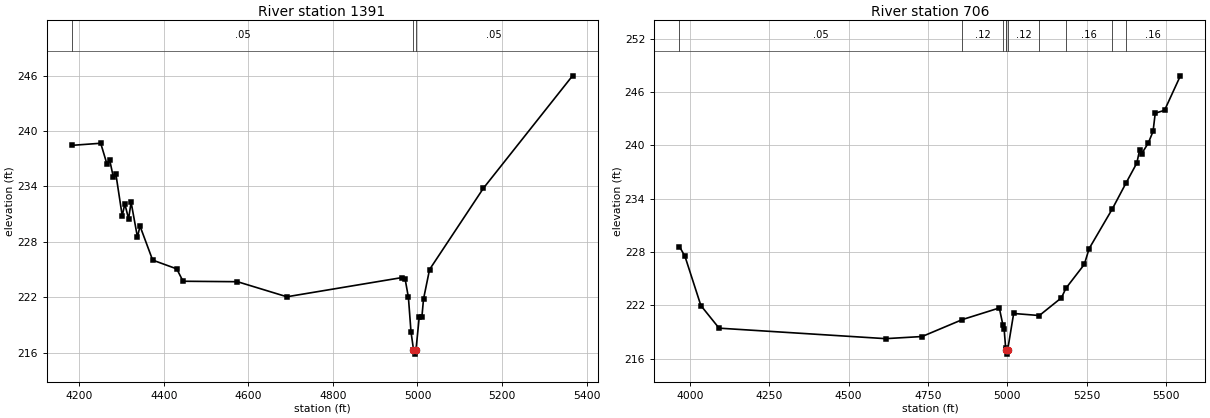
Type RM Length L Ch R = 1 ,1391    ,685,685,685
BEGIN DESCRIPTION:
UNT068 IN ROCK 3.0
END DESCRIPTION:
XS GIS Cut Line= 3
      3654125.17     10157028.63      3653442.11     10157491.64
       3653166.5     10157722.63
#Sta/Elev= 30
  4181.9  238.44  4250.8  238.67  4265.8  236.38  4271.8   236.9  4280.7  234.99
  4286.8  235.29  4301.7  230.81  4307.8  232.12  4316.7  230.48  4322.7  232.28
  4337.7   228.5  4343.7  229.71  4373.6  226.02  4430.6  225.07  4445.5  223.73
  4574.3  223.68  4691.1  222.05  4963.7  224.13  4970.9  223.94  4978.6  221.98
  4984.7  218.26  4990.6  216.34  4993.3  215.84  4996.6  216.34  5004.1  219.82
  5010.4  219.82  5014.3   221.8  5028.6     225  5156.1  233.81  5366.7  245.97
#Mann= 3 ,-1 , 0
  4181.9     .05       0  4990.6     .03       0  4996.6     .05       0
Bank Sta=4990.6,4996.6
XS Rating Curve= 0 ,0
Exp/Cntr=0.3,0.1

Type RM Length L Ch R = 1 ,706     ,0,0,0
BEGIN DESCRIPTION:
UNT068 IN ROCK 1.0
END DESCRIPTION:
XS GIS Cut Line= 3
      3653899.43     10156746.52      3653139.92     10156807.28
      3652689.19     10157487.71
#Sta/Elev= 30
  3967.3  228.62  3984.7  227.52  4034.8  221.99  4092.1  219.45  4616.7  218.27
  4731.8  218.51    4859  220.42    4975  221.72  4986.1  219.84  4990.1  219.37
    4995  217.21  4995.4  217.03  4998.1  216.53  5001.4  217.03  5020.2   221.1
  5101.1  220.87  5170.6  222.86  5184.9  223.94  5242.8  226.62  5257.9  228.39
  5330.9  232.85  5374.8  235.81  5408.2  238.01  5417.3  239.52  5423.3  239.06
  5444.3  240.26  5459.4  241.58  5466.2  243.62  5495.5  243.94  5545.4  247.82
#Mann= 10 ,-1 , 0
  3967.3     .05       0    4859     .12       0  4986.1     .05       0
    4995     .12       0  4995.4     .07       0  5001.4     .12       0
  5101.1     .05       0  5184.9     .16       0  5330.9     .05       0
  5374.8     .16       0
Bank Sta=4995.4,5001.4
XS Rating Curve= 0 ,0
Exp/Cntr=0.3,0.1

Chan Stop Cuts=-1
Use User Specified Reach Order=0
Composite Channel Slope=5