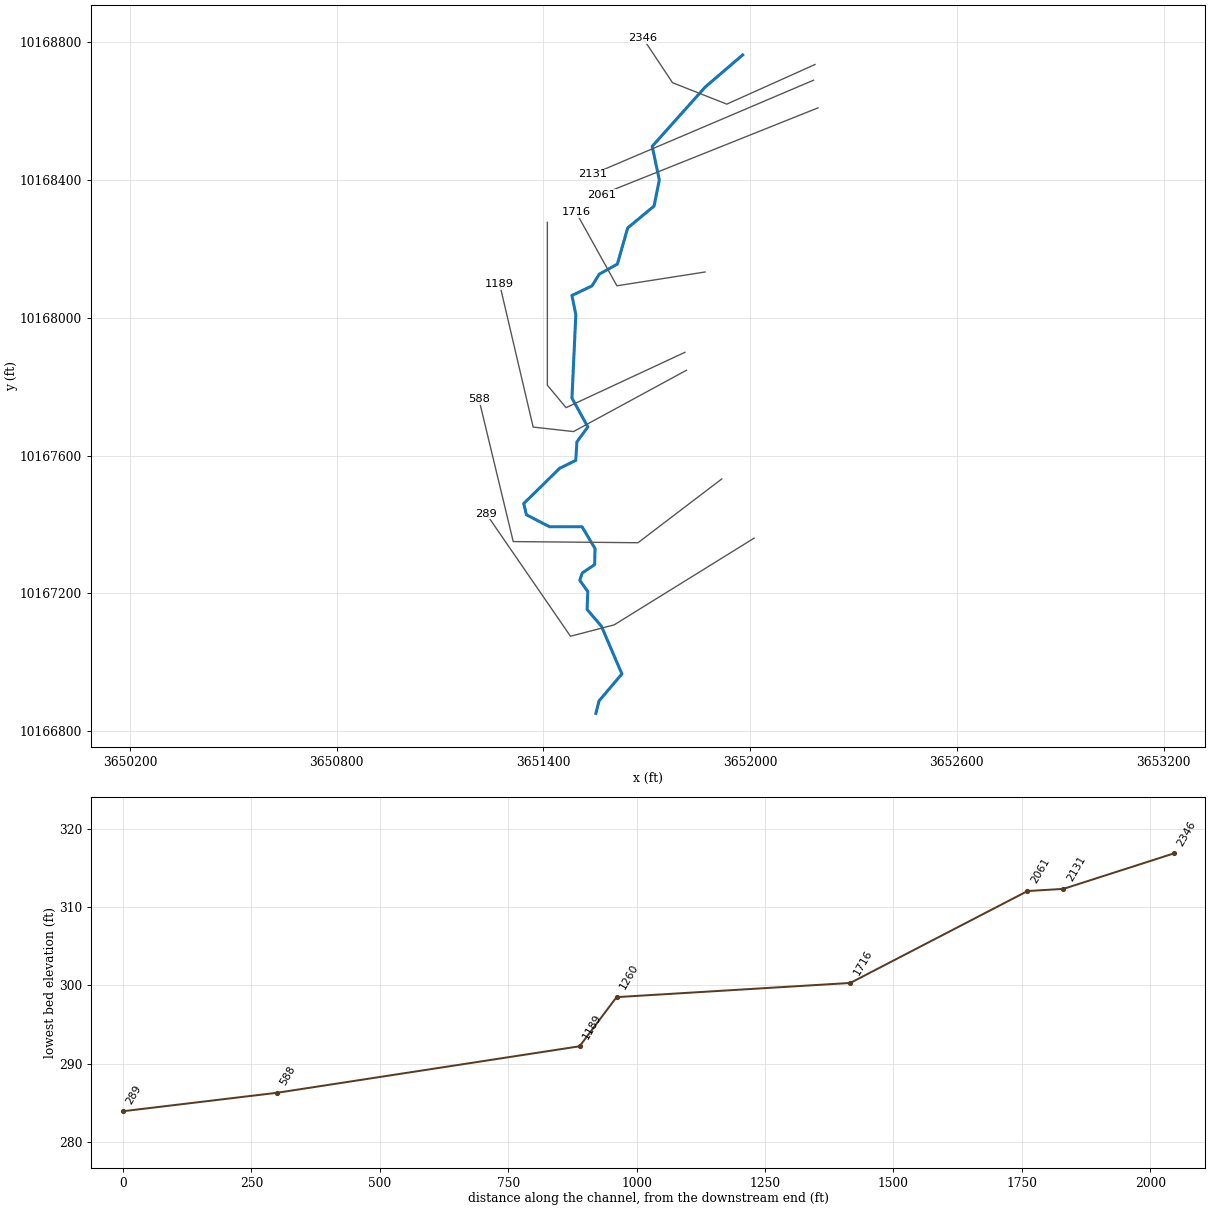
--- UNT069 IN ROCK.prj (project) ---

Proj Title=UNT069 IN ROCK Base Level Engineering
Current Plan=p01
Default Exp/Contr=0.3,0.1
English Units
Geom File=g01
Flow File=f01
Plan File=p01
Y Axis Title=Elevation
X Axis Title(PF)=Main Channel Distance
X Axis Title(XS)=Station
BEGIN DESCRIPTION:
UNT069 IN ROCK
END DESCRIPTION:
DSS Export Rating Curves= 0
DSS Export Rating Curve Sorted= 0
DSS Export Volume Flow Curves= 0
DXF OffsetX= 0
DXF OffsetY= 0
DXF ScaleX= 1
DXF ScaleY= 10

--- UNT069 IN ROCK.p01 (plan) ---

Plan Title=Multiple Run
Short Identifier=Multiple
Geom File=g01
Flow File=f01
Subcritical Flow
K Sum by GR= 0
Std Step Tol= 0.01
Critical Tol= 0.01
Num of Std Step Trials= 20
Max Error Tol= 0.3
Flow Tol Ratio= 0.001
Split Flow NTrial= 30
Split Flow Tol= 0.02
Split Flow Ratio= 0.02
Log Output Level= 0
Friction Slope Method= 1
Unsteady Friction Slope Method= 2
Unsteady Bridges Friction Slope Method= 1
Parabolic Critical Depth
Global Vel Dist=  1 , 1 , 1
Global Log Level= 0
CheckData=True
Encroach Param= -1, 0, 0, 0
BEGIN DESCRIPTION:
Multiple Run
END DESCRIPTION:

--- UNT069 IN ROCK.f01 (steady flow) ---

Flow Title=Multiple
Program Version=4.10
Number of Profiles= 7
Profile Names=10-year,25-year,50-year,1pct_min,100-year,1pct_plu,500-year
River Rch & RM=UNT069 IN ROCK,Reach-1         ,2346
     189     236     272     232     313     424     414
Boundary for River Rch & Prof#=UNT069 IN ROCK,Reach-1         , 1
Up Type= 0
Dn Type= 3
Dn Slope=0.025
Boundary for River Rch & Prof#=UNT069 IN ROCK,Reach-1         , 2
Up Type= 0
Dn Type= 3
Dn Slope=0.025
Boundary for River Rch & Prof#=UNT069 IN ROCK,Reach-1         , 3
Up Type= 0
Dn Type= 3
Dn Slope=0.025
Boundary for River Rch & Prof#=UNT069 IN ROCK,Reach-1         , 4
Up Type= 0
Dn Type= 3
Dn Slope=0.025
Boundary for River Rch & Prof#=UNT069 IN ROCK,Reach-1         , 5
Up Type= 0
Dn Type= 3
Dn Slope=0.025
Boundary for River Rch & Prof#=UNT069 IN ROCK,Reach-1         , 6
Up Type= 0
Dn Type= 3
Dn Slope=0.025
Boundary for River Rch & Prof#=UNT069 IN ROCK,Reach-1         , 7
Up Type= 0
Dn Type= 3
Dn Slope=0.025
DSS Import GetInterval= 0
DSS Import GetPeak= 0
DSS Import FillOption= 0

--- UNT069 IN ROCK.g01 (geometry) ---

Geom Title=Existing Conditions
Program Version=4.10

River Reach=UNT069 IN ROCK  ,Reach-1
Reach XY= 30
       3651978.2     10168763.07      3651869.67       10168670.
      3651715.62     10168497.73      3651736.24     10168400.08
      3651721.07     10168324.33      3651644.42     10168260.77
      3651614.47     10168155.82      3651561.56     10168126.47
        3651541.     10168092.61      3651482.65     10168064.75
      3651493.85     10168008.76      3651482.68     10167766.83
      3651528.79     10167683.07      3651497.09     10167639.89
      3651493.68     10167586.08      3651446.83     10167562.99
      3651342.67     10167460.61      3651350.51     10167428.19
      3651417.34     10167393.42      3651512.01     10167393.35
      3651549.62     10167330.28      3651548.52     10167283.48
      3651512.73     10167259.34       3651505.4     10167238.09
      3651528.54     10167205.29      3651526.58      10167153.3
      3651568.14     10167104.75       3651627.6     10166966.14
      3651561.26     10166887.76      3651552.11     10166851.64

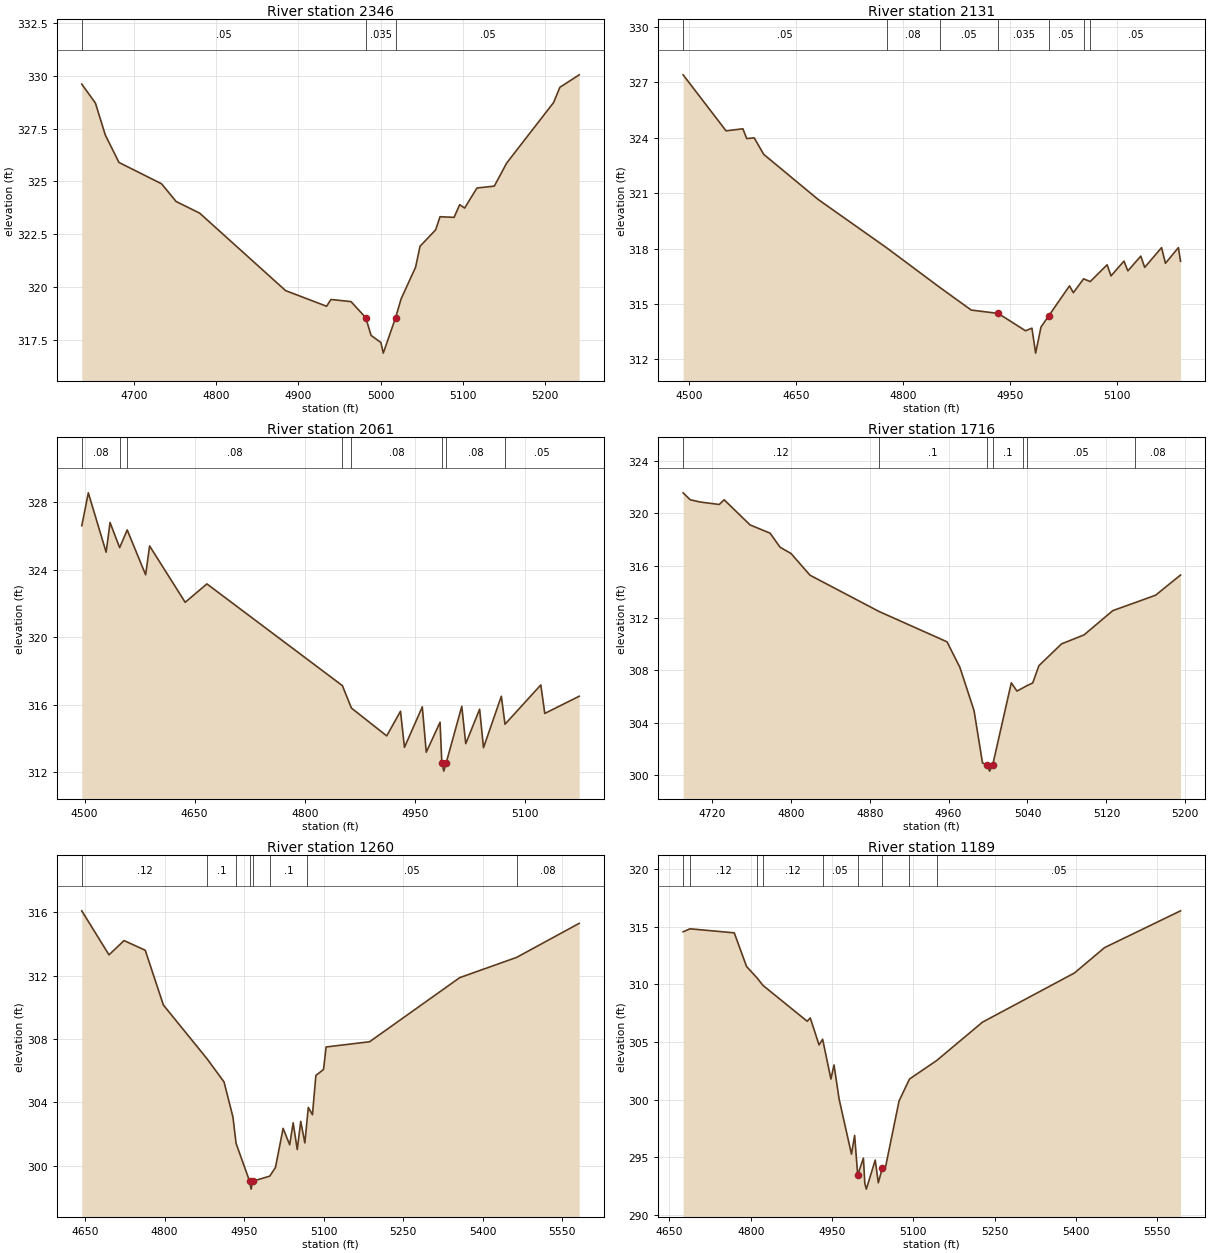
Type RM Length L Ch R = 1 ,2346    ,215,215,215
BEGIN DESCRIPTION:
UNT069 IN ROCK 4.0
END DESCRIPTION:
XS GIS Cut Line= 4
      3652188.19     10168735.23       3651932.1      10168620.2
      3651774.64     10168682.36      3651689.04     10168811.19
#Sta/Elev= 30
  4636.6  329.61  4653.2  328.71  4665.2   327.2  4681.8   325.9  4733.6  324.89
  4751.3  324.05  4779.9   323.5  4884.4  319.83  4934.2  319.09  4939.5  319.41
  4963.9  319.31  4981.8  318.55  4988.3  317.71  5000.3  317.37  5003.1  316.87
    5018  318.54  5024.8  319.44  5042.4  320.94  5047.8  321.93  5066.8  322.71
  5072.1  323.33  5089.2   323.3    5096   323.9    5102  323.74    5117  324.69
  5138.1  324.78  5153.1  325.87  5210.2  328.74  5217.8  329.46  5241.3  330.05
#Mann= 3 , 0 , 0
  4636.6     .05       0  4981.8    .035       0    5018     .05       0
Bank Sta=4981.8,5018
XS Rating Curve= 0 ,0
Exp/Cntr=0.3,0.1

Type RM Length L Ch R = 1 ,2131    ,70,70,70
BEGIN DESCRIPTION:
Mapping XS 653943f0
END DESCRIPTION:
XS GIS Cut Line= 2
       3652183.8     10168689.63      3651542.03     10168416.44
#Sta/Elev= 30
  4491.4   327.4  4551.6  324.37  4575.2  324.48  4580.6  323.95  4591.1  323.99
  4604.3   323.1  4680.6  320.66  4776.8  318.04  4851.2   315.9  4895.4  314.67
  4933.2  314.49  4971.5  313.55  4980.5  313.69  4985.7  312.34  4993.2  313.75
  5004.1  314.36  5033.2  315.98  5038.6  315.61    5053  316.36  5062.2  316.21
  5085.9  317.12  5091.4  316.52  5109.6  317.32    5115  316.79  5133.2  317.59
  5138.6  316.98  5162.3  318.05  5167.7   317.2  5185.9  318.05  5188.9  317.31
#Mann= 7 ,-1 , 0
  4491.4     .05       0  4776.8     .08       0  4851.2     .05       0
  4933.2    .035       0  5004.1     .05       0    5053     .08       0
  5062.2     .05       0
Bank Sta=4933.2,5004.1
XS Rating Curve= 0 ,0
Exp/Cntr=0.3,0.1

Type RM Length L Ch R = 1 ,2061    ,345,345,345
BEGIN DESCRIPTION:
Mapping XS e4a0f80f
END DESCRIPTION:
XS GIS Cut Line= 2
      3652196.88     10168609.36      3651567.56     10168357.63
#Sta/Elev= 30
  4496.2  326.61  4505.1  328.56  4529.4  325.04  4534.7   326.8  4547.8  325.31
  4558.1  326.36  4583.2   323.7  4588.6  325.41  4637.1  322.07  4666.7  323.16
  4851.3  317.13  4863.6   315.8  4911.7  314.15  4930.5  315.61  4935.9  313.47
  4960.2  315.87  4965.6  313.18  4984.4  314.96  4986.8  312.56  4989.5  312.06
  4992.8  312.56    5014   315.9  5019.4  313.69  5038.3  315.73  5043.6  313.45
  5067.9   316.5  5072.9  314.84  5121.7  317.17  5127.1  315.48    5174   316.5
#Mann= 8 ,-1 , 0
  4496.2     .08       0  4547.8     .05       0  4558.1     .08       0
  4851.3     .05       0  4863.6     .08       0  4986.8     .07       0
  4992.8     .08       0  5072.9     .05       0
Bank Sta=4986.8,4992.8
XS Rating Curve= 0 ,0
Exp/Cntr=0.3,0.1

Type RM Length L Ch R = 1 ,1716    ,455,455,455
BEGIN DESCRIPTION:
UNT069 IN ROCK 2.0
END DESCRIPTION:
XS GIS Cut Line= 3
      3651869.21     10168132.92      3651613.09     10168092.86
      3651494.03     10168307.17
#Sta/Elev= 30
  4690.8  321.56    4698  321.03  4708.1  320.86  4727.4  320.67  4732.4  321.03
  4758.7  319.11    4779  318.48  4789.1  317.41  4800.2  316.93  4819.5  315.27
  4889.6   312.5  4958.4  310.19  4971.5  308.23  4985.8  304.94  4994.4  300.94
  4998.8  300.82  5001.6  300.32  5004.8  300.82  5023.6  307.06  5029.3  306.43
  5035.5  306.68  5039.4  306.84  5045.3  307.05  5051.6  308.37  5074.5  310.03
  5097.4  310.72  5126.5  312.57  5149.5  313.19    5170  313.75  5195.2  315.29
#Mann= 7 ,-1 , 0
  4690.8     .12       0  4889.6      .1       0  4998.8     .07       0
  5004.8      .1       0  5035.5     .12       0  5039.4     .05       0
  5149.5     .08       0
Bank Sta=4998.8,5004.8
XS Rating Curve= 0 ,0
Exp/Cntr=0.3,0.1

Type RM Length L Ch R = 1 ,1260    ,72,72,72
BEGIN DESCRIPTION:
Mapping XS 5b4c3a4e
END DESCRIPTION:
XS GIS Cut Line= 4
      3651810.59     10167899.72      3651465.52     10167739.13
      3651411.27     10167804.23      3651411.27     10168276.98
#Sta/Elev= 30
    4644  316.09  4695.3  313.31  4723.7  314.21  4763.7   313.6  4797.9  310.14
  4880.1  306.75  4912.3  305.28  4929.1  303.06    4935   301.4  4960.5  299.01
  4963.3  298.51  4966.5  299.01  4998.5  299.33  5009.3  299.88  5023.7  302.35
  5036.1  301.31  5042.6   302.7  5050.4  301.01  5056.9  302.79  5064.7  301.43
  5068.3  302.67  5071.2  303.67    5079  303.21  5085.5  305.69  5099.9  306.07
  5104.8  307.49  5186.8  307.82  5356.8  311.87  5464.2  313.15  5582.1   315.3
#Mann= 8 ,-1 , 0
    4644     .12       0  4880.1      .1       0    4935     .16       0
  4960.5     .07       0  4966.5     .16       0  4998.5      .1       0
  5068.3     .05       0  5464.2     .08       0
Bank Sta=4960.5,4966.5
XS Rating Curve= 0 ,0
Exp/Cntr=0.3,0.1

Type RM Length L Ch R = 1 ,1189    ,589,589,589
BEGIN DESCRIPTION:
Mapping XS 171235ca
END DESCRIPTION:
XS GIS Cut Line= 4
      3651814.94     10167847.64      3651487.22     10167669.68
      3651370.04      10167682.7       3651272.7     10168098.02
#Sta/Elev= 30
  4675.4  314.55  4688.1  314.81  4769.7  314.46  4792.4  311.54  4811.4  310.57
  4822.7   309.9  4904.3  306.79  4909.9  307.08  4926.1  304.74  4932.7  305.23
    4948  301.78  4953.7     303  4963.1  300.04  4985.9  295.26  4991.7  296.89
  4997.4  293.45  5007.9  294.92  5010.5  292.73  5013.3  292.23  5029.7  294.75
  5035.4  292.78  5042.7  294.05  5048.3  294.05  5073.6  299.87  5092.9  301.78
  5142.9  303.38  5227.4  306.71  5397.2  310.98  5452.7  313.18  5592.8  316.37
#Mann= 9 ,-1 , 0
  4675.4      .1       0  4688.1     .12       0  4811.4     .16       0
  4822.7     .12       0  4932.7     .05       0  4997.4    .035       0
  5042.7     .05       0  5092.9      .1       0  5142.9     .05       0
Bank Sta=4997.4,5042.7
XS Rating Curve= 0 ,0
Exp/Cntr=0.3,0.1

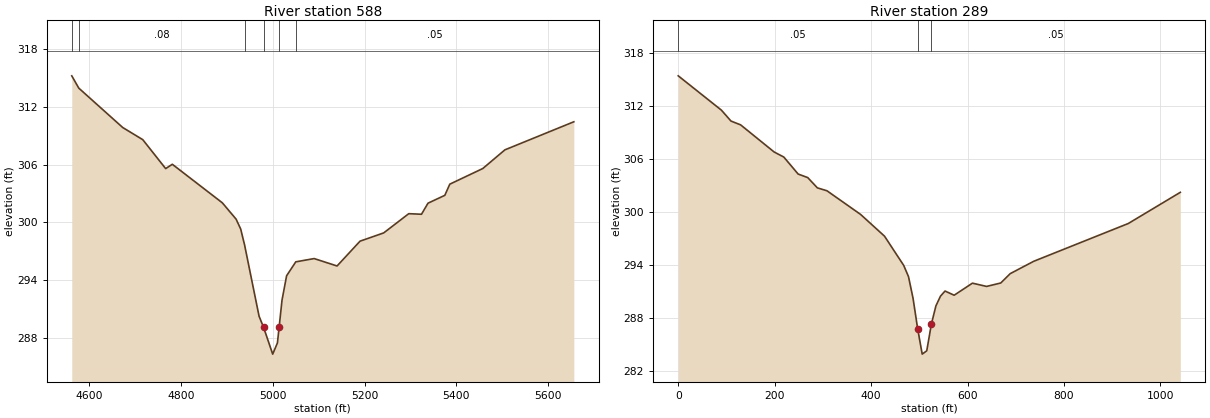
Type RM Length L Ch R = 1 ,588     ,300,300,300
BEGIN DESCRIPTION:
UNT069 IN ROCK 1.0
END DESCRIPTION:
XS GIS Cut Line= 4
      3651917.67     10167532.26      3651674.39       10167347.
      3651312.17     10167350.33      3651212.34     10167764.44
#Sta/Elev= 30
    4562  315.24  4577.3  313.96  4673.1  309.86  4716.7   308.6  4766.6  305.59
  4781.1  306.04  4890.1  302.03  4920.1  300.33  4930.1   299.3  4938.6  297.64
  4970.1  290.24  4980.1  289.06  4999.8  286.29  5010.1  287.45 5013.76  289.06
  5020.1   291.9  5030.1  294.44  5050.1  295.89  5090.1  296.23  5140.1  295.46
  5190.1  298.04  5241.7   298.9  5296.3   300.9    5324  300.84  5338.2  301.99
  5374.9  302.81  5385.7  303.97  5457.7   305.6  5505.8  307.54    5656  310.46
#Mann= 6 ,-1 , 0
    4562      .1       0  4577.3     .08       0  4938.6    .035       0
  4980.1    .035       0 5013.76    .035       0  5050.1     .05       0
Bank Sta=4980.1,5013.76
XS Rating Curve= 0 ,0
Exp/Cntr=0.3,0.1

Type RM Length L Ch R = 1 ,289     ,0,0,0
XS GIS Cut Line= 4
     3652011.383     10167360.25     3651605.133    10167108.514
     3651478.396    10167075.528     3651233.605    10167431.431
#Sta/Elev= 30
       0315.375589.53421311.4962109.4307 310.263129.3272309.8377198.9649306.7667
218.8614306.2014248.7061304.2761268.6026303.8765288.4991302.7173308.3956302.3893
378.0333299.7221427.7745297.2586467.5675 293.958477.5158292.6863486.9839290.2252
 496.452286.8206505.9201283.9317515.3882  284.31524.8563287.3021534.3244289.3802
543.7925290.4799553.2606291.0575572.1968290.5872610.0692291.9497639.4613291.5812
668.8535291.9708688.4482293.0261737.4351294.4267933.3826298.69251041.154302.2122
#Mann= 3 , 0 , 0
       0     .05       0 496.452    .035       0524.8563     .05       0
Bank Sta=496.452,524.8563
XS Rating Curve= 0 ,0
Exp/Cntr=0.3,0.1
Stream Node=UNT069 IN ROCK  ,Reach-1         , 0 , 0 ,Upstream end
Stream Node=UNT069 IN ROCK  ,Reach-1         , 0 , 1 ,Downstream end

Chan Stop Cuts=-1
Use User Specified Reach Order=0
Composite Channel Slope=5