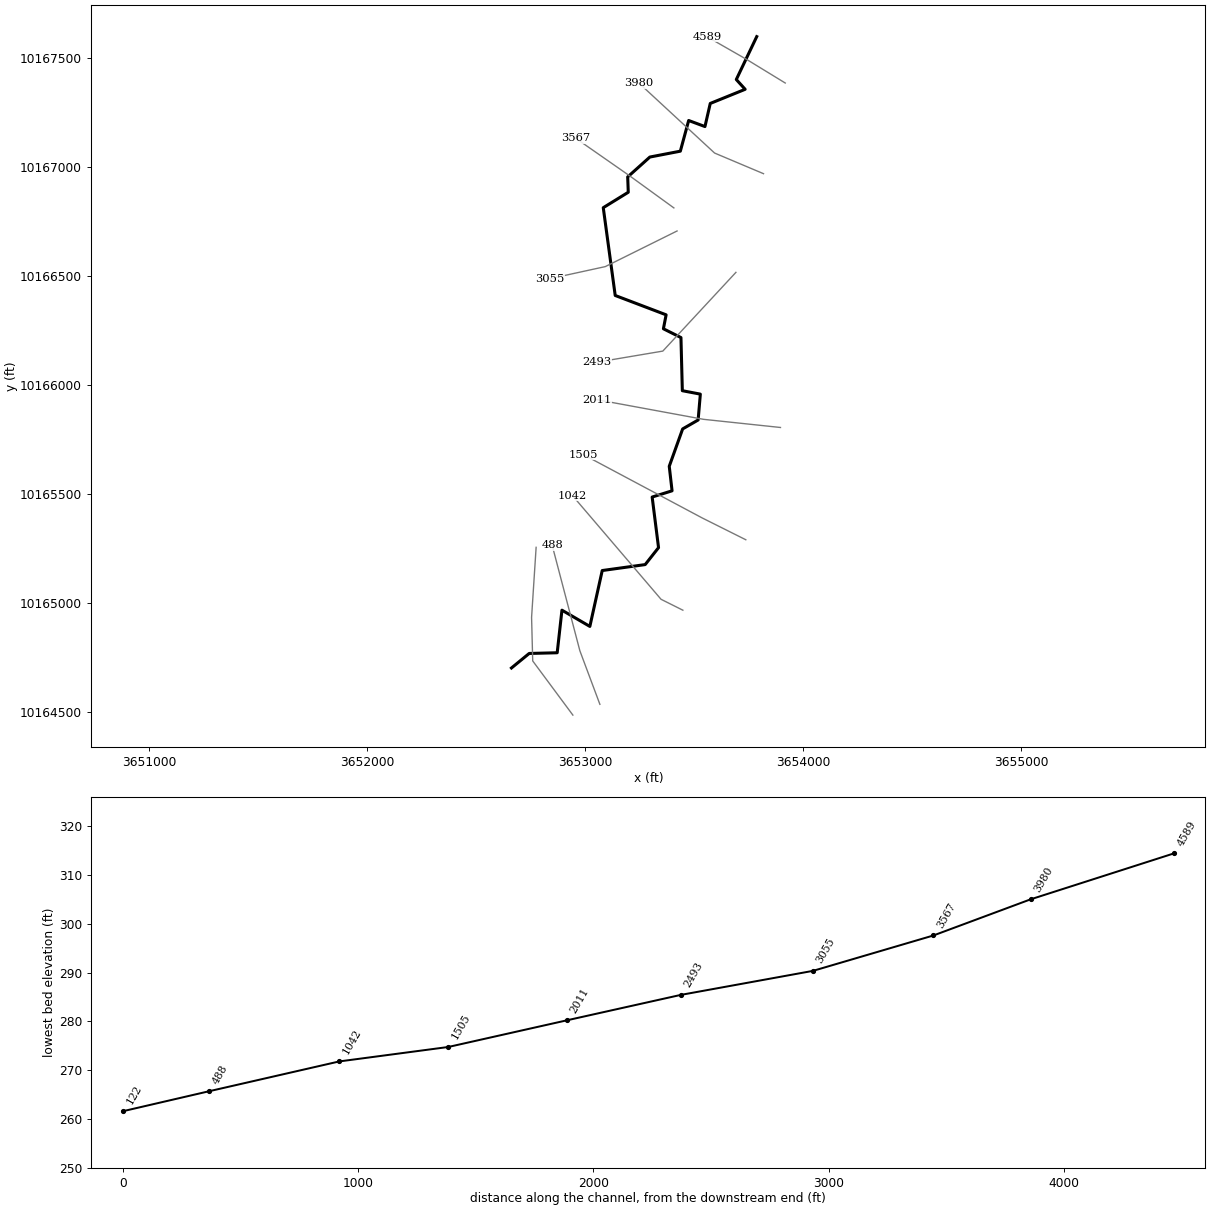
--- UNT070 IN ROCK.prj (project) ---

Proj Title=UNT070 IN ROCK Base Level Engineering
Current Plan=p01
Default Exp/Contr=0.3,0.1
English Units
Geom File=g01
Flow File=f01
Plan File=p01
Y Axis Title=Elevation
X Axis Title(PF)=Main Channel Distance
X Axis Title(XS)=Station
BEGIN DESCRIPTION:
UNT070 IN ROCK
END DESCRIPTION:
DSS Export Rating Curves= 0
DSS Export Rating Curve Sorted= 0
DSS Export Volume Flow Curves= 0
DXF OffsetX= 0
DXF OffsetY= 0
DXF ScaleX= 1
DXF ScaleY= 10

--- UNT070 IN ROCK.p01 (plan) ---

Plan Title=Multiple Run
Short Identifier=Multiple
Geom File=g01
Flow File=f01
Subcritical Flow
K Sum by GR= 0
Std Step Tol= 0.01
Critical Tol= 0.01
Num of Std Step Trials= 20
Max Error Tol= 0.3
Flow Tol Ratio= 0.001
Split Flow NTrial= 30
Split Flow Tol= 0.02
Split Flow Ratio= 0.02
Log Output Level= 0
Friction Slope Method= 1
Unsteady Friction Slope Method= 2
Unsteady Bridges Friction Slope Method= 1
Parabolic Critical Depth
Global Vel Dist=  1 , 1 , 1
Global Log Level= 0
CheckData=True
Encroach Param= -1, 0, 0, 0
BEGIN DESCRIPTION:
Multiple Run
END DESCRIPTION:

--- UNT070 IN ROCK.f01 (steady flow) ---

Flow Title=Multiple
Number of Profiles=7
Profile Names=10-year,25-year,50-year,1pct_min,100-year,1pct_plu,500-year
River Rch & RM= UNT070 IN ROCK,Reach-1,4589
     229     290     338     290     392     530     526
Boundary for River Rch & Prof#=UNT070 IN ROCK,Reach-1,1
Up Type=0
Dn Type=3
Dn Slope=0.005
Boundary for River Rch & Prof#=UNT070 IN ROCK,Reach-1,2
Up Type=0
Dn Type=3
Dn Slope=0.005
Boundary for River Rch & Prof#=UNT070 IN ROCK,Reach-1,3
Up Type=0
Dn Type=3
Dn Slope=0.005
Boundary for River Rch & Prof#=UNT070 IN ROCK,Reach-1,4
Up Type=0
Dn Type=3
Dn Slope=0.005
Boundary for River Rch & Prof#=UNT070 IN ROCK,Reach-1,5
Up Type=0
Dn Type=3
Dn Slope=0.005
Boundary for River Rch & Prof#=UNT070 IN ROCK,Reach-1,6
Up Type=0
Dn Type=3
Dn Slope=0.005
Boundary for River Rch & Prof#=UNT070 IN ROCK,Reach-1,7
Up Type=0
Dn Type=3
Dn Slope=0.005

--- UNT070 IN ROCK.g01 (geometry) ---

Geom Title=Existing Conditions
Program Version=4.10

River Reach=UNT070 IN ROCK  ,Reach-1
Reach XY= 30
      3653786.55     10167596.01      3653692.85     10167399.34
      3653733.45     10167354.51      3653573.48     10167289.62
      3653549.17     10167183.71      3653474.52     10167211.49
      3653436.33     10167070.87      3653296.57     10167043.96
      3653195.01     10166952.81      3653197.61      10166882.5
        3653083.     10166811.81      3653137.76     10166409.33
      3653371.14     10166320.67      3653358.72     10166256.67
      3653439.14     10166216.43      3653445.48     10165972.79
      3653528.01     10165957.11       3653517.9     10165838.53
      3653446.91     10165797.54      3653385.49     10165626.25
       3653398.4      10165513.9      3653307.13     10165485.32
       3653336.4     10165253.36      3653275.16     10165175.66
      3653078.28      10165148.4      3653021.52      10164892.2
      3652893.57     10164966.69       3652871.8     10164771.45
      3652743.46     10164768.28      3652662.11     10164701.64

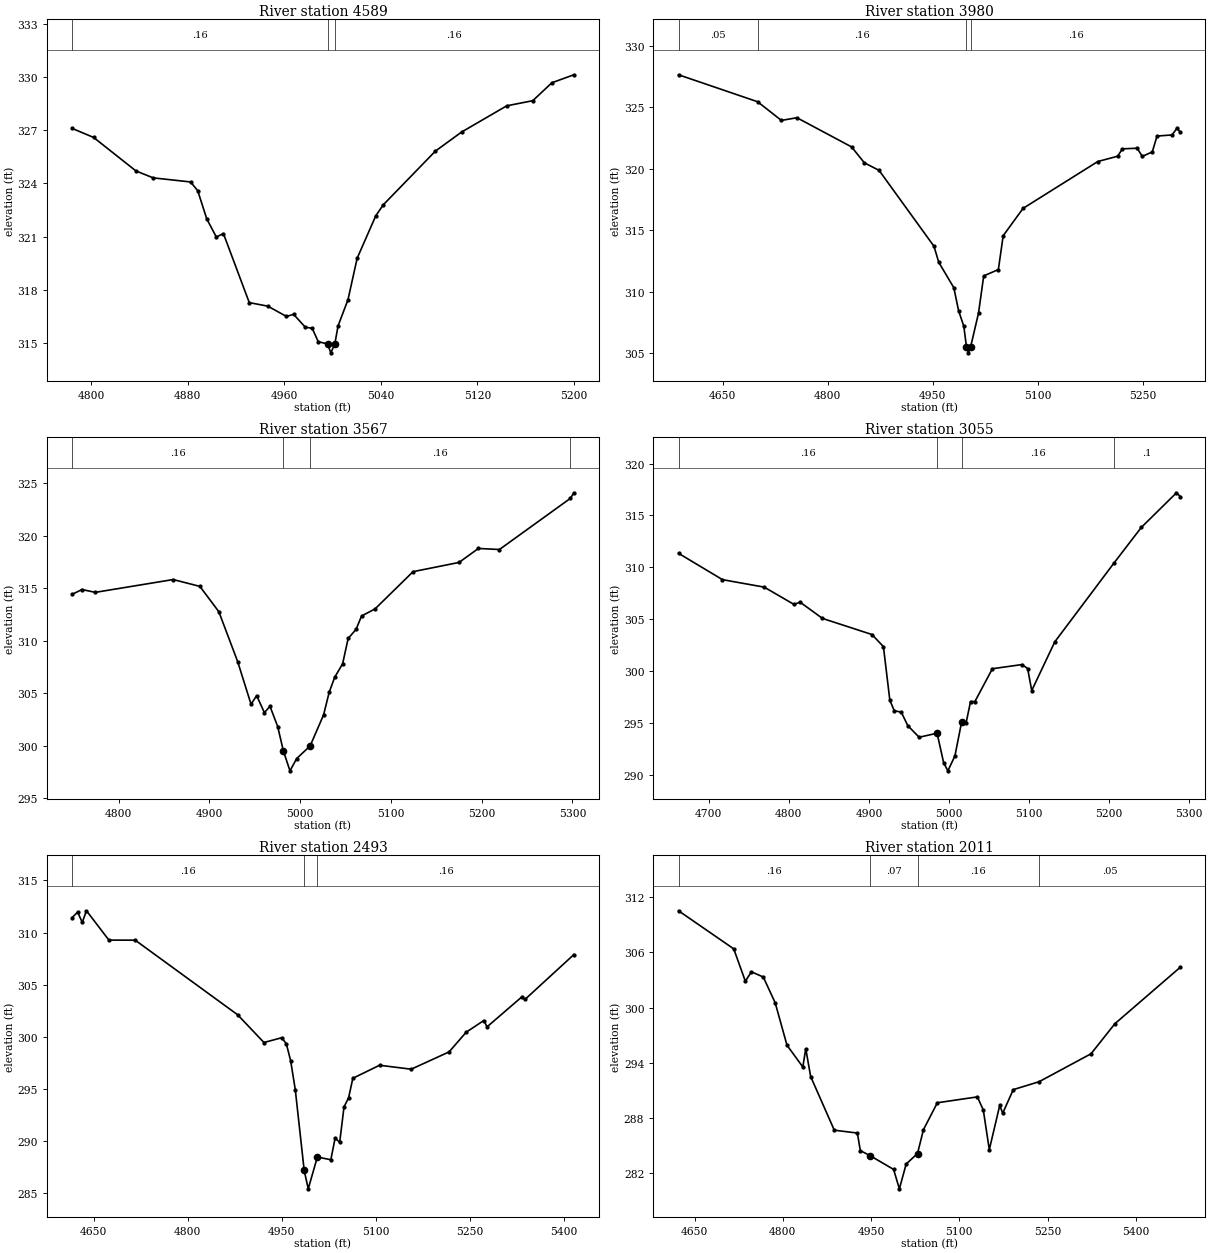
Type RM Length L Ch R = 1 ,4589    ,609,609,609
BEGIN DESCRIPTION:
UNT070 IN ROCK 9.0
END DESCRIPTION:
XS GIS Cut Line= 3
      3653917.29      10167383.3      3653739.67     10167491.84
      3653559.84     10167594.85
#Sta/Elev= 30
  4784.4   327.1  4802.2  326.59  4837.3   324.7  4851.6  324.31  4882.5  324.08
  4888.4  323.59  4895.9     322  4903.8  320.98  4909.7  321.17  4931.1  317.28
  4946.5  317.08  4961.9   316.5  4967.8  316.62  4977.4   315.9  4983.2  315.83
  4988.2  315.08  4995.9  314.95  4998.6  314.45  5001.9  314.95  5004.6  315.97
  5012.8  317.44  5020.4  319.78  5035.8  322.17    5042  322.79  5085.2  325.82
  5106.8  326.89  5144.2  328.37  5165.8  328.66  5181.6  329.67  5199.8  330.12
#Mann= 3 ,-1 , 0
  4784.4     .16       0  4995.9     .07       0  5001.9     .16       0
Bank Sta=4995.9,5001.9
XS Rating Curve= 0 ,0
Exp/Cntr=0.3,0.1

Type RM Length L Ch R = 1 ,3980    ,413,413,413
BEGIN DESCRIPTION:
UNT070 IN ROCK 8.0
END DESCRIPTION:
XS GIS Cut Line= 3
      3653817.62     10166967.65      3653593.32     10167062.29
      3653246.69     10167382.88
#Sta/Elev= 30
  4587.3  327.63    4700  325.44    4734  323.92  4756.1  324.14    4834  321.77
  4852.4  320.47  4873.3  319.86  4951.6  313.69  4958.4  312.39  4979.9  310.32
  4986.7  308.45  4994.1   307.2  4997.9  305.53  5000.7  305.03  5003.9  305.53
  5015.1  308.26  5022.5  311.28  5043.4   311.8  5050.3  314.55  5078.6  316.77
  5185.2  320.58  5213.5  321.01  5220.3  321.61  5241.3  321.66  5248.7     321
  5262.9  321.36  5269.7  322.65  5291.2  322.74    5298  323.28  5302.9  322.97
#Mann= 4 ,-1 , 0
  4587.3     .05       0    4700     .16       0  4997.9     .07       0
  5003.9     .16       0
Bank Sta=4997.9,5003.9
XS Rating Curve= 0 ,0
Exp/Cntr=0.3,0.1

Type RM Length L Ch R = 1 ,3567    ,512,512,512
BEGIN DESCRIPTION:
UNT070 IN ROCK 7.0
END DESCRIPTION:
XS GIS Cut Line= 3
      3653406.67     10166810.75      3653204.95     10166957.12
       3652955.8     10167130.74
#Sta/Elev= 30
  4748.7  314.42  4759.6  314.88  4774.3  314.61  4860.1  315.83  4889.5  315.18
  4910.4  312.77  4931.2  308.01  4945.9  303.96  4952.1  304.78  4960.6  303.16
  4966.8  303.76  4975.3  301.83  4981.5  299.52  4988.8  297.62  4996.2  298.79
    5011  299.99  5025.8  302.94    5032   305.1  5038.1  306.53  5046.8  307.81
  5052.9  310.22  5061.6  311.09  5067.7  312.36  5082.6  313.04  5124.4  316.58
  5175.1  317.46  5196.4  318.79  5219.6  318.69  5297.8  323.56  5301.6  324.09
#Mann= 4 ,-1 , 0
  4748.7     .16       0  4981.5     .07       0    5011     .16       0
  5297.8     .05       0
Bank Sta=4981.5,5011
XS Rating Curve= 0 ,0
Exp/Cntr=0.3,0.1

Type RM Length L Ch R = 1 ,3055    ,562,562,562
BEGIN DESCRIPTION:
UNT070 IN ROCK 6.0
END DESCRIPTION:
XS GIS Cut Line= 3
       3653421.3     10166705.01      3653092.11     10166541.64
      3652838.86     10166486.41
#Sta/Elev= 30
  4662.2  311.34  4717.1   308.8  4769.2  308.08  4806.4  306.41    4814  306.63
    4842  305.06  4903.7  303.51  4918.1  302.34  4926.1  297.17  4931.6  296.16
  4940.4  296.02  4948.5  294.72  4962.7   293.6  4985.1  293.99  4993.3  291.14
  4998.6  290.36  5007.4   291.8  5015.7  295.05  5021.3  294.97  5026.9  297.04
  5032.3  297.04  5054.2  300.21  5091.1  300.61  5098.2  300.23  5103.3   298.1
  5132.1   302.8  5206.3  310.43  5240.2  313.84  5284.1  317.18  5288.9  316.82
#Mann= 4 ,-1 , 0
  4662.2     .16       0  4985.1     .07       0  5015.7     .16       0
  5206.3      .1       0
Bank Sta=4985.1,5015.7
XS Rating Curve= 0 ,0
Exp/Cntr=0.3,0.1

Type RM Length L Ch R = 1 ,2493    ,482,482,482
BEGIN DESCRIPTION:
UNT070 IN ROCK 5.0
END DESCRIPTION:
XS GIS Cut Line= 3
       3653691.1     10166515.31      3653356.01     10166154.39
      3653052.89     10166103.23
#Sta/Elev= 30
  4615.7  311.43  4624.6  311.96  4631.9  310.98  4638.7  312.09  4674.4  309.28
  4716.4  309.27  4879.6  302.12  4921.6  299.46    4950  299.92  4957.3  299.33
  4964.1  297.72  4971.5  294.95  4985.7   287.2  4992.2  285.43  5006.7  288.48
  5028.2  288.22    5035  290.29  5042.3  289.89  5049.2  293.28  5056.5  294.16
  5063.3  296.03  5105.9  297.28  5156.3   296.9  5216.7  298.56    5244  300.45
  5272.1  301.57  5277.2  300.96  5332.6  303.83  5337.7  303.59  5415.6  307.89
#Mann= 3 , 0 , 0
  4615.7     .16       0  4985.7     .07       0  5006.7     .16       0
Bank Sta=4985.7,5006.7
XS Rating Curve= 0 ,0
Exp/Cntr=0.3,0.1

Type RM Length L Ch R = 1 ,2011    ,506,506,506
BEGIN DESCRIPTION:
UNT070 IN ROCK 4.0
END DESCRIPTION:
XS GIS Cut Line= 3
      3653895.35     10165804.19      3653542.11     10165841.64
      3653052.87     10165931.84
#Sta/Elev= 30
  4622.8  310.54  4716.6  306.39  4736.3  302.87  4746.7  303.89  4766.8  303.32
    4787  300.52  4807.1  295.89    4834  293.52    4839  295.51  4847.3  292.48
  4887.5  286.63  4926.7  286.32  4931.7  284.41  4947.9  283.87  4988.2  282.36
  4998.1  280.24  5009.6  282.94  5028.9  284.09    5039  286.69  5062.6  289.62
  5130.6  290.26  5140.7  288.83  5150.9  284.51  5168.6  289.33  5173.7  288.48
  5191.6  291.05  5235.4  291.91  5323.8  294.96  5364.4  298.24  5475.5  304.39
#Mann= 4 ,-1 , 0
  4622.8     .16       0  4947.9     .07       0  5028.9     .16       0
  5235.4     .05       0
Bank Sta=4947.9,5028.9
XS Rating Curve= 0 ,0
Exp/Cntr=0.3,0.1

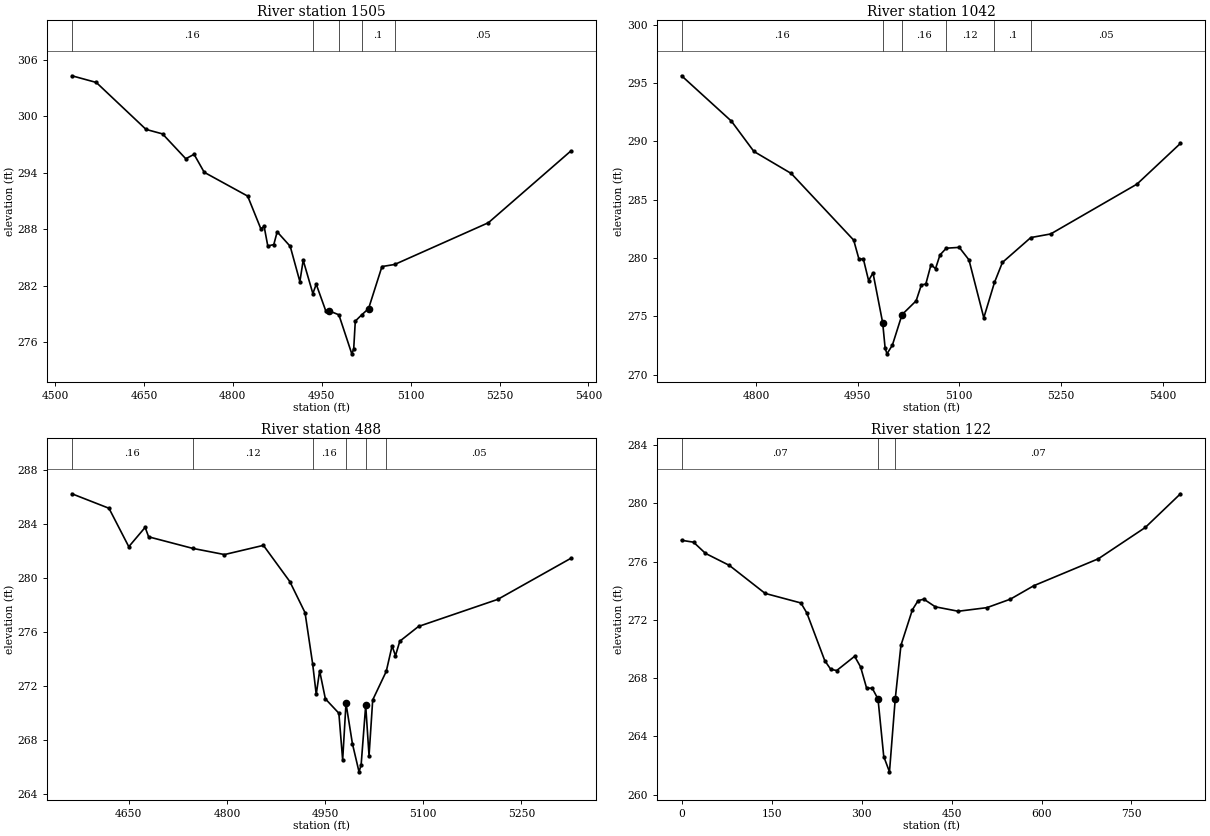
Type RM Length L Ch R = 1 ,1505    ,463,463,463
BEGIN DESCRIPTION:
UNT070 IN ROCK 3.0
END DESCRIPTION:
XS GIS Cut Line= 3
      3653736.45     10165289.53      3653536.45     10165389.53
      3652990.96     10165680.17
#Sta/Elev= 30
  4528.5  304.31  4569.6   303.6  4653.5  298.61  4681.4  298.13  4720.6  295.49
  4734.6  295.96  4751.7  294.05    4825  291.52  4847.2  288.05  4852.8  288.29
    4859  286.21  4869.1  286.37  4874.8  287.72  4896.8  286.18  4913.1  282.43
  4918.7   284.7    4935  281.16  4940.7  282.15    4957  279.28  4962.4  279.32
  4978.9   278.9  5000.7  274.75  5003.9  275.25  5006.6  278.23  5017.2  278.88
    5029  279.56  5051.6  284.03    5073  284.25  5231.2  288.69  5370.2  296.31
#Mann= 5 ,-1 , 0
  4528.5     .16       0    4935      .1       0  4978.9     .07       0
  5017.2      .1       0    5073     .05       0
Bank Sta=4962.4,5029
XS Rating Curve= 0 ,0
Exp/Cntr=0.3,0.1

Type RM Length L Ch R = 1 ,1042    ,554,554,554
BEGIN DESCRIPTION:
UNT070 IN ROCK 2.0
END DESCRIPTION:
XS GIS Cut Line= 3
      3653447.91     10164966.57      3653347.87     10165016.59
      3652942.11     10165491.64
#Sta/Elev= 30
  4689.9  295.61  4763.5  291.72  4796.6  289.13  4851.8  287.24    4944  281.53
  4951.7  279.92  4958.3  279.91    4966  278.07  4972.5  278.72  4986.8  274.45
  4990.4  272.29  4993.1  271.79  5001.1  272.53  5015.4  275.15  5036.2  276.33
  5043.9  277.69  5050.5  277.77  5058.2  279.44  5064.8  279.08  5071.4  280.26
  5080.7  280.84  5099.9  280.91  5114.2  279.84  5136.1  274.88  5151.9  277.91
  5163.6  279.62  5205.5  281.75  5234.9  282.06  5362.3  286.33  5426.5  289.82
#Mann= 6 ,-1 , 0
  4689.9     .16       0  4986.8     .07       0  5015.4     .16       0
  5080.7     .12       0  5151.9      .1       0  5205.5     .05       0
Bank Sta=4986.8,5015.4
XS Rating Curve= 0 ,0
Exp/Cntr=0.3,0.1

Type RM Length L Ch R = 1 ,488     ,366,366,366
BEGIN DESCRIPTION:
UNT070 IN ROCK 1.0
END DESCRIPTION:
XS GIS Cut Line= 3
      3653067.49     10164535.08      3652975.76     10164780.51
       3652848.7     10165264.39
#Sta/Elev= 30
  4563.1  286.21  4619.7  285.14    4650   282.3    4675  283.73  4680.3  283.03
  4747.4  282.18  4796.2  281.72  4855.7   282.4    4896  279.73  4919.3  277.43
    4931  273.63  4936.4  271.39  4941.6  273.13  4950.4  271.06    4971     270
  4976.8  266.55  4981.9  270.73  4991.7  267.75  5001.8  265.67    5005  266.17
    5012  270.58  5017.1  266.86  5022.7  270.98  5043.4  273.09  5052.3  274.97
  5057.5  274.25  5064.1  275.32  5092.7  276.41  5213.8  278.41  5325.4  281.44
#Mann= 6 ,-1 , 0
  4563.1     .16       0  4747.4     .12       0    4931     .16       0
  4981.9      .1       0    5012     .16       0  5043.4     .05       0
Bank Sta=4981.9,5012
XS Rating Curve= 0 ,0
Exp/Cntr=0.3,0.1

Type RM Length L Ch R = 1 ,122     ,0,0,0
XS GIS Cut Line= 4
      3652943.62    10164485.718     3652759.592    10164733.982
     3652754.384    10164933.635     3652775.217    10165254.815
#Sta/Elev= 30
       0277.458519.89263277.329139.78526276.561779.57051275.7378139.2484273.8155
198.9263273.1593208.8726272.4639238.7115269.1993248.6579268.6059258.6042268.5259
288.4431269.5014298.3894268.7709308.3357267.3302317.8876 267.307327.4394 266.569
336.9912262.6264346.5431261.5752356.0949266.5506365.6467270.2543384.7504272.6933
394.3022  273.32 403.854273.4204422.9577272.8963 461.165 272.591508.9242272.8378
 548.042273.4199587.1598274.3437694.7337 276.191772.9693278.3371831.6459280.6495
#Mann= 3 , 0 , 0
       0     .07       0327.4394     .05       0356.0949     .07       0
Bank Sta=327.4394,356.0949
XS Rating Curve= 0 ,0
Exp/Cntr=0.3,0.1

Chan Stop Cuts=-1
Use User Specified Reach Order=0
Composite Channel Slope=5