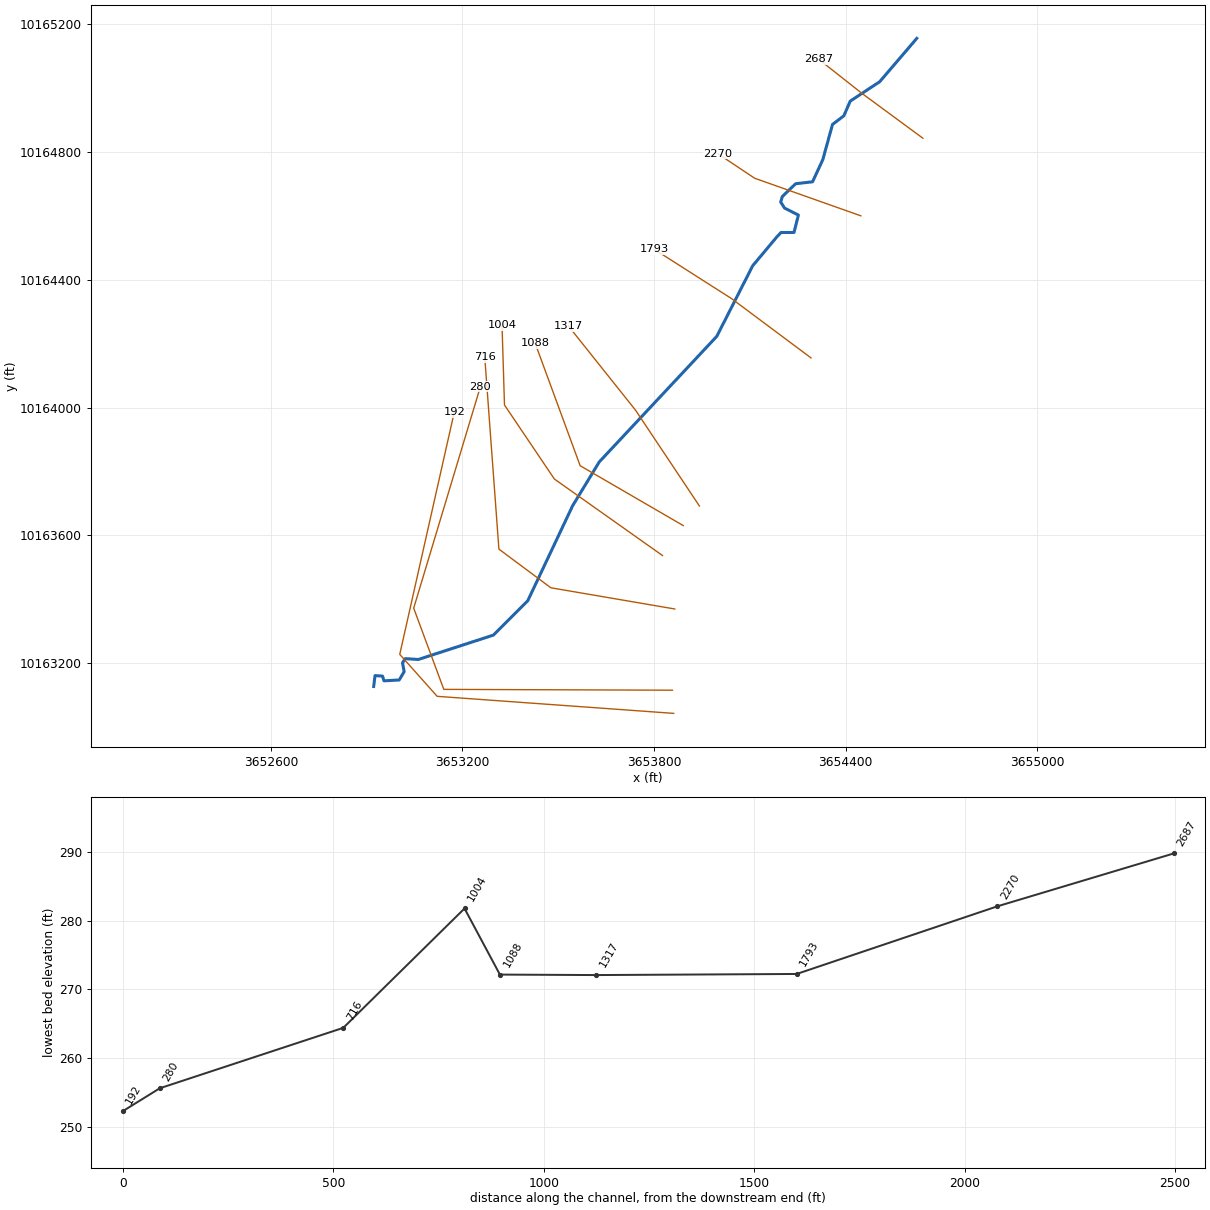
--- UNT071 IN ROCK.prj (project) ---

Proj Title=UNT071 IN ROCK Base Level Engineering
Current Plan=p01
Default Exp/Contr=0.3,0.1
English Units
Geom File=g01
Flow File=f01
Plan File=p01
Y Axis Title=Elevation
X Axis Title(PF)=Main Channel Distance
X Axis Title(XS)=Station
BEGIN DESCRIPTION:
UNT071 IN ROCK
END DESCRIPTION:
DSS Export Rating Curves= 0
DSS Export Rating Curve Sorted= 0
DSS Export Volume Flow Curves= 0
DXF OffsetX= 0
DXF OffsetY= 0
DXF ScaleX= 1
DXF ScaleY= 10

--- UNT071 IN ROCK.p01 (plan) ---

Plan Title=Multiple Run
Short Identifier=Multiple
Geom File=g01
Flow File=f01
Subcritical Flow
K Sum by GR= 0
Std Step Tol= 0.01
Critical Tol= 0.01
Num of Std Step Trials= 20
Max Error Tol= 0.3
Flow Tol Ratio= 0.001
Split Flow NTrial= 30
Split Flow Tol= 0.02
Split Flow Ratio= 0.02
Log Output Level= 0
Friction Slope Method= 1
Unsteady Friction Slope Method= 2
Unsteady Bridges Friction Slope Method= 1
Parabolic Critical Depth
Global Vel Dist=  1 , 1 , 1
Global Log Level= 0
CheckData=True
Encroach Param= -1, 0, 0, 0
BEGIN DESCRIPTION:
Multiple Run
END DESCRIPTION:

--- UNT071 IN ROCK.f01 (steady flow) ---

Flow Title=Multiple
Program Version=4.10
Number of Profiles= 7
Profile Names=10-year,25-year,50-year,1pct_min,100-year,1pct_plu,500-year
River Rch & RM=UNT071 IN ROCK,Reach-1         ,2687
     202     255     296     254     343     464     459
Boundary for River Rch & Prof#=UNT071 IN ROCK,Reach-1         , 1
Up Type= 0
Dn Type= 3
Dn Slope=0.01
Boundary for River Rch & Prof#=UNT071 IN ROCK,Reach-1         , 2
Up Type= 0
Dn Type= 3
Dn Slope=0.01
Boundary for River Rch & Prof#=UNT071 IN ROCK,Reach-1         , 3
Up Type= 0
Dn Type= 3
Dn Slope=0.01
Boundary for River Rch & Prof#=UNT071 IN ROCK,Reach-1         , 4
Up Type= 0
Dn Type= 3
Dn Slope=0.01
Boundary for River Rch & Prof#=UNT071 IN ROCK,Reach-1         , 5
Up Type= 0
Dn Type= 3
Dn Slope=0.01
Boundary for River Rch & Prof#=UNT071 IN ROCK,Reach-1         , 6
Up Type= 0
Dn Type= 3
Dn Slope=0.01
Boundary for River Rch & Prof#=UNT071 IN ROCK,Reach-1         , 7
Up Type= 0
Dn Type= 3
Dn Slope=0.01
DSS Import GetInterval= 0
DSS Import GetPeak= 0
DSS Import FillOption= 0

--- UNT071 IN ROCK.g01 (geometry) ---

Geom Title=Existing Conditions
Program Version=4.10

River Reach=UNT071 IN ROCK  ,Reach-1
Reach XY= 30
      3654622.95     10165156.38      3654506.88     10165020.52
      3654414.52     10164959.76      3654394.38     10164913.58
        3654359.     10164886.77      3654328.62     10164776.52
       3654296.5     10164707.08      3654243.55       10164701.
      3654201.88     10164661.07      3654196.67     10164643.71
       3654208.8     10164624.71      3654252.23     10164602.91
      3654238.34     10164548.22      3654197.54     10164548.22
      3654184.52     10164534.34        3654109.     10164444.06
      3653996.52     10164223.01      3653628.47     10163829.79
      3653545.13     10163692.63      3653404.51     10163394.89
      3653296.87     10163287.25      3653061.63     10163210.86
      3653020.83     10163213.47      3653012.15     10163200.45
      3653017.35     10163172.67      3653001.73     10163146.63
      3652953.99     10163144.02      3652949.65     10163158.78
      3652926.06     10163160.41      3652921.87      10163126.3

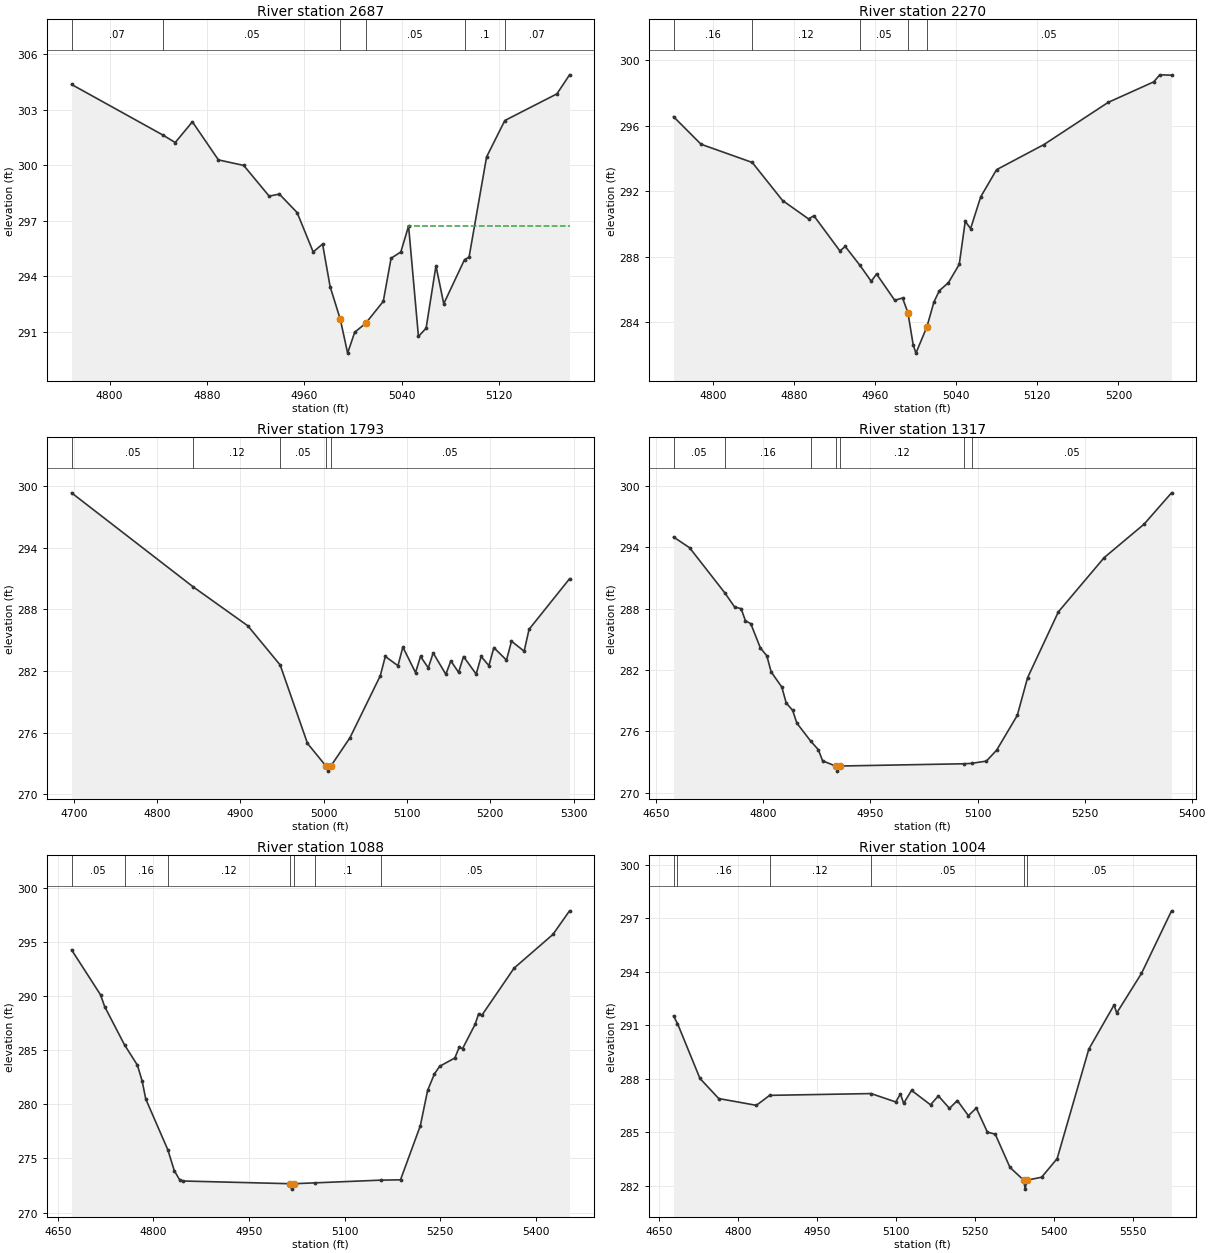
Type RM Length L Ch R = 1 ,2687    ,419,419,419
BEGIN DESCRIPTION:
UNT071 IN ROCK 6.0
END DESCRIPTION:
XS GIS Cut Line= 3
      3654642.09     10164843.52      3654452.16     10164983.27
       3654315.9     10165090.67
#Sta/Elev= 30
  4768.8  304.37  4843.7  301.64    4854  301.23  4868.1  302.35  4889.5  300.29
  4910.3  299.99  4931.2  298.33  4939.6  298.44  4954.2  297.44  4967.4  295.31
  4975.1  295.74  4981.3  293.44  4989.7  291.66  4995.7  289.84  5001.5  290.97
  5010.5  291.45    5025  292.64  5031.4  294.97  5039.4  295.31  5045.8  296.71
  5053.9  290.74  5060.2  291.19  5068.3  294.56  5074.7  292.51  5091.8   294.9
  5095.5  295.03  5109.9  300.45  5124.9  302.42  5167.7  303.86  5178.1  304.89
#Mann= 6 ,-1 , 0
  4768.8     .07       0  4843.7     .05       0  4989.7    .035       0
  5010.5     .05       0  5091.8      .1       0  5124.9     .07       0
#XS Ineff= 2 , 0
                         5045.45          296.72
Permanent Ineff=
       F       F
Bank Sta=4989.7,5010.5
XS Rating Curve= 0 ,0
Exp/Cntr=0.3,0.1

Type RM Length L Ch R = 1 ,2270    ,477,477,477
BEGIN DESCRIPTION:
UNT071 IN ROCK 5.0
END DESCRIPTION:
XS GIS Cut Line= 3
      3654447.67      10164600.5      3654115.17     10164718.16
       3654000.1     10164794.87
#Sta/Elev= 30
  4761.4  296.54  4788.5  294.86    4839  293.75  4868.9  291.43  4894.5  290.31
  4899.8   290.5  4925.4  288.36  4930.7  288.63  4945.2  287.48  4956.3  286.51
  4961.6  286.95  4979.5  285.35  4987.2  285.49  4992.5  284.59  4997.7  282.63
  5000.4  282.13  5011.3  283.75  5018.1  285.24  5023.4  285.93  5032.5  286.43
  5043.1  287.54    5049  290.16  5054.3  289.72  5064.3  291.66  5079.9  293.31
  5126.6  294.84  5189.9  297.41  5234.8  298.66  5240.8  299.09  5252.4  299.07
#Mann= 5 ,-1 , 0
  4761.4     .16       0    4839     .12       0  4945.2     .05       0
  4992.5    .035       0  5011.3     .05       0
Bank Sta=4992.5,5011.3
XS Rating Curve= 0 ,0
Exp/Cntr=0.3,0.1

Type RM Length L Ch R = 1 ,1793    ,476,476,476
BEGIN DESCRIPTION:
UNT071 IN ROCK 4.0
END DESCRIPTION:
XS GIS Cut Line= 3
      3654291.67     10164155.41      3654042.11     10164341.64
      3653800.58     10164495.59
#Sta/Elev= 30
  4697.4  299.34  4843.4  290.19    4909   286.4  4947.8  282.59  4980.6  274.96
  5002.7  272.76  5005.4  272.26  5008.7  272.76  5031.6  275.51    5068  281.54
    5074  283.42  5089.2  282.52  5095.1  284.33  5110.3  281.85  5116.3  283.42
  5125.6  282.31  5131.5  283.76  5146.7  281.68  5152.7  282.99    5162  281.87
  5167.9  283.41  5183.1   281.7  5189.1  283.42  5198.4  282.52  5204.3  284.28
  5219.5  283.06  5225.5   284.9  5240.7  283.93  5246.6  286.06  5295.2  290.98
#Mann= 5 ,-1 , 0
  4697.4     .05       0  4843.4     .12       0  4947.8     .05       0
  5002.7     .03       0  5008.7     .05       0
Bank Sta=5002.7,5008.7
XS Rating Curve= 0 ,0
Exp/Cntr=0.3,0.1

Type RM Length L Ch R = 1 ,1317    ,229,229,229
BEGIN DESCRIPTION:
UNT071 IN ROCK 3.0
END DESCRIPTION:
XS GIS Cut Line= 3
      3653942.11     10163691.63      3653742.11     10163991.64
      3653531.98     10164255.15
#Sta/Elev= 30
  4674.2     295  4696.7  293.95  4746.1  289.53  4759.8  288.15  4768.9  287.99
  4774.9  286.81  4782.4  286.52  4795.9  284.14  4804.9  283.38  4810.9  281.81
  4825.9  280.32    4832  278.77    4841  278.05    4847  276.79  4866.3  275.04
    4877   274.2    4883  273.11  4901.1   272.6  4903.8   272.1  4907.1   272.6
  5081.5  272.82  5091.6  272.86  5112.4  273.08  5126.8  274.15  5155.7  277.55
  5170.1  281.23  5213.3  287.68  5277.4  292.98  5333.4  296.26  5371.8  299.32
#Mann= 7 ,-1 , 0
  4674.2     .05       0  4746.1     .16       0  4866.3     .12       0
  4901.1     .07       0  4907.1     .12       0  5081.5      .1       0
  5091.6     .05       0
Bank Sta=4901.1,4907.1
XS Rating Curve= 0 ,0
Exp/Cntr=0.3,0.1

Type RM Length L Ch R = 1 ,1088    ,84,84,84
BEGIN DESCRIPTION:
Mapping XS 286ae71b
END DESCRIPTION:
XS GIS Cut Line= 3
      3653891.44     10163630.29      3653568.56     10163817.77
      3653427.93     10164200.59
#Sta/Elev= 30
  4671.6  294.27  4717.1  290.11  4723.5  289.03  4754.7  285.49  4774.9  283.62
  4782.3  282.16    4788  280.49  4822.7  275.79  4832.7  273.88    4841  273.04
  4846.8  272.92  5014.4  272.67  5017.1  272.17  5020.4  272.67  5053.5  272.75
  5156.8     273  5187.6  273.03  5218.7  278.02  5230.2   281.3  5240.9  282.82
  5249.2  283.52  5272.8  284.28  5279.7  285.27    5285  285.15  5304.8  287.41
  5310.1  288.36  5315.5  288.25  5365.8  292.58  5426.7  295.69  5452.8  297.87
#Mann= 7 ,-1 , 0
  4671.6     .05       0  4754.7     .16       0  4822.7     .12       0
  5014.4     .07       0  5020.4     .12       0  5053.5      .1       0
  5156.8     .05       0
Bank Sta=5014.4,5020.4
XS Rating Curve= 0 ,0
Exp/Cntr=0.3,0.1

Type RM Length L Ch R = 1 ,1004    ,288,288,288
BEGIN DESCRIPTION:
Mapping XS ed6c43ce
END DESCRIPTION:
XS GIS Cut Line= 4
      3653826.37     10163536.52      3653487.83      10163776.1
      3653331.58     10164007.88      3653323.83      10164258.6
#Sta/Elev= 30
  4677.8  291.52  4685.3   291.1  4727.9  288.02  4763.6  286.89    4835  286.51
  4860.2  287.07  5052.7  287.17  5099.5   286.7  5108.5  287.15  5114.5  286.62
  5129.5  287.35  5165.5  286.54  5180.4  287.04  5201.5  286.34  5216.4  286.78
  5237.4  285.93  5252.4  286.36  5273.4  285.01  5288.4  284.89  5316.3  283.03
  5342.4  282.31  5345.1  281.81  5348.4  282.31  5376.4  282.48  5405.8  283.52
  5465.9  289.66  5513.9  292.14  5518.9  291.69  5565.9  293.91  5622.9  297.42
#Mann= 6 ,-1 , 0
  4677.8     .05       0  4685.3     .16       0  4860.2     .12       0
  5052.7     .05       0  5342.4     .07       0  5348.4     .05       0
Bank Sta=5342.4,5348.4
XS Rating Curve= 0 ,0
Exp/Cntr=0.3,0.1

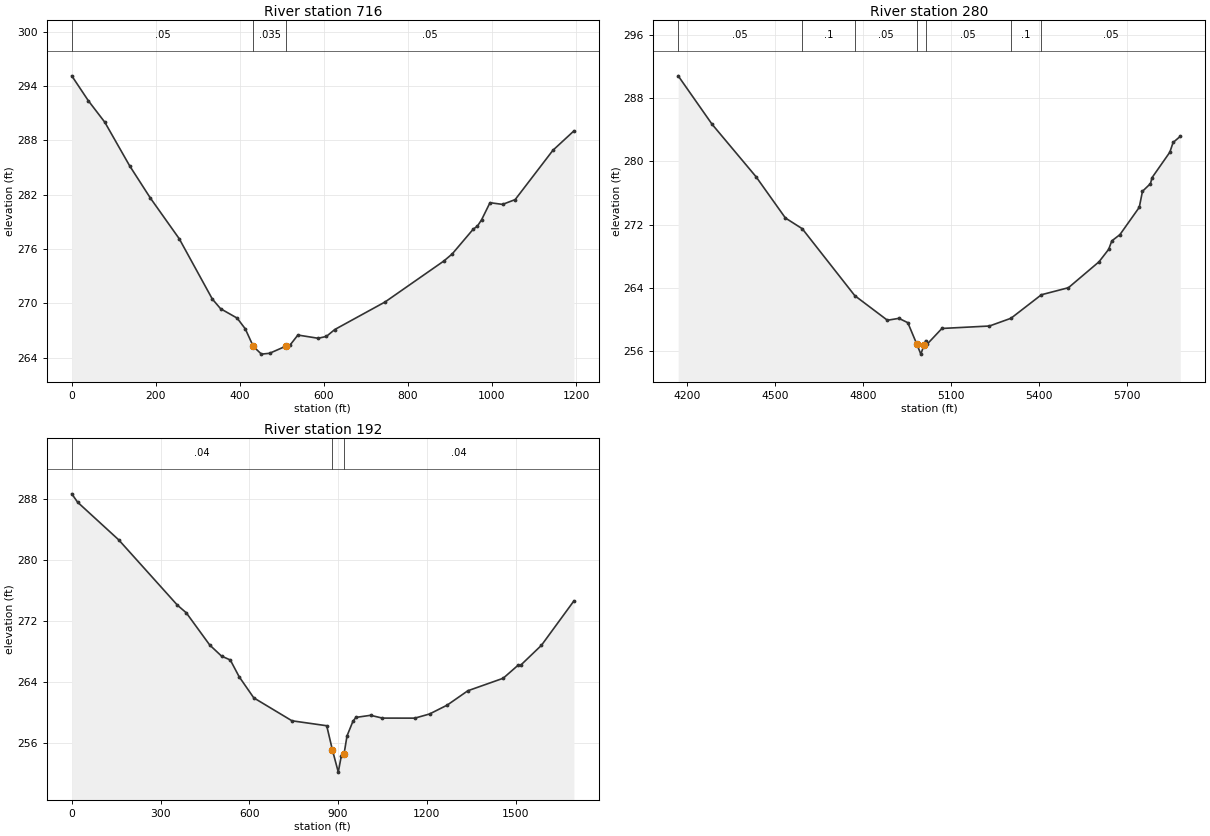
Type RM Length L Ch R = 1 ,716     ,436,436,436
XS GIS Cut Line= 4
     3653864.873    10163369.033     3653476.852     10163435.44
     3653314.092    10163556.533     3653269.821    10164156.794
#Sta/Elev= 30
       0295.117239.35312292.374978.70624289.9913137.7359285.1861186.9273281.6379
255.7953277.1365334.5015 270.484354.1781269.4169393.5312268.3812 412.807267.2032
432.0828265.2522451.3586264.4055470.6344264.4968 509.186265.2777518.8239265.3679
538.0997266.5123586.2892266.1558605.9116266.3578625.8807267.1195745.6953270.1647
885.4789274.6812905.4479275.4657955.3707278.1942965.3552 278.532975.3398279.2348
995.3088281.11731025.262280.92961055.216281.45871145.077286.9018    1195289.0382
#Mann= 3 ,-1 , 0
       0     .05       0432.0828    .035       0 509.186     .05       0
Bank Sta=432.0828,509.186
XS Rating Curve= 0 ,0
Exp/Cntr=0.3,0.1

Type RM Length L Ch R = 1 ,280     ,88,88,88
BEGIN DESCRIPTION:
UNT071 IN ROCK 1.0
END DESCRIPTION:
XS GIS Cut Line= 4
      3653857.63     10163114.65      3653141.48     10163117.25
      3653047.18     10163371.57      3653256.07      10164065.2
#Sta/Elev= 30
  4170.1  290.83  4285.6   284.7  4435.6  278.05  4535.6  272.83  4593.1  271.47
  4772.3  262.99  4883.4  259.88  4922.6  260.12    4953  259.57  4983.4  256.87
  4997.3  255.59  5008.3  256.74  5013.7   257.3  5019.1  256.86  5069.2  258.84
  5231.2  259.15  5304.6  260.13  5408.4  263.11  5500.5     264  5604.7  267.28
  5637.7  268.86  5648.4  269.93    5676  270.72    5742  274.18  5752.9  276.21
  5780.2  277.18  5785.4  277.93  5846.2  281.16  5857.3  282.39  5881.9  283.17
#Mann= 7 ,-1 , 0
  4170.1     .05       0  4593.1      .1       0  4772.3     .05       0
  4983.4    .035       0  5013.7     .05       0  5304.6      .1       0
  5408.4     .05       0
Bank Sta=4983.4,5008.3
XS Rating Curve= 0 ,0
Exp/Cntr=0.3,0.1

Type RM Length L Ch R = 1 ,192     ,0,0,0
XS GIS Cut Line= 4
     3653861.592    10163042.073     3653120.707    10163095.458
     3653003.519    10163226.969     3653174.092    10163984.781
#Sta/Elev= 30
       0288.677719.84532 287.577158.7626282.6484357.2158274.0947386.9838273.1046
466.3651268.8806506.0557267.4383535.8237266.9241565.5917264.7401 615.205261.9652
744.1996258.9637861.6312258.3169881.2031255.1035 900.775252.2434 910.561254.2894
 920.347254.6407930.3056256.9891950.2228258.8907960.1814259.40581009.974259.6825
1049.809 259.3171159.354259.31131209.147259.85361268.899261.01771338.609262.8956
1458.112 264.5331507.905266.22121517.864266.26661587.574268.85381697.119274.6591
#Mann= 3 , 0 , 0
       0     .04       0881.2031    .035       0 920.347     .04       0
Bank Sta=881.2031,920.347
XS Rating Curve= 0 ,0
Exp/Cntr=0.3,0.1
Stream Node=UNT071 IN ROCK  ,Reach-1         , 0 , 0 ,Upstream end
Stream Node=UNT071 IN ROCK  ,Reach-1         , 0 , 1 ,Downstream end

Chan Stop Cuts=-1
Use User Specified Reach Order=0
Composite Channel Slope=5