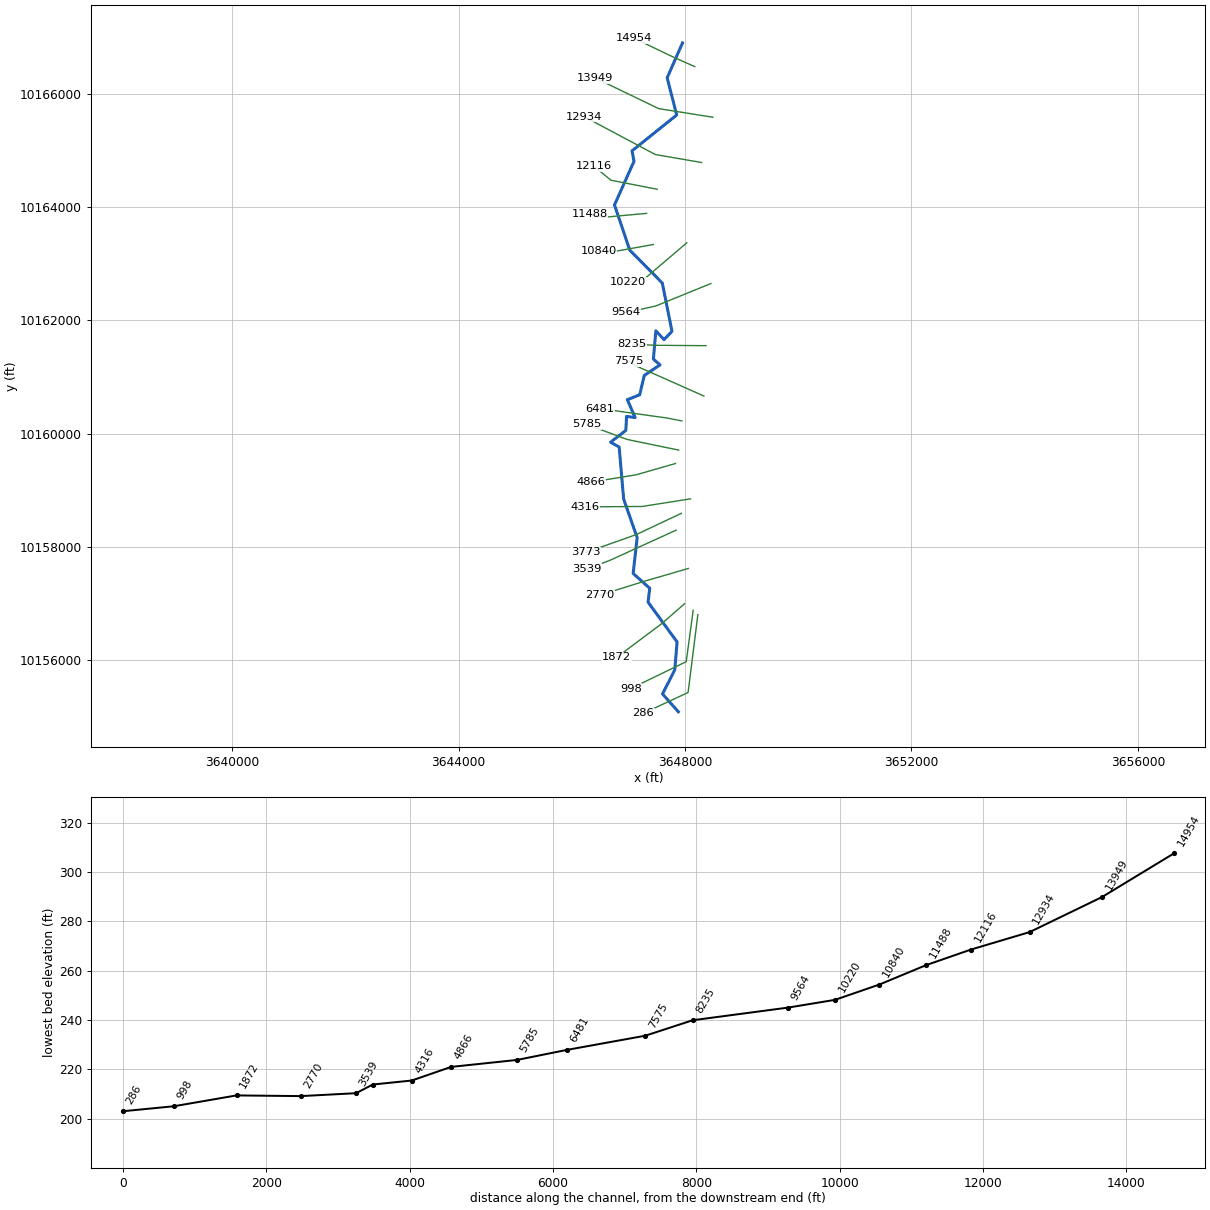
--- UNT072 IN ROCK.prj (project) ---

Proj Title=UNT072 IN ROCK Base Level Engineering
Current Plan=p01
Default Exp/Contr=0.3,0.1
English Units
Geom File=g01
Flow File=f01
Plan File=p01
Y Axis Title=Elevation
X Axis Title(PF)=Main Channel Distance
X Axis Title(XS)=Station
BEGIN DESCRIPTION:
UNT072 IN ROCK
END DESCRIPTION:
DSS Export Rating Curves= 0
DSS Export Rating Curve Sorted= 0
DSS Export Volume Flow Curves= 0
DXF OffsetX= 0
DXF OffsetY= 0
DXF ScaleX= 1
DXF ScaleY= 10

--- UNT072 IN ROCK.p01 (plan) ---

Plan Title=Multiple Run
Short Identifier=Multiple
Geom File=g01
Flow File=f01
Subcritical Flow
K Sum by GR= 0
Std Step Tol= 0.01
Critical Tol= 0.01
Num of Std Step Trials= 20
Max Error Tol= 0.3
Flow Tol Ratio= 0.001
Split Flow NTrial= 30
Split Flow Tol= 0.02
Split Flow Ratio= 0.02
Log Output Level= 0
Friction Slope Method= 1
Unsteady Friction Slope Method= 2
Unsteady Bridges Friction Slope Method= 1
Parabolic Critical Depth
Global Vel Dist=  1 , 1 , 1
Global Log Level= 0
CheckData=True
Encroach Param= -1, 0, 0, 0
BEGIN DESCRIPTION:
Multiple Run
END DESCRIPTION:

--- UNT072 IN ROCK.f01 (steady flow) ---

Flow Title=Multiple
Program Version=4.10
Number of Profiles= 7
Profile Names=10-year,25-year,50-year,1pct_min,100-year,1pct_plu,500-year
River Rch & RM=UNT072 IN ROCK,Reach-1         ,14954
     566     764     927     826    1117    1510    1622
River Rch & RM=UNT072 IN ROCK,Reach-1         ,6481
     735    1008    1234    1109    1500    2029    2218
River Rch & RM=UNT072 IN ROCK,Reach-1         ,4866
     937    1297    1599    1444    1953    2641    2916
Boundary for River Rch & Prof#=UNT072 IN ROCK,Reach-1         , 1
Up Type= 0
Dn Type= 3
Dn Slope=0.01
Boundary for River Rch & Prof#=UNT072 IN ROCK,Reach-1         , 2
Up Type= 0
Dn Type= 3
Dn Slope=0.01
Boundary for River Rch & Prof#=UNT072 IN ROCK,Reach-1         , 3
Up Type= 0
Dn Type= 3
Dn Slope=0.01
Boundary for River Rch & Prof#=UNT072 IN ROCK,Reach-1         , 4
Up Type= 0
Dn Type= 3
Dn Slope=0.01
Boundary for River Rch & Prof#=UNT072 IN ROCK,Reach-1         , 5
Up Type= 0
Dn Type= 3
Dn Slope=0.01
Boundary for River Rch & Prof#=UNT072 IN ROCK,Reach-1         , 6
Up Type= 0
Dn Type= 3
Dn Slope=0.01
Boundary for River Rch & Prof#=UNT072 IN ROCK,Reach-1         , 7
Up Type= 0
Dn Type= 3
Dn Slope=0.01
DSS Import GetInterval= 0
DSS Import GetPeak= 0
DSS Import FillOption= 0

--- UNT072 IN ROCK.g01 (geometry) ---

Geom Title=Existing Conditions
Program Version=4.10

River Reach=UNT072 IN ROCK  ,Reach-1
Reach XY= 30
      3647956.42     10166905.64      3647685.16     10166289.32
      3647853.21     10165630.74      3647064.43     10164997.81
      3647099.49     10164812.45      3646754.61     10164041.67
      3647024.33     10163242.48      3647599.14     10162660.57
      3647769.97     10161807.45      3647630.47     10161659.92
      3647484.63     10161816.17      3647442.27     10161315.65
      3647559.18      10161213.4      3647280.79     10161027.51
      3647199.91      10160685.1      3646981.52     10160599.07
      3647119.06     10160282.73      3646967.71      10160302.8
      3646954.71     10160055.24      3646685.69     10159846.61
      3646837.15     10159761.16      3646916.13     10158843.31
      3647155.08     10158159.92      3647084.15     10157527.16
      3647376.85     10157264.35      3647347.43     10157019.31
      3647860.39     10156315.93      3647819.27     10155822.82
      3647603.06     10155396.53      3647882.11     10155081.64

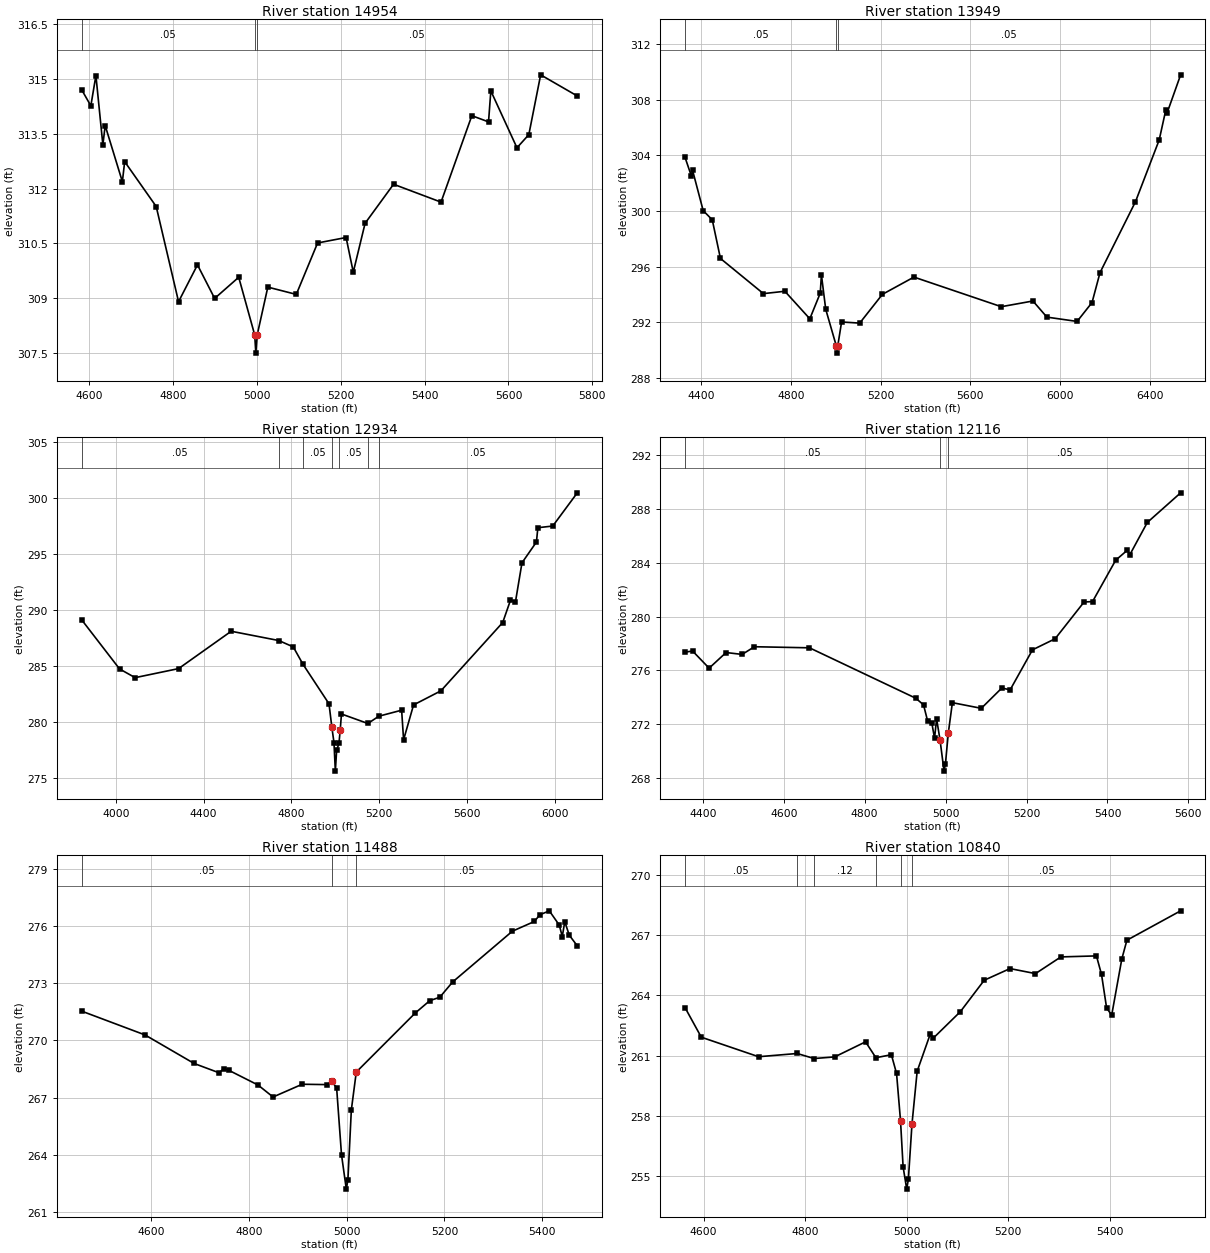
Type RM Length L Ch R = 1 ,14954   ,1005,1005,1005
BEGIN DESCRIPTION:
UNT072 IN ROCK 28.0
END DESCRIPTION:
XS GIS Cut Line= 3
      3648173.12     10166486.06      3647783.65     10166659.38
      3647102.38     10166986.44
#Sta/Elev= 30
  4582.2  314.71    4604  314.27  4616.1   315.1  4632.7   313.2  4638.2  313.73
  4679.2  312.19  4684.7  312.74  4759.9  311.51  4813.2   308.9  4858.3  309.91
  4899.3  308.99  4956.7  309.57  4994.8  307.99  4997.5  307.49  5000.8  307.99
  5026.1   309.3    5094   309.1  5144.8  310.51  5212.8  310.66  5229.9  309.71
  5258.1  311.05    5326  312.12  5439.2  311.63  5512.7     314  5552.5  313.83
    5558  314.68  5620.3  313.12  5648.6  313.48  5676.8  315.12  5764.2  314.54
#Mann= 3 ,-1 , 0
  4582.2     .05       0  4994.8     .03       0  5000.8     .05       0
Bank Sta=4994.8,5000.8
XS Rating Curve= 0 ,0
Exp/Cntr=0.3,0.1

Type RM Length L Ch R = 1 ,13949   ,1009,1009,1009
BEGIN DESCRIPTION:
UNT072 IN ROCK 26.0
END DESCRIPTION:
XS GIS Cut Line= 3
      3648492.06     10165591.65      3647535.72     10165743.79
      3646416.01      10166284.5
#Sta/Elev= 30
  4326.8  303.85  4355.3   302.5  4360.4  302.92  4407.8  300.02  4448.3  299.36
  4484.8  296.58  4676.5  294.05  4772.3  294.22  4883.7  292.24  4930.3  294.09
  4935.4  295.41  4954.6  292.93  5002.2  290.27  5004.9  289.77  5008.2  290.27
  5025.4  292.01  5106.4  291.93  5207.7     294  5348.4  295.24  5738.2  293.11
  5879.4  293.52  5941.7  292.36  6076.5  292.05  6143.2  293.41  6178.8  295.56
    6337  300.66    6443  305.11  6472.6  307.28  6478.2  307.05  6538.6  309.79
#Mann= 3 ,-1 , 0
  4326.8     .05       0  5002.2     .03       0  5008.2     .05       0
Bank Sta=5002.2,5008.2
XS Rating Curve= 0 ,0
Exp/Cntr=0.3,0.1

Type RM Length L Ch R = 1 ,12934   ,818,818,818
BEGIN DESCRIPTION:
UNT072 IN ROCK 24.0
END DESCRIPTION:
XS GIS Cut Line= 3
      3648292.07     10164791.65      3647475.62     10164932.24
      3646213.46     10165604.51
#Sta/Elev= 30
  3844.3  289.13  4016.8  284.74  4087.8  283.96  4285.9  284.77  4525.6  288.11
  4742.5  287.28  4808.4  286.71  4852.3  285.17  4971.3  281.62  4984.1  279.56
    4994  278.15  5000.2   275.6  5006.1  277.45  5016.7  278.09  5022.4  279.28
  5028.1  280.71  5148.5  279.86  5198.1  280.51  5302.3  281.05  5311.2   278.4
  5356.6  281.52  5481.2  282.78  5762.9  288.89  5798.4  290.89  5821.1  290.75
  5850.7  294.23  5916.6  296.09  5923.1  297.37    5991  297.52  6102.8  300.49
#Mann= 7 ,-1 , 0
  3844.3     .05       0  4742.5      .1       0  4852.3     .05       0
  4984.1    .035       0  5016.7     .05       0  5148.5      .1       0
  5198.1     .05       0
Bank Sta=4984.1,5022.4
XS Rating Curve= 0 ,0
Exp/Cntr=0.3,0.1

Type RM Length L Ch R = 1 ,12116   ,628,628,628
BEGIN DESCRIPTION:
UNT072 IN ROCK 22.0
END DESCRIPTION:
XS GIS Cut Line= 3
      3647510.45     10164317.91      3646690.62     10164478.34
      3646391.61     10164727.51
#Sta/Elev= 30
  4356.2  277.36  4374.9  277.44  4415.7  276.17  4457.6  277.33  4497.2  277.19
  4527.7  277.76  4663.7  277.68  4926.3  273.94  4945.5  273.45  4955.7  272.24
  4965.9  272.12  4972.7  270.97  4977.8  272.41  4986.3  270.84  4996.2  268.53
  4999.5  269.03  5006.7  271.35  5016.8  273.61  5088.2  273.19  5139.1   274.7
  5159.5  274.56  5214.7  277.53  5270.6  278.35  5342.2  281.08  5363.1  281.11
  5420.3  284.18    5449  284.92  5455.5   284.6  5498.4  286.98  5580.8  289.18
#Mann= 3 , 0 , 0
  4356.2     .05       0  4986.3    .035       0  5006.7     .05       0
Bank Sta=4986.3,5006.7
XS Rating Curve= 0 ,0
Exp/Cntr=0.3,0.1

Type RM Length L Ch R = 1 ,11488   ,648,648,648
BEGIN DESCRIPTION:
UNT072 IN ROCK 21.0
END DESCRIPTION:
XS GIS Cut Line= 3
      3647321.04     10163891.86      3646564.88     10163822.71
      3646316.03     10163872.48
#Sta/Elev= 30
  4458.5  271.54    4588  270.29  4688.4  268.79  4739.5   268.3  4748.6  268.51
  4758.7  268.44  4818.9  267.66  4849.7  267.03  4909.3   267.7  4959.8  267.68
  4969.6  267.85  4979.6  267.52  4989.6     264  4999.4  262.19  5002.7  262.69
  5009.7  266.35  5019.8  268.34  5140.3  271.44    5170  272.09  5190.5  272.27
  5216.7  273.07  5338.9  275.74  5383.8  276.25    5395   276.6  5414.4  276.81
  5434.8  276.06  5440.9  275.46    5446  276.24  5455.2  275.53  5471.6  274.97
#Mann= 3 , 0 , 0
  4458.5     .05       0  4969.6     .03       0  5019.8     .05       0
Bank Sta=4969.6,5019.8
XS Rating Curve= 0 ,0
Exp/Cntr=0.3,0.1

Type RM Length L Ch R = 1 ,10840   ,620,620,620
BEGIN DESCRIPTION:
UNT072 IN ROCK 19.0
END DESCRIPTION:
XS GIS Cut Line= 3
      3647442.09     10163341.64      3646798.61     10163226.85
      3646476.35     10163226.85
#Sta/Elev= 30
  4563.5  263.39  4595.5  261.92  4708.3  260.95  4784.3  261.11  4817.6  260.86
  4858.1  260.94    4919  261.69  4939.3   260.9  4969.8  261.05    4980  260.12
  4987.8  257.77  4992.9  255.48    5000  254.37  5003.3  254.87  5010.4  257.61
  5020.6  260.23  5046.7   262.1  5051.8  261.86  5105.7  263.19  5152.6  264.75
  5203.4  265.33  5253.6  265.08  5303.6  265.91  5373.6  265.96  5383.6  265.04
  5393.6  263.38  5403.6  263.01  5423.6  265.81  5433.6  266.74  5539.4   268.2
#Mann= 6 ,-1 , 0
  4563.5     .05       0  4784.3      .1       0  4817.6     .12       0
  4939.3     .05       0  4987.8    .035       0  5010.4     .05       0
Bank Sta=4987.8,5010.4
XS Rating Curve= 0 ,0
Exp/Cntr=0.3,0.1

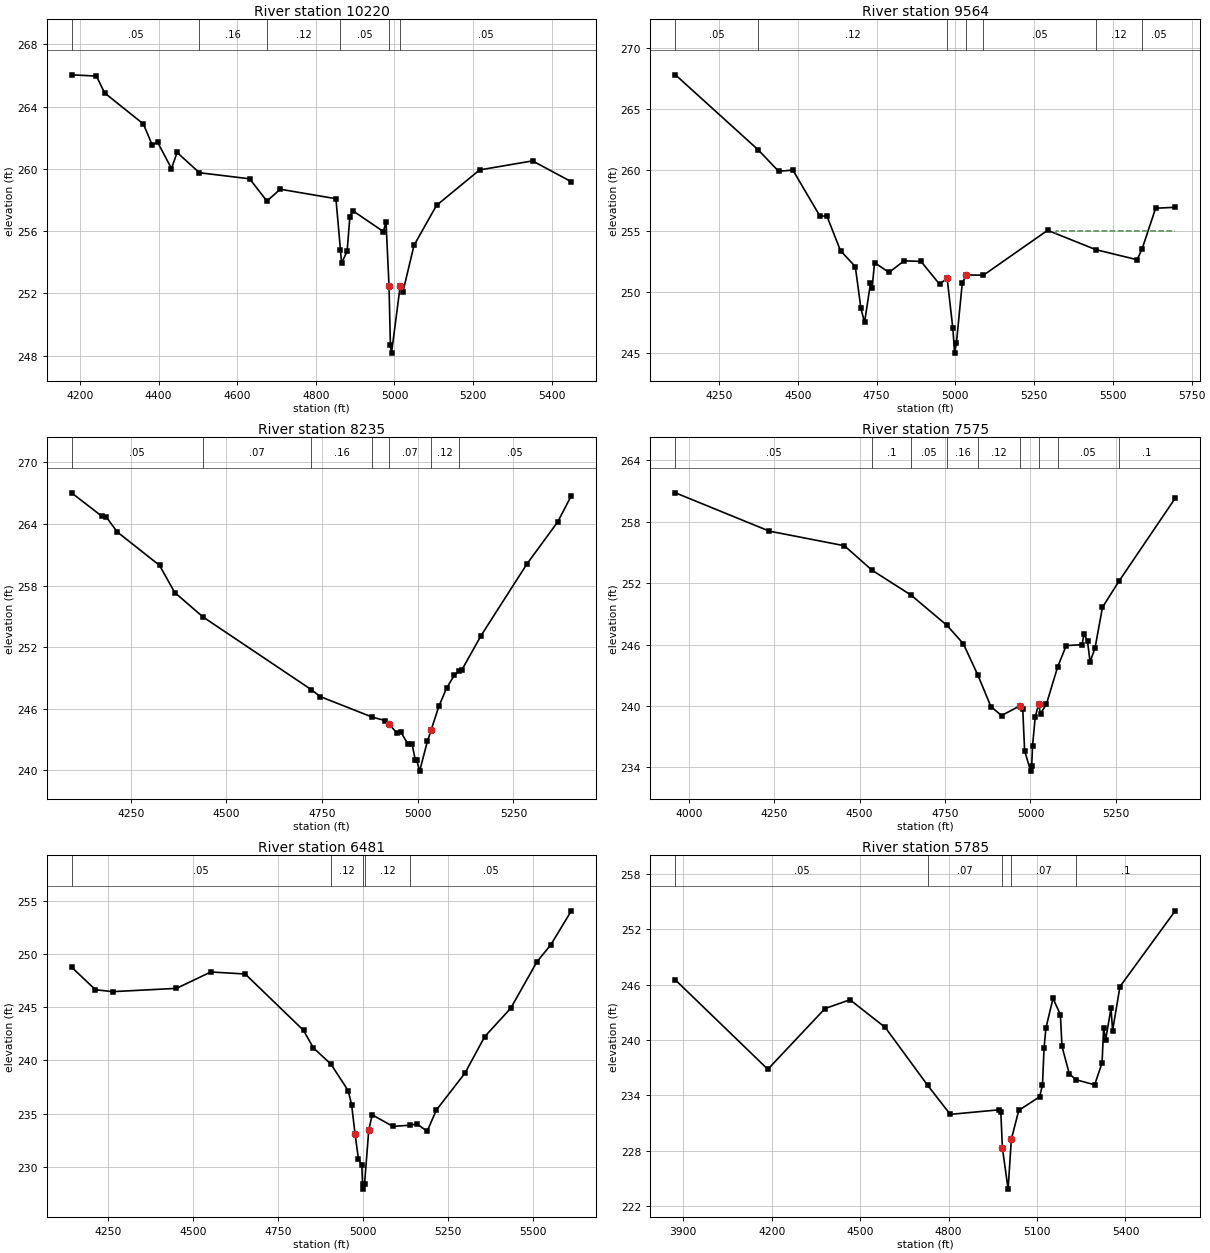
Type RM Length L Ch R = 1 ,10220   ,656,656,656
BEGIN DESCRIPTION:
UNT072 IN ROCK 18.0
END DESCRIPTION:
XS GIS Cut Line= 3
      3648031.17     10163371.15      3647292.11     10162741.64
      3646998.62     10162675.37
#Sta/Elev= 30
  4178.3  266.04  4241.6  265.96  4262.4  264.88  4361.2  262.88  4383.2  261.55
  4397.5   261.7  4432.6  260.02  4446.9  261.05  4503.6  259.75  4631.4  259.36
  4675.4  257.93  4709.3  258.69    4851  258.08  4862.6  254.77  4865.3  253.93
  4879.5  254.71  4886.4   256.9  4893.8  257.31  4971.8  255.97  4978.4   256.6
  4986.1  252.46  4989.6  248.66  4992.4  248.16  5014.6  252.49  5021.2  252.07
  5049.7  255.09  5106.9  257.65  5216.5  259.93  5351.2  260.51    5450  259.17
#Mann= 6 ,-1 , 0
  4178.3     .05       0  4503.6     .16       0  4675.4     .12       0
  4862.6     .05       0  4986.1    .035       0  5014.6     .05       0
Bank Sta=4986.1,5014.6
XS Rating Curve= 0 ,0
Exp/Cntr=0.3,0.1

Type RM Length L Ch R = 1 ,9564    ,1329,1329,1329
BEGIN DESCRIPTION:
UNT072 IN ROCK 17.0
END DESCRIPTION:
XS GIS Cut Line= 3
      3648457.22     10162651.59      3647482.01     10162253.93
      3646961.33     10162140.33
#Sta/Elev= 30
  4111.8  267.84  4374.5  261.69  4439.3  259.93  4484.5  260.03  4570.3  256.26
  4592.5  256.26  4635.7  253.42  4682.7  252.11  4700.5  248.69  4712.1  247.55
  4730.8  250.73  4736.2  250.36  4743.7  252.44  4789.6  251.64  4837.7  252.59
  4891.2  252.54  4950.1  250.67  4974.1  251.16  4992.1  247.08  4997.9  245.02
  5003.6  245.87  5022.2  250.79  5035.3  251.43  5089.3  251.41  5292.9  255.09
  5446.5   253.5  5576.9  252.68  5592.8  253.57  5635.7   256.9  5697.9  256.98
#Mann= 7 ,-1 , 0
  4111.8     .05       0  4374.5     .12       0  4974.1     .07       0
  5035.3     .12       0  5089.3     .05       0  5446.5     .12       0
  5592.8     .05       0
#XS Ineff= 2 , 0
                         5320.93          255.05
Permanent Ineff=
       F       F
Bank Sta=4974.1,5035.3
XS Rating Curve= 0 ,0
Exp/Cntr=0.3,0.1

Type RM Length L Ch R = 1 ,8235    ,660,660,660
BEGIN DESCRIPTION:
UNT072 IN ROCK 15.0
END DESCRIPTION:
XS GIS Cut Line= 3
        3648372.     10161553.32      3647469.95      10161560.1
       3647066.3     10161581.67
#Sta/Elev= 30
  4095.2  267.04  4175.1  264.74  4185.1  264.72  4215.1  263.21  4325.1  259.97
  4365.1  257.31    4439  254.93  4722.1  247.84  4745.1  247.17  4881.6  245.16
  4915.1  244.83  4925.1  244.48  4945.1  243.64  4955.1  243.75  4975.1  242.51
  4985.1  242.55  4993.7  240.98  4997.3  240.98  5004.9   239.9  5025.2   242.8
  5035.2  243.93  5055.2  246.22  5075.2  247.98  5095.3  249.23  5107.3  249.62
  5115.1  249.76  5165.4  253.11  5285.5  260.11  5365.6  264.19  5401.5  266.76
#Mann= 7 ,-1 , 0
  4095.2     .05       0    4439     .07       0  4722.1     .16       0
  4881.6     .12       0  4925.1     .07       0  5035.2     .12       0
  5107.3     .05       0
Bank Sta=4925.1,5035.2
XS Rating Curve= 0 ,0
Exp/Cntr=0.3,0.1

Type RM Length L Ch R = 1 ,7575    ,1094,1094,1094
BEGIN DESCRIPTION:
UNT072 IN ROCK 13.0
END DESCRIPTION:
XS GIS Cut Line= 3
      3648334.14     10160663.33      3647153.92     10161187.53
      3647008.34     10161277.44
#Sta/Elev= 30
    3961  260.82  4235.7  257.08  4455.6  255.65  4535.7  253.28  4650.5  250.83
  4755.5  247.88  4803.5  246.08  4845.9  243.03  4884.2  239.94  4915.2  239.07
  4969.9  240.03  4977.3  239.72  4982.8  235.64  5000.3  233.64  5003.5  234.14
    5006  236.11  5013.7  238.89  5023.8  240.19  5029.3  239.24  5046.5  240.18
  5079.5  243.82  5104.5   245.9    5151  245.99  5156.5  247.07  5166.8  246.33
  5174.3  244.33  5188.7  245.64  5210.6  249.64  5258.5  252.17  5423.5   260.3
#Mann= 9 ,-1 , 0
    3961     .05       0  4535.7      .1       0  4650.5     .05       0
  4755.5     .16       0  4845.9     .12       0  4969.9     .07       0
  5023.8     .12       0  5079.5     .05       0  5258.5      .1       0
Bank Sta=4969.9,5023.8
XS Rating Curve= 0 ,0
Exp/Cntr=0.3,0.1

Type RM Length L Ch R = 1 ,6481    ,696,696,696
BEGIN DESCRIPTION:
UNT072 IN ROCK 12.0
END DESCRIPTION:
XS GIS Cut Line= 3
      3647945.34     10160222.72      3647695.38     10160272.71
      3646492.09     10160441.64
#Sta/Elev= 30
  4143.5  248.77  4213.8  246.64  4264.8  246.46  4452.2  246.77  4553.2  248.31
  4654.2  248.12  4825.8  242.82  4854.7  241.17  4906.3  239.65  4957.1  237.15
  4967.2  235.84  4977.3  233.08  4987.4  230.71  4997.3  230.12  4999.3  228.39
  5002.1  227.89  5005.3  228.39  5017.7  233.46  5027.8  234.88  5088.4  233.79
  5139.5   233.9  5159.1  234.03  5189.4  233.33  5216.3  235.32  5300.4  238.79
  5358.9  242.24  5435.2   244.9  5512.5  249.28  5552.9  250.86  5613.5  254.06
#Mann= 5 ,-1 , 0
  4143.5     .05       0  4906.3     .12       0  4999.3     .07       0
  5005.3     .12       0  5139.5     .05       0
Bank Sta=4977.3,5017.7
XS Rating Curve= 0 ,0
Exp/Cntr=0.3,0.1

Type RM Length L Ch R = 1 ,5785    ,919,919,919
BEGIN DESCRIPTION:
UNT072 IN ROCK 11.0
END DESCRIPTION:
XS GIS Cut Line= 3
      3647889.12     10159707.09      3646979.13     10159895.38
      3646260.71     10160161.53
#Sta/Elev= 30
  3873.5  246.51    4187  236.82    4381  243.41  4465.7  244.36  4585.3  241.36
  4728.7   235.1  4805.7  231.93  4970.2  232.42  4977.3  232.18  4982.7  228.27
    5002  223.82    5013  229.22  5038.1  232.36  5108.9  233.84  5118.6  235.12
  5123.9  239.08  5130.2  241.28  5154.3  244.51  5179.4  242.75  5184.7  239.32
  5209.8   236.3    5234  235.67  5295.6  235.14  5320.7  237.52    5326  241.28
  5332.8  240.02  5351.1  243.44  5356.4  241.02  5381.4  245.79  5568.9  254.01
#Mann= 5 ,-1 , 0
  3873.5     .05       0  4728.7     .07       0  4982.7     .05       0
    5013     .07       0    5234      .1       0
Bank Sta=4982.7,5013
XS Rating Curve= 0 ,0
Exp/Cntr=0.3,0.1

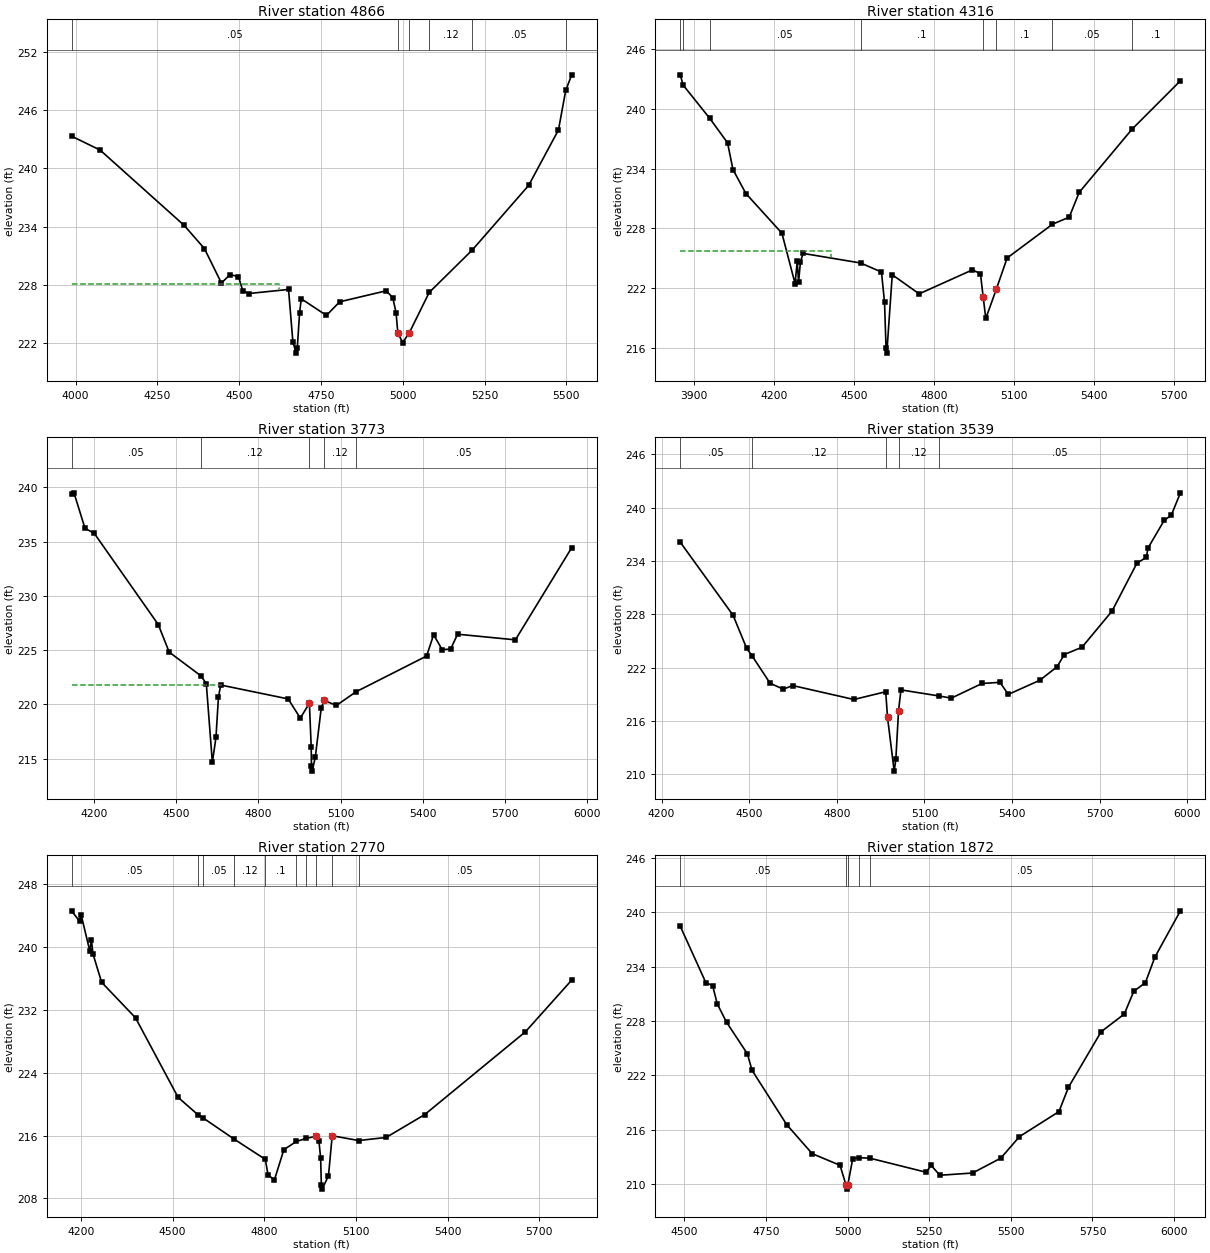
Type RM Length L Ch R = 1 ,4866    ,550,550,550
BEGIN DESCRIPTION:
UNT072 IN ROCK 9.0
END DESCRIPTION:
XS GIS Cut Line= 3
      3647832.29     10159470.39      3647136.16     10159270.44
      3646342.12     10159141.64
#Sta/Elev= 30
  3987.7  243.32    4075  241.89  4331.9  234.14  4393.7  231.76  4445.7  228.21
  4471.9  229.07  4497.7  228.88  4510.9  227.44  4528.9  227.13  4650.9  227.55
  4664.2  222.15  4674.3     221  4677.6   221.5  4684.6  225.13  4689.8  226.59
  4766.7  224.88  4807.3  226.28  4949.1  227.41  4969.4  226.72  4979.5  225.16
    4985  223.06  4985.5  223.04  4999.7  222.09    5020  223.09  5080.8  227.24
  5212.5  231.61  5384.7  238.25  5475.9  243.96  5498.1  248.03  5516.4  249.63
#Mann= 6 ,-1 , 0
  3987.7     .05       0  4985.5    .035       0    5020     .05       0
  5080.8     .12       0  5212.5     .05       0  5498.1      .1       0
#XS Ineff= 2 , 0
         4622.28  228.07
Permanent Ineff=
       F       F
Bank Sta=4985,5020
XS Rating Curve= 0 ,0
Exp/Cntr=0.3,0.1

Type RM Length L Ch R = 1 ,4316    ,543,543,543
BEGIN DESCRIPTION:
UNT072 IN ROCK 7.0
END DESCRIPTION:
XS GIS Cut Line= 3
      3648097.44     10158845.52      3647245.88     10158711.09
      3646232.31     10158703.51
#Sta/Elev= 30
  3848.1  243.42  3859.2  242.38  3958.5  239.06  4025.6  236.59  4045.8  233.91
  4094.4   231.5  4229.4  227.52  4278.7  222.46  4286.8  224.68  4291.9  222.61
  4298.9  224.67  4309.1  225.49  4524.6  224.53  4602.7  223.62  4614.2   220.6
  4619.9  215.98  4622.7  215.48  4643.2  223.35    4744  221.43    4944  223.84
    4974  223.45    4984  221.15    4994  218.96    5034  221.94    5074  225.03
    5244  228.42  5306.9  229.13    5344  231.61    5542  237.95  5723.8  242.82
#Mann= 8 ,-1 , 0
  3848.1     .05       0  3859.2     .08       0  3958.5     .05       0
  4524.6      .1       0    4984     .05       0    5034      .1       0
    5244     .05       0    5542      .1       0
#XS Ineff= 2 , 0
         4414.68  225.75
Permanent Ineff=
       F       F
Bank Sta=4984,5034
XS Rating Curve= 0 ,0
Exp/Cntr=0.3,0.1

Type RM Length L Ch R = 1 ,3773    ,234,234,234
BEGIN DESCRIPTION:
UNT072 IN ROCK 6.0
END DESCRIPTION:
XS GIS Cut Line= 3
      3647936.43     10158589.88      3647139.74     10158214.03
      3646251.22     10157898.75
#Sta/Elev= 30
  4119.1  239.38    4128  239.49  4168.1  236.22  4201.9  235.76  4435.2  227.36
  4475.2  224.82    4590  222.65  4610.4  221.93  4632.5  214.66  4645.7  216.97
  4654.6  220.65  4662.9  221.79  4908.9  220.51  4953.2  218.74  4986.3  220.11
  4992.9  216.12  4993.9  214.36  4996.7  213.86  5008.1  215.19  5029.3  219.63
  5039.9  220.37  5084.8  219.91  5156.6  221.17  5413.7  224.46  5439.3  226.42
  5470.2  225.06    5501  225.09  5526.6  226.47  5737.4  225.95  5942.8  234.44
#Mann= 5 ,-1 , 0
  4119.1     .05       0    4590     .12       0  4986.3     .07       0
  5039.9     .12       0  5156.6     .05       0
#XS Ineff= 2 , 0
         4669.32  221.83
Permanent Ineff=
       F       F
Bank Sta=4986.3,5039.9
XS Rating Curve= 0 ,0
Exp/Cntr=0.3,0.1

Type RM Length L Ch R = 1 ,3539    ,769,769,769
BEGIN DESCRIPTION:
UNT072 IN ROCK 5.0
END DESCRIPTION:
XS GIS Cut Line= 3
      3647842.07     10158291.63      3646672.86     10157757.92
      3646272.82      10157607.9
#Sta/Elev= 30
  4263.8  236.11  4444.8  227.88  4490.8   224.2  4509.5  223.33  4571.6  220.23
    4617  219.57  4648.5  219.98  4858.3  218.41  4967.3  219.28  4973.5  216.39
  4996.3  210.35    5002  211.69  5011.3  217.17  5019.5  219.49  5149.1  218.81
  5191.8  218.56  5297.1  220.21  5358.5  220.34    5387  218.98  5494.9  220.57
  5553.9  222.09  5578.9  223.47  5639.4  224.29  5742.1  228.35  5827.5  233.75
  5859.6   234.4  5865.4  235.45  5920.6  238.55    5945  239.14  5976.3  241.66
#Mann= 5 ,-1 , 0
  4263.8     .05       0  4509.5     .12       0  4967.3     .07       0
  5011.3     .12       0  5149.1     .05       0
Bank Sta=4973.5,5011.3
XS Rating Curve= 0 ,0
Exp/Cntr=0.3,0.1

Type RM Length L Ch R = 1 ,2770    ,898,898,898
BEGIN DESCRIPTION:
UNT072 IN ROCK 4.0
END DESCRIPTION:
XS GIS Cut Line= 3
      3648059.54      10157614.7      3647292.11     10157391.64
      3646492.15     10157141.66
#Sta/Elev= 30
    4169  244.62  4195.1   243.3  4200.3  244.13  4228.7  239.51  4233.9  240.93
  4239.2  239.13  4267.4  235.52  4378.4  230.99  4517.8  220.86  4583.7  218.61
  4599.1  218.25  4701.6  215.53  4803.3  212.96  4812.1  211.01  4832.8  210.32
  4864.1   214.2  4904.9  215.24    4937  215.63  4970.8  215.92  4978.7  215.34
  4984.4  213.13  4986.7  209.67  4989.4  209.17  5010.1  210.88  5022.2  215.97
  5108.8  215.36  5198.7  215.75  5324.9  218.66    5655  229.22  5806.3   235.8
#Mann= 10 ,-1 , 0
    4169     .05       0  4583.7     .12       0  4599.1     .05       0
  4701.6     .12       0  4803.3      .1       0  4904.9     .16       0
    4937      .1       0  4970.8     .07       0  5022.2      .1       0
  5108.8     .05       0
Bank Sta=4970.8,5022.2
XS Rating Curve= 0 ,0
Exp/Cntr=0.3,0.1

Type RM Length L Ch R = 1 ,1872    ,874,874,874
BEGIN DESCRIPTION:
UNT072 IN ROCK 2.0
END DESCRIPTION:
XS GIS Cut Line= 3
      3647992.11     10156991.65      3647592.11     10156641.64
      3646792.12     10156041.65
#Sta/Elev= 30
  4487.7  238.48    4566  232.26  4586.9  231.92  4601.1   229.9  4629.6  227.87
  4693.2   224.4  4707.4  222.58  4813.7  216.57  4891.6  213.37    4977  212.08
  4994.9  209.95  4997.6  209.45  5000.9  209.95  5015.9  212.81  5033.6  212.92
    5068  212.87  5241.1  211.31  5255.7  212.08  5282.8  210.98  5382.8  211.23
  5469.2  212.87  5526.5  215.25  5647.3  218.01  5676.5   220.7  5776.5  226.83
  5847.3  228.78  5876.5   231.3  5911.9  232.24  5941.1  235.07  6019.2  240.18
#Mann= 5 ,-1 , 0
  4487.7     .05       0  4994.9    .035       0  5000.9     .05       0
  5033.6     .16       0    5068     .05       0
Bank Sta=4994.9,5000.9
XS Rating Curve= 0 ,0
Exp/Cntr=0.3,0.1

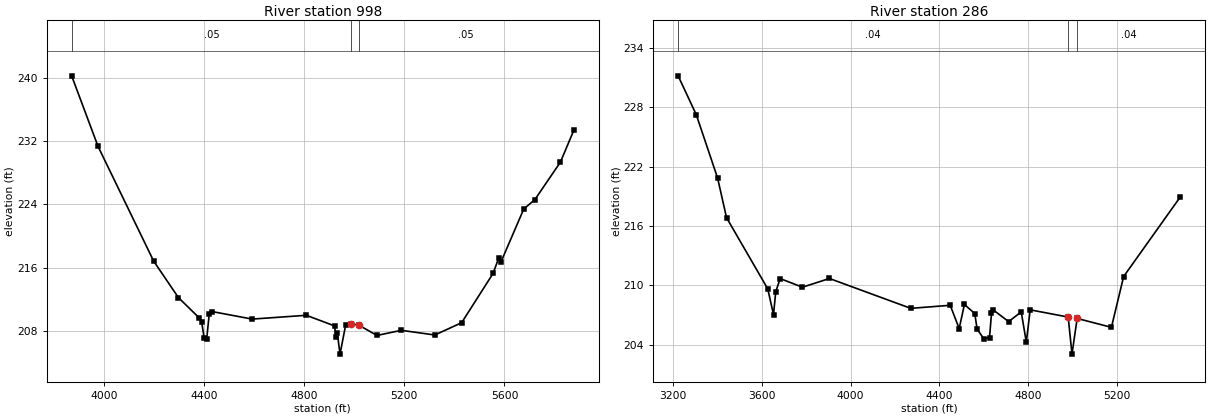
Type RM Length L Ch R = 1 ,998     ,712,712,712
BEGIN DESCRIPTION:
UNT072 IN ROCK 1.0
END DESCRIPTION:
XS GIS Cut Line= 3
      3648144.76      10156876.2      3648021.68     10155967.31
      3647042.14     10155491.66
#Sta/Elev= 30
    3871  240.25  3976.5  231.32  4198.5  216.83  4297.5  212.21  4380.2  209.65
  4390.3  209.15  4400.3  207.09  4410.4  206.96  4420.5   210.1  4430.6  210.45
  4592.1  209.49  4808.5  209.97  4921.1  208.63  4926.9  207.25  4932.4  207.67
  4943.1  205.06  4965.6  208.75  4987.8  208.88  5017.1  208.75  5090.4  207.42
  5187.9  208.07  5321.6  207.48  5428.8  209.03  5554.8  215.28    5577  217.22
  5586.8  216.77    5677  223.41  5721.5   224.6  5823.5  229.34  5877.1  233.37
#Mann= 3 , 0 , 0
    3871     .05       0  4987.8     .03       0  5017.1     .05       0
Bank Sta=4987.8,5017.1
XS Rating Curve= 0 ,0
Exp/Cntr=0.3,0.1

Type RM Length L Ch R = 1 ,286     ,0,0,0
BEGIN DESCRIPTION:
UNT072 IN ROCK 1.0.1
END DESCRIPTION:
XS GIS Cut Line= 3
      3648227.23     10156798.12      3648054.86     10155422.07
      3647260.57     10155053.14
#Sta/Elev= 30
  3222.8  231.19  3304.6  227.26  3400.7  220.85    3441  216.84  3626.7  209.64
  3652.6  207.03  3662.7  209.36  3682.8  210.68  3782.8  209.81  3904.6  210.69
  4271.1  207.67  4448.8  207.98  4489.1  205.62  4512.7  208.06  4559.6  207.14
  4569.7  205.58    4600  204.59  4625.8  204.72  4634.7  207.15  4643.2   207.5
  4711.9  206.33  4768.7  207.31  4791.6  204.25    4809  207.52  4980.3  206.79
  4997.4  203.04  5020.6  206.65    5175  205.75  5230.1  210.89  5485.4  218.94
#Mann= 3 , 0 , 0
  3222.8     .04       0  4980.3     .03       0  5020.6     .04       0
Bank Sta=4980.3,5020.6
XS Rating Curve= 0 ,0
Exp/Cntr=0.3,0.1
Stream Node=UNT072 IN ROCK  ,Reach-1         , 0 , 0 ,Upstream end
Stream Node=UNT072 IN ROCK  ,Reach-1         , 0 , 1 ,Downstream end

Chan Stop Cuts=-1
Use User Specified Reach Order=0
Composite Channel Slope=5