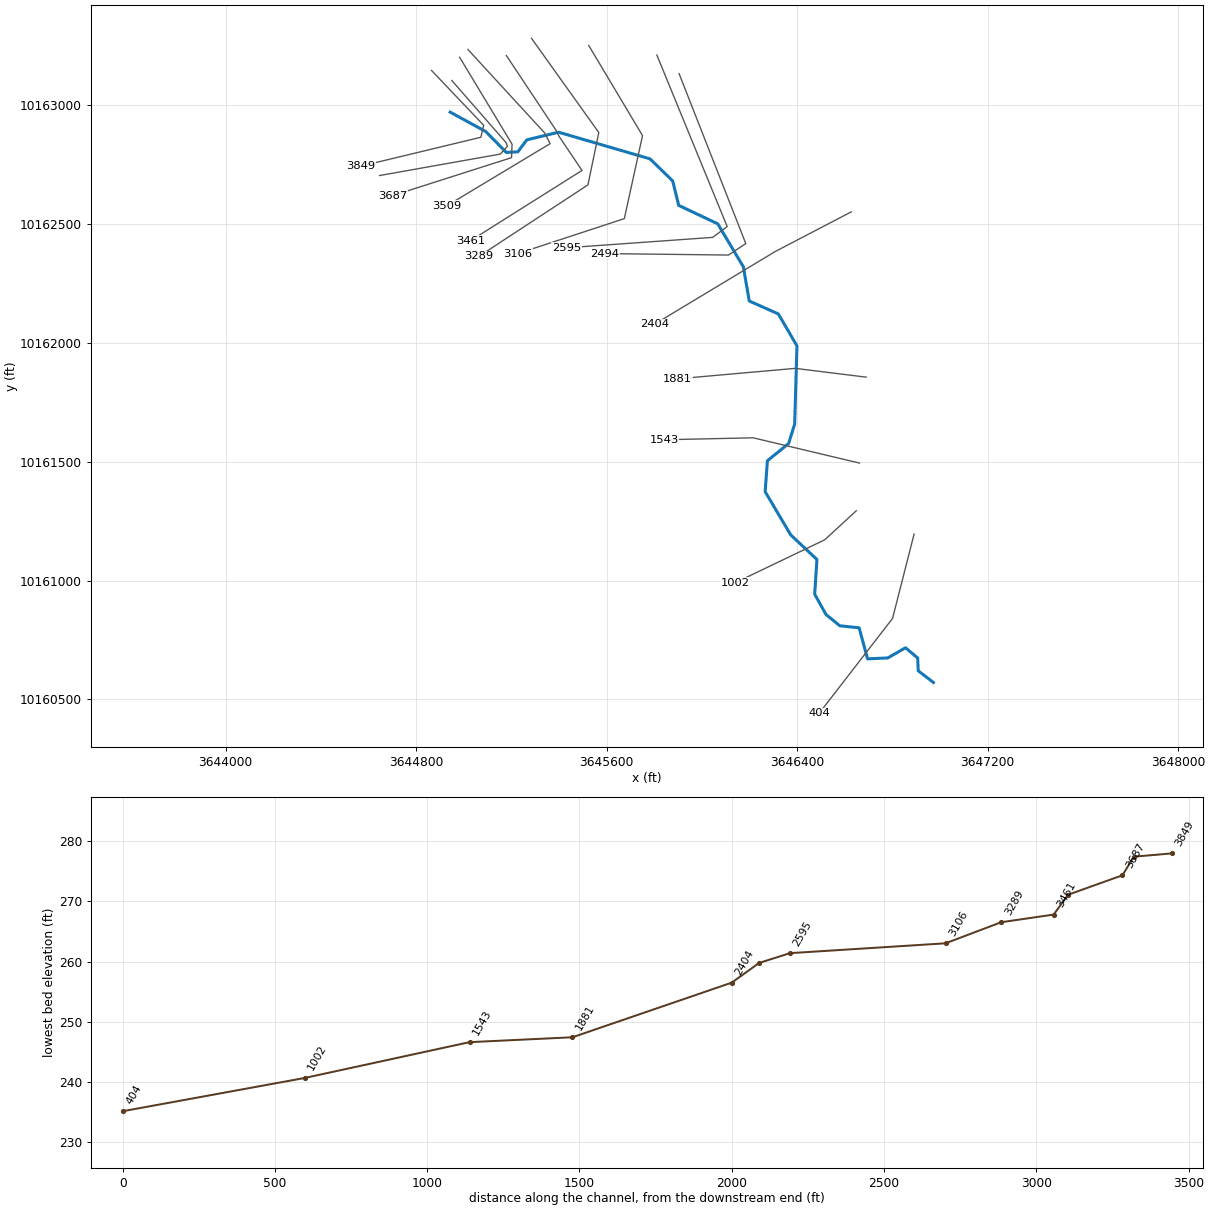
--- UNT074 IN ROCK.prj (project) ---

Proj Title=UNT074 IN ROCK Base Level Engineering
Current Plan=p01
Default Exp/Contr=0.3,0.1
English Units
Geom File=g01
Flow File=f01
Plan File=p01
Y Axis Title=Elevation
X Axis Title(PF)=Main Channel Distance
X Axis Title(XS)=Station
BEGIN DESCRIPTION:
UNT074 IN ROCK
END DESCRIPTION:
DSS Export Rating Curves= 0
DSS Export Rating Curve Sorted= 0
DSS Export Volume Flow Curves= 0
DXF OffsetX= 0
DXF OffsetY= 0
DXF ScaleX= 1
DXF ScaleY= 10

--- UNT074 IN ROCK.p01 (plan) ---

Plan Title=Multiple Run
Short Identifier=Multiple
Geom File=g01
Flow File=f01
Subcritical Flow
K Sum by GR= 0
Std Step Tol= 0.01
Critical Tol= 0.01
Num of Std Step Trials= 20
Max Error Tol= 0.3
Flow Tol Ratio= 0.001
Split Flow NTrial= 30
Split Flow Tol= 0.02
Split Flow Ratio= 0.02
Log Output Level= 0
Friction Slope Method= 1
Unsteady Friction Slope Method= 2
Unsteady Bridges Friction Slope Method= 1
Parabolic Critical Depth
Global Vel Dist=  1 , 1 , 1
Global Log Level= 0
CheckData=True
Encroach Param= -1, 0, 0, 0
BEGIN DESCRIPTION:
Multiple Run
END DESCRIPTION:

--- UNT074 IN ROCK.f01 (steady flow) ---

Flow Title=Multiple
Program Version=4.10
Number of Profiles= 7
Profile Names=10-year,25-year,50-year,1pct_min,100-year,1pct_plu,500-year
River Rch & RM=UNT074 IN ROCK,Reach-1         ,3849
     208     270     319     218     369     520     490
Boundary for River Rch & Prof#=UNT074 IN ROCK,Reach-1         , 1
Up Type= 0
Dn Type= 3
Dn Slope=0.015
Boundary for River Rch & Prof#=UNT074 IN ROCK,Reach-1         , 2
Up Type= 0
Dn Type= 3
Dn Slope=0.015
Boundary for River Rch & Prof#=UNT074 IN ROCK,Reach-1         , 3
Up Type= 0
Dn Type= 3
Dn Slope=0.015
Boundary for River Rch & Prof#=UNT074 IN ROCK,Reach-1         , 4
Up Type= 0
Dn Type= 3
Dn Slope=0.015
Boundary for River Rch & Prof#=UNT074 IN ROCK,Reach-1         , 5
Up Type= 0
Dn Type= 3
Dn Slope=0.015
Boundary for River Rch & Prof#=UNT074 IN ROCK,Reach-1         , 6
Up Type= 0
Dn Type= 3
Dn Slope=0.015
Boundary for River Rch & Prof#=UNT074 IN ROCK,Reach-1         , 7
Up Type= 0
Dn Type= 3
Dn Slope=0.015
DSS Import GetInterval= 0
DSS Import GetPeak= 0
DSS Import FillOption= 0

--- UNT074 IN ROCK.g01 (geometry) ---

Geom Title=Existing Conditions
Program Version=4.10

River Reach=UNT074 IN ROCK  ,Reach-1
Reach XY= 30
      3644943.22     10162968.26       3645092.9     10162886.65
      3645178.83     10162798.97      3645227.45     10162801.58
      3645264.77     10162851.92      3645398.45     10162884.04
      3645782.13     10162772.06      3645877.63     10162679.15
      3645902.63     10162576.54       3646066.6     10162499.11
      3646174.32     10162318.15      3646198.96      10162174.6
      3646320.93     10162120.51      3646399.24     10161986.09
      3646389.61     10161657.41      3646364.06     10161575.52
       3646275.2     10161503.44      3646265.71     10161373.34
      3646372.92     10161191.88      3646483.02     10161088.47
       3646473.7     10160942.46      3646521.14     10160857.34
      3646579.16     10160809.78      3646660.26     10160801.34
       3646695.6     10160670.86       3646780.8     10160674.63
       3646855.1     10160717.57      3646906.19     10160674.34
       3646908.5     10160620.59      3646972.11     10160571.64

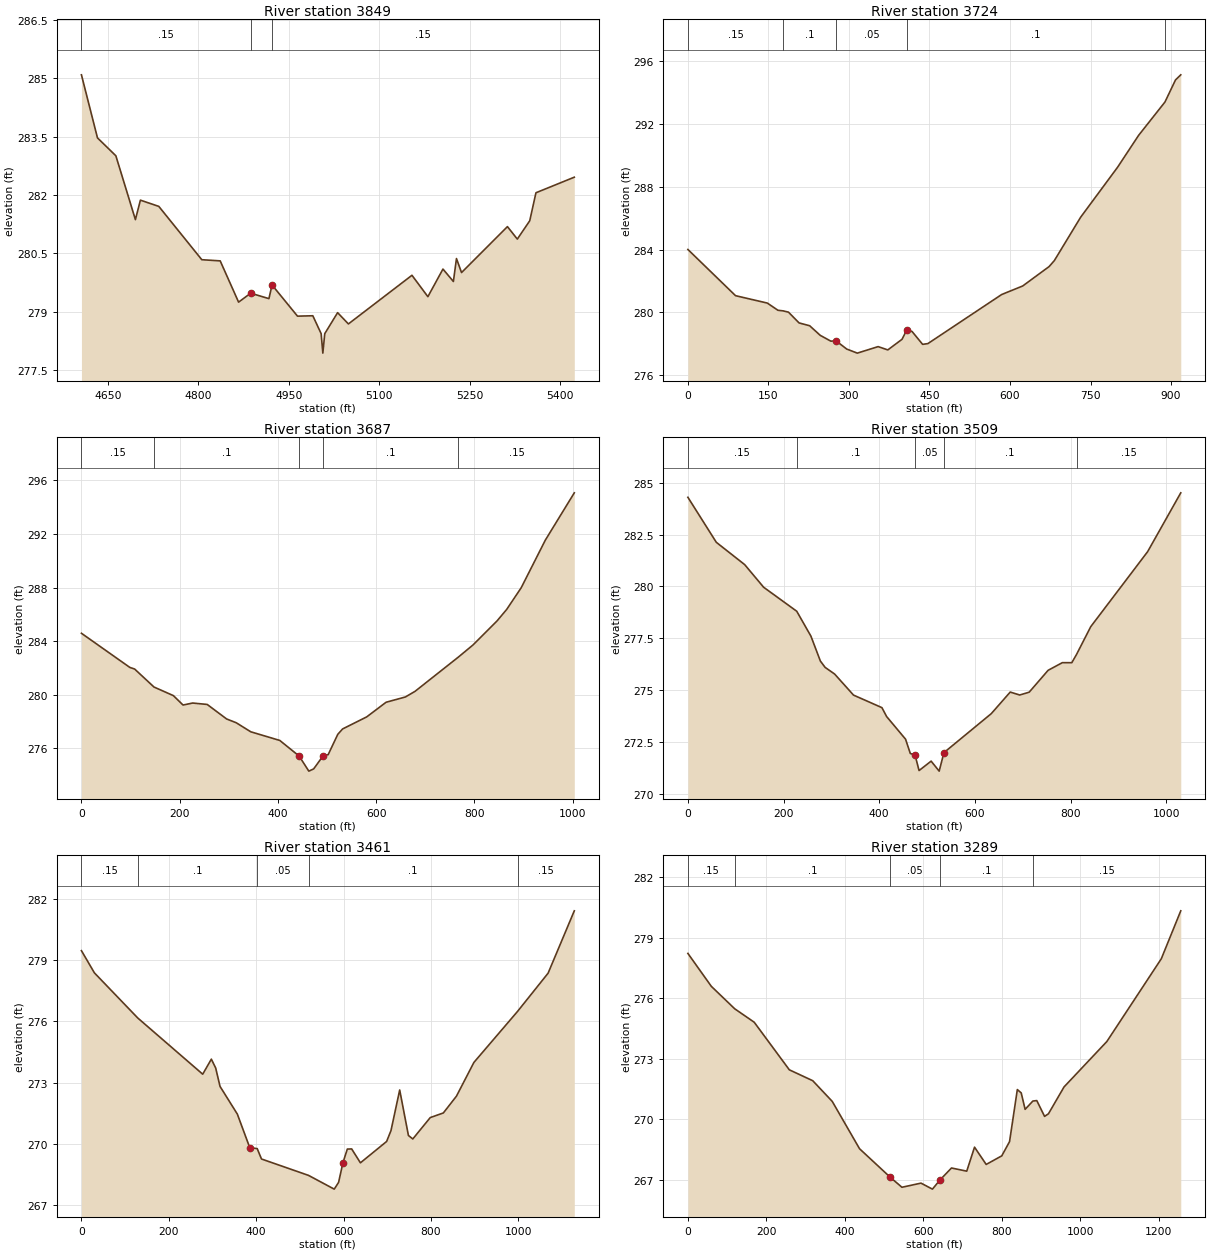
Type RM Length L Ch R = 1 ,3849    ,125,125,125
BEGIN DESCRIPTION:
UNT074 IN ROCK 8.0
END DESCRIPTION:
XS GIS Cut Line= 4
     3644864.769    10163143.659     3645084.029    10162913.106
      3645072.11    10162862.845     3644568.936    10162741.576
#Sta/Elev= 30
  4606.2  285.09  4632.8  283.47  4663.3  283.01  4695.7  281.37    4704  281.87
  4734.5  281.71  4805.8  280.34  4836.3  280.31  4866.8  279.25  4886.9  279.48
  4917.1  279.34  4922.3  279.69  4964.5  278.89  4989.9   278.9  5003.7  278.44
  5006.5  277.94  5009.7  278.44    5031  278.98  5048.9  278.69  5154.3  279.94
  5180.7  279.39  5205.7   280.1    5223  279.78  5228.1  280.37  5236.5  280.01
  5312.6  281.19    5329  280.87  5349.6  281.34  5359.9  282.06  5423.5  282.46
#Mann= 3 , 0 , 0
  4606.2     .15       0  4886.9     .05       0  4922.3     .15       0
Bank Sta=4886.9,4922.3
XS Rating Curve= 0 ,0
Exp/Cntr=0.3,0.1

Type RM Length L Ch R = 1 ,3724    ,37,37,37
XS GIS Cut Line= 5
     3644950.186    10163101.298     3645177.964    10162840.187
     3645183.519    10162824.909     3645154.353     10162792.27
     3644646.714    10162701.993
#Sta/Elev= 30
       0284.003788.75989281.0557147.9332280.5845167.6576280.1261177.5198 280.086
 187.382280.0041207.1064279.3172226.8308279.1379246.5553278.5246266.2797278.1554
276.1419278.1697295.8663277.6508315.5907277.3908354.3742 277.806372.4134277.5954
398.9401278.2745407.7823278.8752417.5966278.7707437.2253277.9507447.0396277.9983
584.4398281.1289 623.697281.6751672.7684282.9107682.5828283.2924731.6542286.0639
800.3543289.2473839.6115291.2853 888.683293.4122908.3116294.8209918.1259295.1466
#Mann= 5 ,-1 , 0
       0     .15       0177.5198      .1       0276.1419     .05       0
407.7823      .1       0 888.683     .15       0
Bank Sta=276.1419,407.7823
XS Rating Curve= 0 ,0
Exp/Cntr=0.3,0.1

Type RM Length L Ch R = 1 ,3687    ,178,178,178
XS GIS Cut Line= 4
     3644982.738    10163199.215     3645203.007    10162833.546
     3645200.837    10162777.123     3644701.705    10162617.618
#Sta/Elev= 30
       0284.595298.49704282.0483108.3467281.9254147.7456280.5844187.1444279.9448
206.8438279.2421226.5432279.3907256.0923279.2853295.4911278.2046315.1906277.9193
344.7397277.2458403.8379276.6008443.2153275.4354462.8934274.3122472.7324274.4772
492.3977275.4715 502.224 275.536521.8766277.0571531.7029277.4585580.8344278.3596
620.1395279.4487659.4447279.8424679.0973280.2616767.5339282.8237797.0128283.7187
846.1443285.5187865.7969286.3769895.2758287.9906944.4072291.54191003.365295.0698
#Mann= 5 ,-1 , 0
       0     .15       0147.7456      .1       0443.2153     .05       0
492.3977      .1       0767.5339     .15       0
Bank Sta=443.2153,492.3977
XS Rating Curve= 0 ,0
Exp/Cntr=0.3,0.1

Type RM Length L Ch R = 1 ,3509    ,48,48,48
XS GIS Cut Line= 4
     3645017.713    10163231.695      3645340.63    10162880.132
     3645362.766    10162835.861      3644927.87    10162574.143
#Sta/Elev= 30
       0284.298159.36322 282.129118.7264281.0518158.3019279.9623 227.559278.8035
257.2406277.6014277.0284276.3997286.9222276.0962  306.71275.7764346.2854274.7596
405.6487274.1545415.5425273.7235 455.118272.6323465.0119271.9433474.9057271.8722
483.3169 271.121508.5503 271.575525.3726271.0931535.2769271.9841634.3199 273.866
673.9371274.9061693.7457274.7642713.5543274.9001753.1716275.9555782.8845276.3237
802.6931276.3225812.5974 276.722842.3103278.0608 961.162281.67511030.492284.5143
#Mann= 5 ,-1 , 0
       0     .15       0 227.559      .1       0474.9057     .05       0
535.2769      .1       0812.5974     .15       0
Bank Sta=474.9057,535.2769
XS Rating Curve= 0 ,0
Exp/Cntr=0.3,0.1

Type RM Length L Ch R = 1 ,3461    ,172,172,172
XS GIS Cut Line= 5
     3645178.998    10163206.469     3645387.332    10162892.667
     3645400.352    10162866.625     3645496.707    10162723.396
     3645027.957    10162427.823
#Sta/Elev= 30
       0 279.458 29.7365278.3714128.8582276.1652277.5407273.4153 297.365274.1498
307.2772273.7161317.1894272.8182 356.838271.4618385.2117269.8232402.3104269.7734
412.1015269.2656519.8029268.4633578.5492267.7916588.5395268.1212598.5297269.0879
  608.52269.7507618.5102269.7582638.4907269.0779698.4322270.1221708.4225270.6527
 728.403272.6418748.3835270.4173758.3737270.2458798.3347 271.292828.3055271.5185
858.2762 272.339898.2372273.9903998.1397276.48711068.071278.35781128.013281.4075
#Mann= 5 ,-1 , 0
       0     .15       0128.8582      .1       0402.3104     .05       0
519.8029      .1       0998.1397     .15       0
Bank Sta=385.2117,598.5297
XS Rating Curve= 0 ,0
Exp/Cntr=0.3,0.1

Type RM Length L Ch R = 1 ,3289    ,183,183,183
XS GIS Cut Line= 4
     3645284.641     10163278.57     3645567.193    10162882.736
      3645521.62    10162662.684     3645063.286    10162361.903
#Sta/Elev= 30
       0278.229659.66836276.5962119.3367275.4803169.0604 274.812258.5629272.4497
318.2313271.9091367.9549270.8817 437.568  268.53516.4485267.1035545.6053266.6172
   594.2 266.823623.3568266.5251642.7947266.9834671.9515 267.575710.8273 267.417
730.6663268.6082760.4248267.7508800.1028268.1775819.9418268.8842839.7809 271.469
849.7004 271.302859.6199270.4873879.4589270.8998889.3784270.9212909.2174270.1372
919.1369270.2667958.8149271.59891067.929273.85351206.802277.9648  1256.4280.3445
#Mann= 5 ,-1 , 0
       0     .15       0119.3367      .1       0516.4485     .05       0
642.7947      .1       0879.4589     .15       0
Bank Sta=516.4485,642.7947
XS Rating Curve= 0 ,0
Exp/Cntr=0.3,0.1

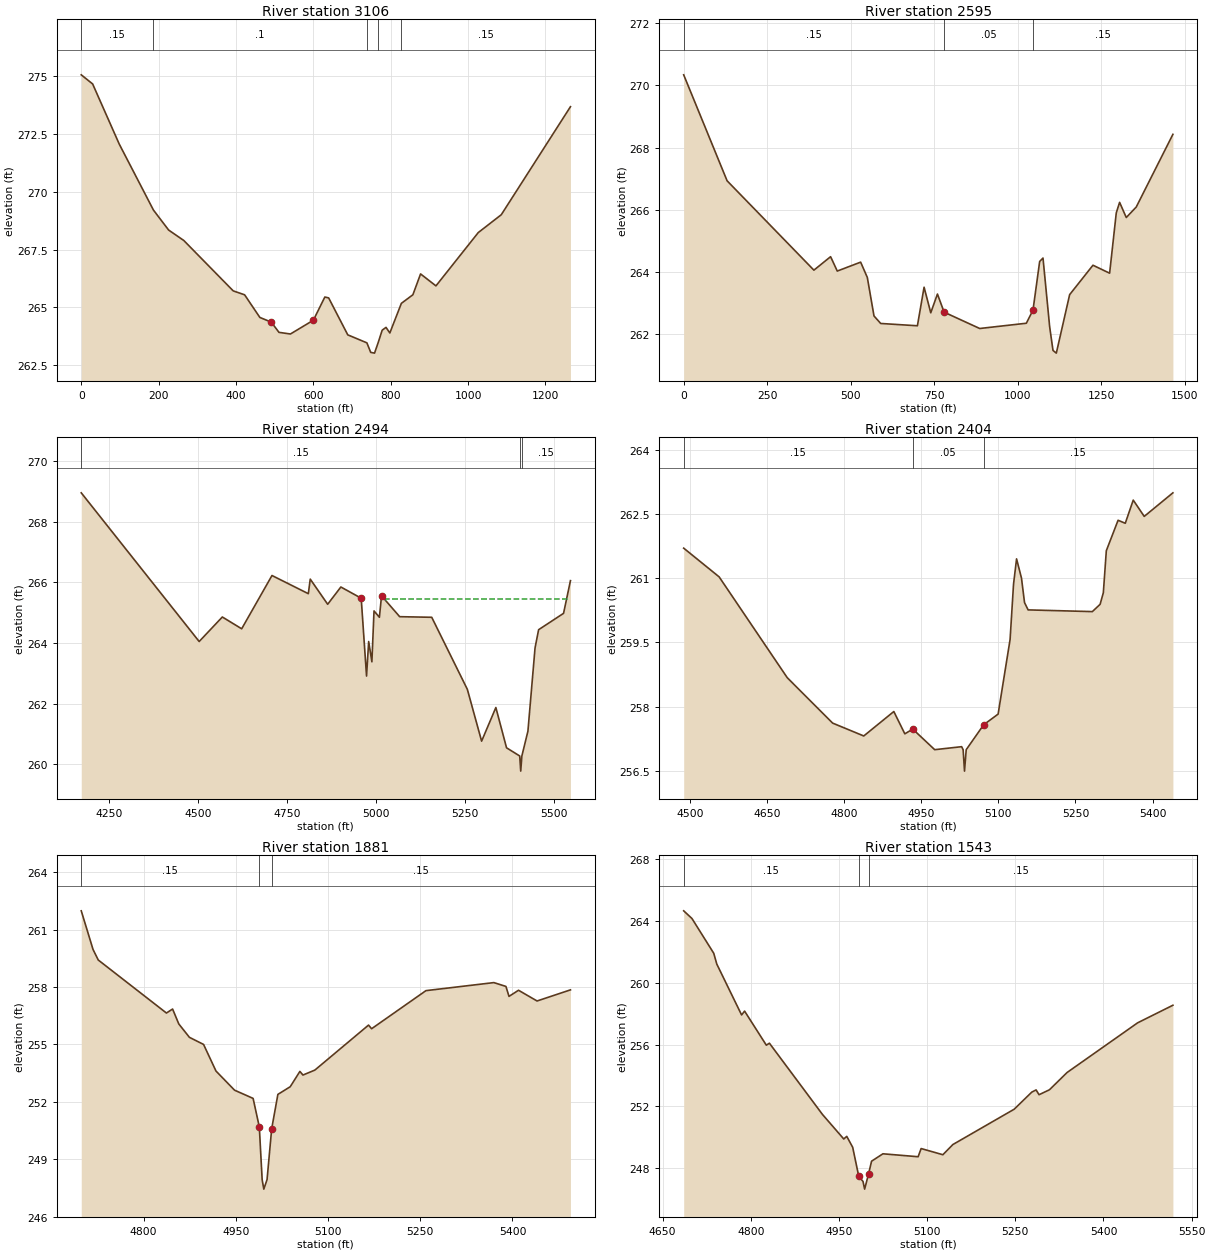
Type RM Length L Ch R = 1 ,3106    ,511,511,511
BEGIN DESCRIPTION:
Mapping XS 1bec5981
END DESCRIPTION:
XS GIS Cut Line= 4
     3645525.096    10163248.269     3645750.791    10162869.797
     3645674.402    10162520.838     3645226.047    10162373.622
#Sta/Elev= 30
       0275.045929.46189274.651298.20629272.0557186.5919269.2067225.8745268.3431
 265.157267.8909392.8252265.7157 422.287265.5465 461.693 264.569  491.34264.3647
511.1047263.9248540.7517263.8537600.0458264.4487629.6928265.4501639.5752265.4117
688.9869263.8164738.3986263.4715748.2809263.0602758.1633263.0275768.0456263.5059
 777.928264.0182787.8103264.1392797.6926263.8983827.4974265.1763857.3022265.5486
877.1721266.4473916.9118265.93141026.196268.23171085.806269.00451264.634273.6692
#Mann= 5 ,-1 , 0
       0     .15       0186.5919      .1       0738.3986     .05       0
768.0456      .1       0827.4974     .15       0
Bank Sta=491.34,600.0458
XS Rating Curve= 0 ,0
Exp/Cntr=0.3,0.1

Type RM Length L Ch R = 1 ,2595    ,101,101,101
BEGIN DESCRIPTION:
Mapping XS 2050a6f6
END DESCRIPTION:
XS GIS Cut Line= 4
     3645811.092    10163208.165     3646106.231    10162487.679
     3646045.467    10162442.106     3645431.776    10162398.361
#Sta/Elev= 30
       0270.3416  129.97266.9337389.9102264.0599439.8986264.4932 459.894264.0306
529.8779264.3177549.8733263.8256569.8687262.5869589.8641262.3457699.8387262.2713
719.8341263.5118739.8295262.6886759.8249263.2921779.8203262.7092 886.434262.1838
1026.072262.3529 1046.02262.77621065.968264.33891075.942264.4495 1095.89262.2382
1105.865261.47851115.839261.39181155.735263.27291225.554264.21861275.424263.9623
1295.373265.90341305.347266.24081325.295265.75261355.217266.09171464.932268.4278
#Mann= 3 , 0 , 0
       0     .15       0779.8203     .05       0 1046.02     .15       0
Bank Sta=779.8203,1046.02
XS Rating Curve= 0 ,0
Exp/Cntr=0.3,0.1

Type RM Length L Ch R = 1 ,2494    ,90,90,90
BEGIN DESCRIPTION:
UNT074 IN ROCK 6.0
END DESCRIPTION:
XS GIS Cut Line= 4
       3645904.4     10163130.07      3646184.36     10162416.06
      3646112.01     10162367.84      3645592.72     10162373.98
#Sta/Elev= 30
  4171.9  268.96  4502.9  264.05  4567.9  264.86  4622.2  264.47  4707.3  266.23
  4809.3  265.63  4814.7  266.11  4863.6  265.28  4900.6  265.85  4957.7  265.48
  4972.7  262.91  4978.7  264.05  4987.7  263.38  4993.7  265.06  5008.8  264.85
  5014.8  265.56  5065.7  264.87  5155.7  264.85  5255.7  262.47  5295.7  260.76
  5335.7  261.87  5365.7  260.54  5402.7  260.27  5405.5  259.77  5408.7  260.27
  5425.7  261.09  5445.7  263.84  5455.7  264.44  5525.7  264.98  5545.1  266.06
#Mann= 3 ,-1 , 0
  4171.9     .15       0  5402.7     .05       0  5408.7     .15       0
#XS Ineff= 2 , 0
                         5026.36          265.46
Permanent Ineff=
       F       F
Bank Sta=4957.7,5014.8
XS Rating Curve= 0 ,0
Exp/Cntr=0.3,0.1

Type RM Length L Ch R = 1 ,2404    ,523,523,523
BEGIN DESCRIPTION:
UNT074 IN ROCK 5.0
END DESCRIPTION:
XS GIS Cut Line= 3
      3646627.11     10162549.16      3646307.64     10162382.48
      3645800.74     10162076.95
#Sta/Elev= 30
  4487.4   261.7  4556.4  261.03  4688.9  258.68  4777.3  257.62  4837.9  257.32
  4896.4  257.89  4917.8  257.37  4933.3  257.48    4976     257  5028.4  257.07
  5031.3     257    5034   256.5  5037.3     257  5071.2  257.58  5099.4  257.83
  5122.7  259.57  5129.4  260.86  5135.3  261.45  5144.9     261  5150.8  260.43
  5157.8  260.26  5282.8  260.22  5297.9  260.39  5304.2  260.66    5310  261.64
  5332.9  262.35  5346.9  262.28  5362.4  262.82  5383.8  262.44  5439.6  262.99
#Mann= 3 , 0 , 0
  4487.4     .15       0  4933.3     .05       0  5071.2     .15       0
Bank Sta=4933.3,5071.2
XS Rating Curve= 0 ,0
Exp/Cntr=0.3,0.1

Type RM Length L Ch R = 1 ,1881    ,338,338,338
BEGIN DESCRIPTION:
UNT074 IN ROCK 4.0
END DESCRIPTION:
XS GIS Cut Line= 3
      3646689.62      10161854.7      3646392.11     10161891.64
      3645897.95     10161847.76
#Sta/Elev= 30
  4698.5  261.98  4717.7  259.96  4726.2  259.41  4837.1  256.64  4847.1  256.85
  4857.2  256.07  4874.5  255.37  4897.5     255  4917.7  253.61  4947.9  252.61
  4978.1  252.18  4988.2  250.69  4992.8  247.94  4995.5  247.44  5000.8  247.94
  5008.3  250.59  5018.4  252.39  5038.5  252.79  5054.2  253.59  5059.2   253.4
  5078.6  253.66  5165.9  256.01  5170.9  255.82  5259.3  257.81  5369.8  258.23
  5389.4  258.03  5394.4  257.51  5409.9  257.83    5440  257.27  5494.4  257.85
#Mann= 3 , 0 , 0
  4698.5     .15       0  4988.2     .05       0  5008.3     .15       0
Bank Sta=4988.2,5008.3
XS Rating Curve= 0 ,0
Exp/Cntr=0.3,0.1

Type RM Length L Ch R = 1 ,1543    ,541,541,541
BEGIN DESCRIPTION:
UNT074 IN ROCK 3.0
END DESCRIPTION:
XS GIS Cut Line= 3
      3646661.79      10161493.6      3646215.49     10161599.75
      3645842.13     10161591.64
#Sta/Elev= 30
  4685.9  264.67    4700  264.17    4737  261.92  4742.2  261.22  4784.4  257.92
  4789.5  258.17  4826.5  255.96  4831.7  256.09    4922  251.47  4958.2  249.88
  4963.3  250.05  4973.4  249.34  4983.7  247.46  4990.9  247.13  4993.7  246.63
  5000.3   247.6  5005.5  248.44  5024.8  248.92  5084.7  248.73  5089.8  249.26
  5126.8  248.86  5143.8  249.52  5248.1  251.81  5278.1  252.92  5285.4  253.06
  5290.4  252.75  5308.1  253.07  5338.1  254.19  5458.1  257.41  5518.1  258.55
#Mann= 3 , 0 , 0
  4685.9     .15       0  4983.7     .05       0  5000.3     .15       0
Bank Sta=4983.7,5000.3
XS Rating Curve= 0 ,0
Exp/Cntr=0.3,0.1

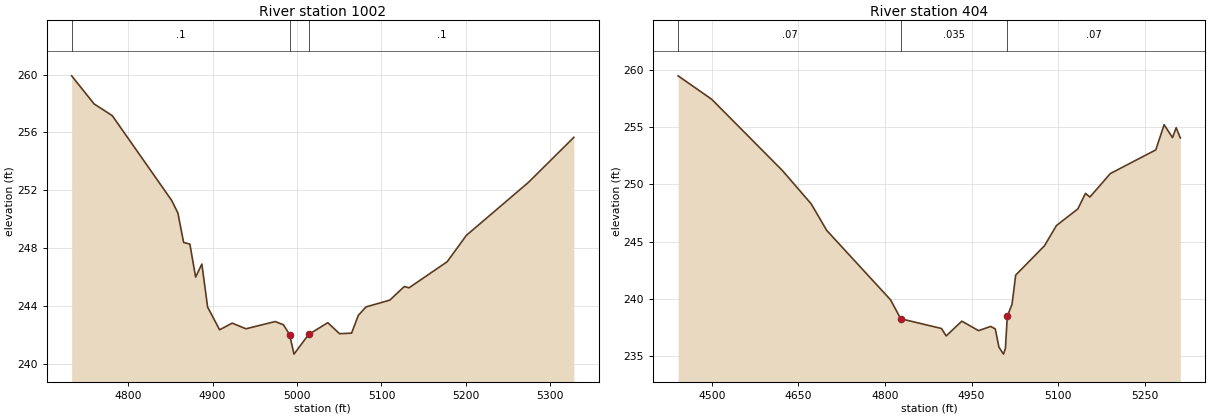
Type RM Length L Ch R = 1 ,1002    ,598,598,598
BEGIN DESCRIPTION:
UNT074 IN ROCK 2.0
END DESCRIPTION:
XS GIS Cut Line= 3
      3646648.29     10161293.13      3646516.01     10161171.23
      3646142.09     10160991.64
#Sta/Elev= 30
  4733.1  259.91  4759.7  257.97  4781.2  257.16  4851.5  251.31  4858.9  250.44
  4865.7   248.4  4873.1  248.29  4879.9  246.01  4887.3  246.91  4894.1  243.94
  4908.3  242.37  4923.2  242.83  4939.5  242.44  4974.1  242.94  4983.9  242.72
  4991.2  242.04  4996.4  240.69  5013.8  242.05  5036.4  242.86  5050.4   242.1
  5064.6  242.14  5072.6  243.37  5081.7  243.95  5109.9  244.42    5127  245.36
  5132.6  245.27  5177.8  247.07  5200.5  248.89    5274  252.55  5327.8  255.66
#Mann= 3 , 0 , 0
  4733.1      .1       0  4991.2     .05       0  5013.8      .1       0
Bank Sta=4991.2,5013.8
XS Rating Curve= 0 ,0
Exp/Cntr=0.3,0.1

Type RM Length L Ch R = 1 ,404     ,0,0,0
BEGIN DESCRIPTION:
UNT074 IN ROCK 1.0
END DESCRIPTION:
XS GIS Cut Line= 3
      3646890.98     10161194.99       3646800.7     10160840.81
      3646492.13     10160441.68
#Sta/Elev= 30
  4441.7  259.48  4499.9  257.43  4622.5   251.2  4672.2   248.3  4699.1  245.98
  4809.8  239.91  4827.3  238.26  4897.9  237.41  4906.1  236.76  4933.2  238.05
  4962.2  237.22  4983.1  237.59  4991.2  237.37  4997.5  235.78  5005.4  235.17
  5008.7  235.67    5012  238.48  5020.2  239.53  5026.5  242.07  5076.3  244.63
  5097.1   246.4  5134.3  247.86  5147.4  249.21  5155.1  248.89  5190.4  250.94
  5269.2  253.01  5283.7  255.21  5298.2  254.08  5304.5  254.95  5311.7  254.06
#Mann= 3 , 0 , 0
  4441.7     .07       0  4827.3    .035       0    5012     .07       0
Bank Sta=4827.3,5012
XS Rating Curve= 0 ,0
Exp/Cntr=0.3,0.1

Chan Stop Cuts=-1
Use User Specified Reach Order=0
Composite Channel Slope=5