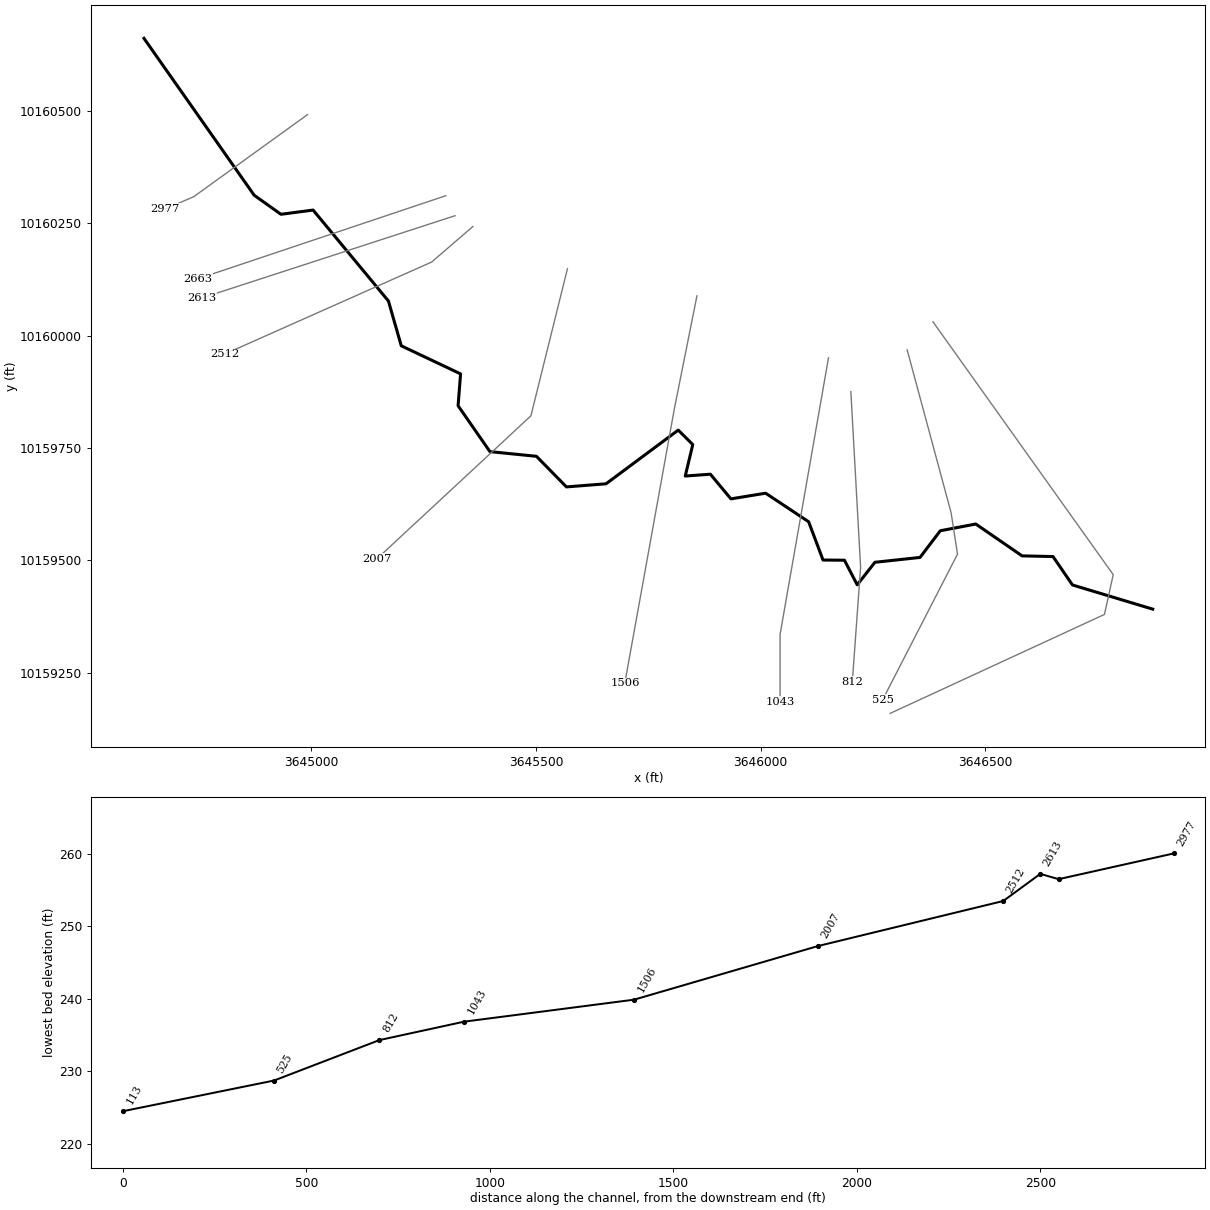
--- UNT075 IN ROCK.prj (project) ---

Proj Title=UNT075 IN ROCK Base Level Engineering
Current Plan=p01
Default Exp/Contr=0.3,0.1
English Units
Geom File=g01
Flow File=f01
Plan File=p01
Y Axis Title=Elevation
X Axis Title(PF)=Main Channel Distance
X Axis Title(XS)=Station
BEGIN DESCRIPTION:
UNT075 IN ROCK
END DESCRIPTION:
DSS Export Rating Curves= 0
DSS Export Rating Curve Sorted= 0
DSS Export Volume Flow Curves= 0
DXF OffsetX= 0
DXF OffsetY= 0
DXF ScaleX= 1
DXF ScaleY= 10

--- UNT075 IN ROCK.p01 (plan) ---

Plan Title=Multiple Run
Short Identifier=Multiple
Geom File=g01
Flow File=f01
Subcritical Flow
K Sum by GR= 0
Std Step Tol= 0.01
Critical Tol= 0.01
Num of Std Step Trials= 20
Max Error Tol= 0.3
Flow Tol Ratio= 0.001
Split Flow NTrial= 30
Split Flow Tol= 0.02
Split Flow Ratio= 0.02
Log Output Level= 0
Friction Slope Method= 1
Unsteady Friction Slope Method= 2
Unsteady Bridges Friction Slope Method= 1
Parabolic Critical Depth
Global Vel Dist=  1 , 1 , 1
Global Log Level= 0
CheckData=True
Encroach Param= -1, 0, 0, 0
BEGIN DESCRIPTION:
Multiple Run
END DESCRIPTION:

--- UNT075 IN ROCK.f01 (steady flow) ---

Flow Title=Multiple
Number of Profiles=7
Profile Names=10-year,25-year,50-year,1pct_min,100-year,1pct_plu,500-year
River Rch & RM= UNT075 IN ROCK,Reach-1,2977
     176     220     254     216     292     394     384
Boundary for River Rch & Prof#=UNT075 IN ROCK,Reach-1,1
Up Type=0
Dn Type=3
Dn Slope=0.005
Boundary for River Rch & Prof#=UNT075 IN ROCK,Reach-1,2
Up Type=0
Dn Type=3
Dn Slope=0.005
Boundary for River Rch & Prof#=UNT075 IN ROCK,Reach-1,3
Up Type=0
Dn Type=3
Dn Slope=0.005
Boundary for River Rch & Prof#=UNT075 IN ROCK,Reach-1,4
Up Type=0
Dn Type=3
Dn Slope=0.005
Boundary for River Rch & Prof#=UNT075 IN ROCK,Reach-1,5
Up Type=0
Dn Type=3
Dn Slope=0.005
Boundary for River Rch & Prof#=UNT075 IN ROCK,Reach-1,6
Up Type=0
Dn Type=3
Dn Slope=0.005
Boundary for River Rch & Prof#=UNT075 IN ROCK,Reach-1,7
Up Type=0
Dn Type=3
Dn Slope=0.005

--- UNT075 IN ROCK.g01 (geometry) ---

Geom Title=Existing Conditions
Program Version=4.10

River Reach=UNT075 IN ROCK  ,Reach-1
Reach XY= 30
      3644628.24      10160661.3       3644873.4      10160312.3
      3644932.95     10160269.94      3645004.48     10160279.31
      3645172.02     10160077.06      3645200.57     10159977.43
      3645332.51     10159914.93      3645326.96      10159844.1
      3645397.79     10159742.02      3645501.26      10159731.6
      3645567.93     10159663.54      3645656.12     10159670.49
      3645816.63     10159789.87      3645848.97     10159757.66
      3645832.24     10159687.73      3645888.15     10159691.79
      3645933.79     10159636.95      3646010.95     10159649.55
      3646106.66     10159586.06      3646138.72     10159500.89
      3646186.35     10159500.47      3646214.77     10159445.74
      3646254.15      10159495.9      3646354.43     10159506.66
      3646399.56     10159566.01      3646478.46     10159580.98
      3646581.43     10159510.13      3646650.23     10159508.64
      3646693.58     10159445.42      3646872.11     10159391.64

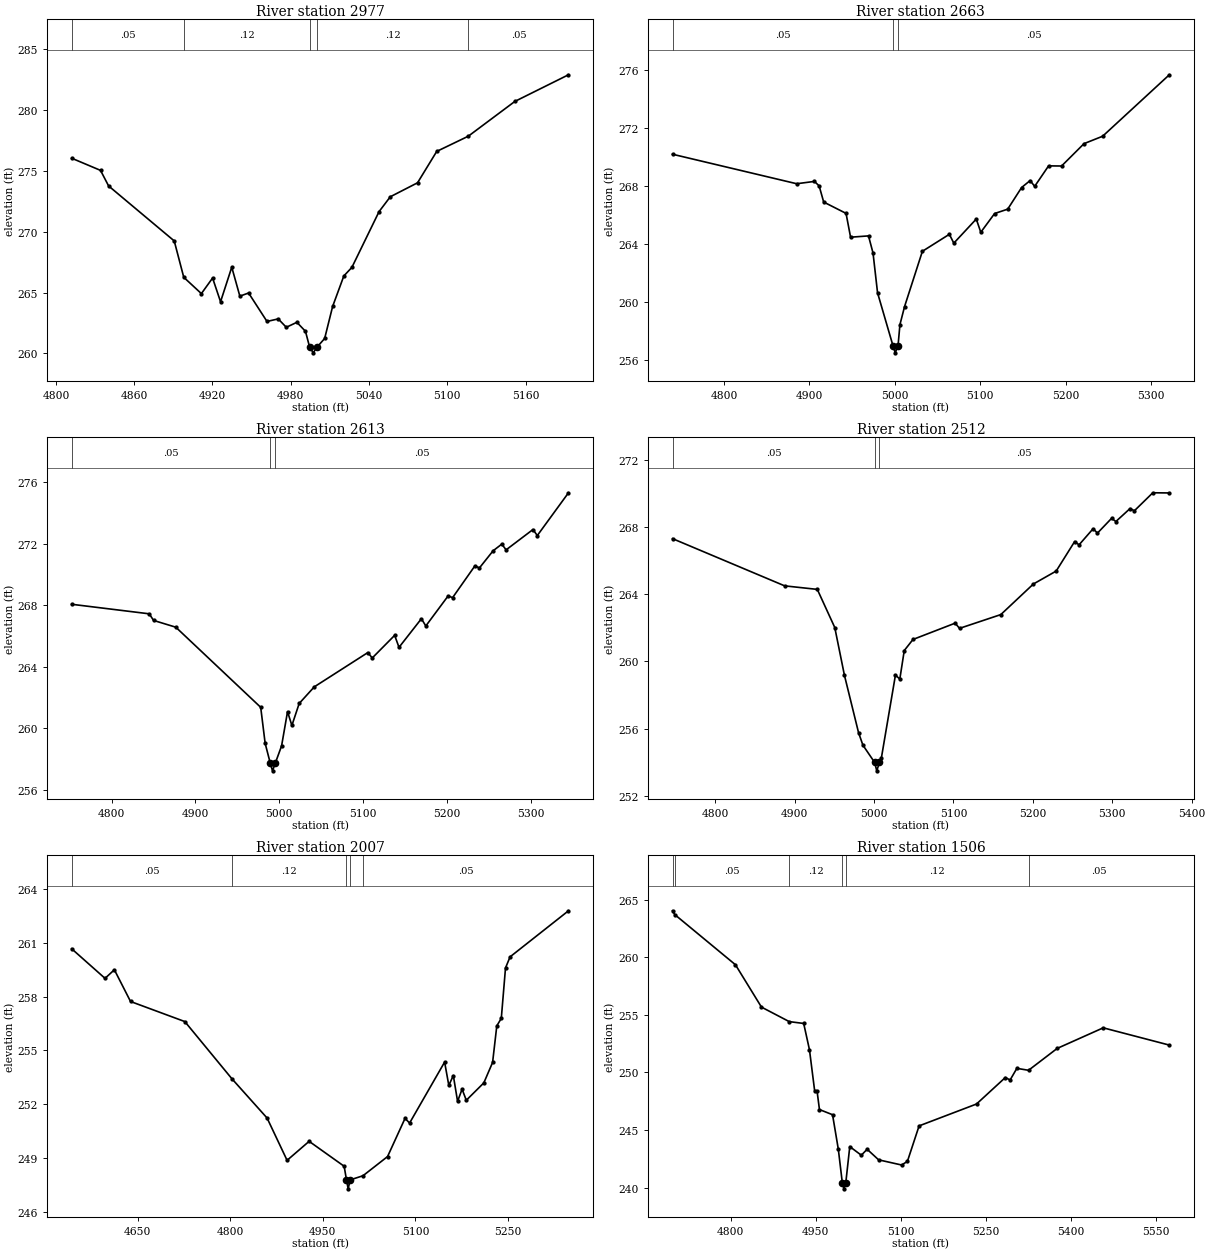
Type RM Length L Ch R = 1 ,2977    ,314,314,314
BEGIN DESCRIPTION:
UNT075 IN ROCK 6.0
END DESCRIPTION:
XS GIS Cut Line= 3
      3644992.12     10160491.66      3644739.37     10160309.36
      3644675.98     10160281.69
#Sta/Elev= 30
  4812.1  276.05  4834.2  275.05  4840.4  273.77  4890.7  269.25    4898  266.26
  4911.5  264.92  4920.1   266.2  4926.2  264.25  4934.8  267.09    4941  264.71
  4947.7  264.97  4961.8  262.63  4970.4  262.84  4976.6  262.15  4984.7  262.56
  4991.3  261.82  4994.4  260.55  4997.2  260.05  5000.4  260.55    5006  261.23
  5012.1  263.86  5020.7  266.37  5026.9  267.08  5047.7  271.66  5056.3  272.88
  5077.2  274.03  5091.9  276.61  5116.1  277.86  5151.8  280.72  5192.9  282.91
#Mann= 5 ,-1 , 0
  4812.1     .05       0    4898     .12       0  4994.4     .07       0
  5000.4     .12       0  5116.1     .05       0
Bank Sta=4994.4,5000.4
XS Rating Curve= 0 ,0
Exp/Cntr=0.3,0.1

Type RM Length L Ch R = 1 ,2663    ,50,50,50
BEGIN DESCRIPTION:
Mapping XS c274c4b5
END DESCRIPTION:
XS GIS Cut Line= 2
       3645299.7     10160311.29      3644748.08     10160126.33
#Sta/Elev= 30
  4739.7  270.17  4885.1  268.14  4905.9   268.3  4911.4  267.99  4916.7  266.88
  4942.9   266.1  4948.2  264.46  4969.2  264.55  4974.5  263.37  4979.8  260.63
  4997.8     257  5000.5   256.5  5003.8     257    5006  258.44  5011.4  259.68
  5032.3  263.49  5063.9  264.66  5069.1  264.05  5095.4  265.71  5100.7   264.8
  5116.9  266.09  5132.2  266.39  5148.5  267.88  5158.5  268.36  5163.8  267.96
  5180.1  269.37  5195.3  269.36  5221.6   270.9  5243.4  271.41  5321.5  275.64
#Mann= 3 ,-1 , 0
  4739.7     .05       0  4997.8     .03       0  5003.8     .05       0
Bank Sta=4997.8,5003.8
XS Rating Curve= 0 ,0
Exp/Cntr=0.3,0.1

Type RM Length L Ch R = 1 ,2613    ,101,101,101
BEGIN DESCRIPTION:
Mapping XS c481a14e
END DESCRIPTION:
XS GIS Cut Line= 2
      3645320.24     10160266.78      3644756.56     10160083.58
#Sta/Elev= 30
  4752.5  268.06    4845  267.44  4850.2  267.01  4876.7  266.57    4978  261.36
  4983.3  259.02  4989.4  257.73  4992.1  257.23  4995.4  257.73  5002.9  258.85
    5010  261.08  5015.2  260.18  5023.9  261.61  5041.9  262.69  5105.8  264.92
  5111.1  264.57  5137.8  266.04    5143  265.26  5169.7  267.12    5175  266.65
  5201.7  268.61  5206.9  268.49  5233.6  270.56  5238.9  270.42  5255.3  271.54
  5265.6  271.97  5270.8   271.6  5302.8  272.92    5308  272.53  5345.2  275.31
#Mann= 3 ,-1 , 0
  4752.5     .05       0  4989.4     .03       0  4995.4     .05       0
Bank Sta=4989.4,4995.4
XS Rating Curve= 0 ,0
Exp/Cntr=0.3,0.1

Type RM Length L Ch R = 1 ,2512    ,505,505,505
BEGIN DESCRIPTION:
UNT075 IN ROCK 5.0
END DESCRIPTION:
XS GIS Cut Line= 3
      3645359.84     10160242.71      3645268.23     10160163.75
      3644807.13     10159958.66
#Sta/Elev= 30
  4746.2  267.31  4887.4   264.5  4928.5  264.29  4950.5  262.02  4962.7  259.17
  4980.4  255.77  4985.9  255.02  5000.7  253.99  5003.4  253.49  5006.7  253.99
  5009.2  254.26  5026.9  259.19  5032.4  258.95    5038  260.65    5049  261.31
  5102.1  262.28  5107.6  261.97  5159.6  262.79  5200.6  264.61  5229.3  265.38
  5252.6  267.14  5258.1  266.94  5275.8   267.9  5281.3  267.64  5299.1  268.52
  5304.5  268.33  5322.3   269.1  5327.8  268.97    5351  270.04  5371.8  270.03
#Mann= 3 ,-1 , 0
  4746.2     .05       0  5000.7     .03       0  5006.7     .05       0
Bank Sta=5000.7,5006.7
XS Rating Curve= 0 ,0
Exp/Cntr=0.3,0.1

Type RM Length L Ch R = 1 ,2007    ,501,501,501
BEGIN DESCRIPTION:
UNT075 IN ROCK 4.0
END DESCRIPTION:
XS GIS Cut Line= 3
      3645570.18     10160148.75      3645488.94     10159821.65
      3645146.38     10159503.57
#Sta/Elev= 30
  4543.3  260.67  4597.3  259.02  4612.4   259.5  4638.6  257.73  4726.5  256.61
  4802.5  253.43  4859.7  251.23  4892.1  248.87  4927.8  249.93  4984.5  248.54
  4988.3  247.78    4991  247.28  4994.3  247.78    5015  248.01  5054.8  249.08
  5083.1  251.21  5090.5  250.95  5147.2  254.35    5154  253.05  5161.3   253.6
  5168.2  252.16  5175.5  252.84  5182.3  252.22  5210.7  253.19  5224.9  254.33
  5231.7  256.37    5239  256.79  5245.8   259.6  5253.2  260.22  5347.8  262.79
#Mann= 5 ,-1 , 0
  4543.3     .05       0  4802.5     .12       0  4988.3     .07       0
  4994.3     .12       0    5015     .05       0
Bank Sta=4988.3,4994.3
XS Rating Curve= 0 ,0
Exp/Cntr=0.3,0.1

Type RM Length L Ch R = 1 ,1506    ,463,463,463
BEGIN DESCRIPTION:
UNT075 IN ROCK 3.0
END DESCRIPTION:
XS GIS Cut Line= 3
      3645858.26     10160088.55      3645808.25     10159838.52
      3645697.79      10159226.9
#Sta/Elev= 30
  4697.4  264.05  4701.3  263.72  4808.4  259.36  4854.3  255.68  4903.3  254.42
  4928.8  254.26    4939  251.97  4948.2  248.38  4952.4  248.38  4956.6  246.78
  4979.7  246.33  4989.9  243.33    4997  240.39  4999.8  239.89    5003  240.39
  5010.1  243.56  5030.5  242.81  5040.7  243.33    5061  242.41  5101.6  241.96
  5111.8  242.28  5132.4  245.36  5233.7  247.26  5284.5  249.56    5293  249.35
  5304.9  250.36  5325.5  250.19    5376  252.09  5457.3  253.88  5573.9  252.38
#Mann= 6 ,-1 , 0
  4697.4      .1       0  4701.3     .05       0  4903.3     .12       0
    4997     .07       0    5003     .12       0  5325.5     .05       0
Bank Sta=4997,5003
XS Rating Curve= 0 ,0
Exp/Cntr=0.3,0.1

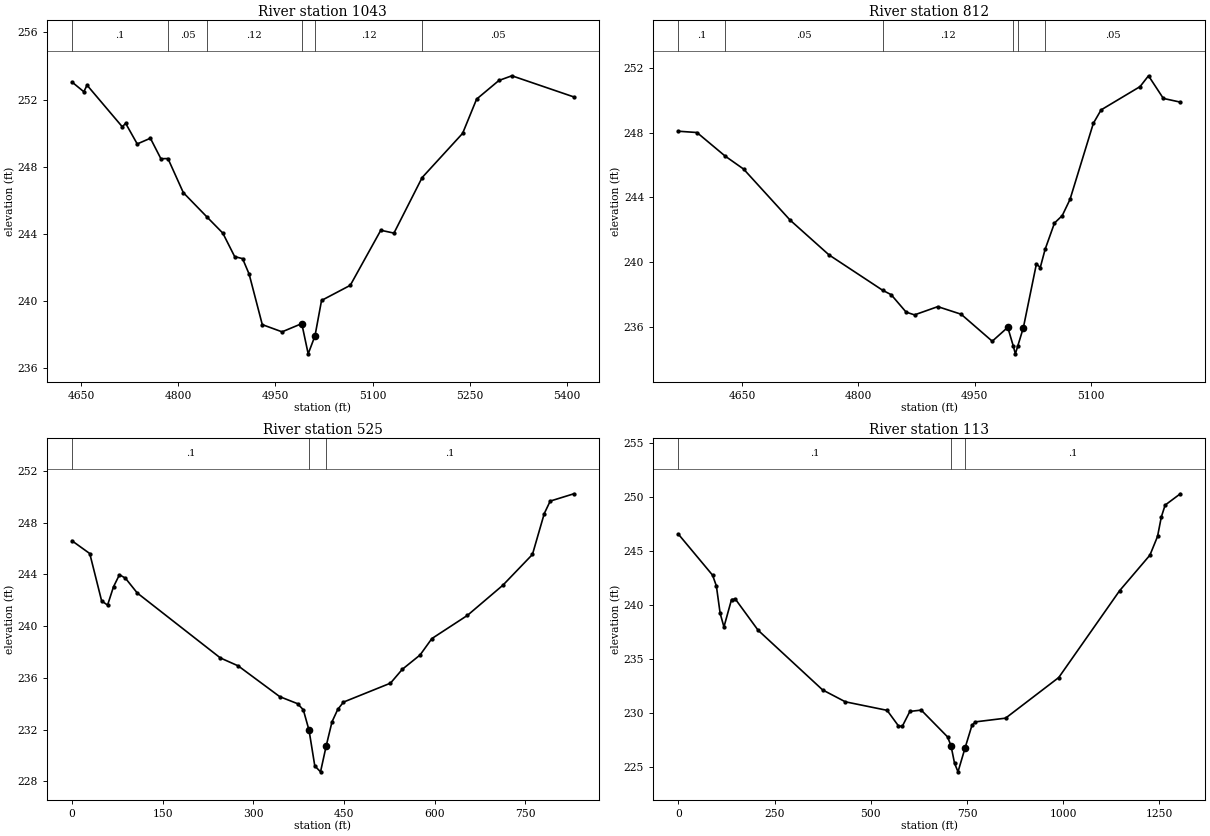
Type RM Length L Ch R = 1 ,1043    ,231,231,231
BEGIN DESCRIPTION:
UNT075 IN ROCK 2.0
END DESCRIPTION:
XS GIS Cut Line= 3
      3646150.92     10159950.85      3646043.15     10159335.39
      3646043.15     10159186.02
#Sta/Elev= 30
  4636.1  253.05  4654.4  252.47  4659.4  252.86  4713.8  250.38  4718.9  250.59
  4736.8  249.36  4757.1   249.7  4773.3  248.48  4784.2  248.49  4807.9  246.46
  4844.4  245.01  4868.8  244.05  4887.1  242.65  4899.3  242.53  4909.4  241.61
  4929.7   238.6  4960.2  238.17  4990.6  238.66  5000.5  236.86    5011  237.93
  5021.1  240.04  5065.4  240.94  5112.5  244.22  5132.8  244.05  5176.3  247.36
  5238.7  249.99  5260.3  252.03  5294.7  253.14  5314.7  253.42  5410.3  252.16
#Mann= 6 ,-1 , 0
  4636.1      .1       0  4784.2     .05       0  4844.4     .12       0
  4990.6     .07       0    5011     .12       0  5176.3     .05       0
Bank Sta=4990.6,5011
XS Rating Curve= 0 ,0
Exp/Cntr=0.3,0.1

Type RM Length L Ch R = 1 ,812     ,287,287,287
BEGIN DESCRIPTION:
Mapping XS 1ea23e36
END DESCRIPTION:
XS GIS Cut Line= 3
      3646200.59     10159875.47      3646222.29     10159484.83
      3646203.85     10159229.84
#Sta/Elev= 30
  4568.2  248.09  4592.1  248.01  4628.5  246.55  4652.2  245.75  4712.2  242.59
  4762.3  240.44  4831.5  238.25  4842.4  237.98  4861.7   236.9  4872.5  236.73
  4902.5  237.24  4932.6  236.77  4972.7   235.1  4992.7  235.96  4999.7  234.82
  5002.5  234.32  5005.7  234.82  5012.8  235.94  5029.6  239.88  5034.6  239.66
  5040.8  240.78  5052.9  242.41  5062.9  242.87  5072.9  243.87    5103  248.58
    5113  249.41  5163.2  250.85  5174.1  251.52  5193.2  250.12  5215.1  249.89
#Mann= 6 ,-1 , 0
  4568.2      .1       0  4628.5     .05       0  4831.5     .12       0
  4999.7     .07       0  5005.7     .12       0  5040.8     .05       0
Bank Sta=4992.7,5012.8
XS Rating Curve= 0 ,0
Exp/Cntr=0.3,0.1

Type RM Length L Ch R = 1 ,525     ,412,412,412
XS GIS Cut Line= 4
      3646325.85      10159968.4     3646423.506    10159606.421
     3646437.829    10159513.973     3646271.162    10159189.754
#Sta/Elev= 30
       0246.599729.47099245.610649.11832241.950958.94199241.628568.76566243.0457
78.58932243.974388.41298243.7108108.0603242.5634245.5916 237.544275.0626236.9323
343.8282234.5541373.2993234.0112382.7979233.5378392.2966231.9538401.7953 229.201
411.2939228.7452420.7926230.7752430.2913232.6112439.7899233.5699449.2886234.1343
 527.011235.5968546.5861236.6666575.9486237.7717595.5236239.0428654.2487240.8302
712.9738243.1636761.9113245.5415781.4863248.7028791.2739249.6635830.4239250.2294
#Mann= 3 , 0 , 0
       0      .1       0392.2966     .07       0420.7926      .1       0
Bank Sta=392.2966,420.7926
XS Rating Curve= 0 ,0
Exp/Cntr=0.3,0.1

Type RM Length L Ch R = 1 ,113     ,0,0,0
XS GIS Cut Line= 4
     3646383.141      10160030.9     3646784.183      10159468.4
     3646764.652    10159379.858     3646288.089    10159159.806
#Sta/Elev= 30
       0246.548288.74281242.751898.60313241.7554108.4634239.2082118.3238237.9515
138.0444240.4929147.9047240.5366207.0666 237.645374.6919 232.113433.8538231.0086
542.3172230.2174571.8981228.7721581.7584228.7332601.4791230.1179  631.06230.2401
699.3064227.7607708.3909226.9381717.4753 225.328726.5599224.5157744.7288226.7093
762.8978228.8372771.9823229.1493850.1741229.4924988.3886233.26191146.348 241.302
1225.328244.60871245.073246.33831254.945248.14811264.818249.24671304.307250.2966
#Mann= 3 , 0 , 0
       0      .1       0708.3909     .07       0744.7288      .1       0
Bank Sta=708.3909,744.7288
XS Rating Curve= 0 ,0
Exp/Cntr=0.3,0.1

Chan Stop Cuts=-1
Use User Specified Reach Order=0
Composite Channel Slope=5