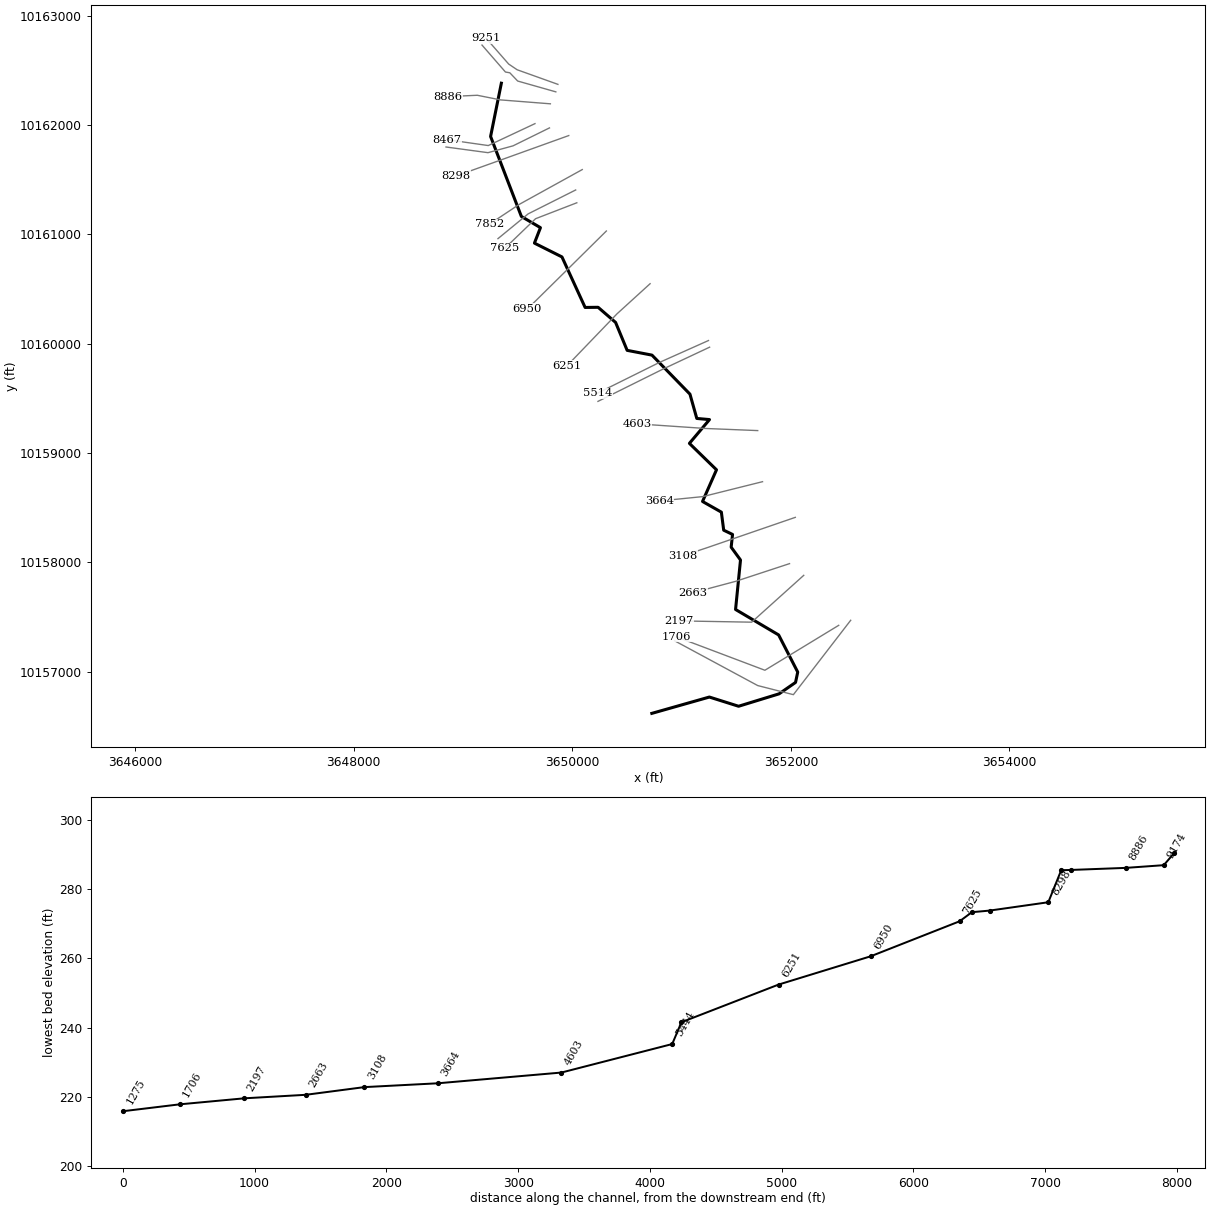
--- UNT076 IN ROCK.prj (project) ---

Proj Title=UNT076 IN ROCK Base Level Engineering
Current Plan=p01
Default Exp/Contr=0.3,0.1
English Units
Geom File=g01
Flow File=f01
Plan File=p01
Y Axis Title=Elevation
X Axis Title(PF)=Main Channel Distance
X Axis Title(XS)=Station
BEGIN DESCRIPTION:
UNT076 IN ROCK
END DESCRIPTION:
DSS Export Rating Curves= 0
DSS Export Rating Curve Sorted= 0
DSS Export Volume Flow Curves= 0
DXF OffsetX= 0
DXF OffsetY= 0
DXF ScaleX= 1
DXF ScaleY= 10

--- UNT076 IN ROCK.p01 (plan) ---

Plan Title=Multiple Run
Short Identifier=Multiple
Geom File=g01
Flow File=f01
Subcritical Flow
K Sum by GR= 0
Std Step Tol= 0.01
Critical Tol= 0.01
Num of Std Step Trials= 20
Max Error Tol= 0.3
Flow Tol Ratio= 0.001
Split Flow NTrial= 30
Split Flow Tol= 0.02
Split Flow Ratio= 0.02
Log Output Level= 0
Friction Slope Method= 1
Unsteady Friction Slope Method= 2
Unsteady Bridges Friction Slope Method= 1
Parabolic Critical Depth
Global Vel Dist=  1 , 1 , 1
Global Log Level= 0
CheckData=True
Encroach Param= -1, 0, 0, 0
BEGIN DESCRIPTION:
Multiple Run
END DESCRIPTION:

--- UNT076 IN ROCK.f01 (steady flow) ---

Flow Title=Multiple
Program Version=4.10
Number of Profiles= 7
Profile Names=10-year,25-year,50-year,1pct_min,100-year,1pct_plu,500-year
River Rch & RM=UNT076 IN ROCK,Reach-1         ,9251
     449     595     713     628     849    1148    1203
Boundary for River Rch & Prof#=UNT076 IN ROCK,Reach-1         , 1
Up Type= 0
Dn Type= 3
Dn Slope=0.005
Boundary for River Rch & Prof#=UNT076 IN ROCK,Reach-1         , 2
Up Type= 0
Dn Type= 3
Dn Slope=0.005
Boundary for River Rch & Prof#=UNT076 IN ROCK,Reach-1         , 3
Up Type= 0
Dn Type= 3
Dn Slope=0.005
Boundary for River Rch & Prof#=UNT076 IN ROCK,Reach-1         , 4
Up Type= 0
Dn Type= 3
Dn Slope=0.005
Boundary for River Rch & Prof#=UNT076 IN ROCK,Reach-1         , 5
Up Type= 0
Dn Type= 3
Dn Slope=0.005
Boundary for River Rch & Prof#=UNT076 IN ROCK,Reach-1         , 6
Up Type= 0
Dn Type= 3
Dn Slope=0.005
Boundary for River Rch & Prof#=UNT076 IN ROCK,Reach-1         , 7
Up Type= 0
Dn Type= 3
Dn Slope=0.005
DSS Import GetInterval= 0
DSS Import GetPeak= 0
DSS Import FillOption= 0

--- UNT076 IN ROCK.g01 (geometry) ---

Geom Title=Existing Conditions
Program Version=4.10

River Reach=UNT076 IN ROCK  ,Reach-1
Reach XY= 30
      3649351.94     10162381.71      3649253.59      10161894.5
      3649535.13     10161162.68      3649709.58     10161060.28
      3649654.48     10160918.87      3649906.35     10160792.62
      3650118.16     10160330.46      3650237.07     10160331.78
        3650397.     10160193.39      3650502.66     10159937.99
      3650729.88     10159894.28      3651077.19     10159537.42
      3651139.79     10159315.05      3651256.07     10159304.73
        3651072.      10159087.2      3651319.93     10158845.39
      3651192.19     10158555.68      3651364.48     10158458.01
      3651385.79     10158293.01      3651466.76       10158254.
      3651454.07     10158137.61      3651539.53     10158020.26
      3651494.32     10157567.62       3651888.3     10157334.76
        3652063.     10156995.18      3652042.91     10156900.31
      3651892.74     10156796.14      3651522.08     10156682.42
      3651254.72     10156766.63      3650728.34      10156617.3

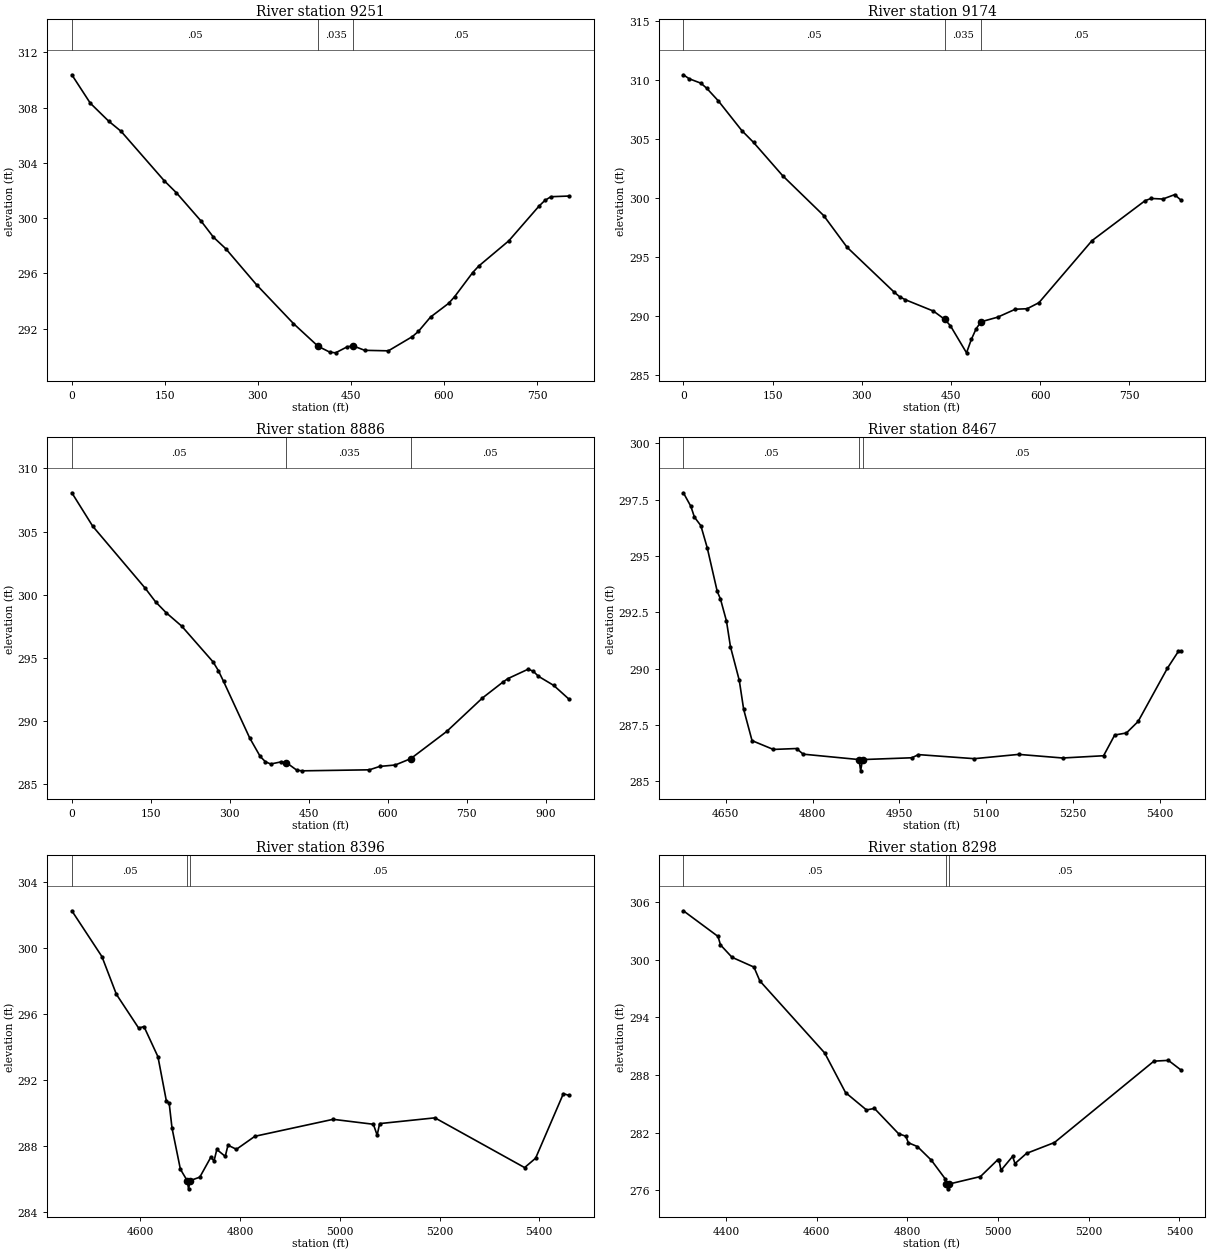
Type RM Length L Ch R = 1 ,9251    ,77,77,77
XS GIS Cut Line= 4
     3649869.407    10162371.089     3649496.143    10162504.769
     3649418.886    10162556.853     3649213.157    10162792.096
#Sta/Elev= 30
       0 310.36929.77546308.312559.55092307.006479.40123306.2769148.8773302.7057
168.7276301.8222208.4282299.7795228.2785298.6171248.1288297.7831297.7546295.1741
357.3055292.3641397.0061290.7192 415.785290.2975425.1745290.2447443.9534290.6809
453.3429290.7535472.1218290.4272510.3205290.3897  549.16291.4228558.8699 291.802
578.2897292.8329607.4194293.8235617.1293294.3066 646.259296.0526655.9689 296.523
704.5184298.3523753.0678300.8569762.7777 301.279772.4876301.5446801.6173301.5927
#Mann= 3 , 0 , 0
       0     .05       0397.0061    .035       0453.3429     .05       0
Bank Sta=397.0061,453.3429
XS Rating Curve= 0 ,0
Exp/Cntr=0.3,0.1

Type RM Length L Ch R = 1 ,9174    ,288,288,288
XS GIS Cut Line= 5
      3649850.31    10162302.512     3649501.352    10162401.471
     3649429.303    10162476.992     3649389.372    10162483.936
     3649174.963    10162730.464
#Sta/Elev= 30
       0310.41839.825774  310.0829.47732309.7047 39.3031309.273958.95465308.1954
98.25774305.6894117.9093304.6897167.0382301.8572235.8186298.4894275.1217295.8024
353.7279292.0266363.5536291.6025373.0424291.3543420.4861290.3859439.4636 289.685
448.9524289.1438476.0359286.8496484.1418287.9917492.2478288.8955500.3538289.4803
528.3009289.8718558.0625290.5473577.9036290.5883597.7447291.0997687.0295296.3638
776.3144299.7499786.2349299.9349 806.076299.8864825.9171300.2583835.8376299.8202
#Mann= 3 , 0 , 0
       0     .05       0439.4636    .035       0500.3538     .05       0
Bank Sta=439.4636,500.3538
XS Rating Curve= 0 ,0
Exp/Cntr=0.3,0.1

Type RM Length L Ch R = 1 ,8886    ,419,419,419
XS GIS Cut Line= 4
     3649800.397    10162193.137     3649344.668    10162228.945
     3649131.994    10162271.262     3648862.897    10162259.327
#Sta/Elev= 30
       0308.077939.74928305.4263139.1225300.5354158.9971299.4476178.8718 298.596
208.6837297.5235268.3077294.6897 278.245294.0057288.1823293.1459337.8689288.6664
357.7436287.2096367.6809286.7886377.6182286.6117397.4928286.7805407.4302286.7234
427.3048286.1205437.2421 286.071565.1339286.1521584.7734286.4205614.2326286.5335
643.6918287.0362711.8804289.1863779.6569291.8315818.3863293.0848828.0687293.3693
 866.798294.1182876.4804293.9469886.1628293.5541915.2098292.8311944.2569291.7405
#Mann= 3 ,-1 , 0
       0     .05       0407.4302    .035       0643.6918     .05       0
Bank Sta=407.4302,643.6918
XS Rating Curve= 0 ,0
Exp/Cntr=0.3,0.1

Type RM Length L Ch R = 1 ,8467    ,71,71,71
BEGIN DESCRIPTION:
Mapping XS e6fb56d3
END DESCRIPTION:
XS GIS Cut Line= 3
      3649659.43     10162011.82      3649232.39     10161811.32
      3648849.54     10161866.01
#Sta/Elev= 30
  4576.9  297.81  4589.8  297.21    4596  296.73  4607.1  296.35  4618.1  295.37
  4635.4  293.43  4640.9   293.1  4651.3  292.12  4658.2  290.98  4673.4  289.49
    4681   288.2  4695.5  286.81  4732.2  286.42  4772.3  286.46  4783.8  286.21
  4880.3  285.97    4883  285.47  4886.3  285.97  4971.6  286.05  4982.7  286.19
  5079.3  286.01    5156   286.2  5231.8  286.04  5302.5  286.14  5321.7  287.06
  5341.9  287.15  5362.1  287.66  5412.6  290.02  5431.6  290.77  5435.4  290.77
#Mann= 3 ,-1 , 0
  4576.9     .05       0  4880.3     .03       0  4886.3     .05       0
Bank Sta=4880.3,4886.3
XS Rating Curve= 0 ,0
Exp/Cntr=0.3,0.1

Type RM Length L Ch R = 1 ,8396    ,98,98,98
BEGIN DESCRIPTION:
Mapping XS e81929b3
END DESCRIPTION:
XS GIS Cut Line= 4
      3649792.25     10161972.76      3649458.95     10161808.71
      3649229.78     10161746.21       3648845.7     10161798.12
#Sta/Elev= 30
    4463  302.28  4523.3   299.5  4552.3  297.21  4596.9  295.16  4607.6  295.25
  4635.6  293.42  4652.5  290.73  4658.1   290.6  4663.8  289.09  4680.6  286.59
  4694.2   285.9    4697   285.4  4700.2   285.9  4719.5  286.11  4741.8  287.33
    4748  287.09  4753.6  287.79  4770.5  287.37    4776  288.05  4792.9   287.8
  4829.9  288.59  4986.7  289.62  5067.4  289.32    5075  288.66    5080  289.36
  5190.8  289.71  5370.6  286.69  5392.6  287.26  5448.3  291.18  5459.6  291.07
#Mann= 3 ,-1 , 0
    4463     .05       0  4694.2     .03       0  4700.2     .05       0
Bank Sta=4694.2,4700.2
XS Rating Curve= 0 ,0
Exp/Cntr=0.3,0.1

Type RM Length L Ch R = 1 ,8298    ,446,446,446
BEGIN DESCRIPTION:
UNT076 IN ROCK 15.0
END DESCRIPTION:
XS GIS Cut Line= 3
       3649968.5     10161902.69      3649315.79     10161668.07
      3648936.86     10161532.36
#Sta/Elev= 30
  4306.4   305.1  4382.8  302.43  4388.2  301.55  4413.6  300.26    4462  299.24
    4475   297.8    4618   290.3  4663.9  286.18  4710.1  284.37  4727.6  284.53
  4780.8   281.9    4797  281.63  4802.3  280.96  4822.4  280.56  4853.1  279.14
  4883.8  277.19  4886.2  276.66  4888.9  276.16  4892.2  276.66  4961.4  277.44
  4999.3  279.18  5002.1  279.18  5006.7  278.09  5032.2  279.54  5037.5  278.79
  5062.9  279.85  5124.5  280.98  5343.8  289.45  5375.7  289.53  5402.5  288.56
#Mann= 3 ,-1 , 0
  4306.4     .05       0  4886.2     .03       0  4892.2     .05       0
Bank Sta=4886.2,4892.2
XS Rating Curve= 0 ,0
Exp/Cntr=0.3,0.1

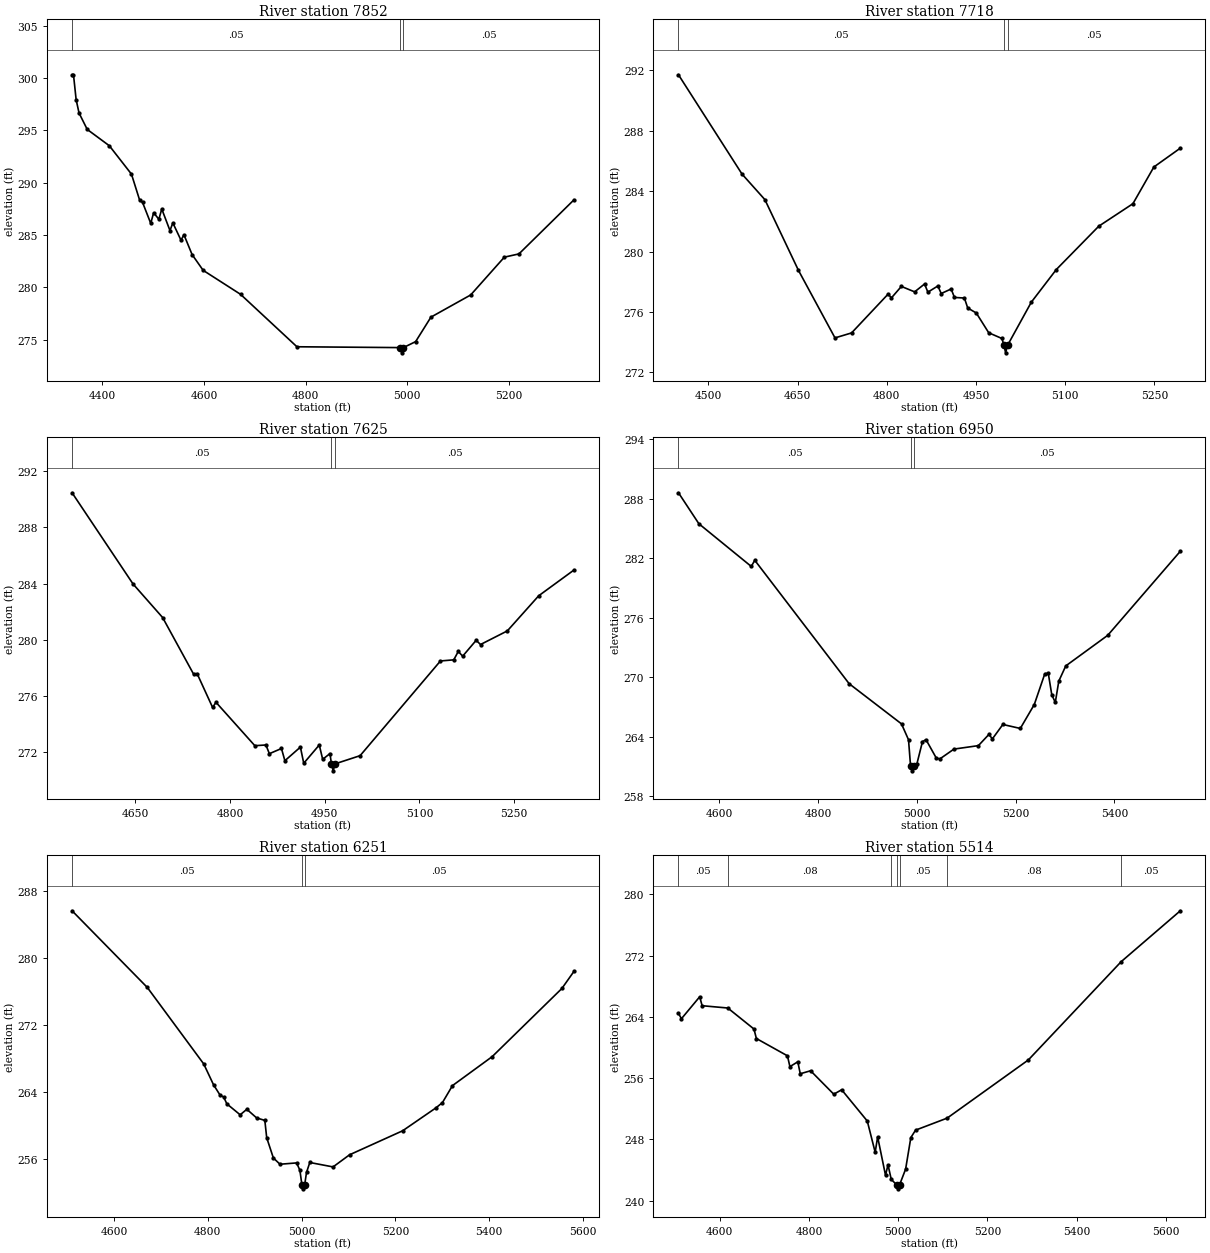
Type RM Length L Ch R = 1 ,7852    ,134,134,134
BEGIN DESCRIPTION:
UNT076 IN ROCK 14.0
END DESCRIPTION:
XS GIS Cut Line= 3
       3650092.1     10161591.64        3649515.     10161272.84
      3649242.08     10161091.63
#Sta/Elev= 30
  4340.7  300.31  4343.5  300.31  4348.7  297.93  4354.4  296.66  4370.5  295.09
    4414  293.53  4457.5  290.82  4473.6  288.33  4479.3  288.12  4495.4  286.12
  4501.1  287.13  4511.4  286.51  4517.1  287.49  4533.2  285.43  4538.9  286.16
  4554.9  284.51  4560.7  285.03  4576.7  283.14  4598.5  281.63    4672  279.34
  4782.9  274.33  4986.2  274.25  4988.9  273.75  4992.2  274.25  5016.3  274.82
  5046.4  277.16  5124.6  279.28  5190.8  282.89  5219.5   283.2  5327.6  288.36
#Mann= 3 ,-1 , 0
  4340.7     .05       0  4986.2     .03       0  4992.2     .05       0
Bank Sta=4986.2,4992.2
XS Rating Curve= 0 ,0
Exp/Cntr=0.3,0.1

Type RM Length L Ch R = 1 ,7718    ,93,93,93
BEGIN DESCRIPTION:
Mapping XS 6238dabc
END DESCRIPTION:
XS GIS Cut Line= 3
      3650031.88     10161405.08      3649596.97     10161186.32
      3649320.96     10160959.78
#Sta/Elev= 30
  4449.6  291.71  4556.5  285.13  4594.9  283.44  4651.4  278.75  4712.8  274.28
  4740.7  274.61  4802.1  277.18  4807.7  276.93  4824.4  277.69  4846.7  277.33
  4863.4  277.85    4869  277.31  4885.8  277.72  4891.4  277.22  4908.1  277.52
  4913.7  276.96  4930.4  276.92    4936  276.26  4950.4  275.93  4971.3  274.62
  4993.5  274.24    4997  273.79  4999.7  273.29    5003  273.79    5043  276.65
    5085  278.81  5156.4  281.68  5213.8  283.17    5249   285.6  5293.5  286.85
#Mann= 3 ,-1 , 0
  4449.6     .05       0    4997     .03       0    5003     .05       0
Bank Sta=4997,5003
XS Rating Curve= 0 ,0
Exp/Cntr=0.3,0.1

Type RM Length L Ch R = 1 ,7625    ,675,675,675
BEGIN DESCRIPTION:
Mapping XS fccf17bc
END DESCRIPTION:
XS GIS Cut Line= 3
      3650042.25     10161287.87      3649664.68     10161142.05
      3649383.43     10160871.22
#Sta/Elev= 30
  4549.6  290.46  4646.2  283.97  4693.1  281.58  4742.3  277.54  4747.7  277.59
  4772.3  275.18  4777.6  275.55  4839.2  272.46  4856.8  272.51  4862.2  271.89
  4881.4  272.26  4886.8  271.39  4911.4  272.36  4916.7  271.21  4941.3  272.51
  4946.7  271.49  4958.3   271.9  4960.5  271.17  4963.3  270.67  4966.5  271.17
    5006  271.75  5133.3  278.49  5154.4  278.57  5161.6  279.17  5168.5  278.83
  5189.9  279.96  5196.8  279.66  5239.3  280.63    5289  283.13  5344.8  284.96
#Mann= 3 ,-1 , 0
  4549.6     .05       0  4960.5     .03       0  4966.5     .05       0
Bank Sta=4960.5,4966.5
XS Rating Curve= 0 ,0
Exp/Cntr=0.3,0.1

Type RM Length L Ch R = 1 ,6950    ,699,699,699
BEGIN DESCRIPTION:
UNT076 IN ROCK 12.0
END DESCRIPTION:
XS GIS Cut Line= 3
      3650312.43     10161029.63      3649969.54     10160690.59
      3649589.97     10160315.98
#Sta/Elev= 30
  4517.8  288.58  4559.1  285.46  4665.1  281.16  4672.2  281.78  4863.1  269.35
  4969.1   265.3  4983.3   263.7  4987.4  261.07  4990.1  260.57  4993.4  261.07
    5000  261.22  5011.5  263.51  5018.7  263.71  5039.8  261.83    5047  261.78
  5075.2  262.76  5124.7  263.11    5146  264.24    5153  263.79  5174.2  265.24
  5209.5  264.84  5237.8  267.25  5259.1  270.35  5266.1   270.4  5273.2  268.23
  5280.3  267.46  5287.4  269.61  5301.5  271.14  5386.4  274.22  5533.3  282.69
#Mann= 3 ,-1 , 0
  4517.8     .05       0  4987.4     .03       0  4993.4     .05       0
Bank Sta=4987.4,4993.4
XS Rating Curve= 0 ,0
Exp/Cntr=0.3,0.1

Type RM Length L Ch R = 1 ,6251    ,737,737,737
BEGIN DESCRIPTION:
UNT076 IN ROCK 11.0
END DESCRIPTION:
XS GIS Cut Line= 3
      3650712.62     10160547.58      3650410.33     10160272.45
      3649951.61     10159795.76
#Sta/Elev= 30
  4510.5  285.65    4671  276.48  4791.3  267.34  4812.2  264.85  4826.4  263.59
  4833.8  263.39  4840.6  262.57    4869  261.26  4883.2  261.92  4904.1  260.89
  4921.6  260.59  4925.6  258.52  4939.8   256.1  4953.9  255.35  4989.4  255.51
  4996.4  254.63  5000.6  252.91  5003.3  252.41  5006.6  252.91  5010.5  254.37
  5017.5  255.56  5067.1  255.03  5102.3  256.48  5215.5  259.35  5286.3  262.08
  5300.4  262.72  5321.8  264.75  5406.4  268.21  5555.1  276.36  5580.8   278.4
#Mann= 3 ,-1 , 0
  4510.5     .05       0  5000.6     .03       0  5006.6     .05       0
Bank Sta=5000.6,5006.6
XS Rating Curve= 0 ,0
Exp/Cntr=0.3,0.1

Type RM Length L Ch R = 1 ,5514    ,70,70,70
BEGIN DESCRIPTION:
UNT076 IN ROCK 9.0
END DESCRIPTION:
XS GIS Cut Line= 3
      3651246.55     10160027.82      3650796.98     10159826.97
      3650230.69     10159545.93
#Sta/Elev= 30
  4507.6  264.46  4514.2  263.75  4555.2  266.62  4560.6  265.45  4618.1  265.15
  4676.7  262.41  4682.2  261.17  4751.8  258.91  4757.3   257.5    4775  258.13
  4780.5  256.57  4803.7  256.96  4855.6   253.9  4873.3  254.48  4930.7   250.4
  4948.4  246.32  4953.9  248.34  4971.6  243.31  4977.1  244.69  4984.4  242.79
  4996.9  242.05  4999.7  241.55  5002.9  242.05  5016.6  244.12  5028.3  248.24
  5038.9  249.21  5109.7  250.78  5291.6  258.37  5499.7   271.2  5632.2  277.84
#Mann= 7 ,-1 , 0
  4507.6     .05       0  4618.1     .08       0  4984.4     .05       0
  4996.9    .035       0  5002.9     .05       0  5109.7     .08       0
  5499.7     .05       0
Bank Sta=4996.9,5002.9
XS Rating Curve= 0 ,0
Exp/Cntr=0.3,0.1

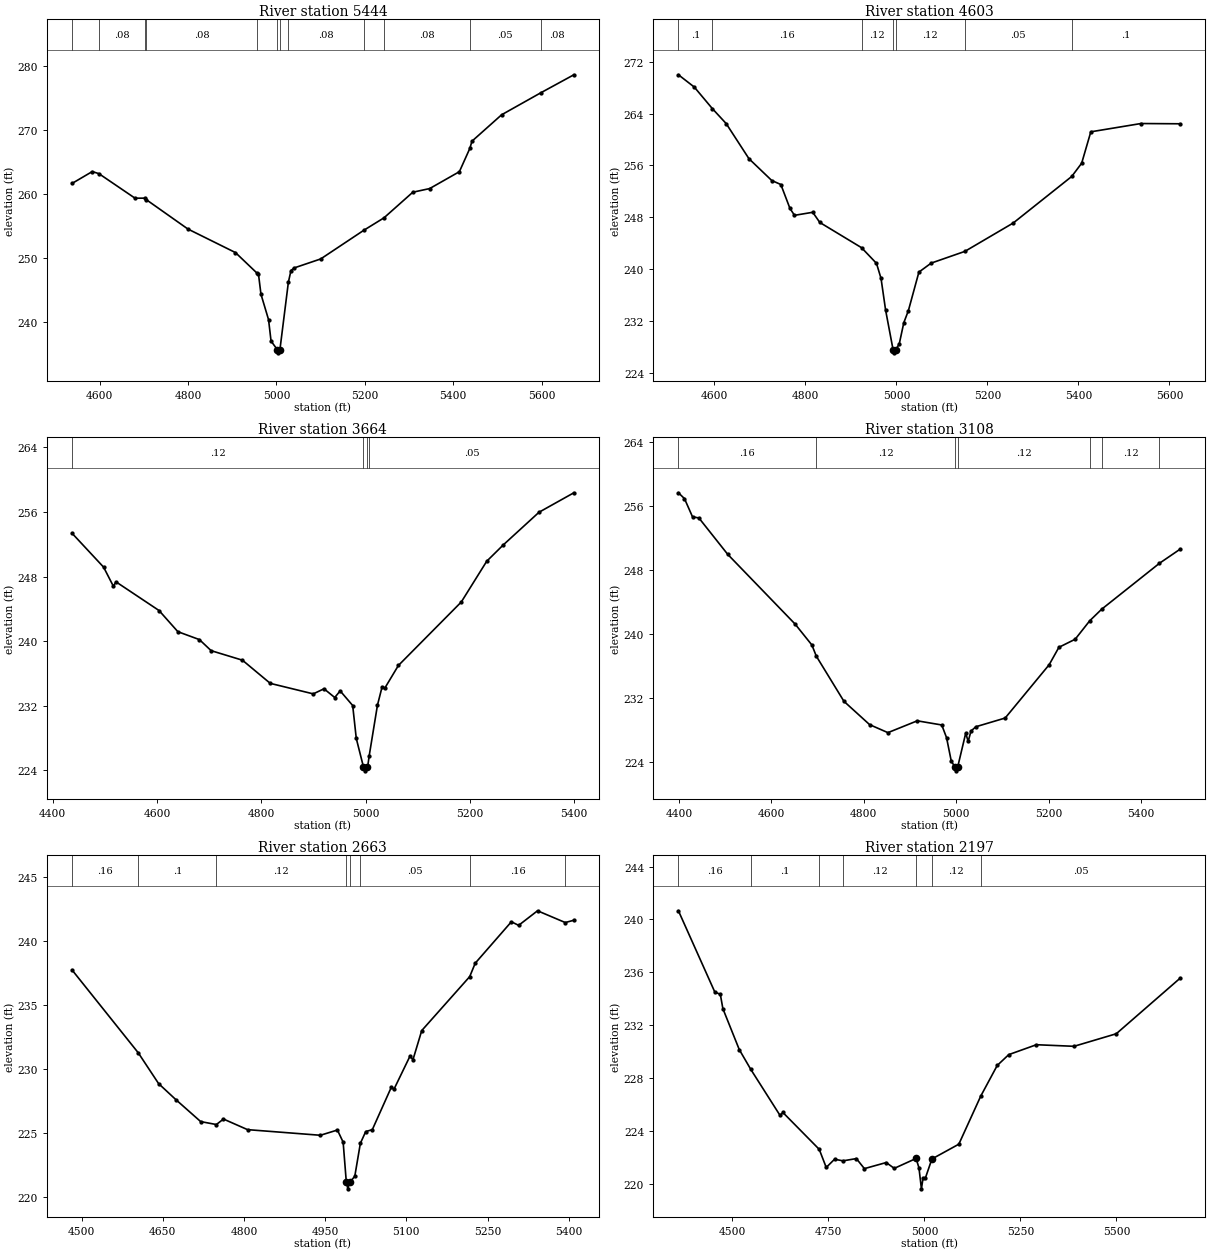
Type RM Length L Ch R = 1 ,5444    ,841,841,841
BEGIN DESCRIPTION:
UNT076 IN ROCK 8.0
END DESCRIPTION:
XS GIS Cut Line= 3
      3651256.91     10159967.03      3650838.39     10159770.42
      3650235.78     10159471.22
#Sta/Elev= 30
  4537.6  261.63  4583.6  263.49  4598.6  263.16  4680.3  259.34  4703.5  259.35
  4705.6  259.12  4799.9  254.54  4907.5  250.87  4955.6  247.71  4959.5  247.52
  4965.1  244.39  4982.3  240.42  4987.9   237.1    5002  235.76  5004.7  235.26
    5008  235.76  5027.1  246.25    5033  248.08  5040.5  248.49  5100.2  249.88
  5197.6  254.34  5243.3  256.28  5308.5  260.27  5346.7  260.84  5413.9  263.47
  5437.5  267.09  5442.4  268.22  5509.4  272.33  5597.9  275.75  5672.8  278.56
#Mann= 12 ,-1 , 0
  4537.6     .05       0  4598.6     .08       0  4703.5     .05       0
  4705.6     .08       0  4955.6     .05       0    5002    .035       0
    5008     .05       0  5027.1     .08       0  5197.6     .05       0
  5243.3     .08       0  5437.5     .05       0  5597.9     .08       0
Bank Sta=5002,5008
XS Rating Curve= 0 ,0
Exp/Cntr=0.3,0.1

Type RM Length L Ch R = 1 ,4603    ,939,939,939
BEGIN DESCRIPTION:
UNT076 IN ROCK 7.0
END DESCRIPTION:
XS GIS Cut Line= 3
      3651697.02     10159204.07      3651218.21     10159223.43
      3650595.85     10159265.72
#Sta/Elev= 30
  4520.8  269.99  4555.7  268.09  4595.3  264.77  4625.8  262.45  4675.8  257.03
  4725.9  253.66  4745.9  253.04  4765.9  249.35  4775.9  248.28    4816  248.75
  4831.5  247.18  4923.3  243.28  4956.1  240.86  4966.1  238.53  4976.1  233.65
  4992.5  227.54  4995.3  227.04  4998.5  227.54  5006.1  228.41  5016.1  231.69
  5026.2  233.56  5049.3  239.51  5076.3   240.9  5150.3  242.71  5256.7   247.1
  5385.1  254.28    5407  256.33  5427.1  261.18  5537.3  262.46  5623.8  262.42
#Mann= 7 ,-1 , 0
  4520.8      .1       0  4595.3     .16       0  4923.3     .12       0
  4992.5     .07       0  4998.5     .12       0  5150.3     .05       0
  5385.1      .1       0
Bank Sta=4992.5,4998.5
XS Rating Curve= 0 ,0
Exp/Cntr=0.3,0.1

Type RM Length L Ch R = 1 ,3664    ,556,556,556
BEGIN DESCRIPTION:
UNT076 IN ROCK 5.0
END DESCRIPTION:
XS GIS Cut Line= 3
      3651741.03     10158736.65      3651194.62     10158600.18
      3650797.42     10158560.28
#Sta/Elev= 30
  4436.8  253.37  4497.5  249.16  4516.2   246.8  4521.3  247.34  4603.8  243.79
  4639.9  241.17  4681.2  240.19  4703.7  238.82  4763.7  237.64  4817.1  234.77
  4899.5  233.47  4920.1   234.1  4940.7  233.02  4951.1  233.84  4975.1  232.03
    4982  227.95  4995.7  224.44  4998.5  223.94  5001.7  224.44  5003.8  224.44
  5006.8  225.82  5022.6  232.07  5031.5  234.34  5036.5  234.16  5062.8  236.99
  5183.4  244.85  5232.1  249.89  5263.8  251.91  5332.4  255.96  5399.2  258.37
#Mann= 4 ,-1 , 0
  4436.8     .12       0  4995.7     .07       0  5001.7     .12       0
  5006.8     .05       0
Bank Sta=4995.7,5001.7
XS Rating Curve= 0 ,0
Exp/Cntr=0.3,0.1

Type RM Length L Ch R = 1 ,3108    ,445,445,445
BEGIN DESCRIPTION:
UNT076 IN ROCK 4.0
END DESCRIPTION:
XS GIS Cut Line= 3
      3652040.96     10158410.37      3651228.82     10158131.08
      3651012.84     10158059.37
#Sta/Elev= 30
  4398.7  257.64  4411.8  256.91  4429.2  254.63    4443  254.49  4505.5  249.93
  4651.1  241.22  4687.6  238.59  4697.2  237.19    4757  231.54  4812.6  228.62
  4852.2  227.62  4915.7   229.1  4968.7  228.58  4979.1  226.99  4989.4  224.03
  4997.3  223.34    5000  222.84  5003.3  223.34  5020.6  227.56  5025.9  226.52
    5032  227.82  5042.6  228.36    5106  229.45  5201.2  236.12  5222.3   238.3
  5257.5  239.31    5289  241.62  5314.9  243.07  5439.8  248.81  5485.1   250.6
#Mann= 7 ,-1 , 0
  4398.7     .16       0  4697.2     .12       0  4997.3     .07       0
  5003.3     .12       0    5289     .05       0  5314.9     .12       0
  5439.8     .05       0
Bank Sta=4997.3,5003.3
XS Rating Curve= 0 ,0
Exp/Cntr=0.3,0.1

Type RM Length L Ch R = 1 ,2663    ,466,466,466
BEGIN DESCRIPTION:
UNT076 IN ROCK 3.0
END DESCRIPTION:
XS GIS Cut Line= 3
      3651988.02     10157987.06      3651496.12     10157825.35
      3651100.56      10157719.8
#Sta/Elev= 30
  4482.2  237.75  4604.7  231.26  4642.3  228.85  4674.1   227.6    4720  225.88
    4749  225.65  4762.1  226.08  4806.6  225.25  4941.1  224.81  4972.6  225.22
  4983.2  224.27  4989.1  221.12  4991.9  220.62  4995.1  221.12  5004.7   221.6
    5015  224.18  5024.9   225.1  5037.1  225.25    5072  228.55  5077.2  228.42
  5106.9  231.02  5112.1  230.71  5128.4     233    5217  237.22  5227.2  238.27
    5294  241.51  5307.4  241.23  5342.3  242.37  5393.5  241.45  5409.4  241.63
#Mann= 8 ,-1 , 0
  4482.2     .16       0  4604.7      .1       0    4749     .12       0
  4989.1     .07       0  4995.1     .12       0    5015     .05       0
    5217     .16       0  5393.5     .05       0
Bank Sta=4989.1,4995.1
XS Rating Curve= 0 ,0
Exp/Cntr=0.3,0.1

Type RM Length L Ch R = 1 ,2197    ,491,491,491
BEGIN DESCRIPTION:
UNT076 IN ROCK 2.0
END DESCRIPTION:
XS GIS Cut Line= 3
      3652117.91     10157879.91      3651641.74     10157451.54
      3650975.35     10157463.32
#Sta/Elev= 30
  4359.5  240.66  4454.4   234.5  4468.6  234.34  4475.3  233.25    4518  230.15
  4547.8  228.66  4624.1  225.17  4631.6  225.39  4726.2   222.6  4744.4  221.23
  4766.1  221.85  4788.1  221.73  4822.9   221.9  4843.8  221.14  4900.6   221.6
  4921.6  221.16  4978.4  221.91  4985.9   221.2  4992.3  219.61  4996.4   220.4
  5002.3   220.4  5019.6  221.87  5089.7  222.99  5146.8  226.63  5189.7  228.95
  5219.7  229.77  5291.7  230.52  5389.7   230.4  5499.7  231.35  5666.5  235.57
#Mann= 7 ,-1 , 0
  4359.5     .16       0  4547.8      .1       0  4726.2     .16       0
  4788.1     .12       0  4978.4     .07       0  5019.6     .12       0
  5146.8     .05       0
Bank Sta=4978.4,5019.6
XS Rating Curve= 0 ,0
Exp/Cntr=0.3,0.1

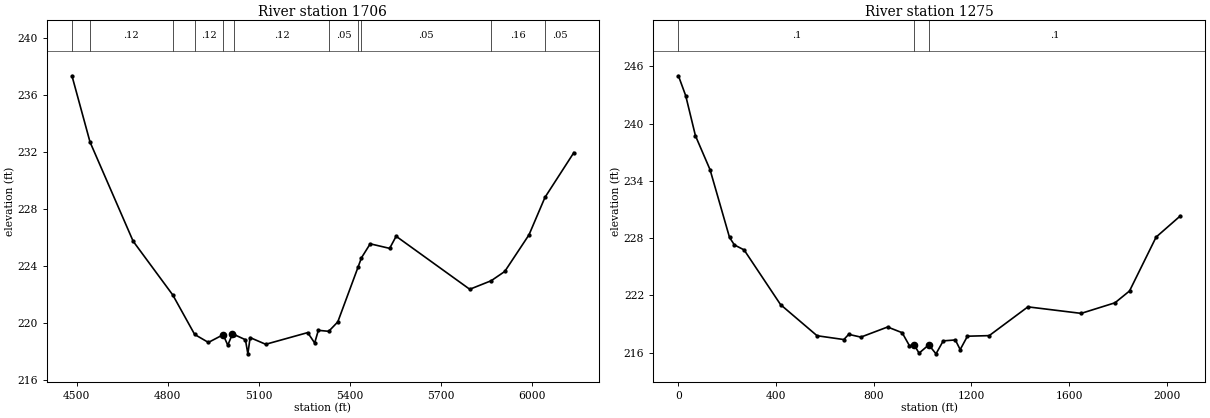
Type RM Length L Ch R = 1 ,1706    ,431,431,431
BEGIN DESCRIPTION:
UNT076 IN ROCK 1.0
END DESCRIPTION:
XS GIS Cut Line= 3
      3652437.77     10157422.63      3651762.62     10157011.78
      3650953.97     10157317.09
#Sta/Elev= 30
  4484.4  237.38    4544  232.73  4686.2  225.77  4816.8     222    4889  219.23
  4934.2  218.67  4982.7  219.21  4998.2  218.48  5013.6  219.26  5019.5  219.22
  5056.3  218.86  5064.4  217.87  5071.8  219.01  5123.2  218.54  5261.6  219.36
  5284.6  218.63  5296.7  219.52  5330.9  219.45  5360.8  220.11  5428.1  223.98
  5438.9  224.61  5467.7  225.59  5531.8  225.27  5553.2  226.12  5795.9   222.4
  5866.6     223  5911.3  223.65  5991.2  226.22  6043.9  228.85  6139.1  231.99
#Mann= 11 ,-1 , 0
  4484.4     .16       0    4544     .12       0  4816.8     .16       0
    4889     .12       0  4982.7     .07       0  5019.5     .12       0
  5330.9     .05       0  5428.1     .12       0  5438.9     .05       0
  5866.6     .16       0  6043.9     .05       0
Bank Sta=4982.7,5013.6
XS Rating Curve= 0 ,0
Exp/Cntr=0.3,0.1

Type RM Length L Ch R = 1 ,1275    ,0,0,0
XS GIS Cut Line= 5
      3652547.54     10157468.95     3652023.234    10156788.395
     3651696.845    10156871.728     3650936.429     10157281.45
3650936.4287850710157281.4501158
#Sta/Elev= 30
       0244.996729.89482242.909969.75459 238.717129.5442235.1674209.2638228.0813
229.1936227.2881269.0534226.7648418.5275221.0334568.0016217.7778 677.616217.3792
697.5459217.9233747.3706217.6346 856.985218.6928916.4307218.0969946.1536216.7443
965.9688216.8104985.7841215.95341025.415216.82261055.137215.8829 1084.86217.2418
1134.398 217.3361154.214216.32691183.937217.72951273.121217.78951431.674220.8021
1649.684220.11891788.418221.22821847.876222.46471956.881  228.112055.977230.3252
#Mann= 3 , 0 , 0
       0      .1       0965.9688     .05       01025.415      .1       0
Bank Sta=965.9688,1025.415
XS Rating Curve= 0 ,0
Exp/Cntr=0.3,0.1
Stream Node=UNT076 IN ROCK  ,Reach-1         , 0 , 0 ,Upstream end
Stream Node=UNT076 IN ROCK  ,Reach-1         , 0 , 1 ,Downstream end

Chan Stop Cuts=-1
Use User Specified Reach Order=0
Composite Channel Slope=5