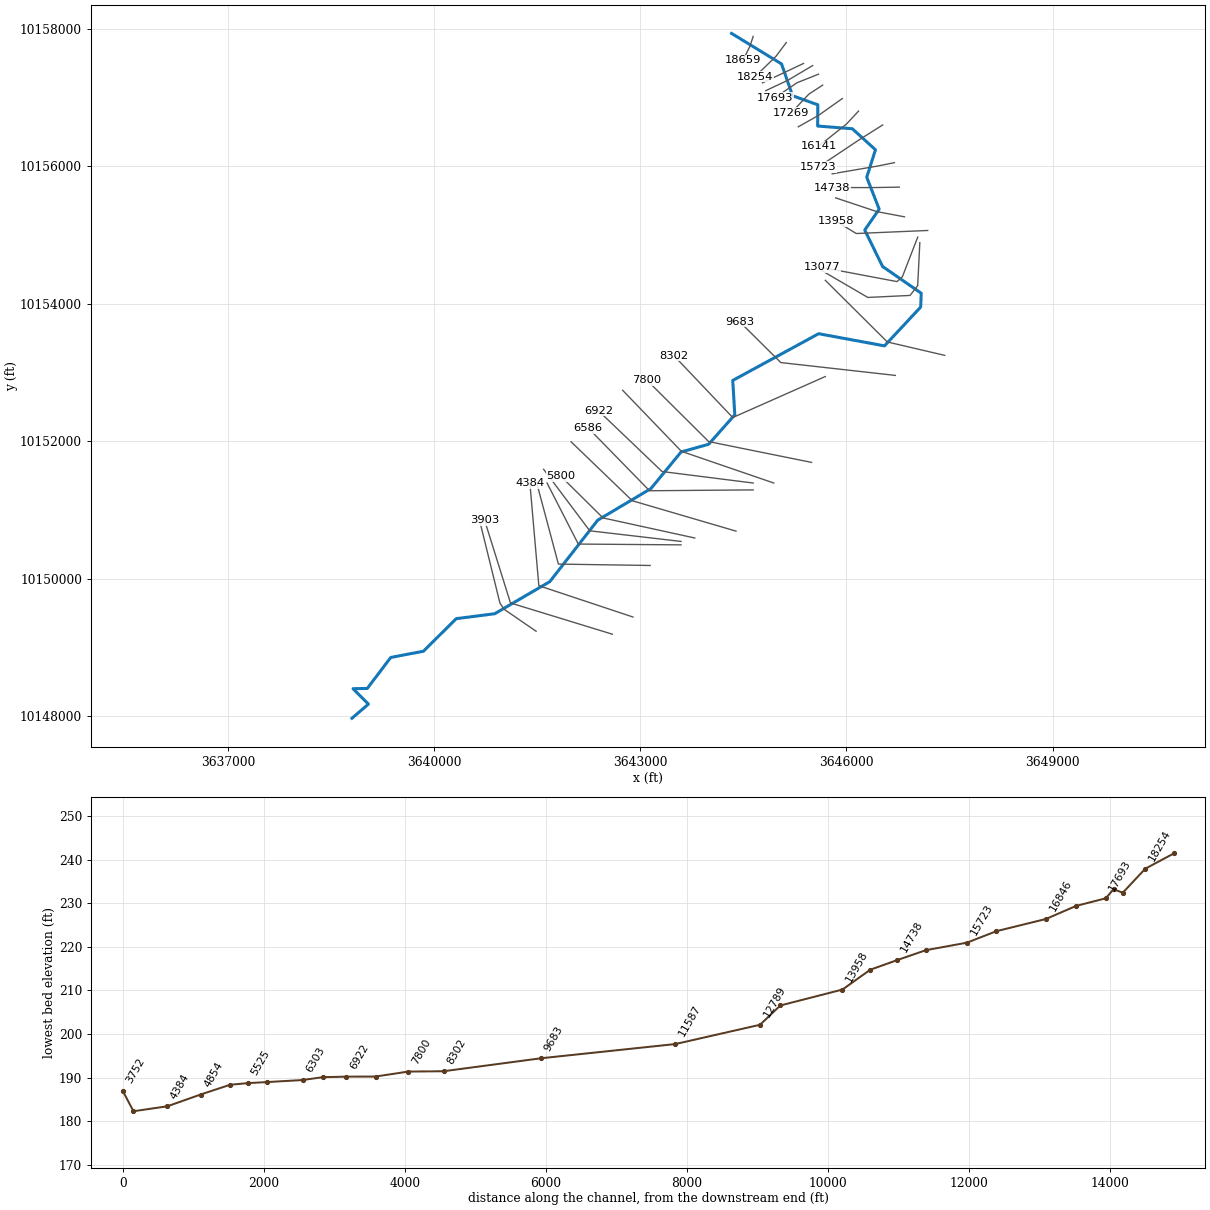
--- UNT077 IN ROCK.prj (project) ---

Proj Title=UNT077 IN ROCK Base Level Engineering
Current Plan=p01
Default Exp/Contr=0.3,0.1
English Units
Geom File=g01
Flow File=f01
Plan File=p01
Y Axis Title=Elevation
X Axis Title(PF)=Main Channel Distance
X Axis Title(XS)=Station
BEGIN DESCRIPTION:
UNT077 IN ROCK
END DESCRIPTION:
DSS Export Rating Curves= 0
DSS Export Rating Curve Sorted= 0
DSS Export Volume Flow Curves= 0
DXF OffsetX= 0
DXF OffsetY= 0
DXF ScaleX= 1
DXF ScaleY= 10

--- UNT077 IN ROCK.p01 (plan) ---

Plan Title=Multiple Run
Short Identifier=Multiple
Geom File=g01
Flow File=f01
Subcritical Flow
K Sum by GR= 0
Std Step Tol= 0.01
Critical Tol= 0.01
Num of Std Step Trials= 20
Max Error Tol= 0.3
Flow Tol Ratio= 0.001
Split Flow NTrial= 30
Split Flow Tol= 0.02
Split Flow Ratio= 0.02
Log Output Level= 0
Friction Slope Method= 1
Unsteady Friction Slope Method= 2
Unsteady Bridges Friction Slope Method= 1
Parabolic Critical Depth
Global Vel Dist=  1 , 1 , 1
Global Log Level= 0
CheckData=True
Encroach Param= -1, 0, 0, 0
BEGIN DESCRIPTION:
Multiple Run
END DESCRIPTION:

--- UNT077 IN ROCK.f01 (steady flow) ---

Flow Title=Multiple
Number of Profiles=7
Profile Names=10-year,25-year,50-year,1pct_min,100-year,1pct_plu,500-year
River Rch & RM= UNT077 IN ROCK,Reach-1,18659
     370     484     574     501     678     917     945
River Rch & RM= UNT077 IN ROCK,Reach-1,11587
     725     982    1192    1060    1433    1938    2075
Boundary for River Rch & Prof#=UNT077 IN ROCK,Reach-1,1
Up Type=0
Dn Type=3
Dn Slope=0.005
Boundary for River Rch & Prof#=UNT077 IN ROCK,Reach-1,2
Up Type=0
Dn Type=3
Dn Slope=0.005
Boundary for River Rch & Prof#=UNT077 IN ROCK,Reach-1,3
Up Type=0
Dn Type=3
Dn Slope=0.005
Boundary for River Rch & Prof#=UNT077 IN ROCK,Reach-1,4
Up Type=0
Dn Type=3
Dn Slope=0.005
Boundary for River Rch & Prof#=UNT077 IN ROCK,Reach-1,5
Up Type=0
Dn Type=3
Dn Slope=0.005
Boundary for River Rch & Prof#=UNT077 IN ROCK,Reach-1,6
Up Type=0
Dn Type=3
Dn Slope=0.005
Boundary for River Rch & Prof#=UNT077 IN ROCK,Reach-1,7
Up Type=0
Dn Type=3
Dn Slope=0.005

--- UNT077 IN ROCK.g01 (geometry) ---

Geom Title=Existing Conditions
Program Version=4.10

River Reach=UNT077 IN ROCK  ,Reach-1
Reach XY= 30
      3644327.89     10157934.74      3645055.03     10157490.87
      3645215.24     10157027.89      3645582.48     10156896.27
      3645580.74     10156587.19      3646085.26     10156547.56
      3646421.82     10156241.54      3646294.56     10155841.67
      3646475.93     10155377.71      3646265.99     10155073.18
        3646525.     10154543.56      3647087.55     10154153.86
      3647079.86      10153952.6      3646553.16     10153388.04
      3645594.61      10153564.7      3644344.56     10152884.61
      3644374.58     10152384.66      3643993.69     10151955.65
      3643593.09     10151843.76      3643153.74     10151310.79
      3642380.07     10150851.51      3641681.87     10149956.11
      3640880.07     10149489.14      3640320.18     10149417.53
      3639842.75     10148943.35      3639367.49     10148853.29
      3639025.69      10148401.9      3638818.44     10148398.65
      3639041.97     10148174.04      3638802.81     10147967.95

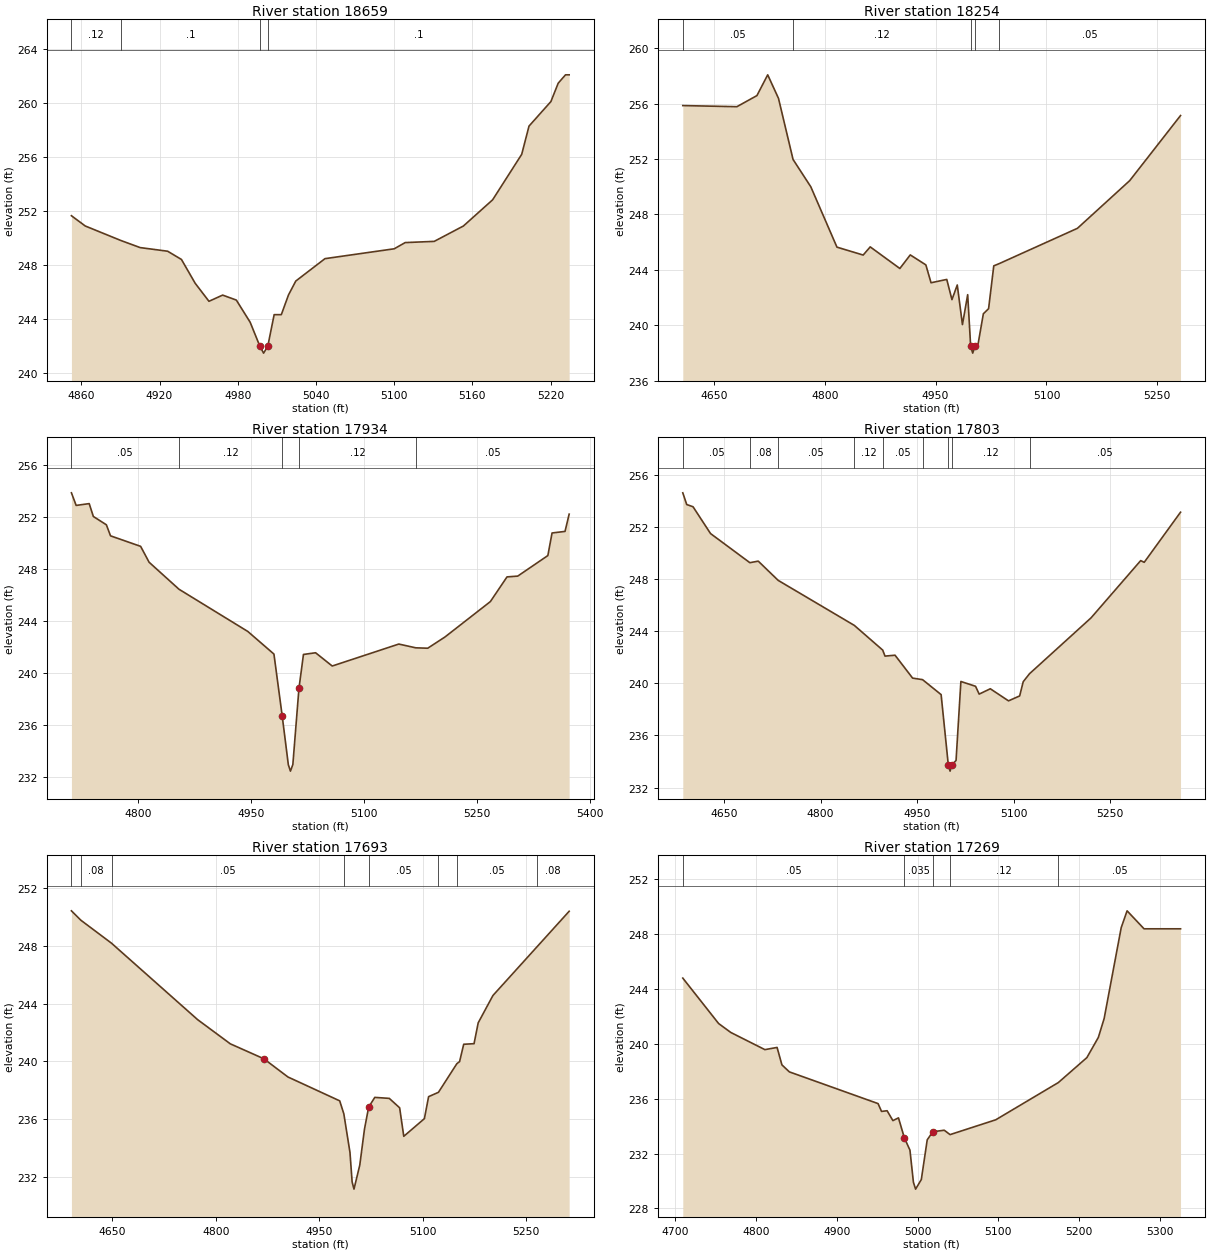
Type RM Length L Ch R = 1 ,18659   ,405,405,405
BEGIN DESCRIPTION:
UNT077 IN ROCK 26.0
END DESCRIPTION:
XS GIS Cut Line= 3
      3644642.12     10157891.68      3644592.11     10157741.64
      3644492.09     10157541.61
#Sta/Elev= 30
  4852.4  251.67    4863  250.91  4890.2  249.84  4905.1  249.31  4926.2  249.04
  4936.8  248.43  4947.3  246.67  4957.9  245.33  4968.4  245.79  4978.9  245.42
  4989.5  243.78    4997  241.99  4999.8  241.49    5003  241.99  5007.9  244.34
  5013.4  244.34  5018.9   245.8  5024.5  246.83  5046.9  248.49    5100  249.22
  5108.4  249.68  5130.7  249.77  5153.1  250.91  5175.5  252.85  5197.8  256.22
  5203.4  258.31  5220.2  260.13  5225.8  261.49  5231.4  262.11  5234.2  262.11
#Mann= 4 ,-1 , 0
  4852.4     .12       0  4890.2      .1       0    4997     .07       0
    5003      .1       0
Bank Sta=4997,5003
XS Rating Curve= 0 ,0
Exp/Cntr=0.3,0.1

Type RM Length L Ch R = 1 ,18254   ,320,320,320
BEGIN DESCRIPTION:
UNT077 IN ROCK 25.0
END DESCRIPTION:
XS GIS Cut Line= 3
      3645123.67     10157801.72      3644973.69     10157601.75
      3644669.98     10157306.55
#Sta/Elev= 30
  4607.9  255.85  4681.1  255.77  4708.2  256.57  4722.8  258.07  4737.4  256.37
  4757.1  251.96  4781.1  249.99  4816.5  245.63    4852  245.06  4861.5  245.65
  4901.6  244.09  4915.7  245.07  4936.8  244.35  4943.8  243.06  4965.1   243.3
  4972.1  241.84  4979.3   242.9  4986.3  240.04  4993.4   242.2  4997.4  238.48
  5000.2  237.98  5003.4  238.48  5007.6  238.68  5014.6  240.82  5021.7  241.19
  5028.7  244.28    5036  244.44  5141.9  246.99  5212.6  250.43  5281.4  255.13
#Mann= 5 ,-1 , 0
  4607.9     .05       0  4757.1     .12       0  4997.4     .07       0
  5003.4     .12       0    5036     .05       0
Bank Sta=4997.4,5003.4
XS Rating Curve= 0 ,0
Exp/Cntr=0.3,0.1

Type RM Length L Ch R = 1 ,17934   ,131,131,131
BEGIN DESCRIPTION:
Mapping XS 999b0da2
END DESCRIPTION:
XS GIS Cut Line= 2
      3645375.39     10157498.12      3644777.49      10157216.5
#Sta/Elev= 30
  4711.3  253.88  4717.6  252.91  4734.9  253.05  4740.4  252.06  4757.7  251.42
  4763.2  250.57  4803.2  249.76  4814.4  248.54  4854.1  246.46  4945.5  243.21
  4980.2  241.47  4991.1  236.74  4999.3  232.96  5002.1  232.46  5005.3  232.96
  5013.4  238.82  5019.4  241.44  5035.5  241.57  5057.6  240.55    5146  242.24
  5168.6  241.95  5184.4  241.92  5207.2  242.78  5267.6  245.51  5289.7  247.41
  5303.9  247.47  5343.9  249.05  5349.5  250.79  5366.7  250.91  5372.2  252.24
#Mann= 5 ,-1 , 0
  4711.3     .05       0  4854.1     .12       0  4991.1     .07       0
  5013.4     .12       0  5168.6     .05       0
Bank Sta=4991.1,5013.4
XS Rating Curve= 0 ,0
Exp/Cntr=0.3,0.1

Type RM Length L Ch R = 1 ,17803   ,110,110,110
BEGIN DESCRIPTION:
UNT077 IN ROCK 24.0
END DESCRIPTION:
XS GIS Cut Line= 3
      3645507.34     10157466.75      3645146.69     10157253.05
      3644826.27     10157102.57
#Sta/Elev= 30
  4585.9  254.65    4592  253.75  4601.8  253.58    4629  251.52  4690.1  249.28
  4703.1   249.4  4734.1  247.92  4852.4  244.46  4896.5  242.56    4900   242.1
  4915.6  242.17  4942.9  240.41  4958.4  240.29  4987.2  239.14  4998.3  233.76
  5001.1  233.26  5004.3  233.76  5010.4  234.08  5017.9  240.15  5040.7  239.78
  5046.3  239.18  5063.6  239.59  5091.9  238.66  5109.2  239.04  5114.7  240.13
  5124.6  240.75  5220.1  245.04  5297.2  249.44  5302.7  249.31  5359.1  253.16
#Mann= 9 ,-1 , 0
  4585.9     .05       0  4690.1     .08       0  4734.1     .05       0
  4852.4     .12       0  4896.5     .05       0  4958.4     .12       0
  4998.3     .07       0  5004.3     .12       0  5124.6     .05       0
Bank Sta=4998.3,5004.3
XS Rating Curve= 0 ,0
Exp/Cntr=0.3,0.1

Type RM Length L Ch R = 1 ,17693   ,424,424,424
BEGIN DESCRIPTION:
UNT077 IN ROCK 23.0
END DESCRIPTION:
XS GIS Cut Line= 3
      3645592.08     10157341.63      3645281.24     10157217.61
      3644960.54     10157000.95
#Sta/Elev= 30
  4590.8  250.41  4604.5  249.76    4649  248.17  4773.8  242.89  4821.2  241.22
  4869.7  240.19  4904.7  238.93  4979.8  237.28  4985.8  236.38  4994.7  233.71
  4997.8  231.68  5000.5  231.18  5008.9  232.84  5015.7  235.32  5021.8  236.85
  5030.7  237.52  5051.7  237.45  5066.7   236.8  5072.7  234.83  5102.6  236.05
  5108.7  237.57    5123  237.87  5149.7  239.85  5153.6  239.99  5159.6  241.19
  5174.6  241.23  5180.6  242.67    5202  244.56  5265.8  247.92  5312.5  250.38
#Mann= 8 ,-1 , 0
  4590.8     .05       0  4604.5     .08       0    4649     .05       0
  4985.8    .035       0  5021.8     .05       0    5123     .12       0
  5149.7     .05       0  5265.8     .08       0
Bank Sta=4869.7,5021.8
XS Rating Curve= 0 ,0
Exp/Cntr=0.3,0.1

Type RM Length L Ch R = 1 ,17269   ,423,423,423
BEGIN DESCRIPTION:
Mapping XS 803daaf5
END DESCRIPTION:
XS GIS Cut Line= 3
      3645652.64     10157181.99      3645452.97     10157051.77
      3645192.57     10156777.48
#Sta/Elev= 30
  4709.2  244.78  4753.6  241.47  4768.7  240.82  4810.9  239.57    4826  239.73
    4832  238.46  4841.2  237.95  4951.1  235.64  4955.4  235.07  4962.3  235.12
  4969.5   234.4  4976.4   234.6  4983.7  233.14  4990.6  232.25  4994.9  229.91
  4997.6  229.41  5004.7  230.11    5012     233  5018.9  233.59  5033.1   233.7
  5040.3  233.38  5096.9  234.46  5174.4  237.17  5209.8  238.99    5224  240.46
  5231.2  241.84  5252.3  248.45  5259.6  249.68  5280.6  248.37  5325.8  248.37
#Mann= 5 ,-1 , 0
  4709.2     .05       0  4983.7    .035       0  5018.9     .05       0
  5040.3     .12       0  5174.4     .05       0
Bank Sta=4983.7,5018.9
XS Rating Curve= 0 ,0
Exp/Cntr=0.3,0.1

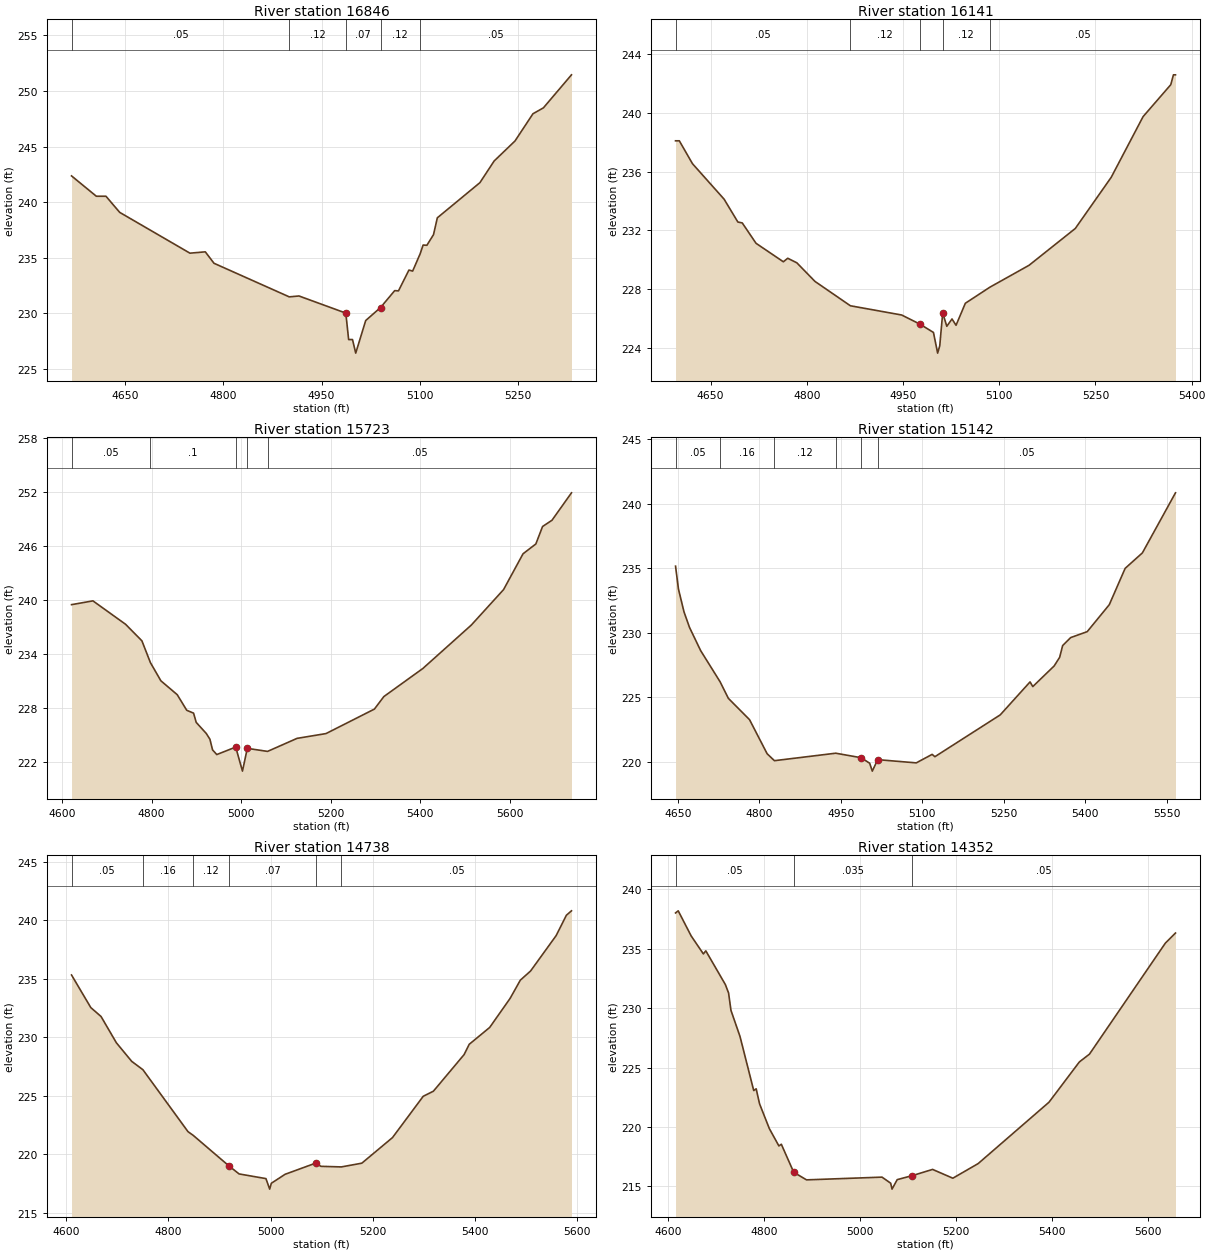
Type RM Length L Ch R = 1 ,16846   ,705,705,705
BEGIN DESCRIPTION:
UNT077 IN ROCK 22.0
END DESCRIPTION:
XS GIS Cut Line= 3
       3645939.4     10156987.41      3645592.11     10156741.64
      3645298.97     10156576.12
#Sta/Elev= 30
  4568.9  242.37  4606.7  240.54  4621.4  240.54  4642.3  239.09  4749.4  235.42
  4772.8  235.54  4786.1  234.51  4900.8  231.49  4915.6  231.57    4987  230.03
  4991.3  227.65  4997.2  227.65  5002.1  226.43  5017.3  229.36  5039.9  230.53
  5061.5  232.05  5067.3  232.03  5083.2   233.9  5088.9  233.81  5100.3  235.36
  5104.8  236.15  5110.6  236.13  5120.7  237.09  5126.5   238.6  5191.4  241.76
  5213.1  243.71  5244.9  245.51  5272.3  247.96  5288.2  248.49    5331  251.46
#Mann= 5 ,-1 , 0
  4568.9     .05       0  4900.8     .12       0    4987     .07       0
  5039.9     .12       0  5100.3     .05       0
Bank Sta=4987,5039.9
XS Rating Curve= 0 ,0
Exp/Cntr=0.3,0.1

Type RM Length L Ch R = 1 ,16141   ,418,418,418
BEGIN DESCRIPTION:
UNT077 IN ROCK 21.0
END DESCRIPTION:
XS GIS Cut Line= 3
      3646175.75     10156805.18      3645999.28     10156615.38
      3645592.07     10156291.62
#Sta/Elev= 30
  4595.4   238.1  4601.3   238.1  4621.8  236.54  4671.1  234.12  4692.6  232.56
  4699.4   232.5  4720.9  231.11  4763.5  229.85  4770.3  230.09  4784.5  229.78
  4812.8  228.51    4868  226.85  4947.9  226.22  4976.7  225.59  4997.5  225.03
    5004  223.62  5007.3  224.12  5011.9  226.36  5018.3  225.45  5026.4  225.95
  5032.7  225.52  5047.2  227.02  5085.2  228.11  5146.5  229.61  5218.6  232.12
  5274.6  235.61  5324.3  239.75  5367.5  241.93  5371.6   242.6  5374.8   242.6
#Mann= 5 ,-1 , 0
  4595.4     .05       0    4868     .12       0  4976.7     .07       0
  5011.9     .12       0  5085.2     .05       0
Bank Sta=4976.7,5011.9
XS Rating Curve= 0 ,0
Exp/Cntr=0.3,0.1

Type RM Length L Ch R = 1 ,15723   ,581,581,581
BEGIN DESCRIPTION:
UNT077 IN ROCK 20.0
END DESCRIPTION:
XS GIS Cut Line= 3
      3646526.75      10156602.6      3646192.11     10156391.64
       3645592.1     10155991.64
#Sta/Elev= 30
  4621.1  239.47  4668.9  239.89  4741.8  237.29  4778.3  235.45  4797.3  233.03
  4820.7  231.01  4857.2  229.47  4878.4  227.74  4893.7  227.42  4899.6  226.39
  4922.1  225.16  4930.2  224.52  4936.1  223.34  4945.5  222.82  4987.8  223.65
  5002.9  220.98  5013.7  223.51  5058.9  223.17  5124.9  224.62  5189.5  225.15
  5297.6  227.87  5318.7  229.26  5405.8  232.38    5514   237.2  5586.1  241.14
  5629.6  245.12  5658.2  246.21  5673.2  248.15  5694.2  248.84  5737.8  251.89
#Mann= 5 ,-1 , 0
  4621.1     .05       0  4797.3      .1       0  4987.8     .07       0
  5013.7      .1       0  5058.9     .05       0
Bank Sta=4987.8,5013.7
XS Rating Curve= 0 ,0
Exp/Cntr=0.3,0.1

Type RM Length L Ch R = 1 ,15142   ,404,404,404
BEGIN DESCRIPTION:
UNT077 IN ROCK 19.0
END DESCRIPTION:
XS GIS Cut Line= 3
      3646697.36       10156054.      3646447.37     10156004.01
      3645792.08     10155891.64
#Sta/Elev= 30
  4645.9  235.16  4651.3  233.38  4661.5  231.61  4671.7   230.4  4692.1  228.61
  4727.9  226.19    4743  224.91  4782.1  223.25  4814.4  220.61  4827.8  220.07
  4940.7  220.65  4987.4   220.3  5003.1  219.87  5007.9  219.26  5017.8  220.15
  5088.8   219.9    5118  220.56  5123.1  220.38  5243.2  223.62  5298.1  226.18
  5303.2  225.82  5342.5  227.42  5352.6  228.09  5358.1     229  5372.9  229.62
  5403.3  230.08  5443.9  232.17  5473.1  234.99  5504.8  236.19  5565.7  240.85
#Mann= 6 ,-1 , 0
  4645.9     .05       0  4727.9     .16       0  4827.8     .12       0
  4940.7     .05       0  4987.4    .035       0  5017.8     .05       0
Bank Sta=4987.4,5017.8
XS Rating Curve= 0 ,0
Exp/Cntr=0.3,0.1

Type RM Length L Ch R = 1 ,14738   ,386,386,386
BEGIN DESCRIPTION:
UNT077 IN ROCK 18.0
END DESCRIPTION:
XS GIS Cut Line= 3
       3646769.8     10155697.96      3646392.11     10155691.64
      3645792.15     10155691.64
#Sta/Elev= 30
  4610.8  235.32  4648.5  232.53  4668.5  231.77  4698.5  229.52  4728.5  227.93
  4750.3  227.22  4838.5  221.92    4849  221.59  4918.5  218.99  4938.5   218.3
    4991   217.9  4998.3     217  5001.5   217.5  5028.5  218.27  5088.5  219.23
  5098.5  218.95  5138.5   218.9  5178.5  219.22  5238.5  221.41  5298.5  224.94
  5318.5  225.38  5378.5  228.51  5388.5  229.39  5428.5  230.83  5468.5  233.32
  5488.5  234.88  5508.5  235.66  5558.5  238.69  5578.5  240.43  5588.5  240.81
#Mann= 6 ,-1 , 0
  4610.8     .05       0  4750.3     .16       0    4849     .12       0
  4918.5     .07       0  5088.5     .12       0  5138.5     .05       0
Bank Sta=4918.5,5088.5
XS Rating Curve= 0 ,0
Exp/Cntr=0.3,0.1

Type RM Length L Ch R = 1 ,14352   ,394,394,394
BEGIN DESCRIPTION:
UNT077 IN ROCK 17.0
END DESCRIPTION:
XS GIS Cut Line= 3
      3646844.08     10155265.89      3646442.11     10155341.64
      3645842.11     10155541.64
#Sta/Elev= 30
  4615.1  238.02  4620.7   238.2  4647.6  236.09  4673.1  234.57  4678.2  234.83
  4718.9  231.99  4725.6  231.28  4730.6  229.81  4749.4  227.62    4778  223.06
  4783.1  223.21  4790.1  221.95  4810.5  219.86  4830.4   218.4  4835.5  218.54
  4861.3  216.18    4888  215.54  5045.2  215.77  5063.3  215.26  5066.1  214.76
  5076.9  215.56  5108.5   215.9  5150.6  216.42  5192.8  215.68  5245.5  216.91
  5393.1  222.08  5456.3  225.47  5477.4  226.13  5635.5  235.48  5656.6  236.33
#Mann= 3 , 0 , 0
  4615.1     .05       0  4861.3    .035       0  5108.5     .05       0
Bank Sta=4861.3,5108.5
XS Rating Curve= 0 ,0
Exp/Cntr=0.3,0.1

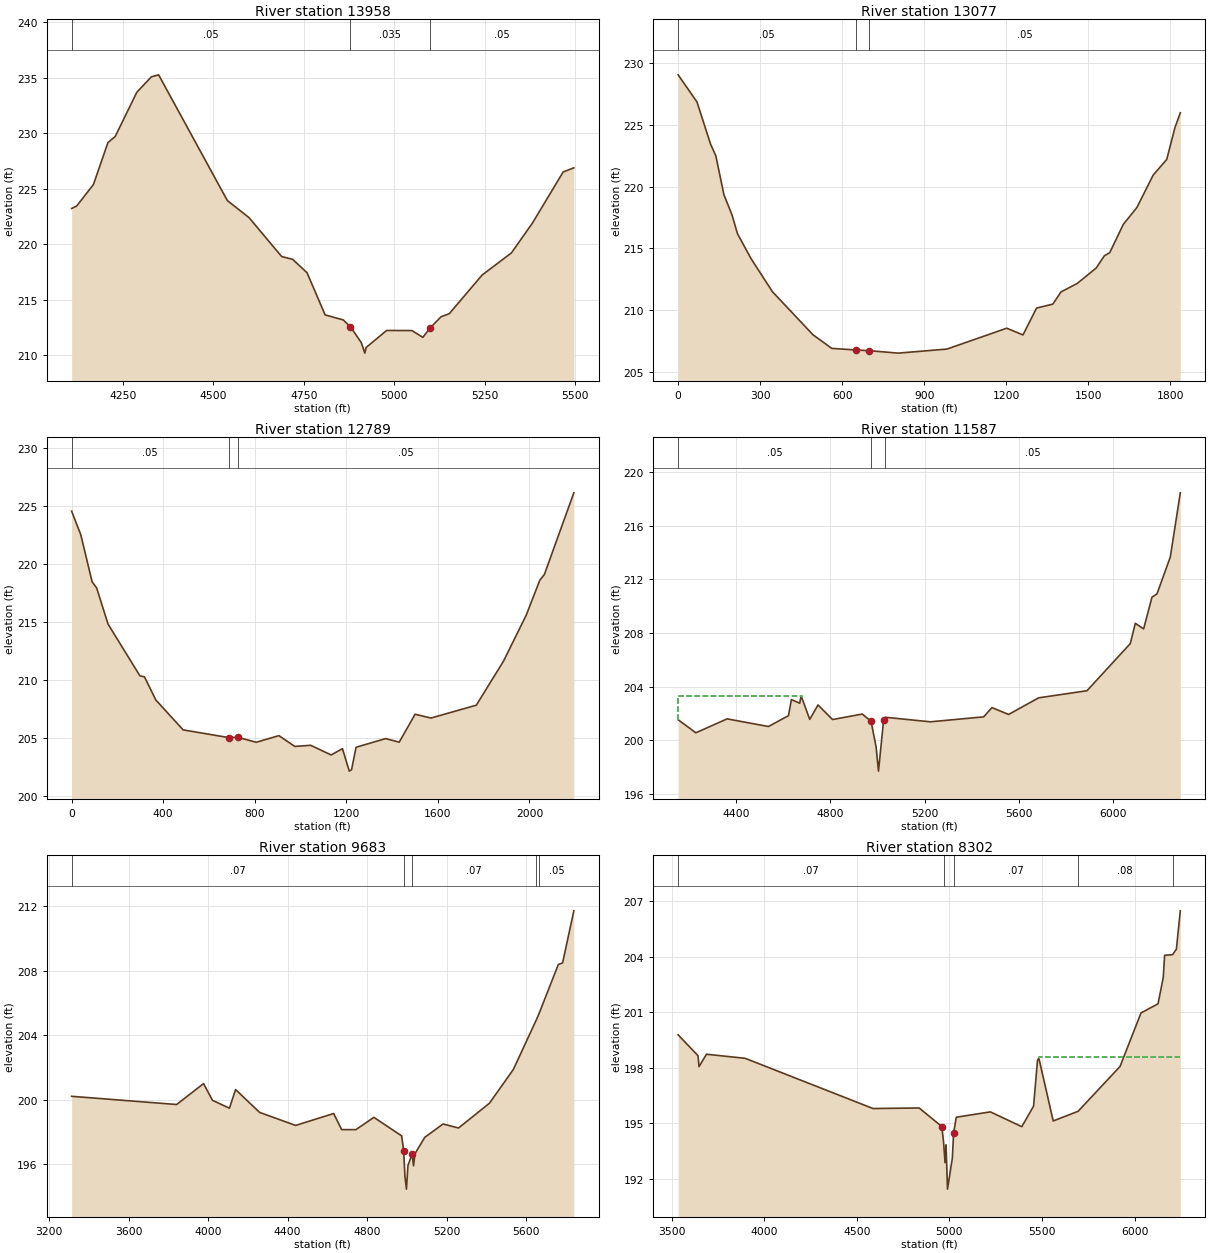
Type RM Length L Ch R = 1 ,13958   ,881,881,881
BEGIN DESCRIPTION:
UNT077 IN ROCK 16.0
END DESCRIPTION:
XS GIS Cut Line= 3
      3647182.36     10155067.17      3646141.97     10155022.85
      3645845.99     10155204.47
#Sta/Elev= 30
  4107.8  223.23  4121.7  223.45  4168.1  225.39  4208.1  229.16  4228.2  229.71
  4288.2   233.7  4328.3  235.08  4348.3  235.26  4538.4  223.94  4598.5   222.4
  4688.6   218.9  4718.6  218.66  4758.6  217.45  4808.7  213.65  4858.7   213.2
  4878.8  212.58  4908.8  211.15  4918.5  210.21  4921.8  210.71  4978.8  212.25
  5048.9  212.24  5078.9  211.63    5099  212.47    5129  213.48    5152  213.76
  5242.8  217.24  5323.8  219.23  5381.8  221.91    5467  226.52  5496.4  226.89
#Mann= 3 , 0 , 0
  4107.8     .05       0  4878.8    .035       0    5099     .05       0
Bank Sta=4878.8,5099
XS Rating Curve= 0 ,0
Exp/Cntr=0.3,0.1

Type RM Length L Ch R = 1 ,13077   ,288,288,288
XS GIS Cut Line= 4
     3647037.055    10154970.927     3646813.097    10154392.629
     3646734.972    10154323.184     3645644.694    10154529.348
#Sta/Elev= 30
       0229.016969.00517226.8267118.2946223.4465138.0103 222.476 167.584219.3314
197.1576217.7095216.8734 216.204266.1628214.1976345.0259211.5093492.8941  208.04
561.8993 206.936649.5541206.8078697.0668206.7525804.9227206.5529983.4567206.8814
1201.665208.56531261.176208.02231310.769210.1899 1370.28210.50871400.036211.4903
1459.547212.17841528.977213.42271558.733214.4106 1578.57214.66661628.163216.9502
1677.755218.30781737.267220.92381786.859222.18841816.615224.74131836.452225.9529
#Mann= 3 , 0 , 0
       0     .05       0649.5541    .035       0697.0668     .05       0
Bank Sta=649.5541,697.0668
XS Rating Curve= 0 ,0
Exp/Cntr=0.3,0.1

Type RM Length L Ch R = 1 ,12789   ,1202,1202,1202
XS GIS Cut Line= 5
     3647067.472    10154889.179     3647036.222    10154264.179
     3646925.111    10154121.818     3646310.937    10154092.431
     3645643.716     10154481.41
#Sta/Elev= 30
       0224.569439.76514222.548589.47157218.4713109.3541217.9337159.0606214.8182
298.2386210.3506318.1211210.2632367.8275208.2632 487.123205.6817686.2792205.0166
726.2648 205.042806.2358204.6117905.3979205.1846974.8115204.25511044.225204.3513
1133.471203.51761183.052204.05841212.801202.11971222.717202.23711242.549204.1808
 1371.46204.92871430.948 204.6211500.301207.03091569.654206.70531767.806207.8156
1886.696211.62091985.772215.58732045.217218.60922065.032219.09842193.831226.1564
#Mann= 3 , 0 , 0
       0     .05       0686.2792    .035       0726.2648     .05       0
#Block Obstruct= 2 , 0
                          735.97          204.83
Bank Sta=686.2792,726.2648
XS Rating Curve= 0 ,0
Exp/Cntr=0.3,0.1

Type RM Length L Ch R = 1 ,11587   ,1904,1904,1904
BEGIN DESCRIPTION:
UNT077 IN ROCK 15.0
END DESCRIPTION:
XS GIS Cut Line= 3
      3647430.08     10153249.47      3646594.56     10153444.61
      3645692.14     10154341.61
#Sta/Elev= 30
  4153.9  201.53  4229.1  200.55  4361.8  201.59  4537.1  201.02  4622.1  201.83
  4634.5  203.03  4669.8  202.76  4675.6  203.32  4712.3  201.55  4747.4  202.63
    4809  201.54  4935.2  201.95  4972.5  201.41  4993.9  199.48  5003.9  197.69
  5025.7   201.5  5032.7  201.71  5223.7  201.37    5450  201.74  5485.3  202.43
    5556  201.92  5683.3  203.16  5888.4  203.69  6072.2  207.21  6093.4  208.72
  6128.8  208.31  6164.1  210.67  6185.4  210.92  6241.9  213.67  6284.3  218.46
#Mann= 3 ,-1 , 0
  4153.9     .05       0  4972.5    .035       0  5032.7     .05       0
#XS Ineff= 2 , 0
         4678.98  203.29
Permanent Ineff=
       F       F
Bank Sta=4972.5,5025.7
XS Rating Curve= 0 ,0
Exp/Cntr=0.3,0.1

Type RM Length L Ch R = 1 ,9683    ,1381,1381,1381
BEGIN DESCRIPTION:
UNT077 IN ROCK 14.0
END DESCRIPTION:
XS GIS Cut Line= 3
      3646711.42     10152957.79      3645044.56     10153144.61
      3644442.08     10153741.67
#Sta/Elev= 30
  3314.1   200.2  3842.1  199.69  3977.5  200.99  4022.4  199.95  4107.6  199.46
  4138.5  200.62  4259.3   199.2  4440.4  198.39  4631.6  199.13  4671.9  198.13
  4743.8  198.13    4834  198.89  4973.7  197.74  4983.8  196.82  4990.1  195.23
  4997.8  194.43  5005.2  195.89  5026.4  196.62  5033.5  195.88  5040.5  196.63
    5090  197.65  5181.9  198.48  5259.8  198.23  5415.3  199.77  5535.5  201.87
  5650.6  204.94  5664.9  205.35  5761.8   208.4    5783  208.49  5839.6  211.73
#Mann= 5 ,-1 , 0
  3314.1     .07       0  4983.8     .05       0  5026.4     .07       0
  5650.6      .1       0  5664.9     .05       0
Bank Sta=4983.8,5026.4
XS Rating Curve= 0 ,0
Exp/Cntr=0.3,0.1

Type RM Length L Ch R = 1 ,8302    ,502,502,502
BEGIN DESCRIPTION:
UNT077 IN ROCK 13.0
END DESCRIPTION:
XS GIS Cut Line= 3
      3645692.07     10152941.62      3644344.56     10152344.61
      3643492.11     10153241.63
#Sta/Elev= 30
  3535.3  199.78  3642.8  198.65  3648.2  198.06  3688.4  198.73  3897.4  198.51
  4587.6   195.8  4836.8  195.83  4958.7  194.83  4968.1  194.04  4976.5  192.88
    4982  193.84  4989.7  191.45  5015.9  193.13  5022.8  194.49    5037  195.33
    5221  195.62  5390.9  194.82  5454.4  195.93  5475.5  198.39  5482.7  198.53
  5560.4  195.13  5694.8  195.65  5921.2  198.07  6034.5  200.96  6126.3  201.45
  6154.6  202.87  6161.9  204.07  6204.5   204.1  6225.4   204.4  6246.6  206.47
#Mann= 5 ,-1 , 0
  3535.3     .07       0  4968.1    .035       0  5022.8     .07       0
  5694.8     .08       0  6204.5     .05       0
#XS Ineff= 2 , 0
                         5484.09          198.58
Permanent Ineff=
       F       F
Bank Sta=4958.7,5022.8
XS Rating Curve= 0 ,0
Exp/Cntr=0.3,0.1

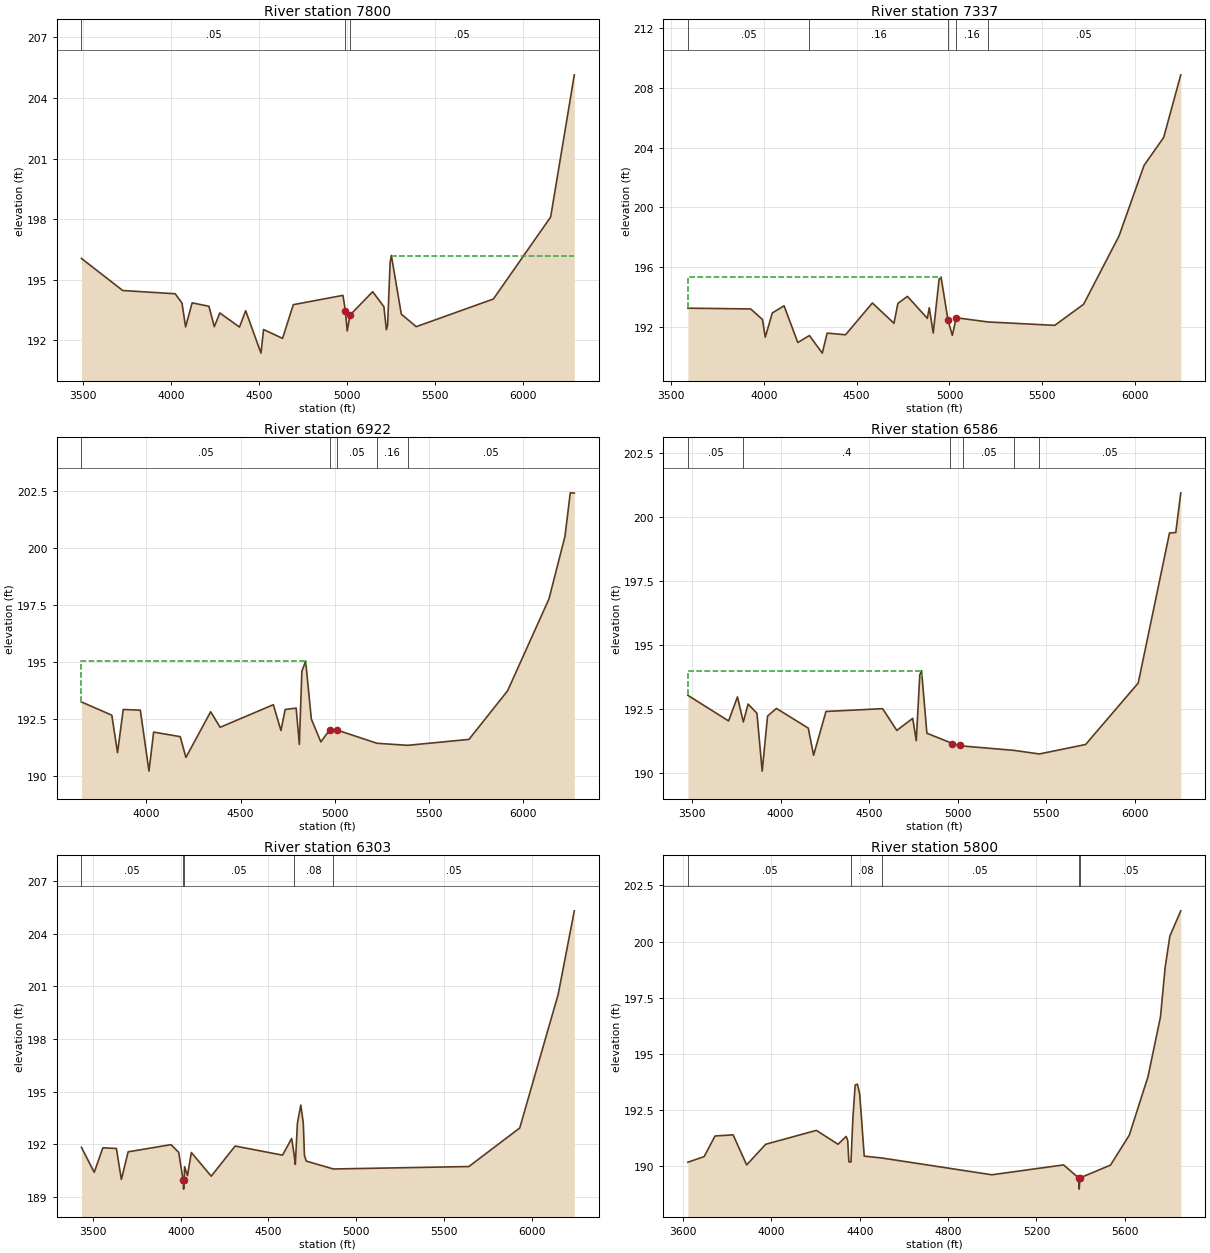
Type RM Length L Ch R = 1 ,7800    ,463,463,463
BEGIN DESCRIPTION:
UNT077 IN ROCK 12.0
END DESCRIPTION:
XS GIS Cut Line= 3
      3645492.15     10151691.63      3643994.56     10151994.61
      3643092.08     10152891.67
#Sta/Elev= 30
  3491.8  196.06  3726.5  194.47  4024.4  194.31  4063.2  193.85  4083.6  192.67
  4120.8  193.86  4216.2  193.69  4246.8  192.68    4278  193.36  4389.7  192.66
  4425.1  193.47  4511.9  191.37  4526.5  192.54  4634.5   192.1  4695.7  193.77
  4977.9  194.23  4991.6  193.45  5001.8  192.47  5018.4  193.26  5146.7  194.41
  5210.3  193.67  5224.4  192.53  5231.5  192.76  5245.6  195.85  5252.7  196.21
  5309.3   193.3  5394.1  192.68  5832.5  194.05  6157.8  198.11  6292.2  205.15
#Mann= 3 , 0 , 0
  3491.8     .05       0  4991.6    .035       0  5018.4     .05       0
#XS Ineff= 2 , 0
                         5253.12          196.19
Permanent Ineff=
       F       F
Bank Sta=4991.6,5018.4
XS Rating Curve= 0 ,0
Exp/Cntr=0.3,0.1

Type RM Length L Ch R = 1 ,7337    ,415,415,415
BEGIN DESCRIPTION:
UNT077 IN ROCK 11.0
END DESCRIPTION:
XS GIS Cut Line= 3
      3644942.07     10151391.66      3643597.27       10151853.
      3642742.12     10152741.63
#Sta/Elev= 30
  3591.1  193.24  3929.4  193.19  3992.8  192.48  4007.9   191.3  4045.7  192.92
  4109.1   193.4  4183.1  190.94  4245.7  191.41    4315  190.23  4341.2  191.57
  4440.3  191.46  4584.8  193.59  4701.1  192.23  4722.3  193.56  4773.7  194.03
  4880.9  192.56  4891.4  193.27  4912.6  191.58  4944.3  195.18  4954.9  195.32
  4992.5  192.42  5015.5  191.42  5036.8   192.6  5206.4  192.32  5567.1  192.09
  5722.7   193.5  5913.6  198.08  6048.2   202.8  6154.1  204.68  6246.1  208.87
#Mann= 5 ,-1 , 0
  3591.1     .05       0  4245.7     .16       0  4992.5    .035       0
  5036.8     .16       0  5206.4     .05       0
#XS Ineff= 2 , 0
         4955.68  195.36
Permanent Ineff=
       F       F
Bank Sta=4992.5,5036.8
XS Rating Curve= 0 ,0
Exp/Cntr=0.3,0.1

Type RM Length L Ch R = 1 ,6922    ,336,336,336
BEGIN DESCRIPTION:
UNT077 IN ROCK 10.0
END DESCRIPTION:
XS GIS Cut Line= 3
      3644642.08     10151391.65      3643315.84     10151559.02
      3642392.09     10152441.66
#Sta/Elev= 30
  3655.4  193.24  3816.6  192.66  3846.9  191.02  3877.1  192.91  3967.8  192.88
  4013.7  190.21  4038.4  191.92  4179.5  191.72  4209.7  190.81  4340.8  192.81
  4391.2  192.13  4673.4  193.12  4713.7  191.99  4736.2  192.91  4794.3  192.97
  4811.4  191.38  4824.6  194.58  4844.7  195.03    4875  192.49  4925.4  191.49
  4971.9  192.01    5011  192.01  5222.9  191.43  5385.5  191.34    5711   191.6
  5916.1  193.73  6135.3  197.75  6220.2  200.49  6248.5   202.4  6269.8  202.39
#Mann= 5 ,-1 , 0
  3655.4     .05       0  4971.9    .035       0    5011     .05       0
  5222.9     .16       0  5385.5     .05       0
#XS Ineff= 2 , 0
         4846.59  195.03
Permanent Ineff=
       F       F
Bank Sta=4971.9,5011
XS Rating Curve= 0 ,0
Exp/Cntr=0.3,0.1

Type RM Length L Ch R = 1 ,6586    ,283,283,283
BEGIN DESCRIPTION:
UNT077 IN ROCK 9.0
END DESCRIPTION:
XS GIS Cut Line= 3
      3644642.07     10151291.64      3643133.35     10151279.33
      3642242.08     10152191.67
#Sta/Elev= 30
    3476  193.04    3706  192.04    3756  192.98  3789.1     192    3816   192.7
    3866  192.34  3895.7  190.08    3926  192.23    3976  192.53    4156  191.76
    4186   190.7    4256  192.41    4576  192.52    4656  191.67    4746  192.14
    4766  191.27    4786  193.84    4796     194    4826  191.56    4956   191.2
    4966  191.14  5015.7   191.1  5029.8  191.06  5319.7  190.89  5461.1  190.75
  5722.7  191.12  6019.8  193.52  6196.5  199.38    6232   199.4  6260.2  200.95
#Mann= 6 ,-1 , 0
    3476     .05       0  3789.1      .4       0    4956    .035       0
  5029.8     .05       0  5319.7     .08       0  5461.1     .05       0
#XS Ineff= 2 , 0
         4799.72  194.01
Permanent Ineff=
       F       F
Bank Sta=4966,5015.7
XS Rating Curve= 0 ,0
Exp/Cntr=0.3,0.1

Type RM Length L Ch R = 1 ,6303    ,503,503,503
BEGIN DESCRIPTION:
UNT077 IN ROCK 8.0
END DESCRIPTION:
XS GIS Cut Line= 3
       3644392.1     10150691.64      3642883.35      10151133.5
      3641992.14     10151991.61
#Sta/Elev= 30
  3433.8  191.82  3506.7  190.39    3556  191.79  3633.2  191.75  3661.4  189.98
  3700.1  191.56  3944.4  191.97  3988.3  191.53  4013.5  189.93  4016.2  189.43
  4019.5  189.93  4021.7  190.71  4038.2   190.2  4060.3  191.52  4173.6  190.17
  4309.9  191.89    4580  191.37  4632.1  192.32  4646.2  191.39  4652.9  190.84
  4664.9   193.2  4684.2  194.23  4698.4   193.2    4705  191.35  4715.5  191.03
  4869.9  190.58  5642.1  190.72    5932  192.92  6151.2  200.55  6243.1  205.32
#Mann= 5 ,-1 , 0
  3433.8     .05       0  4013.5     .03       0  4019.5     .05       0
  4646.2     .08       0  4869.9     .05       0
Bank Sta=4013.5,4019.5
XS Rating Curve= 0 ,0
Exp/Cntr=0.3,0.1

Type RM Length L Ch R = 1 ,5800    ,275,275,275
BEGIN DESCRIPTION:
UNT077 IN ROCK 7.0
END DESCRIPTION:
XS GIS Cut Line= 3
      3643792.07     10150591.65      3642456.46     10150883.67
       3641842.1     10151491.65
#Sta/Elev= 30
  3622.1  190.16  3695.6  190.41  3744.9  191.33  3826.8  191.38  3888.2  190.04
  3974.2  190.96  4203.8  191.58  4301.8  190.96  4338.6  191.31  4345.7  191.13
  4350.8  190.18  4360.4  190.17  4369.3  192.16  4379.5   193.6  4389.6  193.64
    4400  193.19  4420.5  190.43  4499.2  190.35    4998   189.6  5323.2  190.04
    5391  189.46  5393.7  188.96    5397  189.46  5535.4  190.03  5620.2  191.36
  5705.1  193.97  5761.7  196.64  5782.9  198.85  5804.1  200.24  5853.6  201.37
#Mann= 5 ,-1 , 0
  3622.1     .05       0  4360.4     .08       0  4499.2     .05       0
    5391     .03       0    5397     .05       0
Bank Sta=5391,5397
XS Rating Curve= 0 ,0
Exp/Cntr=0.3,0.1

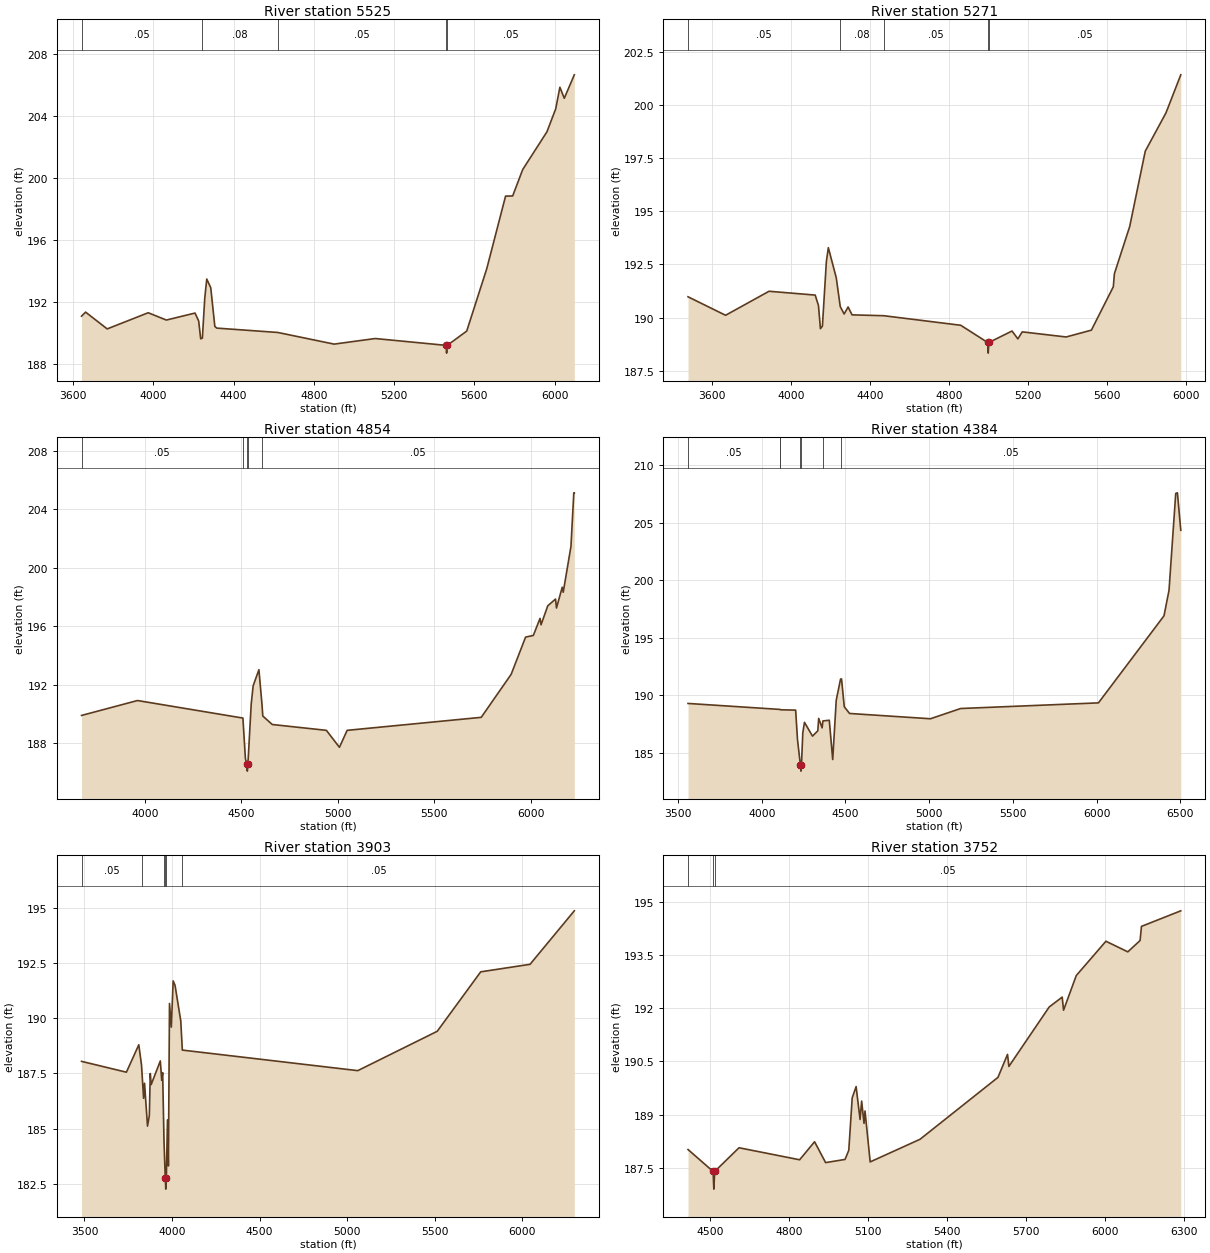
Type RM Length L Ch R = 1 ,5525    ,254,254,254
BEGIN DESCRIPTION:
UNT077 IN ROCK 6.0
END DESCRIPTION:
XS GIS Cut Line= 3
      3643592.14     10150541.64      3642263.75     10150696.17
      3641592.11     10151591.64
#Sta/Elev= 30
  3641.9   191.1  3662.1  191.36  3769.8  190.28  3974.2  191.32  4064.8  190.85
  4207.6   191.3  4225.8  190.79  4235.9  189.64  4244.3  189.69    4256  192.23
  4266.1  193.49  4286.1  192.93  4306.4  190.44  4316.5  190.33  4620.5  190.05
  4901.1   189.3  5105.9  189.66  5459.2  189.22  5461.9  188.72  5465.2  189.22
  5562.2  190.14  5662.2  194.16  5755.9  198.83  5791.3  198.84  5841.3  200.54
  5962.1  202.97  6005.9  204.45  6026.7  205.84  6048.6  205.13  6098.6  206.64
#Mann= 5 ,-1 , 0
  3641.9     .05       0  4244.3     .08       0  4620.5     .05       0
  5459.2     .03       0  5465.2     .05       0
Bank Sta=5459.2,5465.2
XS Rating Curve= 0 ,0
Exp/Cntr=0.3,0.1

Type RM Length L Ch R = 1 ,5271    ,417,417,417
BEGIN DESCRIPTION:
UNT077 IN ROCK 5.0
END DESCRIPTION:
XS GIS Cut Line= 3
      3643592.09     10150491.64      3642096.89     10150503.29
      3641642.13      10151391.6
#Sta/Elev= 30
  3479.8  190.98  3669.8  190.11  3889.8  191.24  4123.3  191.06  4139.8  190.57
  4149.8  189.48  4159.8   189.6  4179.8  192.64  4189.8  193.29  4229.8  191.88
    4250  190.52  4269.8  190.17  4289.8   190.5  4309.8  190.13  4470.2  190.09
  4859.8  189.64  4995.9  188.83  4998.7  188.33  5001.9  188.83  5119.2  189.37
  5148.7     189  5170.9  189.33    5393  189.09  5520.6  189.41  5631.7  191.45
  5637.3  192.07  5714.7  194.29  5793.3  197.83  5898.1  199.63    5973  201.42
#Mann= 5 ,-1 , 0
  3479.8     .05       0    4250     .08       0  4470.2     .05       0
  4995.9     .03       0  5001.9     .05       0
Bank Sta=4995.9,5001.9
XS Rating Curve= 0 ,0
Exp/Cntr=0.3,0.1

Type RM Length L Ch R = 1 ,4854    ,470,470,470
BEGIN DESCRIPTION:
UNT077 IN ROCK 4.0
END DESCRIPTION:
XS GIS Cut Line= 3
      3643142.15     10150191.64      3641807.16      10150211.8
      3641492.11     10151391.62
#Sta/Elev= 30
  3670.5   189.9  3960.6  190.92  4507.6  189.72  4520.6  186.94  4527.6  186.59
  4530.4  186.09  4533.6  186.59  4550.6  190.68  4560.6  191.92  4590.6  193.03
  4606.4  190.68  4610.7  189.86  4659.9  189.28  4940.7  188.88  5008.3  187.72
  5048.3  188.88  5743.9  189.77  5899.1  192.71  5974.1  195.26  6014.1  195.37
    6049  196.54  6054.2   196.1  6089.1   197.4  6129.2  197.86  6134.4  197.25
  6164.1  198.67  6169.3  198.33  6209.4  201.46  6224.2  205.13  6226.8  205.13
#Mann= 5 ,-1 , 0
  3670.5     .05       0  4507.6     .08       0  4527.6     .03       0
  4533.6     .08       0  4606.4     .05       0
Bank Sta=4527.6,4533.6
XS Rating Curve= 0 ,0
Exp/Cntr=0.3,0.1

Type RM Length L Ch R = 1 ,4384    ,481,481,481
BEGIN DESCRIPTION:
UNT077 IN ROCK 3.0
END DESCRIPTION:
XS GIS Cut Line= 3
      3642892.12     10149441.64      3641522.43     10149897.56
      3641392.11     10151391.61
#Sta/Elev= 30
  3559.6  189.28  4109.9  188.76  4111.7  188.73  4202.5   188.7  4213.5  186.15
  4231.1   183.9  4233.9   183.4  4237.1   183.9  4245.2  186.73  4255.2  187.64
  4303.2  186.44  4334.8   186.9  4340.1  187.98  4360.6  187.16  4365.4  187.76
  4403.4  187.82  4423.9  184.41  4444.9  189.56  4470.8   191.4  4476.5  191.41
    4493  188.99  4524.6  188.41  5007.7  187.95    5188  188.84  6011.1  189.33
  6402.5  196.89  6432.7  199.11  6472.8  207.53  6482.9  207.58  6502.9  204.33
#Mann= 7 ,-1 , 0
  3559.6     .05       0  4109.9     .16       0  4111.7     .05       0
  4231.1     .03       0  4237.1     .05       0  4365.4     .08       0
  4470.8     .05       0
Bank Sta=4231.1,4237.1
XS Rating Curve= 0 ,0
Exp/Cntr=0.3,0.1

Type RM Length L Ch R = 1 ,3903    ,151,151,151
BEGIN DESCRIPTION:
UNT077 IN ROCK 2.0
END DESCRIPTION:
XS GIS Cut Line= 3
      3642592.12     10149191.64      3641109.99       10149646.
      3640732.82     10150851.67
#Sta/Elev= 30
  3483.5  188.04  3739.6  187.55  3810.3  188.79  3825.8  187.88  3837.8  186.37
  3843.1  187.05  3860.1  185.11  3870.5  185.59  3875.8  187.49    3881  186.99
  3933.3  188.06  3941.3  187.18  3946.5  187.53  3954.4  184.39  3961.6  182.76
  3964.4  182.26  3967.6  182.76  3974.1  185.39  3979.3  183.31  3985.6  190.66
    3996  189.59  4006.5  191.68  4017.3  191.48    4050  189.87  4058.9  188.55
  5060.6  187.62  5514.3   189.4  5762.6  192.09  6044.2  192.43    6297  194.85
#Mann= 6 ,-1 , 0
  3483.5     .05       0  3825.8     .16       0  3954.4     .08       0
  3961.6     .03       0  3967.6     .08       0  4058.9     .05       0
Bank Sta=3961.6,3967.6
XS Rating Curve= 0 ,0
Exp/Cntr=0.3,0.1

Type RM Length L Ch R = 1 ,3752    ,36,36,36
BEGIN DESCRIPTION:
Mapping XS b5135df2
END DESCRIPTION:
XS GIS Cut Line= 4
      3641482.73     10149234.16      3641016.57     10149554.49
      3640956.67     10149643.03      3640670.26      10150806.9
#Sta/Elev= 30
  4417.7  188.01    4513  187.39  4515.7  186.89    4519  187.39  4611.4  188.06
  4841.5  187.72  4898.3  188.23  4940.2  187.64    5014  187.73  5028.2  187.99
  5041.1  189.47    5056  189.79    5071  188.86    5077  189.38    5086  188.75
  5089.8   189.1  5109.4  187.66  5298.8   188.3  5594.6  190.05  5630.9   190.7
  5636.1  190.36  5789.1  192.04  5838.5  192.32  5843.7  191.95    5892  192.93
  6004.6   193.9  6087.7   193.6  6134.3  193.92  6139.5  194.32  6288.8  194.76
#Mann= 3 ,-1 , 0
  4417.7     .05       0    4513     .03       0    4519     .05       0
Bank Sta=4513,4519
XS Rating Curve= 0 ,0
Exp/Cntr=0.3,0.1