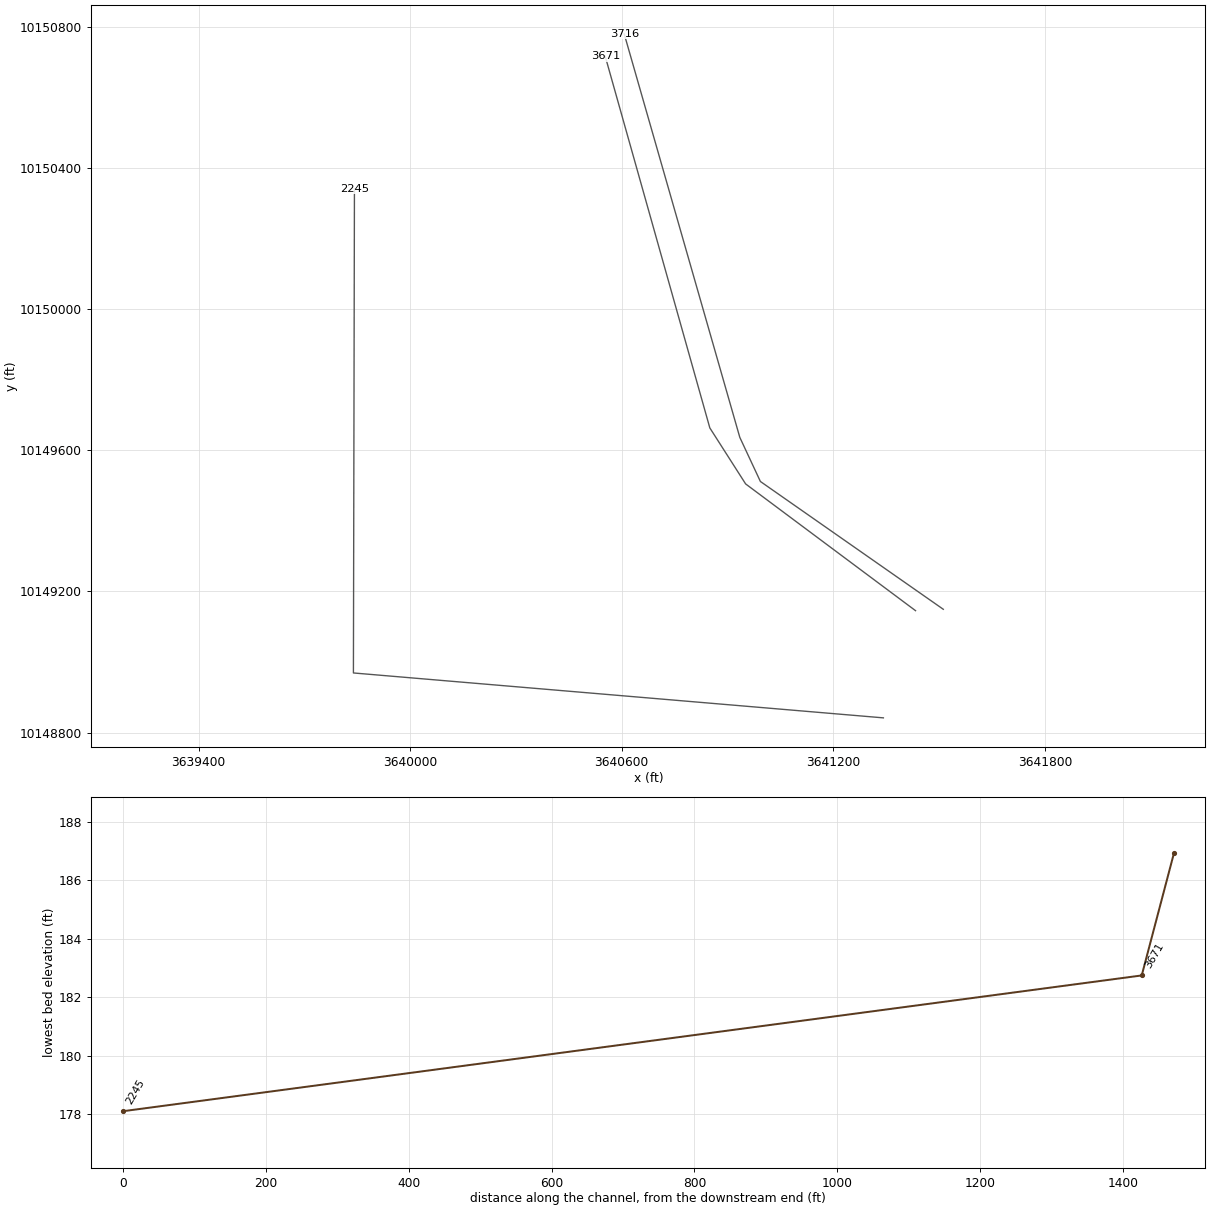
HEC-RAS study UNT077 IN ROCK.prj: UNT077 IN ROCK Base Level Engineering

--- UNT077 IN ROCK.g01 (geometry) --- (continued)

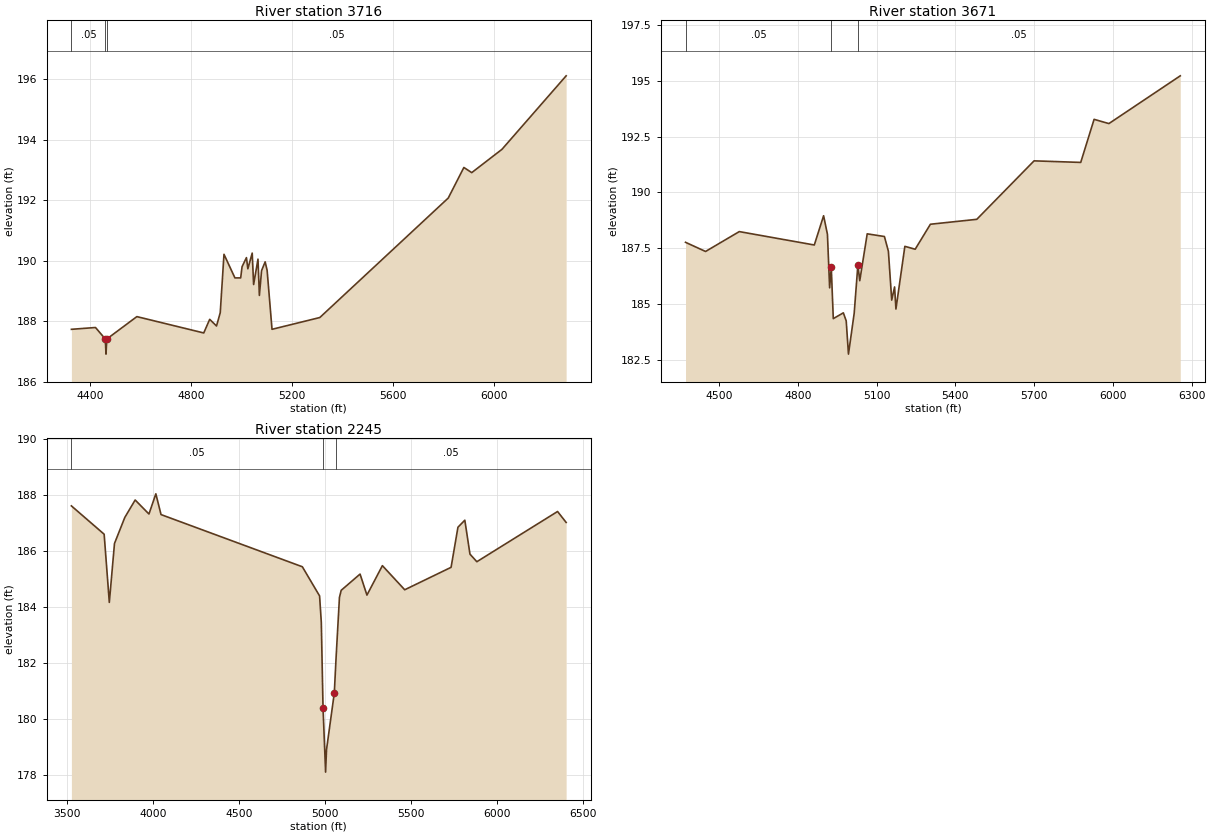
Type RM Length L Ch R = 1 ,3716    ,45,45,45
BEGIN DESCRIPTION:
Mapping XS 0dc1f27d
END DESCRIPTION:
XS GIS Cut Line= 4
      3641511.96     10149149.54      3640993.31     10149511.95
      3640934.91      10149637.1      3640607.07     10150781.33
#Sta/Elev= 30
  4325.5  187.74    4421   187.8  4459.9  187.42  4462.6  186.92  4465.9  187.42
    4585  188.16  4850.1  187.62  4873.7  188.07  4900.7  187.85  4915.5  188.29
  4930.3  190.22  4973.7  189.44  4996.5  189.44    5002  189.81  5019.4  190.11
  5024.9  189.74  5042.2  190.26  5047.8  189.22  5065.1  190.06  5070.6  188.86
  5079.3  189.68  5093.5  189.97  5101.3  189.69  5120.7  187.74  5310.2  188.13
  5819.3  192.08  5881.2  193.09  5912.4  192.92  6032.2  193.69  6286.6  196.12
#Mann= 3 ,-1 , 0
  4325.5     .05       0  4459.9     .03       0  4465.9     .05       0
Bank Sta=4459.9,4465.9
XS Rating Curve= 0 ,0
Exp/Cntr=0.3,0.1

Type RM Length L Ch R = 1 ,3671    ,1426,1426,1426
BEGIN DESCRIPTION:
Mapping XS ef7a4ea0
END DESCRIPTION:
XS GIS Cut Line= 4
      3641433.25     10149145.62      3640951.46     10149505.01
       3640849.9     10149663.86      3640553.29      10150717.6
#Sta/Elev= 30
  4372.5  187.76  4448.8  187.35  4577.3  188.24    4863  187.64  4898.4  188.95
    4913  188.12  4921.4  185.72  4927.6  186.64  4935.3  184.34  4973.6   184.6
  4984.5  184.24  4993.1  182.75  5014.9  184.58  5028.9  186.74  5036.1  186.04
  5064.5  188.14    5130  188.02  5145.2  187.36  5157.8  185.17  5168.7  185.76
  5173.9  184.77  5207.9  187.58  5247.2  187.45  5305.2  188.57  5481.8  188.79
    5700  191.41  5877.7  191.34  5928.6  193.27    5985  193.08  6256.8  195.22
#Mann= 3 , 0 , 0
  4372.5     .05       0  4927.6    .035       0  5028.9     .05       0
Bank Sta=4927.6,5028.9
XS Rating Curve= 0 ,0
Exp/Cntr=0.3,0.1

Type RM Length L Ch R = 1 ,2245    ,0,0,0
BEGIN DESCRIPTION:
UNT077 IN ROCK 1.0
END DESCRIPTION:
XS GIS Cut Line= 3
       3641342.1     10148841.64      3639839.21     10148968.98
      3639842.11      10150341.6
#Sta/Elev= 30
  3523.5   187.6  3714.2  186.59  3744.3  184.16  3774.4  186.26  3834.6  187.19
  3894.8  187.81  3975.1  187.31  4015.2  188.03  4045.4  187.29  4868.3  185.43
  4968.7  184.39  4978.7  183.45  4988.7  180.41  5003.7  178.11    5009  178.91
  5054.4  180.93  5064.4  182.15  5084.4  184.34  5094.4  184.59  5204.4  185.17
  5244.4  184.42  5334.4  185.47  5464.4  184.61  5734.4  185.41  5774.4  186.84
  5814.4  187.09  5844.4  185.88  5884.4  185.61  6354.4   187.4  6404.4  187.01
#Mann= 3 ,-1 , 0
  3523.5     .05       0  4988.7    .035       0  5064.4     .05       0
Bank Sta=4988.7,5054.4
XS Rating Curve= 0 ,0
Exp/Cntr=0.3,0.1

Chan Stop Cuts=-1
Use User Specified Reach Order=0
Composite Channel Slope=5