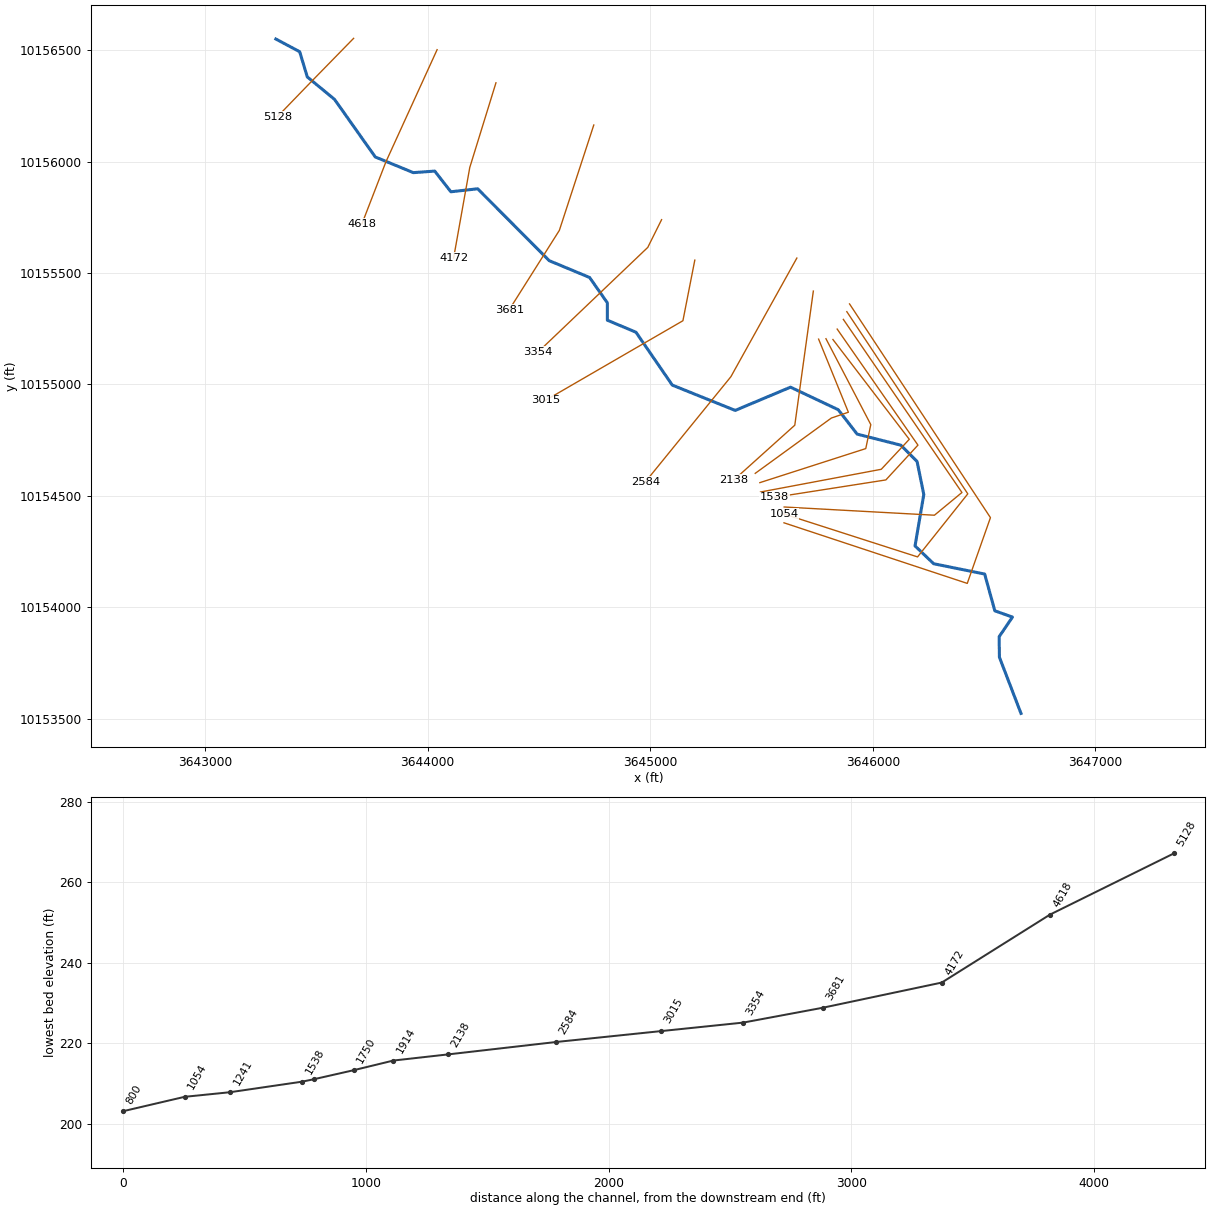
--- UNT078 IN ROCK.prj (project) ---

Proj Title=UNT078 IN ROCK Base Level Engineering
Current Plan=p01
Default Exp/Contr=0.3,0.1
English Units
Geom File=g01
Flow File=f01
Plan File=p01
Y Axis Title=Elevation
X Axis Title(PF)=Main Channel Distance
X Axis Title(XS)=Station
BEGIN DESCRIPTION:
UNT078 IN ROCK
END DESCRIPTION:
DSS Export Rating Curves= 0
DSS Export Rating Curve Sorted= 0
DSS Export Volume Flow Curves= 0
DXF OffsetX= 0
DXF OffsetY= 0
DXF ScaleX= 1
DXF ScaleY= 10

--- UNT078 IN ROCK.p01 (plan) ---

Plan Title=Multiple Run
Short Identifier=Multiple
Geom File=g01
Flow File=f01
Subcritical Flow
K Sum by GR= 0
Std Step Tol= 0.01
Critical Tol= 0.01
Num of Std Step Trials= 20
Max Error Tol= 0.3
Flow Tol Ratio= 0.001
Split Flow NTrial= 30
Split Flow Tol= 0.02
Split Flow Ratio= 0.02
Log Output Level= 0
Friction Slope Method= 1
Unsteady Friction Slope Method= 2
Unsteady Bridges Friction Slope Method= 1
Parabolic Critical Depth
Global Vel Dist=  1 , 1 , 1
Global Log Level= 0
CheckData=True
Encroach Param= -1, 0, 0, 0
BEGIN DESCRIPTION:
Multiple Run
END DESCRIPTION:

--- UNT078 IN ROCK.f01 (steady flow) ---

Flow Title=Multiple
Number of Profiles=7
Profile Names=10-year,25-year,50-year,1pct_min,100-year,1pct_plu,500-year
River Rch & RM= UNT078 IN ROCK,Reach-1,5128
     238     304     356     307     415     561     562
Boundary for River Rch & Prof#=UNT078 IN ROCK,Reach-1,1
Up Type=0
Dn Type=3
Dn Slope=0.005
Boundary for River Rch & Prof#=UNT078 IN ROCK,Reach-1,2
Up Type=0
Dn Type=3
Dn Slope=0.005
Boundary for River Rch & Prof#=UNT078 IN ROCK,Reach-1,3
Up Type=0
Dn Type=3
Dn Slope=0.005
Boundary for River Rch & Prof#=UNT078 IN ROCK,Reach-1,4
Up Type=0
Dn Type=3
Dn Slope=0.005
Boundary for River Rch & Prof#=UNT078 IN ROCK,Reach-1,5
Up Type=0
Dn Type=3
Dn Slope=0.005
Boundary for River Rch & Prof#=UNT078 IN ROCK,Reach-1,6
Up Type=0
Dn Type=3
Dn Slope=0.005
Boundary for River Rch & Prof#=UNT078 IN ROCK,Reach-1,7
Up Type=0
Dn Type=3
Dn Slope=0.005

--- UNT078 IN ROCK.g01 (geometry) ---

Geom Title=Existing Conditions
Program Version=4.10

River Reach=UNT078 IN ROCK  ,Reach-1
Reach XY= 30
       3643318.6     10156550.47      3643425.66     10156493.54
      3643459.82     10156380.36      3643582.07     10156279.79
      3643765.23     10156021.11      3643936.24     10155950.79
      3644032.33     10155957.79       3644104.8     10155864.92
      3644225.12     10155878.36      3644546.48     10155555.83
      3644727.91     10155480.31      3644807.77     10155366.59
      3644807.77     10155288.47      3644936.24     10155234.65
      3645099.52     10154997.27      3645382.04     10154883.61
      3645630.59     10154987.98      3645844.92     10154886.77
      3645929.87     10154777.27      3646126.05     10154727.67
      3646199.17      10154654.3      3646229.26     10154506.13
      3646189.95     10154275.46      3646273.65     10154195.49
      3646502.77     10154149.22      3646548.34     10153984.29
      3646627.55     10153956.08      3646567.87     10153868.19
      3646568.96     10153775.96      3646665.86     10153523.91

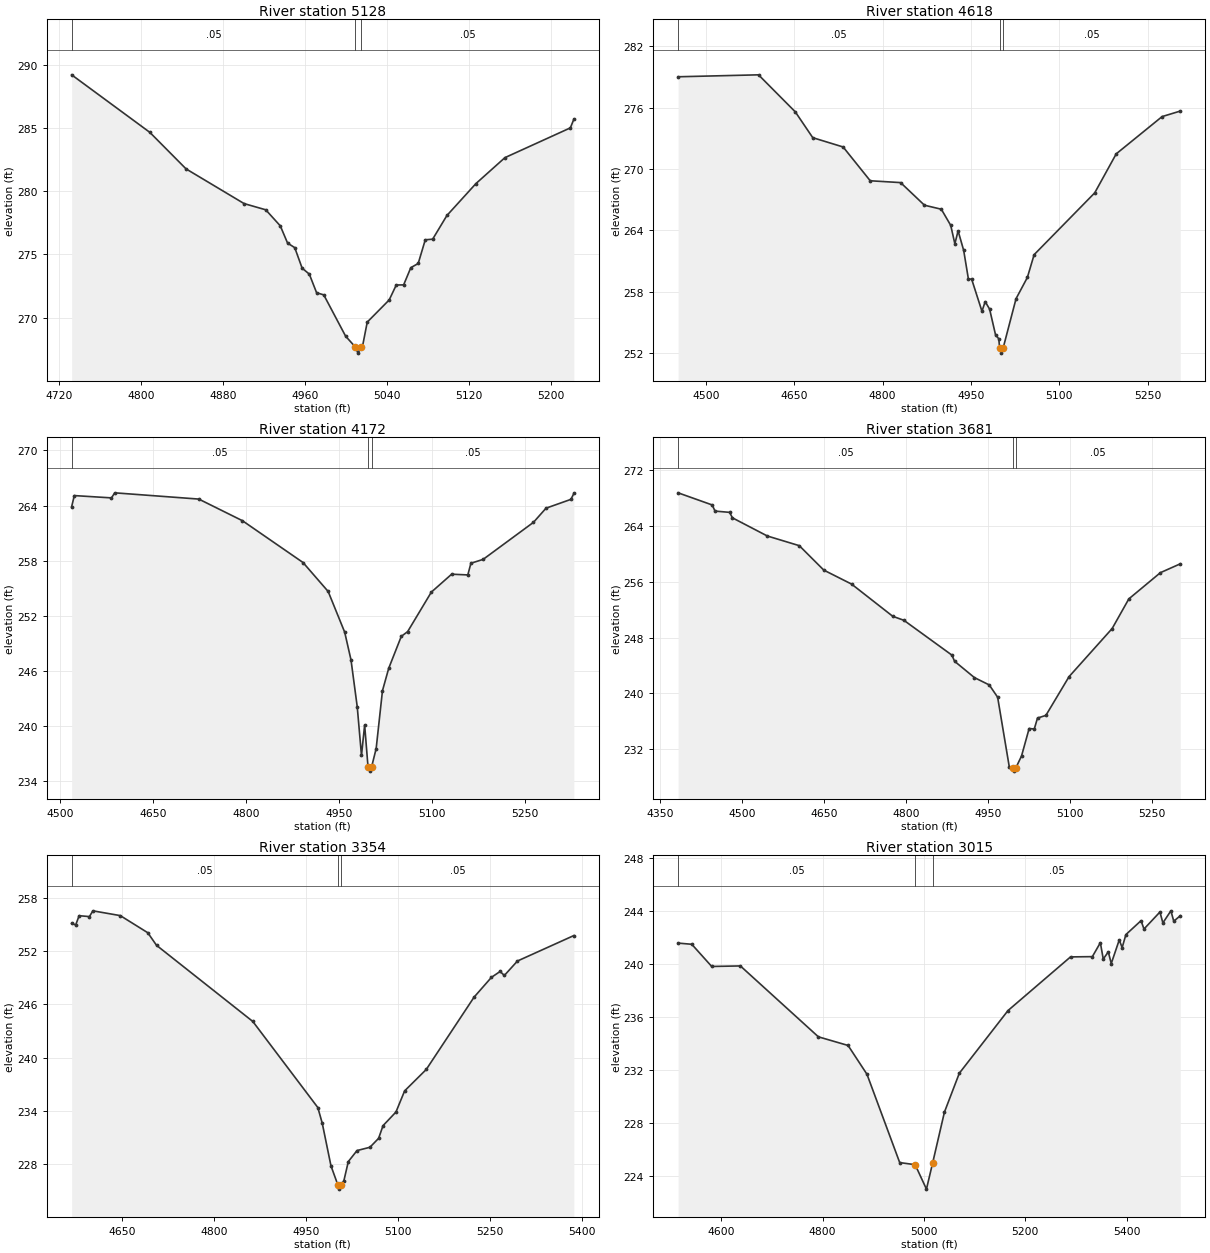
Type RM Length L Ch R = 1 ,5128    ,510,510,510
BEGIN DESCRIPTION:
UNT078 IN ROCK 9.0
END DESCRIPTION:
XS GIS Cut Line= 3
      3643667.93      10156553.6      3643469.64     10156350.81
      3643326.24     10156202.68
#Sta/Elev= 30
  4732.5  289.19  4808.7  284.65  4844.1  281.76  4900.7  279.02  4921.8  278.53
    4936  277.26  4943.1   275.9  4950.1  275.54  4957.3  273.92  4964.3  273.45
  4971.4  271.98  4978.4  271.81  4999.7  268.55    5009  267.71  5011.8  267.21
    5015  267.71  5016.1  267.71  5020.8  269.66  5042.2  271.41  5049.1  272.59
  5056.3   272.6  5063.3  273.96  5070.5  274.29  5077.4  276.16  5084.6  276.21
  5098.5  278.08  5126.8   280.6  5155.1  282.65  5218.9     285  5222.3  285.68
#Mann= 3 ,-1 , 0
  4732.5     .05       0    5009    .035       0    5015     .05       0
Bank Sta=5009,5015
XS Rating Curve= 0 ,0
Exp/Cntr=0.3,0.1

Type RM Length L Ch R = 1 ,4618    ,446,446,446
BEGIN DESCRIPTION:
UNT078 IN ROCK 8.0
END DESCRIPTION:
XS GIS Cut Line= 3
        3644043.     10156502.67      3643813.39     10156000.12
      3643705.01     10155720.19
#Sta/Elev= 30
  4452.8  279.01  4589.3   279.2  4651.8  275.58  4681.4  273.06    4733  272.15
    4779  268.85  4830.6  268.67  4871.1  266.46  4899.7  266.07  4915.7  264.49
  4922.7  262.69  4928.2  263.96  4937.7  262.04  4945.7  259.25  4951.2  259.24
  4968.7   256.1  4974.2  257.04  4981.7  256.31  4991.8  253.79  4997.3  253.41
  4998.7  252.51  5001.5  252.01  5004.7  252.51  5026.6  257.33  5045.8   259.4
  5057.3  261.63  5160.2  267.67  5196.7  271.48  5274.6  275.12  5305.5  275.66
#Mann= 3 ,-1 , 0
  4452.8     .05       0  4998.7     .03       0  5004.7     .05       0
Bank Sta=4998.7,5004.7
XS Rating Curve= 0 ,0
Exp/Cntr=0.3,0.1

Type RM Length L Ch R = 1 ,4172    ,491,491,491
BEGIN DESCRIPTION:
UNT078 IN ROCK 7.0
END DESCRIPTION:
XS GIS Cut Line= 3
      3644307.36     10156354.09      3644189.75     10155974.01
      3644117.11     10155567.41
#Sta/Elev= 30
  4518.6  263.87  4522.9  265.08  4582.9  264.83  4588.2  265.38  4723.9   264.7
  4794.3  262.35  4892.2   257.8  4932.8  254.65  4959.5  250.22  4969.7   247.2
  4979.8  242.08  4986.6  236.81  4991.7  240.13  4997.1  235.61  4999.9  235.11
  5003.1  235.61  5010.3  237.56  5020.5  243.86  5030.6   246.3  5050.9  249.77
  5061.1  250.28  5099.4  254.58  5132.2  256.53  5158.3  256.45  5163.3  257.72
    5183  258.14  5264.3  262.17  5284.6  263.71  5324.8  264.67  5329.5  265.31
#Mann= 3 ,-1 , 0
  4518.6     .05       0  4997.1     .03       0  5003.1     .05       0
Bank Sta=4997.1,5003.1
XS Rating Curve= 0 ,0
Exp/Cntr=0.3,0.1

Type RM Length L Ch R = 1 ,3681    ,327,327,327
BEGIN DESCRIPTION:
UNT078 IN ROCK 6.0
END DESCRIPTION:
XS GIS Cut Line= 3
      3644746.83     10156164.71      3644592.11     10155691.64
      3644367.39     10155336.25
#Sta/Elev= 30
  4382.9  268.75  4445.2  267.01  4450.4  266.13    4477  265.95  4482.3  265.16
    4546  262.56  4604.5  261.17  4649.2  257.67  4700.1  255.66  4775.4  251.04
  4795.7  250.47  4883.6  245.47  4888.3   244.6  4924.7  242.25  4951.8   241.2
  4967.1  239.44  4988.3   229.5  4994.6  229.34  4997.4  228.84  5000.6  229.34
  5010.8  231.01  5024.7  234.95  5034.1  234.88    5040  236.45  5055.3  236.83
  5097.7  242.39  5176.5  249.29    5207  253.54  5264.7   257.3  5301.1  258.57
#Mann= 3 ,-1 , 0
  4382.9     .05       0  4994.6     .03       0  5000.6     .05       0
Bank Sta=4994.6,5000.6
XS Rating Curve= 0 ,0
Exp/Cntr=0.3,0.1

Type RM Length L Ch R = 1 ,3354    ,339,339,339
BEGIN DESCRIPTION:
UNT078 IN ROCK 5.0
END DESCRIPTION:
XS GIS Cut Line= 3
      3645051.41     10155739.82      3644989.35      10155615.3
      3644497.27     10155146.46
#Sta/Elev= 30
  4567.8  255.13  4574.4  254.96    4580     256  4596.8   255.9  4602.4  256.55
  4647.1  256.01  4691.9  254.08  4706.2  252.66  4863.2  244.07  4969.2  234.36
  4976.4  232.59  4990.6  227.79  5001.7  225.66  5004.5  225.16  5007.7  225.66
  5011.7  226.12  5018.9  228.27  5033.1  229.51  5054.1  229.88  5068.3  230.89
  5075.5  232.32  5096.6  233.86  5110.7  236.24    5146  238.66    5224  246.82
  5252.3  249.05  5266.4  249.71  5273.3  249.26  5294.7  250.89  5386.6  253.76
#Mann= 3 ,-1 , 0
  4567.8     .05       0  5001.7    .035       0  5007.7     .05       0
Bank Sta=5001.7,5007.7
XS Rating Curve= 0 ,0
Exp/Cntr=0.3,0.1

Type RM Length L Ch R = 1 ,3015    ,431,431,431
BEGIN DESCRIPTION:
UNT078 IN ROCK 4.0
END DESCRIPTION:
XS GIS Cut Line= 3
       3645200.6      10155558.1      3645147.23     10155286.15
      3644529.16     10154928.35
#Sta/Elev= 30
  4514.8  241.57  4541.8  241.48  4581.1  239.81  4637.7  239.85  4791.7  234.51
  4850.3  233.86  4887.6  231.69  4952.2  225.04  4982.7  224.88    5005  223.04
  5017.4  225.04  5040.5  228.84  5069.9  231.77    5166  236.49  5289.4  240.53
  5332.5  240.55  5348.3   241.6    5354  240.37    5364  240.91  5369.8  240.03
  5385.6  241.81  5391.3  241.23  5398.7  242.21  5428.6  243.26  5434.4  242.63
  5465.9  243.91  5471.7  243.09  5487.5     244  5493.2  243.22  5506.1  243.63
#Mann= 3 , 0 , 0
  4514.8     .05       0  4982.7    .035       0  5017.4     .05       0
Bank Sta=4982.7,5017.4
XS Rating Curve= 0 ,0
Exp/Cntr=0.3,0.1

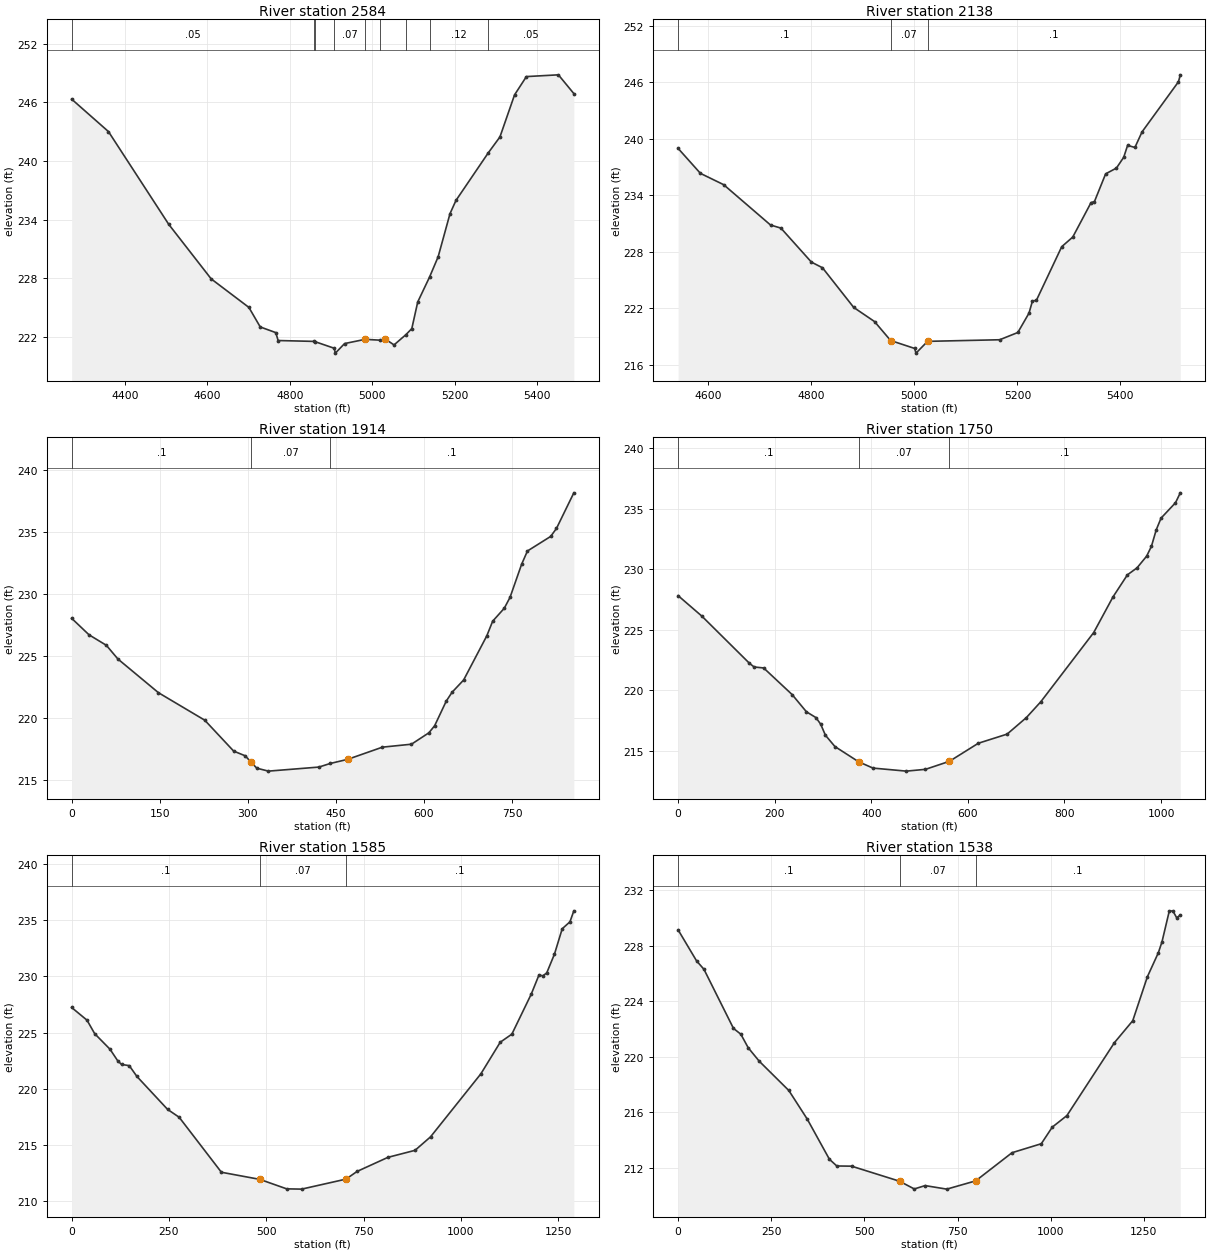
Type RM Length L Ch R = 1 ,2584    ,446,446,446
BEGIN DESCRIPTION:
UNT078 IN ROCK 3.0
END DESCRIPTION:
XS GIS Cut Line= 3
        3645659.     10155567.37      3645362.66     10155034.87
      3644978.34     10154562.58
#Sta/Elev= 30
  4270.5  246.34  4359.8  243.02  4506.1  233.52    4609  227.94  4700.5  225.02
    4728  223.02  4765.7  222.44  4771.4  221.63  4859.5  221.54  4859.8  221.53
  4907.4  220.84  4910.2  220.34  4932.7  221.32  4982.3  221.75  5017.4  221.67
  5031.8  221.77  5052.6  221.18  5081.4  222.23  5095.7  222.85  5110.1  225.58
  5138.8  228.13  5159.6   230.2  5188.4  234.62  5202.8  235.97    5281  240.83
  5309.5  242.47    5345  246.78  5373.7  248.65  5451.3  248.83  5488.8  246.91
#Mann= 9 ,-1 , 0
  4270.5     .05       0  4859.5     .12       0  4859.8     .05       0
  4907.4     .07       0  4982.3     .05       0  5017.4     .12       0
  5081.4     .05       0  5138.8     .12       0    5281     .05       0
Bank Sta=4982.3,5031.8
XS Rating Curve= 0 ,0
Exp/Cntr=0.3,0.1

Type RM Length L Ch R = 1 ,2138    ,224,224,224
BEGIN DESCRIPTION:
UNT078 IN ROCK 2.0
END DESCRIPTION:
XS GIS Cut Line= 3
      3645733.09     10155419.23      3645649.74     10154817.25
      3645376.81     10154572.07
#Sta/Elev= 30
  4541.6  238.98  4584.9  236.33    4630  235.13  4720.9  230.85  4741.1  230.52
  4800.3  226.91  4821.8  226.31  4882.4   222.1  4922.8   220.6    4954  218.59
  5000.5  217.75  5003.3  217.25  5025.7   218.5  5165.7  218.67  5200.9  219.44
  5222.6   221.5  5229.3  222.79  5236.8  222.84  5286.1  228.55  5307.5  229.57
  5342.9  233.22  5349.6  233.34  5371.3  236.28  5392.2  236.89  5406.4  238.04
  5413.9   239.3  5428.1  239.08  5441.9  240.73  5512.6  246.05  5516.2  246.79
#Mann= 3 , 0 , 0
  4541.6      .1       0    4954     .07       0  5025.7      .1       0
Bank Sta=4954,5025.7
XS Rating Curve= 0 ,0
Exp/Cntr=0.3,0.1

Type RM Length L Ch R = 1 ,1914    ,164,164,164
XS GIS Cut Line= 4
     3645756.808     10155203.62     3645890.489    10154875.495
       3645814.1    10154849.453     3645472.086    10154601.189
#Sta/Elev= 30
       0228.034629.56579226.705859.13158225.860478.84211224.7548 147.829222.0452
226.6711219.8331275.9474217.3443295.6579216.9642305.5132216.4532315.3684215.9685
 335.079215.7323421.0838216.0583440.4319 216.349470.0643  216.68529.3291217.6623
578.7164217.8989608.3488218.8142618.2263219.3861637.9813221.3669647.8587222.0787
667.6136223.0691707.1235226.6291 717.001 227.798736.7559228.8394746.6334229.7223
766.3884232.3887776.2658233.4516815.7757 234.623825.6531235.2633855.2856238.1339
#Mann= 3 ,-1 , 0
       0      .1       0305.5132     .07       0440.4319      .1       0
Bank Sta=305.5132,470.0643
XS Rating Curve= 0 ,0
Exp/Cntr=0.3,0.1

Type RM Length L Ch R = 1 ,1750    ,165,165,165
XS GIS Cut Line= 5
     3645789.794    10155205.356     3645991.183    10154819.939
     3645968.614      10154712.3     3645492.919    10154559.522
3645492.9188837810154559.5219627
#Sta/Elev= 30
       0227.813949.19541 226.122147.5862222.2336157.4253221.9246177.1035221.8453
 236.138219.6452265.6552218.2272285.3334217.7491295.1725217.2046305.0115 216.292
324.6897215.3577373.8851214.0977403.4023213.5797472.5392213.3281512.1588213.4764
561.7925214.1384621.5493215.6281681.3061216.3847 721.144217.7489751.0224219.0553
860.5765224.7706900.4144227.7056930.2928229.5314950.2117230.1073970.1307231.0733
980.0901231.8892990.0496233.25291000.009234.21491029.887235.48361039.847236.3022
#Mann= 3 , 0 , 0
       0      .1       0373.8851     .07       0561.7925      .1       0
Bank Sta=373.8851,561.7925
XS Rating Curve= 0 ,0
Exp/Cntr=0.3,0.1

Type RM Length L Ch R = 1 ,1585    ,47,47,47
BEGIN DESCRIPTION:
Mapping XS 3480d08b
END DESCRIPTION:
XS GIS Cut Line= 4
     3645821.044    10155201.883     3646164.119    10154753.966
     3646038.251    10154619.417     3645495.716     10154517.42
#Sta/Elev= 30
       0227.226539.45602226.097959.18403224.897498.64005223.5102118.3681222.4835
128.2321222.1584147.9601222.0551167.6881221.0919246.6001218.1578276.1921 217.463
384.6962212.5692483.3362 211.936552.3843211.0926590.7656211.0678 704.835211.9584
733.3523212.6443812.5103213.8951882.1624214.5198921.9636215.71791051.318221.3264
1101.069224.1375 1130.92224.85561180.672228.41481200.572230.11991210.523230.0426
1220.473230.30291240.374231.97761260.274234.23241280.175234.85191290.125235.8268
#Mann= 3 , 0 , 0
       0      .1       0483.3362     .07       0 704.835      .1       0
Bank Sta=483.3362,704.835
XS Rating Curve= 0 ,0
Exp/Cntr=0.3,0.1

Type RM Length L Ch R = 1 ,1538    ,297,297,297
XS GIS Cut Line= 4
     3645840.141    10155248.758     3646202.989    10154727.925
     3646058.891    10154571.6753645558.8912412110154493.5500377
#Sta/Elev= 30
       0 229.14649.51354 226.91469.31895226.3095148.5406222.0548 168.346 221.634
188.1514220.6586217.8596 219.687297.0812217.5844346.5948215.5215 406.011212.6335
425.8164  212.15465.4273212.1367594.1625211.0533633.7733 210.496662.8447210.7376
720.9875210.4835798.5112211.0783896.0472213.1052974.5812213.75191004.031214.9467
1043.298 215.7771170.916221.0312    1220222.60711259.267225.77141288.717227.5012
1298.534228.29251318.167230.51781327.984230.4969  1337.8 230.0221347.617230.2069
#Mann= 3 , 0 , 0
       0      .1       0594.1625     .07       0798.5112      .1       0
Bank Sta=594.1625,798.5112
XS Rating Curve= 0 ,0
Exp/Cntr=0.3,0.1

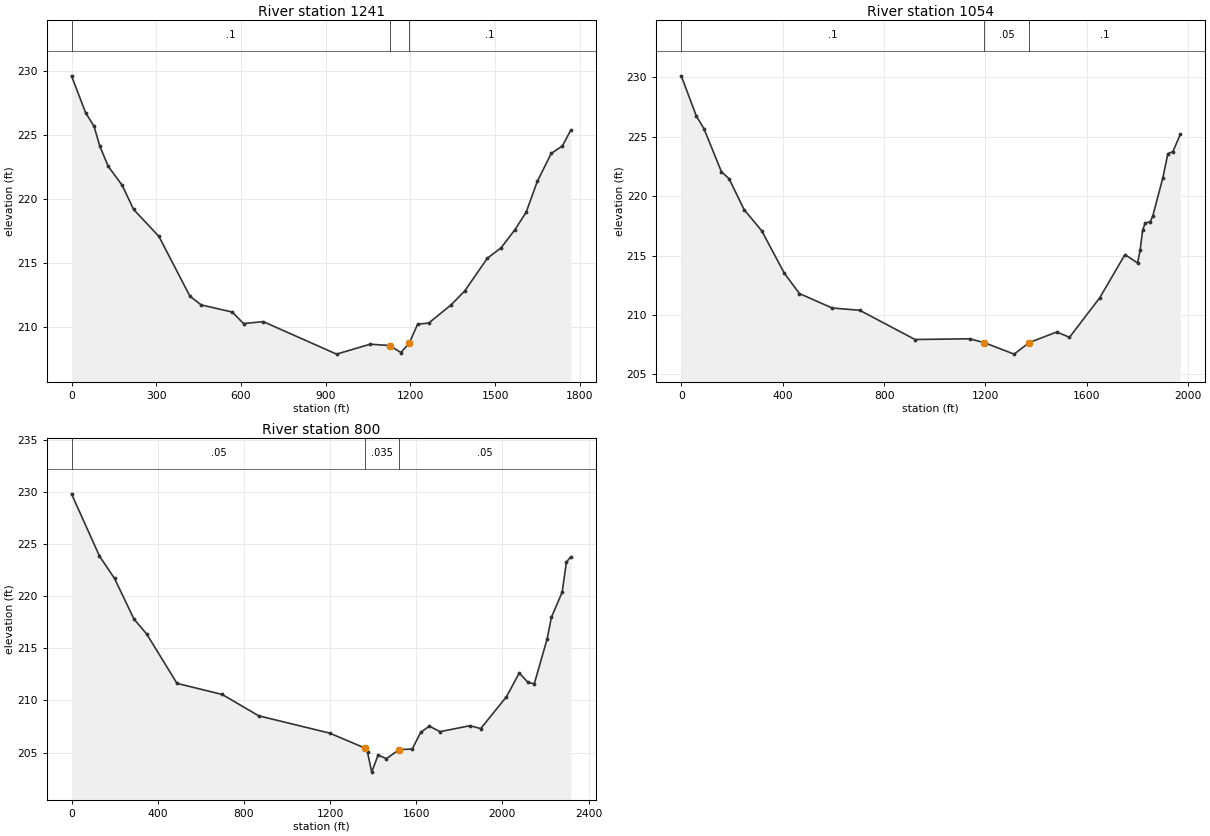
Type RM Length L Ch R = 1 ,1241    ,187,187,187
BEGIN DESCRIPTION:
Mapping XS e4e9353d
END DESCRIPTION:
XS GIS Cut Line= 4
     3645867.919    10155292.161     3646400.664     10154515.25
     3646276.966    10154413.254     3645602.053    10154450.146
#Sta/Elev= 30
       0 229.64849.92826226.761479.88522225.697899.85652224.1701129.8135222.5719
179.7417221.0707219.6843219.1965309.5552217.0749419.3974212.3935  459.34211.7123
569.1821211.1556609.1248210.2514679.0244210.4044938.6512 207.8591057.816208.6357
1127.108208.53181166.535207.98481196.106208.72361225.676210.19851265.103210.2938
1343.958211.70781393.242212.82251472.096 215.353 1521.38216.18461570.664217.6133
1610.092218.96891649.519221.37861698.803223.5725 1738.23 224.1541767.801225.3797
#Mann= 3 , 0 , 0
       0      .1       01127.108     .07       01196.106      .1       0
Bank Sta=1127.108,1196.106
XS Rating Curve= 0 ,0
Exp/Cntr=0.3,0.1

Type RM Length L Ch R = 1 ,1054    ,254,254,254
XS GIS Cut Line= 5
     3645883.544    10155326.883     3646426.947    10154509.175
     3646201.252    10154226.189     3645600.558    10154418.897
3645600.5578837610154418.8970373
#Sta/Elev= 30
       0230.113159.48845226.729289.23267225.6821158.6358222.0346188.3801221.4714
247.8685 218.865317.2717217.0869406.5044213.5154465.9928211.8087594.8845210.5928
703.9466210.3995922.0709207.94091137.557208.00351196.057207.66971313.055206.7125
 1372.15207.68291481.583208.57471531.325208.12541650.705211.45271750.189215.0804
1799.931214.3797 1809.88215.44821819.828217.12261829.776217.73741849.673217.8333
1859.622218.31291899.415221.52181919.312223.55961939.209223.74581969.054225.2261
#Mann= 3 , 0 , 0
       0      .1       01196.057     .05       0 1372.15      .1       0
Bank Sta=1196.057,1372.15
XS Rating Curve= 0 ,0
Exp/Cntr=0.3,0.1

Type RM Length L Ch R = 1 ,800     ,0,0,0
BEGIN DESCRIPTION:
UNT078 IN ROCK 1.0
END DESCRIPTION:
XS GIS Cut Line= 4
     3645895.697    10155361.606     3646528.702    10154402.403
     3646424.536    10154107.264     3645601.294    10154379.204
#Sta/Elev= 30
       0229.8117 129.892223.8415199.8339221.6951289.7592217.8169349.7094216.3534
489.5931211.6398699.4187210.5781869.2775208.52711197.948206.8739 1364.22205.4191
1374.001  205.041393.562 203.1321422.904204.75961462.027204.43331521.684205.2941
 1581.34205.34151621.111206.95111660.882207.54281710.596 207.0111849.795207.5835
1899.509207.30752018.822210.35412078.479 212.638 2118.25211.74672148.078211.5962
2207.735215.89682227.621217.97442277.334220.3708 2297.22223.25632317.106223.7702
#Mann= 3 , 0 , 0
       0     .05       0 1364.22    .035       01521.684     .05       0
Bank Sta=1364.22,1521.684
XS Rating Curve= 0 ,0
Exp/Cntr=0.3,0.1

Chan Stop Cuts=-1
Use User Specified Reach Order=0
Composite Channel Slope=5