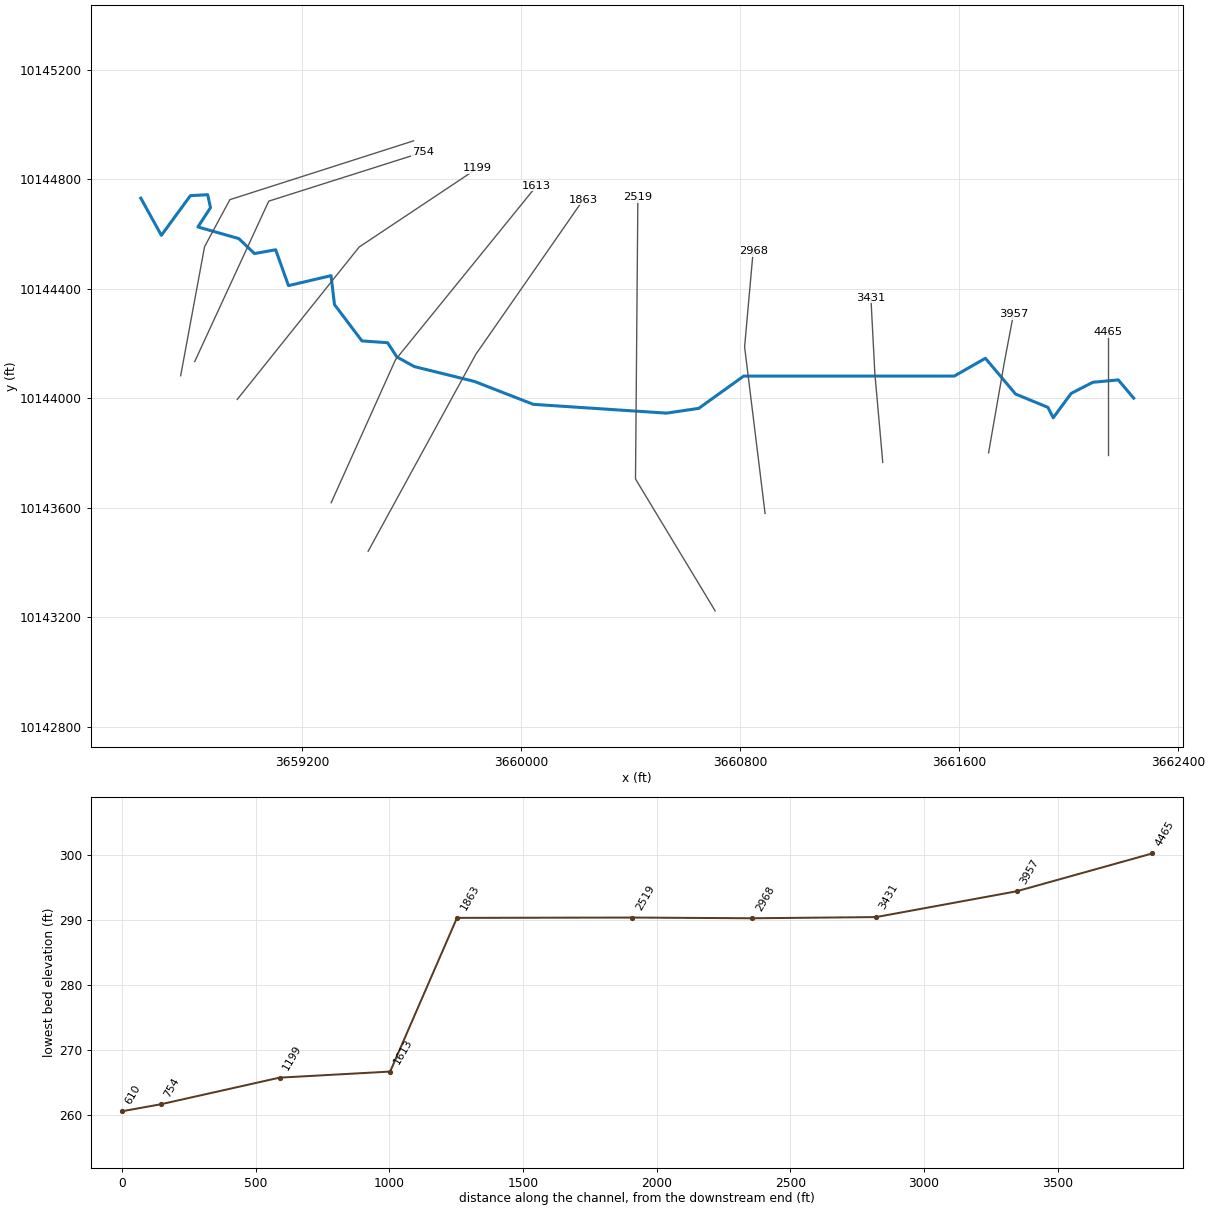
--- UNT082 IN ROCK.prj (project) ---

Proj Title=UNT082 IN ROCK Base Level Engineering
Current Plan=p01
Default Exp/Contr=0.3,0.1
English Units
Geom File=g01
Flow File=f01
Plan File=p01
Y Axis Title=Elevation
X Axis Title(PF)=Main Channel Distance
X Axis Title(XS)=Station
BEGIN DESCRIPTION:
UNT082 IN ROCK
END DESCRIPTION:
DSS Export Rating Curves= 0
DSS Export Rating Curve Sorted= 0
DSS Export Volume Flow Curves= 0
DXF OffsetX= 0
DXF OffsetY= 0
DXF ScaleX= 1
DXF ScaleY= 10

--- UNT082 IN ROCK.p01 (plan) ---

Plan Title=Multiple Run
Short Identifier=Multiple
Geom File=g01
Flow File=f01
Subcritical Flow
K Sum by GR= 0
Std Step Tol= 0.01
Critical Tol= 0.01
Num of Std Step Trials= 20
Max Error Tol= 0.3
Flow Tol Ratio= 0.001
Split Flow NTrial= 30
Split Flow Tol= 0.02
Split Flow Ratio= 0.02
Log Output Level= 0
Friction Slope Method= 1
Unsteady Friction Slope Method= 2
Unsteady Bridges Friction Slope Method= 1
Parabolic Critical Depth
Global Vel Dist=  1 , 1 , 1
Global Log Level= 0
CheckData=True
Encroach Param= -1, 0, 0, 0
BEGIN DESCRIPTION:
Multiple Run
END DESCRIPTION:

--- UNT082 IN ROCK.f01 (steady flow) ---

Flow Title=Multiple
Number of Profiles=7
Profile Names=10-year,25-year,50-year,1pct_min,100-year,1pct_plu,500-year
River Rch & RM= UNT082 IN ROCK,Reach-1,4465
     509     681     822     729     986    1333    1416
Boundary for River Rch & Prof#=UNT082 IN ROCK,Reach-1,1
Up Type=0
Dn Type=3
Dn Slope=0.005
Boundary for River Rch & Prof#=UNT082 IN ROCK,Reach-1,2
Up Type=0
Dn Type=3
Dn Slope=0.005
Boundary for River Rch & Prof#=UNT082 IN ROCK,Reach-1,3
Up Type=0
Dn Type=3
Dn Slope=0.005
Boundary for River Rch & Prof#=UNT082 IN ROCK,Reach-1,4
Up Type=0
Dn Type=3
Dn Slope=0.005
Boundary for River Rch & Prof#=UNT082 IN ROCK,Reach-1,5
Up Type=0
Dn Type=3
Dn Slope=0.005
Boundary for River Rch & Prof#=UNT082 IN ROCK,Reach-1,6
Up Type=0
Dn Type=3
Dn Slope=0.005
Boundary for River Rch & Prof#=UNT082 IN ROCK,Reach-1,7
Up Type=0
Dn Type=3
Dn Slope=0.005

--- UNT082 IN ROCK.g01 (geometry) ---

Geom Title=Existing Conditions
Program Version=4.10

River Reach=UNT082 IN ROCK  ,Reach-1
Reach XY= 30
      3662237.21     10144000.88      3662181.01     10144067.64
      3662088.04     10144059.07      3662008.63     10144018.19
      3661943.35     10143929.32      3661924.01     10143967.34
      3661805.88     10144016.04      3661695.84     10144146.63
      3661582.18     10144081.74       3660813.2     10144081.62
      3660649.14     10143963.67      3660531.09     10143946.31
      3660044.98     10143978.43      3659830.31     10144062.07
      3659610.85     10144116.33      3659547.05     10144151.49
       3659513.2     10144203.57      3659419.45     10144210.08
      3659319.19     10144342.89      3659306.67     10144448.57
      3659151.28     10144412.11      3659104.41     10144543.19
      3659027.15      10144529.3      3658969.86     10144583.98
      3658820.55     10144626.52      3658866.56     10144696.83
      3658856.23     10144744.33      3658793.06     10144740.76
      3658687.15     10144595.88      3658612.11     10144731.64

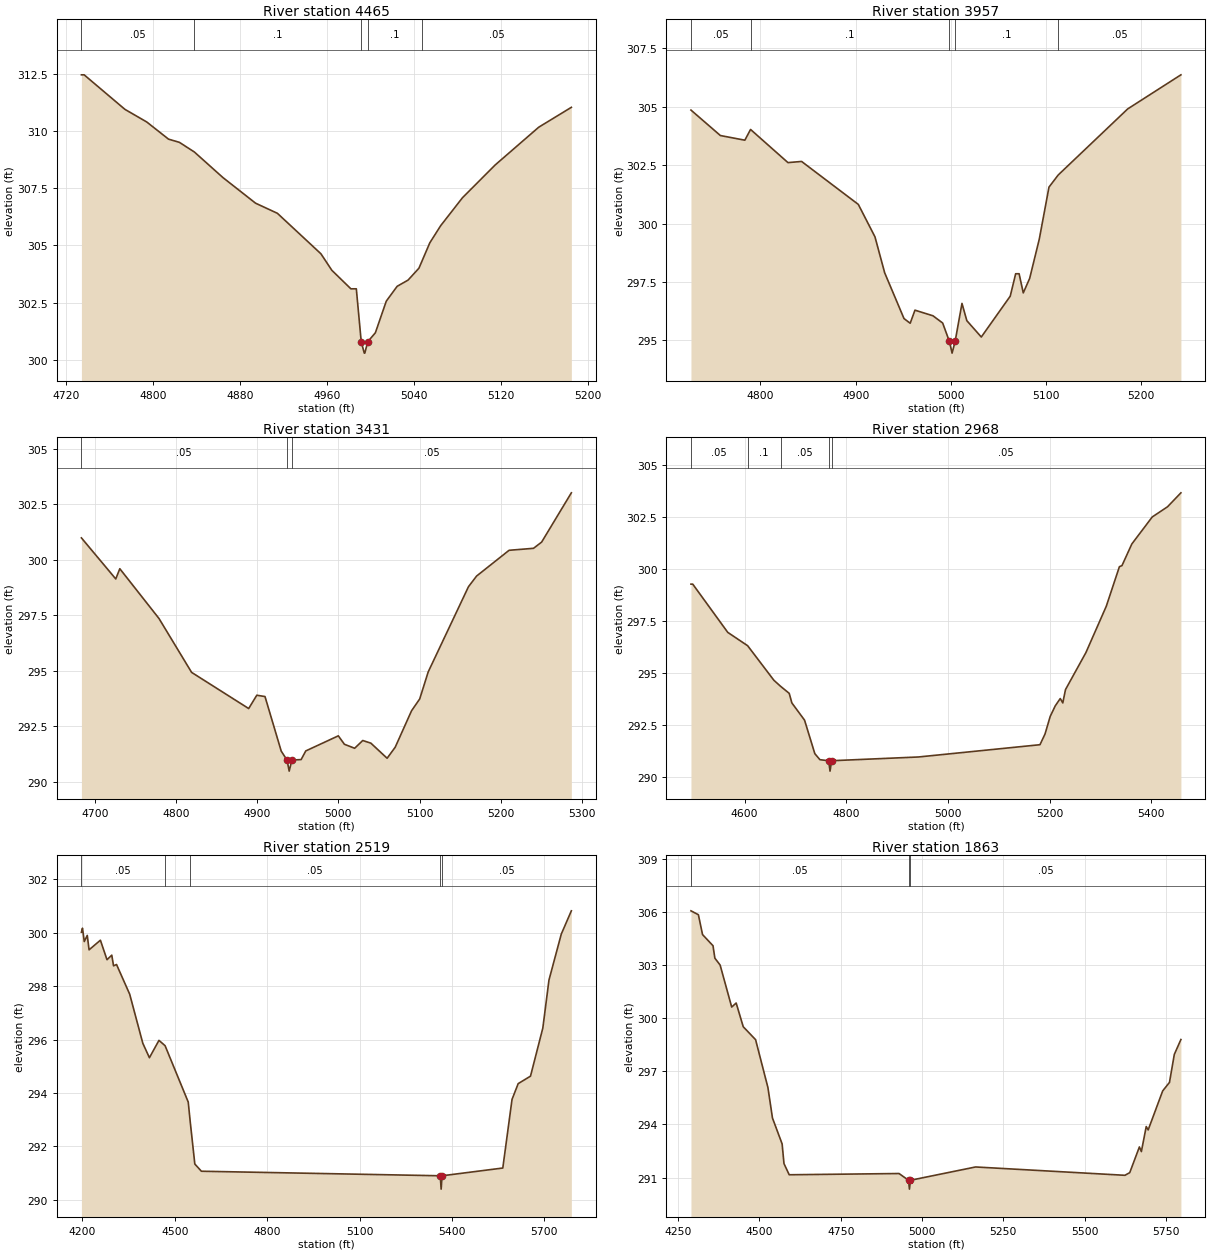
Type RM Length L Ch R = 1 ,4465    ,508,508,508
BEGIN DESCRIPTION:
UNT082 IN ROCK 9.0
END DESCRIPTION:
XS GIS Cut Line= 3
      3662142.11     10143791.63      3662142.11     10144041.64
      3662142.11     10144241.63
#Sta/Elev= 30
  4734.4  312.45  4736.9  312.45  4774.4  310.94  4794.4  310.39  4814.4  309.64
  4824.4   309.5  4838.1  309.08  4864.4  307.96  4894.4  306.84  4914.4   306.4
  4954.4  304.63  4964.4  303.91  4981.9   303.1  4986.9   303.1  4991.4  300.79
  4994.2  300.29  4994.7  300.29  4997.4  300.79  5004.4  301.18  5014.4  302.56
  5024.4  303.21  5034.4  303.48  5044.4     304  5047.2  304.31  5054.4  305.11
  5064.4  305.86  5084.4  307.08  5114.4  308.51  5154.4  310.16  5184.4  311.03
#Mann= 5 ,-1 , 0
  4734.4     .05       0  4838.1      .1       0  4991.4     .07       0
  4997.4      .1       0  5047.2     .05       0
Bank Sta=4991.4,4997.4
XS Rating Curve= 0 ,0
Exp/Cntr=0.3,0.1

Type RM Length L Ch R = 1 ,3957    ,526,526,526
BEGIN DESCRIPTION:
UNT082 IN ROCK 8.0
END DESCRIPTION:
XS GIS Cut Line= 3
      3661707.32     10143801.21      3661766.02     10144137.91
      3661798.23     10144307.81
#Sta/Elev= 30
    4727  304.86  4757.9  303.77  4783.6  303.57  4789.6  304.03  4828.9  302.61
  4843.2  302.66  4902.8  300.82  4920.3  299.43  4930.5  297.89  4950.8  295.93
  4957.3  295.73  4962.3  296.29  4981.2  296.05  4991.4  295.74  4998.5  294.95
  5001.3  294.45  5004.5  294.95  5011.7  296.58  5016.8  295.84    5032  295.14
  5062.4  296.89  5068.1  297.85  5071.7  297.85  5076.1  297.03  5082.8  297.65
  5092.9  299.33  5103.1  301.56  5112.8  302.08  5185.8  304.91  5241.7  306.37
#Mann= 5 ,-1 , 0
    4727     .05       0  4789.6      .1       0  4998.5     .07       0
  5004.5      .1       0  5112.8     .05       0
Bank Sta=4998.5,5004.5
XS Rating Curve= 0 ,0
Exp/Cntr=0.3,0.1

Type RM Length L Ch R = 1 ,3431    ,463,463,463
BEGIN DESCRIPTION:
UNT082 IN ROCK 7.0
END DESCRIPTION:
XS GIS Cut Line= 3
      3661321.02     10143766.48      3661292.11     10144091.64
       3661277.7     10144368.22
#Sta/Elev= 30
  4683.6  300.98  4725.9  299.13  4730.9  299.59  4779.1  297.35  4819.3  294.92
  4889.6  293.29  4899.6  293.89  4909.7  293.83  4929.7  291.37  4936.8  290.97
  4939.5  290.47  4942.8  290.97  4954.2  290.99  4959.9  291.38    5000  292.06
  5007.5  291.68  5020.1   291.5  5030.1  291.85  5040.1  291.73  5060.1  291.05
  5070.1  291.55  5090.2  293.19  5100.2  293.72  5110.7  294.94  5160.3  298.78
  5170.3  299.26  5210.3  300.42  5240.4  300.51  5250.4  300.79    5287  303.01
#Mann= 3 ,-1 , 0
  4683.6     .05       0  4936.8    .033       0  4942.8     .05       0
Bank Sta=4936.8,4942.8
XS Rating Curve= 0 ,0
Exp/Cntr=0.3,0.1

Type RM Length L Ch R = 1 ,2968    ,449,449,449
BEGIN DESCRIPTION:
UNT082 IN ROCK 6.0
END DESCRIPTION:
XS GIS Cut Line= 3
      3660891.34     10143579.81      3660816.58     10144188.37
      3660847.83     10144537.84
#Sta/Elev= 30
  4494.4  299.28  4497.9  299.28  4566.8  296.96  4605.9  296.32  4657.5  294.66
  4670.6  294.37  4687.7  294.03  4692.9  293.57  4717.9  292.74  4738.1  291.13
  4748.1  290.84  4765.3  290.79    4768  290.29  4771.3  290.79  4941.9  290.97
  5181.1  291.56  5191.1  292.08  5201.2  292.92  5211.2  293.43    5221  293.78
    5226  293.57  5231.3  294.21  5271.5  295.99  5311.6  298.22  5337.4  300.12
  5342.4  300.17  5361.8  301.21    5402  302.51  5432.1     303  5458.4  303.67
#Mann= 5 ,-1 , 0
  4494.4     .05       0  4605.9      .1       0  4670.6     .05       0
  4765.3    .033       0  4771.3     .05       0
Bank Sta=4765.3,4771.3
XS Rating Curve= 0 ,0
Exp/Cntr=0.3,0.1

Type RM Length L Ch R = 1 ,2519    ,656,656,656
BEGIN DESCRIPTION:
UNT082 IN ROCK 5.0
END DESCRIPTION:
XS GIS Cut Line= 3
      3660709.06     10143223.89      3660418.25     10143705.69
      3660426.93     10144734.38
#Sta/Elev= 30
  4196.6  300.02  4200.1  300.17  4205.9  299.67  4215.6   299.9  4221.5  299.36
  4258.3  299.72  4279.7  298.99  4295.2  299.16    4301  298.76  4310.7  298.81
  4353.4   297.7  4396.1  295.86  4417.5  295.32  4448.5  295.97  4468.4  295.77
  4543.6  293.66  4549.9  292.94    4565  291.34  4586.3  291.07  5362.3   290.9
  5365.1   290.4  5368.3   290.9  5565.4  291.19  5595.4  293.76  5615.4  294.35
  5655.4  294.63  5695.4  296.43  5715.4  298.23  5755.4  299.95  5788.1  300.82
#Mann= 5 ,-1 , 0
  4196.6     .05       0  4468.4      .1       0  4549.9     .05       0
  5362.3    .033       0  5368.3     .05       0
Bank Sta=5362.3,5368.3
XS Rating Curve= 0 ,0
Exp/Cntr=0.3,0.1

Type RM Length L Ch R = 1 ,1863    ,250,250,250
BEGIN DESCRIPTION:
UNT082 IN ROCK 4.0
END DESCRIPTION:
XS GIS Cut Line= 3
      3659442.11     10143441.64      3659834.95     10144160.65
      3660227.17      10144725.5
#Sta/Elev= 30
  4289.5  306.05  4312.3  305.83  4325.1  304.71  4357.3  304.08    4363  303.38
  4379.2  302.99  4414.8  300.62  4428.5  300.85  4450.3  299.51  4488.3  298.78
  4526.2  296.08  4540.2  294.36  4569.9   292.9  4575.6  291.79  4591.7  291.16
  4929.5  291.23  4958.7  290.85  4961.5  290.35  4964.7  290.85    5165   291.6
  5624.3  291.13  5639.1  291.28  5668.8  292.73  5674.9  292.47  5689.8  293.88
  5695.8  293.69  5740.4  295.89  5761.3  296.37  5776.2  297.95  5796.5  298.79
#Mann= 3 ,-1 , 0
  4289.5     .05       0  4958.7    .033       0  4964.7     .05       0
Bank Sta=4958.7,4964.7
XS Rating Curve= 0 ,0
Exp/Cntr=0.3,0.1

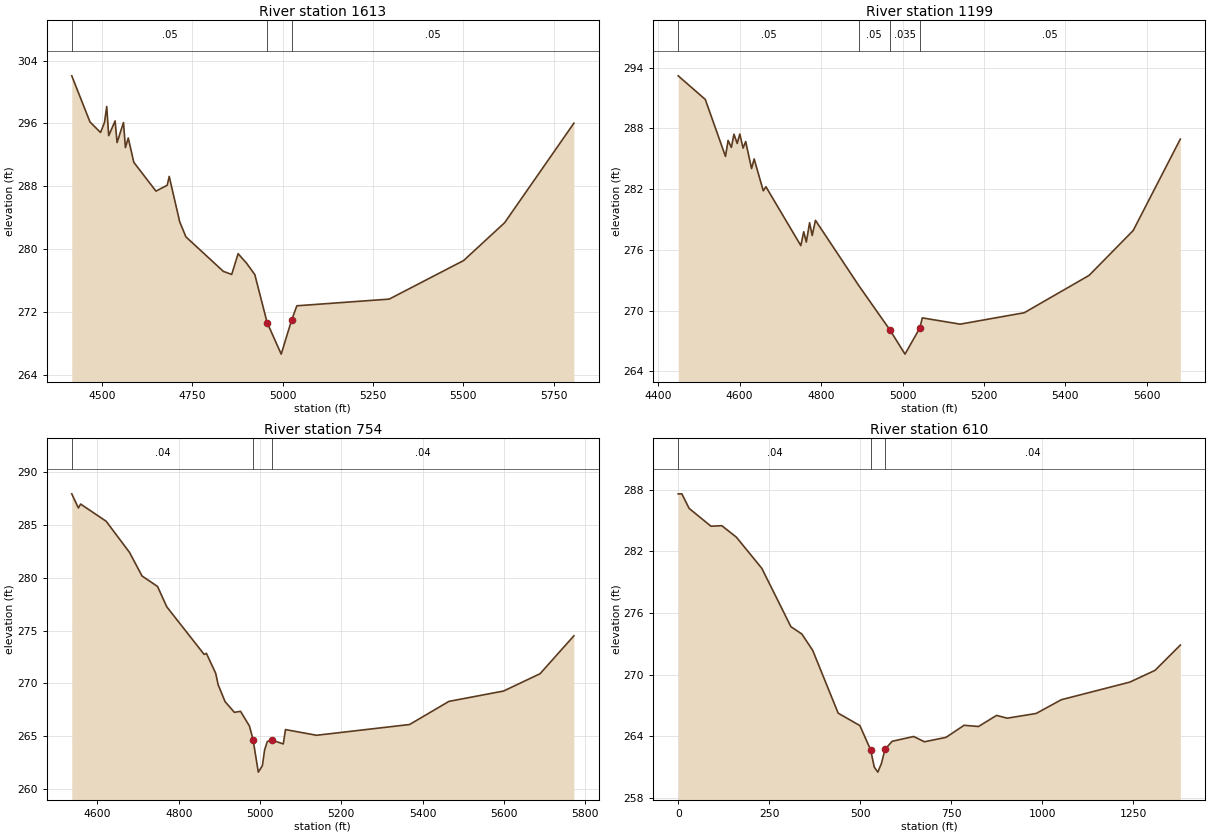
Type RM Length L Ch R = 1 ,1613    ,414,414,414
BEGIN DESCRIPTION:
UNT082 IN ROCK 3.0
END DESCRIPTION:
XS GIS Cut Line= 3
      3659307.15     10143618.91      3659542.11     10144141.64
      3660057.11     10144776.64
#Sta/Elev= 30
  4415.7  302.06  4466.2  296.19  4495.4  294.85  4506.4  296.14  4512.5  298.16
    4518  294.45  4535.7  296.32  4541.2  293.57  4558.9  296.11  4564.3  292.93
  4572.2  294.15  4587.5  291.06  4648.9  287.39  4680.1  288.14  4685.6  289.26
  4714.7  283.48  4731.9  281.57  4835.5  277.18  4858.7  276.79  4876.4  279.43
  4899.5  278.24  4922.7  276.77  4956.8  270.67  4995.8  266.65  5024.8  271.01
  5039.1   272.8  5294.9  273.65  5501.1  278.56  5614.6  283.37  5806.4  296.03
#Mann= 3 , 0 , 0
  4415.7     .05       0  4956.8     .03       0  5024.8     .05       0
Bank Sta=4956.8,5024.8
XS Rating Curve= 0 ,0
Exp/Cntr=0.3,0.1

Type RM Length L Ch R = 1 ,1199    ,445,445,445
BEGIN DESCRIPTION:
UNT082 IN ROCK 2.0
END DESCRIPTION:
XS GIS Cut Line= 3
      3658964.23     10143996.46       3659409.2     10144553.04
      3659842.13     10144841.66
#Sta/Elev= 30
  4449.2   293.2  4515.7  290.87  4565.3  285.24  4571.7  286.82  4579.7  286.13
  4586.1  287.43  4594.1  286.52  4600.5  287.45  4608.5  286.06  4614.9  286.71
  4629.3  284.04  4635.7  284.99  4658.1  281.84  4664.5  282.25  4750.3  276.43
  4757.4   277.8  4763.8  276.78  4771.8  278.69  4778.2  277.43  4786.2  278.93
  4892.3   272.5 4968.75  268.12  5006.1  265.71  5042.3  268.28  5048.7  269.29
  5141.6  268.67    5299   269.8  5458.2  273.49  5566.4  277.92  5682.1  286.95
#Mann= 4 ,-1 , 0
  4449.2     .05       0  4892.3     .05       0 4968.75    .035       0
  5042.3     .05       0
Bank Sta=4968.75,5042.3
XS Rating Curve= 0 ,0
Exp/Cntr=0.3,0.1

Type RM Length L Ch R = 1 ,754     ,144,144,144
BEGIN DESCRIPTION:
UNT082 IN ROCK 1.0
END DESCRIPTION:
XS GIS Cut Line= 3
      3658808.94     10144134.71      3659079.19     10144720.77
      3659641.36     10144899.28
#Sta/Elev= 30
  4536.8  287.96  4553.1  286.62  4558.6  286.99  4621.5  285.36  4678.9  282.41
  4709.6  280.18  4747.7  279.19  4770.7  277.25  4862.5  272.75    4868  272.85
    4891  270.95  4896.8  269.89  4913.9  268.28  4936.9  267.26  4951.9  267.36
  4973.9  265.97  4982.8  264.68  4995.7   261.6  5005.7  262.21  5011.2  263.71
  5017.9   264.5  5028.7  264.64  5057.1  264.27  5062.6  265.63  5139.1  265.09
  5367.8  266.11  5464.6   268.3  5598.9  269.28  5688.8  270.92    5772  274.51
#Mann= 3 , 0 , 0
  4536.8     .04       0  4982.8     .03       0  5028.7     .04       0
Bank Sta=4982.8,5028.7
XS Rating Curve= 0 ,0
Exp/Cntr=0.3,0.1

Type RM Length L Ch R = 1 ,610     ,0,0,0
XS GIS Cut Line= 4
     3658757.642    10144082.996     3658844.882    10144554.351
      3658937.33    10144726.226 3659607.902767510144941.0689255
#Sta/Elev= 30
       0287.59169.981754287.601129.94526 286.18789.83578284.4542119.7811284.5001
159.7081283.3858229.5804280.3547309.4344274.6792339.3796273.9699369.3249272.3743
439.1972266.2684498.8167265.0593528.3554262.6962538.2017261.0334548.0479260.5333
557.8941261.3678567.7404 262.752587.4328263.5327646.5103263.9985 676.049263.4848
735.4162263.9161784.8889 265.089 824.467264.9715873.9398266.0486903.6234265.7808
982.7797266.23911052.042267.57811240.038269.28941309.299270.43411378.561272.8917
#Mann= 3 , 0 , 0
       0     .04       0528.3554    .035       0567.7404     .04       0
Bank Sta=528.3554,567.7404
XS Rating Curve= 0 ,0
Exp/Cntr=0.3,0.1

Chan Stop Cuts=-1
Use User Specified Reach Order=0
Composite Channel Slope=5