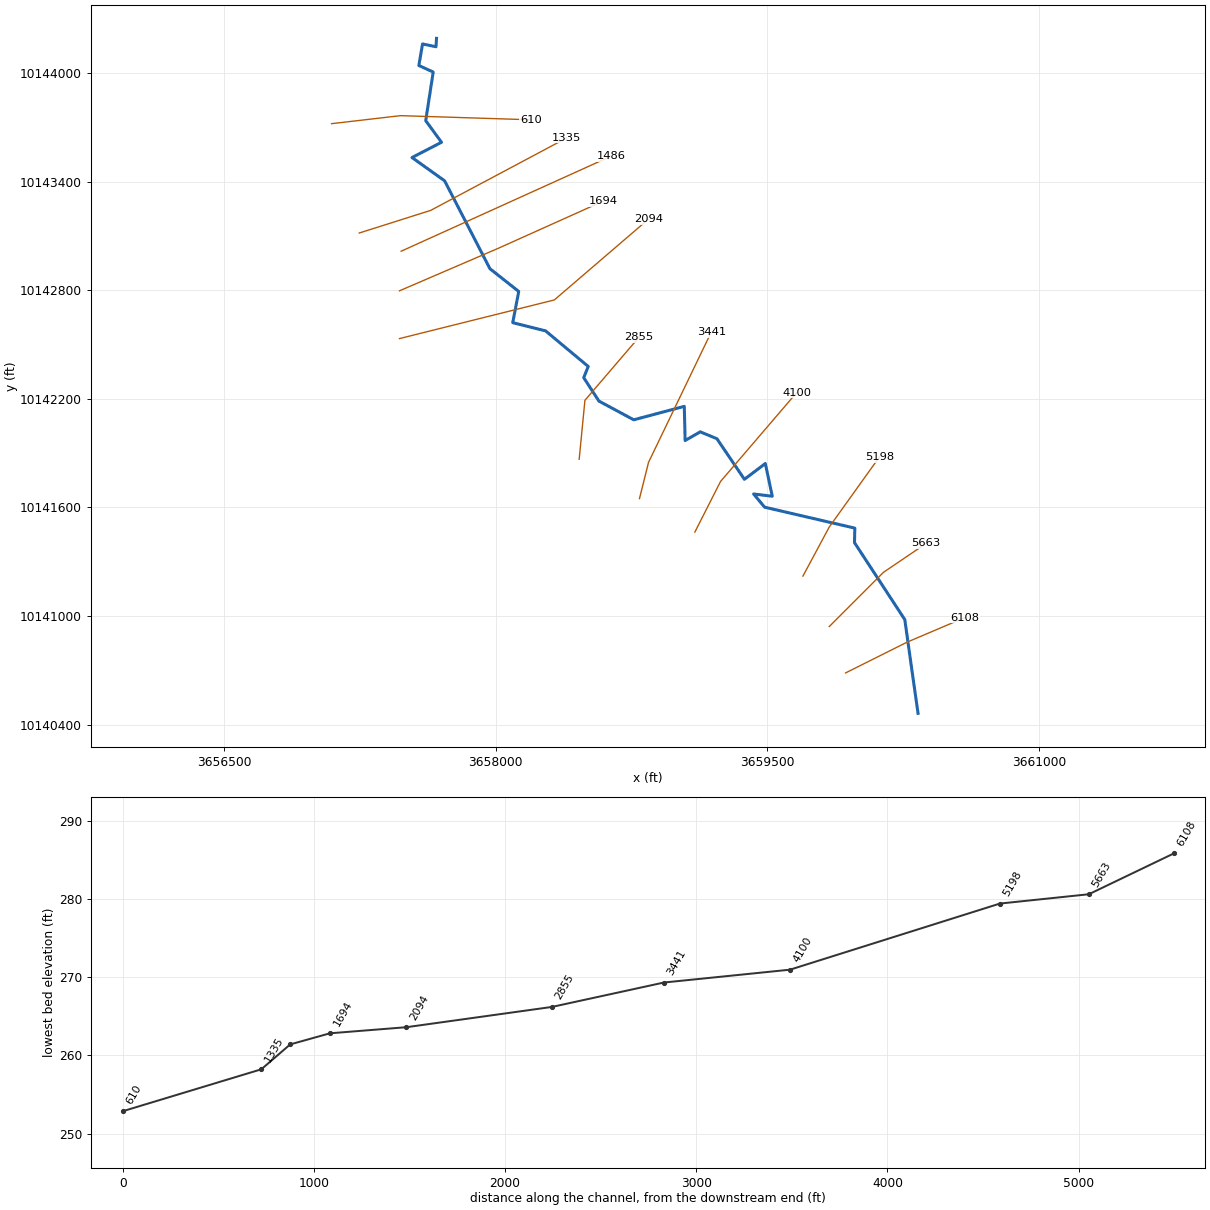
--- UNT084 IN ROCK.prj (project) ---

Proj Title=UNT084 IN ROCK Base Level Engineering
Current Plan=p01
Default Exp/Contr=0.3,0.1
English Units
Geom File=g01
Flow File=f01
Plan File=p01
Y Axis Title=Elevation
X Axis Title(PF)=Main Channel Distance
X Axis Title(XS)=Station
BEGIN DESCRIPTION:
UNT084 IN ROCK
END DESCRIPTION:
DSS Export Rating Curves= 0
DSS Export Rating Curve Sorted= 0
DSS Export Volume Flow Curves= 0
DXF OffsetX= 0
DXF OffsetY= 0
DXF ScaleX= 1
DXF ScaleY= 10

--- UNT084 IN ROCK.p01 (plan) ---

Plan Title=Multiple Run
Short Identifier=Multiple
Geom File=g01
Flow File=f01
Subcritical Flow
K Sum by GR= 0
Std Step Tol= 0.01
Critical Tol= 0.01
Num of Std Step Trials= 20
Max Error Tol= 0.3
Flow Tol Ratio= 0.001
Split Flow NTrial= 30
Split Flow Tol= 0.02
Split Flow Ratio= 0.02
Log Output Level= 0
Friction Slope Method= 1
Unsteady Friction Slope Method= 2
Unsteady Bridges Friction Slope Method= 1
Parabolic Critical Depth
Global Vel Dist=  1 , 1 , 1
Global Log Level= 0
CheckData=True
Encroach Param= -1, 0, 0, 0
BEGIN DESCRIPTION:
Multiple Run
END DESCRIPTION:

--- UNT084 IN ROCK.f01 (steady flow) ---

Flow Title=Multiple
Program Version=4.10
Number of Profiles= 7
Profile Names=10-year,25-year,50-year,1pct_min,100-year,1pct_plu,500-year
River Rch & RM=UNT084 IN ROCK,Reach-1         ,6108
     354     460     544     474     641     867     887
River Rch & RM=UNT084 IN ROCK,Reach-1         ,2094
     534     713     859     760    1028    1390    1470
Boundary for River Rch & Prof#=UNT084 IN ROCK,Reach-1         , 1
Up Type= 0
Dn Type= 3
Dn Slope=0.007
Boundary for River Rch & Prof#=UNT084 IN ROCK,Reach-1         , 2
Up Type= 0
Dn Type= 3
Dn Slope=0.007
Boundary for River Rch & Prof#=UNT084 IN ROCK,Reach-1         , 3
Up Type= 0
Dn Type= 3
Dn Slope=0.007
Boundary for River Rch & Prof#=UNT084 IN ROCK,Reach-1         , 4
Up Type= 0
Dn Type= 3
Dn Slope=0.007
Boundary for River Rch & Prof#=UNT084 IN ROCK,Reach-1         , 5
Up Type= 0
Dn Type= 3
Dn Slope=0.007
Boundary for River Rch & Prof#=UNT084 IN ROCK,Reach-1         , 6
Up Type= 0
Dn Type= 3
Dn Slope=0.007
Boundary for River Rch & Prof#=UNT084 IN ROCK,Reach-1         , 7
Up Type= 0
Dn Type= 3
Dn Slope=0.007
DSS Import GetInterval= 0
DSS Import GetPeak= 0
DSS Import FillOption= 0

--- UNT084 IN ROCK.g01 (geometry) ---

Geom Title=Existing Conditions
Program Version=4.10

River Reach=UNT084 IN ROCK  ,Reach-1
Reach XY= 30
      3660332.62     10140461.95       3660259.3     10140980.28
      3659981.55     10141405.27      3659983.37     10141485.48
      3659484.92     10141601.25      3659424.27     10141674.18
       3659527.2     10141661.72      3659488.91     10141842.47
      3659373.38     10141755.14      3659221.41     10141979.39
      3659129.06     10142017.57      3659045.81     10141969.17
      3659041.11      10142158.3      3658761.96     10142083.91
      3658569.57     10142187.36      3658485.39     10142316.74
      3658510.54     10142378.65      3658274.86     10142575.26
      3658093.28     10142620.76      3658126.45     10142793.02
      3657967.14     10142918.98      3657717.04     10143404.31
      3657536.82     10143532.97      3657699.78      10143617.4
       3657612.5     10143736.79       3657653.9     10144005.53
      3657574.47     10144041.47        3657595.     10144160.56
       3657669.4     10144145.16      3657672.11     10144191.64

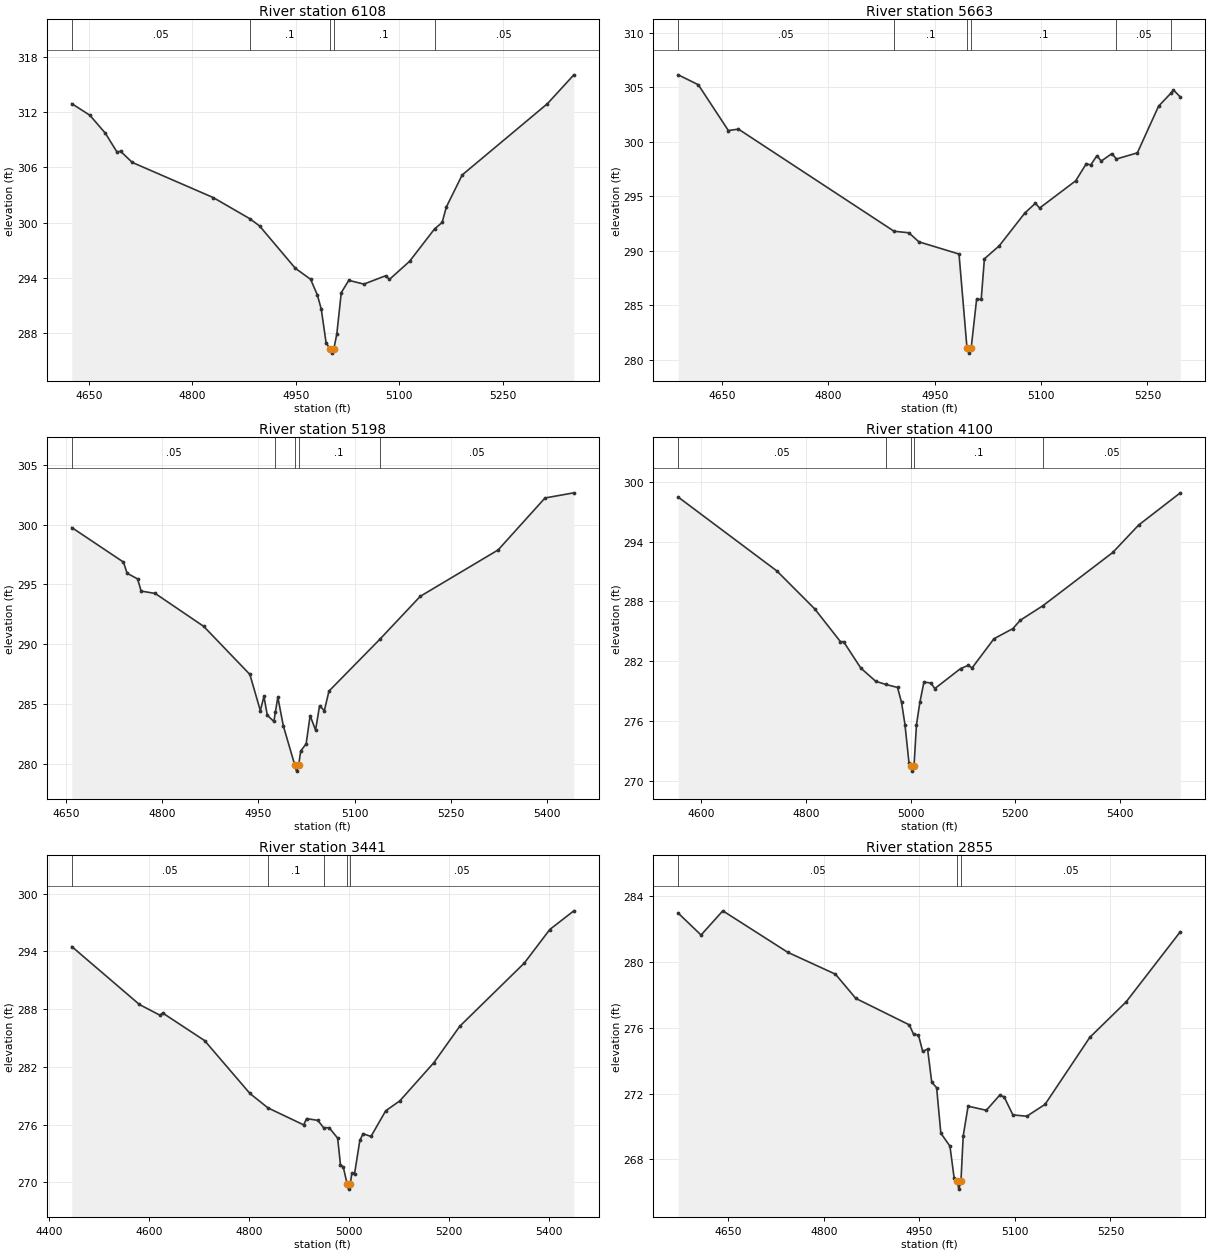
Type RM Length L Ch R = 1 ,6108    ,445,445,445
BEGIN DESCRIPTION:
UNT084 IN ROCK 12.0
END DESCRIPTION:
XS GIS Cut Line= 3
      3659932.59     10140685.43      3660271.91      10140855.3
      3660592.12     10140991.65
#Sta/Elev= 30
  4625.4  312.92  4651.6  311.66    4674  309.71  4690.7  307.69  4696.3  307.73
  4713.1  306.53  4830.5  302.71  4883.5  300.41  4897.5  299.63  4949.2  295.04
  4971.5  293.83  4981.3  292.12  4986.9   290.6  4993.9  286.94  4999.2  286.31
  5001.9  285.81  5005.2  286.31  5009.4  287.86  5015.9  292.38  5026.8  293.72
  5048.6  293.31  5080.3  294.22  5085.7  293.82  5114.8  295.78  5151.1  299.31
  5162.1  300.01  5168.1  301.68  5191.1  305.17  5314.7  312.92  5352.9  316.05
#Mann= 5 ,-1 , 0
  4625.4     .05       0  4883.5      .1       0  4999.2     .07       0
  5005.2      .1       0  5151.1     .05       0
Bank Sta=4999.2,5005.2
XS Rating Curve= 0 ,0
Exp/Cntr=0.3,0.1

Type RM Length L Ch R = 1 ,5663    ,465,465,465
BEGIN DESCRIPTION:
UNT084 IN ROCK 11.0
END DESCRIPTION:
XS GIS Cut Line= 3
      3659842.08     10140941.61      3660142.11     10141241.64
      3660377.11     10141400.75
#Sta/Elev= 30
  4588.3  306.12  4616.6  305.21    4659  301.01  4673.2  301.14  4892.7  291.77
  4913.6  291.63  4927.7   290.8  4984.3  289.68  4995.5  281.09  4998.2  280.59
  5001.5  281.09  5009.1  285.52  5015.6  285.52  5020.1  289.24  5041.1  290.44
    5077  293.43    5092  294.34    5098   293.9  5148.9   296.4  5163.9  297.98
  5169.9  297.84  5178.8   298.7  5184.9  298.21  5199.8  298.89  5206.4   298.4
  5235.8  298.96  5265.7  303.24  5283.6  304.47  5286.7  304.73  5296.4  304.09
#Mann= 6 ,-1 , 0
  4588.3     .05       0  4892.7      .1       0  4995.5     .07       0
  5001.5      .1       0  5206.4     .05       0  5283.6      .1       0
Bank Sta=4995.5,5001.5
XS Rating Curve= 0 ,0
Exp/Cntr=0.3,0.1

Type RM Length L Ch R = 1 ,5198    ,1098,1098,1098
BEGIN DESCRIPTION:
UNT084 IN ROCK 10.0
END DESCRIPTION:
XS GIS Cut Line= 3
      3659696.51     10141220.15      3659842.11     10141491.64
      3660118.97     10141878.26
#Sta/Elev= 30
  4658.6  299.76  4739.3  296.87  4744.9  295.94  4761.2  295.47  4766.9  294.45
  4788.8  294.25  4864.5   291.5  4936.6  287.48  4952.9  284.45  4958.5  285.64
  4963.8  284.07    4974  283.55  4976.5  284.37  4980.2  285.58  4988.8  283.18
  5006.7   279.9  5009.4   279.4  5012.7   279.9  5015.9  281.08  5024.4  281.68
  5030.6  284.04  5039.1  282.83  5045.3  284.85  5052.8  284.46    5060  286.09
  5139.4  290.42  5202.5  294.01  5324.1  297.89  5397.2  302.23  5442.2  302.66
#Mann= 5 ,-1 , 0
  4658.6     .05       0  4976.5      .1       0  5006.7     .07       0
  5012.7      .1       0  5139.4     .05       0
Bank Sta=5006.7,5012.7
XS Rating Curve= 0 ,0
Exp/Cntr=0.3,0.1

Type RM Length L Ch R = 1 ,4100    ,659,659,659
BEGIN DESCRIPTION:
UNT084 IN ROCK 9.0
END DESCRIPTION:
XS GIS Cut Line= 3
      3659099.32     10141463.26      3659241.37     10141743.13
      3659661.79     10142234.05
#Sta/Elev= 30
  4555.6  298.46  4744.2  291.05  4816.6  287.24  4865.8  283.95  4871.8  283.95
  4904.7   281.3  4933.3  279.97  4952.1  279.66    4975  279.35  4982.7  277.84
  4989.2  275.63  4996.9  271.78  5000.5  271.45  5003.3  270.95  5006.5  271.45
  5011.2   275.6  5017.8  277.88  5025.5  279.89  5038.7   279.8  5046.3  279.24
  5095.7  281.25    5110  281.56  5117.7  281.32  5159.4  284.24  5195.6  285.26
  5209.8   286.1  5253.1  287.56  5386.6   292.9    5436  295.65  5515.8  298.89
#Mann= 5 ,-1 , 0
  4555.6     .05       0  4952.1      .1       0  5000.5     .07       0
  5006.5      .1       0  5253.1     .05       0
Bank Sta=5000.5,5006.5
XS Rating Curve= 0 ,0
Exp/Cntr=0.3,0.1

Type RM Length L Ch R = 1 ,3441    ,586,586,586
BEGIN DESCRIPTION:
UNT084 IN ROCK 7.0
END DESCRIPTION:
XS GIS Cut Line= 3
      3658793.51     10141648.63      3658843.49     10141848.59
      3659189.41     10142567.04
#Sta/Elev= 30
  4445.7  294.51  4580.9  288.49  4622.2  287.37  4627.3  287.61  4711.2  284.74
  4801.7  279.25  4837.8  277.75  4909.3  275.98  4914.9  276.64  4937.5  276.45
    4949  275.69  4960.1  275.69  4977.1  274.61  4982.7  271.85  4988.3  271.61
  4996.3  269.81    4999  269.31  5002.3  269.81  5005.4  270.94  5010.9  270.91
  5021.5  274.38    5028  275.07  5043.7  274.78  5073.2  277.45  5101.4  278.48
  5169.3  282.44  5221.2  286.23  5350.3   292.8  5401.1  296.28  5449.2  298.22
#Mann= 5 ,-1 , 0
  4445.7     .05       0  4837.8      .1       0    4949     .05       0
  4996.3     .03       0  5002.3     .05       0
Bank Sta=4996.3,5002.3
XS Rating Curve= 0 ,0
Exp/Cntr=0.3,0.1

Type RM Length L Ch R = 1 ,2855    ,761,761,761
BEGIN DESCRIPTION:
UNT084 IN ROCK 6.0
END DESCRIPTION:
XS GIS Cut Line= 3
      3658460.41     10141866.03      3658492.11     10142191.64
      3658792.08     10142541.62
#Sta/Elev= 30
  4571.5  282.96  4607.3  281.63  4641.5   283.1  4743.4  280.58  4818.3  279.25
  4850.2  277.78  4934.3  276.17  4940.9   275.6  4948.6  275.55  4955.2  274.56
  4962.9   274.7  4969.4  272.69  4977.1  272.35  4983.7  269.59    4998   268.8
  5004.6  266.86  5009.3  266.69    5012  266.19  5015.3  266.69  5018.8  269.42
  5026.5  271.23  5055.1  270.98  5075.9  271.89    5083   271.8  5096.8   270.7
  5118.7  270.62  5147.3  271.34  5217.5  275.41  5274.6  277.57  5359.6  281.83
#Mann= 3 ,-1 , 0
  4571.5     .05       0  5009.3     .03       0  5015.3     .05       0
Bank Sta=5009.3,5015.3
XS Rating Curve= 0 ,0
Exp/Cntr=0.3,0.1

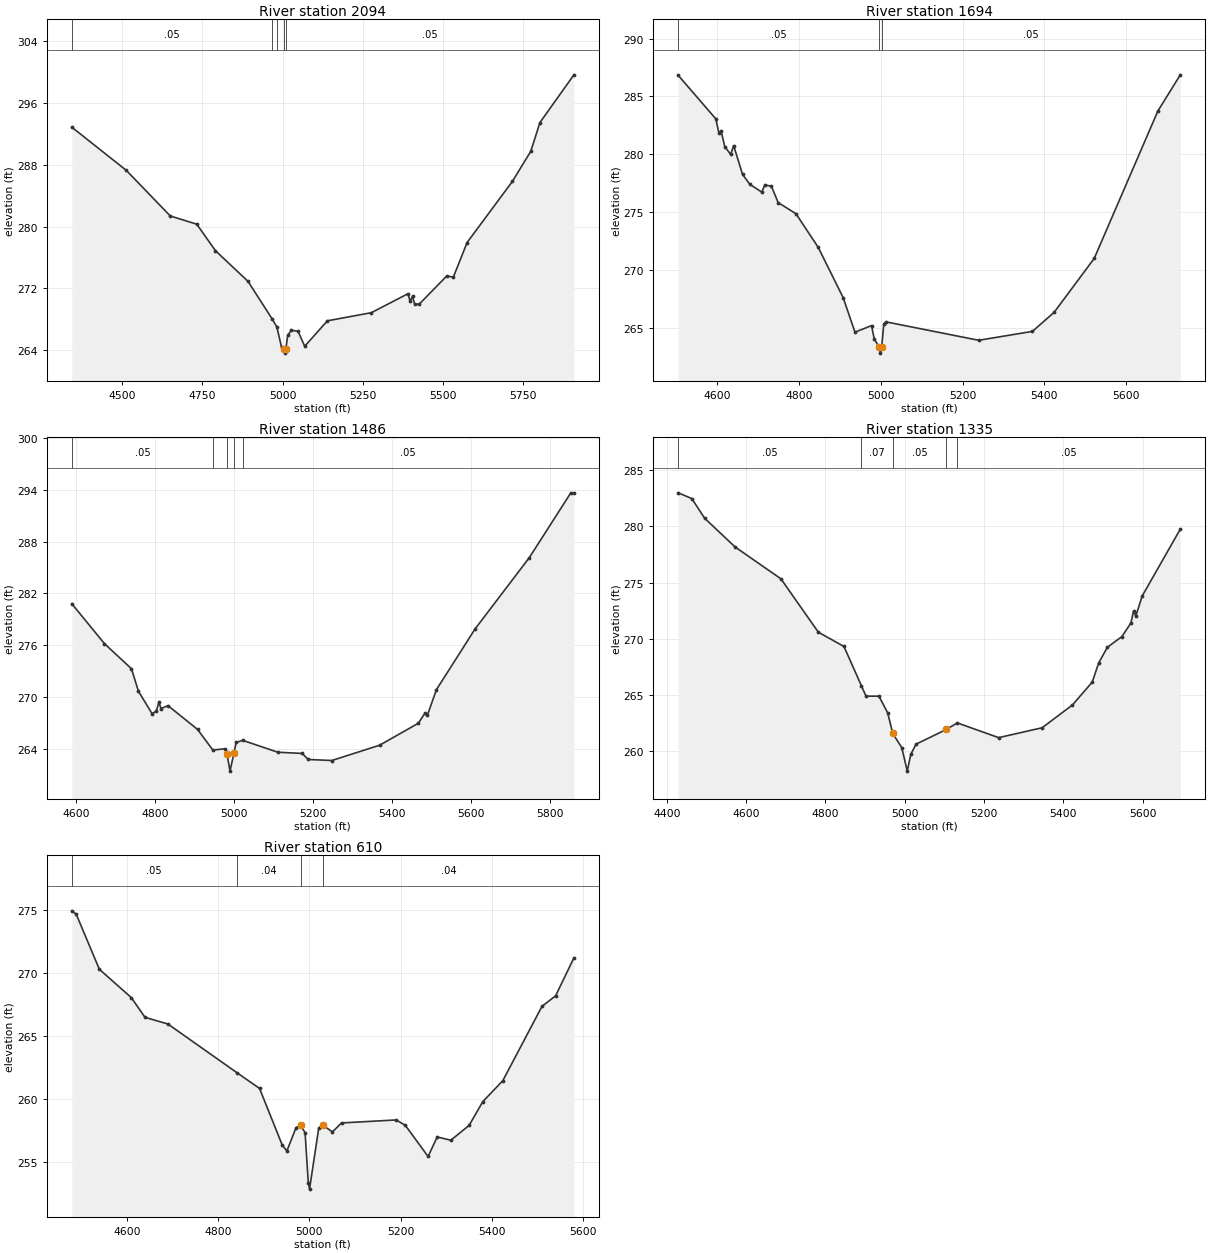
Type RM Length L Ch R = 1 ,2094    ,400,400,400
BEGIN DESCRIPTION:
UNT084 IN ROCK 5.0
END DESCRIPTION:
XS GIS Cut Line= 3
      3657467.37     10142532.67      3658323.14     10142746.25
       3658842.1     10143191.64
#Sta/Elev= 30
  4342.8  292.88  4512.6  287.29    4650  281.37  4732.5  280.31  4790.9  276.87
  4892.4   272.9  4967.7  268.03  4982.5  266.98    4997  264.35  5004.3   264.1
  5007.1   263.6  5010.3   264.1  5016.2  265.92  5027.9  266.57  5048.5  266.42
  5069.2  264.49    5140  267.79  5277.1  268.84  5391.3   271.3  5397.8  270.32
  5405.5  270.97  5412.1  269.92  5426.4  269.95    5512  273.59  5532.8  273.45
  5575.6  277.93  5717.2  285.87  5774.3  289.76  5802.8  293.48  5908.7  299.66
#Mann= 5 ,-1 , 0
  4342.8     .05       0  4967.7     .12       0  4982.5     .05       0
  5004.3     .03       0  5010.3     .05       0
Bank Sta=5004.3,5010.3
XS Rating Curve= 0 ,0
Exp/Cntr=0.3,0.1

Type RM Length L Ch R = 1 ,1694    ,208,208,208
BEGIN DESCRIPTION:
UNT084 IN ROCK 4.0
END DESCRIPTION:
XS GIS Cut Line= 3
      3657467.38     10142796.57      3658015.97     10143032.67
      3658592.11     10143291.64
#Sta/Elev= 30
  4503.9  286.83  4596.1  283.06  4603.4  281.87  4608.9  282.03  4617.9  280.67
  4632.4  279.99  4639.7  280.75  4661.5  278.26  4679.5   277.4  4708.4  276.74
  4715.9  277.35    4732  277.25  4748.6  275.83  4792.1  274.87  4846.5  271.97
  4907.6  267.62  4936.6  264.63  4977.2   265.2  4983.7  264.05  4995.9  263.32
  4998.7  262.82  5001.9  263.32  5007.2  265.35  5012.6  265.52  5239.4  263.93
    5371   264.7  5424.1  266.35  5522.2  271.01    5678  283.75  5732.8  286.87
#Mann= 3 ,-1 , 0
  4503.9     .05       0  4995.9     .03       0  5001.9     .05       0
Bank Sta=4995.9,5001.9
XS Rating Curve= 0 ,0
Exp/Cntr=0.3,0.1

Type RM Length L Ch R = 1 ,1486    ,151,151,151
BEGIN DESCRIPTION:
Mapping XS ef69b9f1
END DESCRIPTION:
XS GIS Cut Line= 2
       3657476.9     10143015.43      3658634.93     10143539.75
#Sta/Elev= 30
  4589.8   280.8  4672.4  276.18    4741  273.26  4758.6  270.65  4793.1  268.06
  4804.1  268.36  4810.3  269.41  4815.7  268.65  4833.4  268.99  4908.1  266.24
    4947  263.84  4977.4  263.99  4982.9  263.35  4990.4   261.4  5000.5  263.53
    5006  264.72  5022.4  264.97  5111.4  263.59  5173.2  263.45  5188.3  262.75
    5248  262.63    5369   264.4  5466.9  266.94  5484.5  268.15    5490  267.87
  5513.1  270.85    5611  277.89  5748.1  286.14  5852.9  293.63    5861  293.65
#Mann= 5 ,-1 , 0
  4589.8     .05       0    4947     .12       0  4982.9     .07       0
  5000.5     .12       0  5022.4     .05       0
Bank Sta=4982.9,5000.5
XS Rating Curve= 0 ,0
Exp/Cntr=0.3,0.1

Type RM Length L Ch R = 1 ,1335    ,725,725,725
BEGIN DESCRIPTION:
UNT084 IN ROCK 3.0
END DESCRIPTION:
XS GIS Cut Line= 3
      3657245.14       10143116.      3657639.72     10143240.94
      3658392.09     10143641.63
#Sta/Elev= 30
  4428.7  282.98  4463.1  282.47  4495.4  280.72  4572.4  278.16  4687.8  275.33
  4782.2  270.58  4846.8  269.31  4890.6  265.83  4902.4  264.89    4935  264.89
    4957  263.41  4969.9  261.57  4992.6  260.31  5006.4  258.22  5015.2   259.7
  5028.6  260.62  5105.1  261.93  5132.7  262.51  5236.9   261.2  5346.7  262.08
  5423.1  264.11  5472.9  266.14  5489.2  267.85  5511.1  269.24  5547.7  270.19
  5570.4   271.4    5577  272.45  5582.7  272.02    5599  273.81    5695  279.75
#Mann= 5 ,-1 , 0
  4428.7     .05       0  4890.6     .07       0  4969.9     .05       0
  5105.1     .07       0  5132.7     .05       0
Bank Sta=4969.9,5105.1
XS Rating Curve= 0 ,0
Exp/Cntr=0.3,0.1

Type RM Length L Ch R = 1 ,610     ,0,0,0
BEGIN DESCRIPTION:
UNT084 IN ROCK 1.0
END DESCRIPTION:
XS GIS Cut Line= 3
      3657092.37     10143720.17       3657473.8      10143764.5
      3658192.14     10143741.64
#Sta/Elev= 30
  4478.1  274.94  4487.9  274.67  4538.7   270.3  4608.7  268.06  4638.9  266.49
  4689.2  265.96  4840.3  262.11  4890.4  260.85  4940.4  256.35  4950.5  255.89
  4970.5  257.73  4980.5  257.91  4990.5  257.34  4997.5  253.36  5000.2  252.86
  5020.5  257.72  5030.5  257.91  5050.5   257.4  5070.5  258.11  5190.6  258.35
  5210.6  257.92  5260.6  255.45  5280.6     257  5310.6  256.74  5350.7  257.92
  5380.7   259.8  5424.6  261.46  5510.7  267.36  5540.7   268.2  5580.8  271.21
#Mann= 4 ,-1 , 0
  4478.1     .05       0  4840.3     .04       0  4980.5    .035       0
  5030.5     .04       0
Bank Sta=4980.5,5030.5
XS Rating Curve= 0 ,0
Exp/Cntr=0.3,0.1

Chan Stop Cuts=-1
Use User Specified Reach Order=0
Composite Channel Slope=5