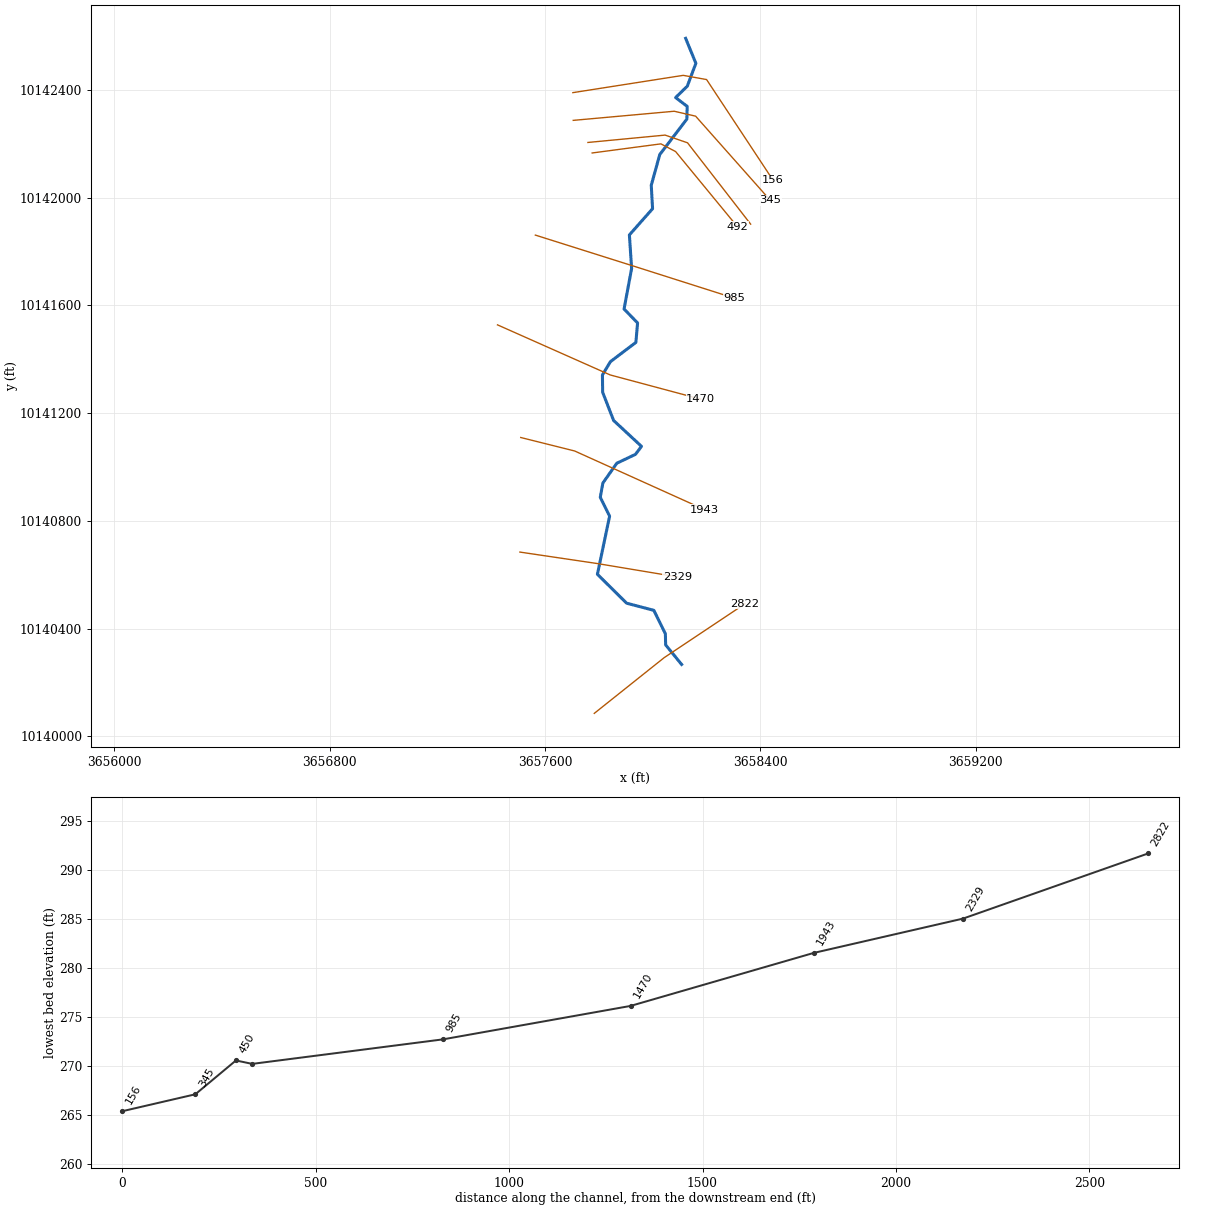
--- UNT085 IN ROCK.prj (project) ---

Proj Title=UNT085 IN ROCK Base Level Engineering
Current Plan=p01
Default Exp/Contr=0.3,0.1
English Units
Geom File=g01
Flow File=f01
Plan File=p01
Y Axis Title=Elevation
X Axis Title(PF)=Main Channel Distance
X Axis Title(XS)=Station
BEGIN DESCRIPTION:
UNT085 IN ROCK
END DESCRIPTION:
DSS Export Rating Curves= 0
DSS Export Rating Curve Sorted= 0
DSS Export Volume Flow Curves= 0
DXF OffsetX= 0
DXF OffsetY= 0
DXF ScaleX= 1
DXF ScaleY= 10

--- UNT085 IN ROCK.p01 (plan) ---

Plan Title=Multiple Run
Short Identifier=Multiple
Geom File=g01
Flow File=f01
Subcritical Flow
K Sum by GR= 0
Std Step Tol= 0.01
Critical Tol= 0.01
Num of Std Step Trials= 20
Max Error Tol= 0.3
Flow Tol Ratio= 0.001
Split Flow NTrial= 30
Split Flow Tol= 0.02
Split Flow Ratio= 0.02
Log Output Level= 0
Friction Slope Method= 1
Unsteady Friction Slope Method= 2
Unsteady Bridges Friction Slope Method= 1
Parabolic Critical Depth
Global Vel Dist=  1 , 1 , 1
Global Log Level= 0
CheckData=True
Encroach Param= -1, 0, 0, 0
BEGIN DESCRIPTION:
Multiple Run
END DESCRIPTION:

--- UNT085 IN ROCK.f01 (steady flow) ---

Flow Title=Multiple
Program Version=4.10
Number of Profiles= 7
Profile Names=10-year,25-year,50-year,1pct_min,100-year,1pct_plu,500-year
River Rch & RM=UNT085 IN ROCK,Reach-1         ,2822
     293     381     450     392     530     717     735
Boundary for River Rch & Prof#=UNT085 IN ROCK,Reach-1         , 1
Up Type= 0
Dn Type= 3
Dn Slope=0.0163
Boundary for River Rch & Prof#=UNT085 IN ROCK,Reach-1         , 2
Up Type= 0
Dn Type= 3
Dn Slope=0.0163
Boundary for River Rch & Prof#=UNT085 IN ROCK,Reach-1         , 3
Up Type= 0
Dn Type= 3
Dn Slope=0.0163
Boundary for River Rch & Prof#=UNT085 IN ROCK,Reach-1         , 4
Up Type= 0
Dn Type= 3
Dn Slope=0.0163
Boundary for River Rch & Prof#=UNT085 IN ROCK,Reach-1         , 5
Up Type= 0
Dn Type= 3
Dn Slope=0.0163
Boundary for River Rch & Prof#=UNT085 IN ROCK,Reach-1         , 6
Up Type= 0
Dn Type= 3
Dn Slope=0.0163
Boundary for River Rch & Prof#=UNT085 IN ROCK,Reach-1         , 7
Up Type= 0
Dn Type= 3
Dn Slope=0.0163
DSS Import GetInterval= 0
DSS Import GetPeak= 0
DSS Import FillOption= 0

--- UNT085 IN ROCK.g01 (geometry) ---

Geom Title=Existing Conditions
Program Version=4.10

River Reach=UNT085 IN ROCK  ,Reach-1
Reach XY= 30
      3658107.11     10140266.64       3658047.8     10140339.15
      3658046.83     10140380.55      3658003.97     10140467.59
      3657903.12     10140494.01       3657794.4     10140601.44
      3657839.74     10140817.24      3657805.06     10140887.42
      3657814.72      10140940.4      3657866.35     10141013.71
      3657935.71     10141046.75      3657958.11     10141076.47
      3657854.57     10141172.62      3657813.88     10141277.24
       3657813.1     10141341.75      3657842.69     10141390.94
      3657937.28     10141462.49      3657943.58     10141534.79
      3657893.39      10141586.5      3657921.45     10141736.95
      3657913.19     10141861.67      3657999.29     10141958.96
      3657994.36     10142045.86      3658025.96     10142160.06
       3658126.6     10142291.77      3658127.79     10142339.01
      3658084.79     10142371.66      3658128.05     10142413.74
      3658160.07     10142498.91      3658122.11     10142591.64

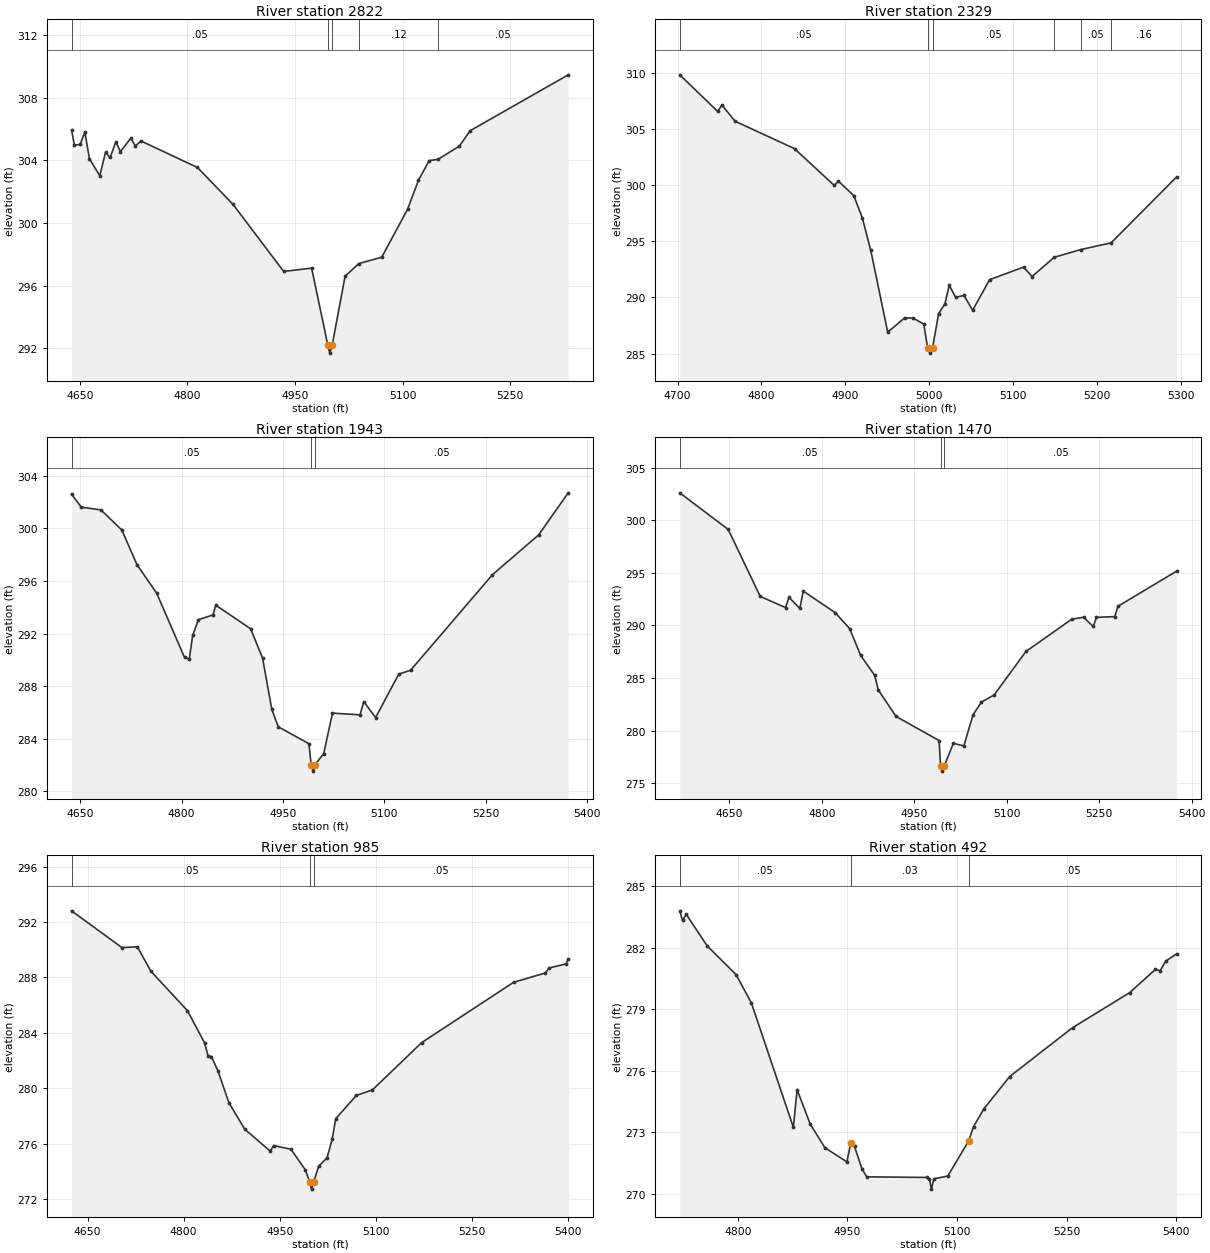
Type RM Length L Ch R = 1 ,2822    ,479,479,479
BEGIN DESCRIPTION:
UNT085 IN ROCK 6.0
END DESCRIPTION:
XS GIS Cut Line= 3
      3657782.76     10140084.94      3658042.11     10140291.64
      3658342.11     10140491.65
#Sta/Elev= 30
  4638.5  305.95  4642.6  304.98  4650.5  305.02  4657.1  305.81  4663.5  304.11
  4677.9  303.02  4685.9  304.51  4692.3  304.19  4700.3  305.19  4706.7  304.57
  4721.1  305.42  4727.5  304.93  4735.5  305.24    4814  303.55  4863.6  301.19
  4934.1  296.91  4973.1  297.12  4995.7  292.19  4998.4  291.69  5001.7  292.19
  5019.7   296.6  5038.8  297.41  5070.8  297.82  5106.8  300.88  5121.9  302.73
  5136.9  303.99  5149.2  304.07    5179  304.92    5194   305.9  5330.7  309.47
#Mann= 5 ,-1 , 0
  4638.5     .05       0  4995.7     .03       0  5001.7     .05       0
  5038.8     .12       0  5149.2     .05       0
Bank Sta=4995.7,5001.7
XS Rating Curve= 0 ,0
Exp/Cntr=0.3,0.1

Type RM Length L Ch R = 1 ,2329    ,386,386,386
BEGIN DESCRIPTION:
UNT085 IN ROCK 5.0
END DESCRIPTION:
XS GIS Cut Line= 3
      3657506.67      10140683.9      3657792.11     10140641.64
      3658092.12     10140591.64
#Sta/Elev= 30
  4702.5  309.85  4747.7  306.59  4752.8  307.15  4768.6  305.71  4839.4  303.27
  4886.8  299.99  4891.8  300.37  4910.2  299.07  4920.3   297.1  4930.4  294.19
  4950.6  286.91  4970.8  288.18  4980.9  288.16  4993.6  287.63  4998.2  285.54
  5000.9  285.04  5004.2  285.54  5011.3  288.55  5018.9  289.44    5024  291.09
  5031.6  290.02  5041.7  290.18  5051.9  288.86  5072.2  291.59  5112.7  292.71
  5122.8  291.87  5149.4  293.59  5180.9  294.27  5217.1  294.87  5295.2  300.74
#Mann= 6 ,-1 , 0
  4702.5     .05       0  4998.2     .03       0  5004.2     .05       0
  5149.4     .16       0  5180.9     .05       0  5217.1     .16       0
Bank Sta=4998.2,5004.2
XS Rating Curve= 0 ,0
Exp/Cntr=0.3,0.1

Type RM Length L Ch R = 1 ,1943    ,473,473,473
BEGIN DESCRIPTION:
UNT085 IN ROCK 4.0
END DESCRIPTION:
XS GIS Cut Line= 3
      3657509.79     10141109.36      3657709.81     10141059.35
      3658192.08     10140841.66
#Sta/Elev= 30
    4637   302.6  4651.5  301.61  4680.6   301.4  4711.5  299.87    4734  297.23
  4763.1  295.07  4804.3  290.18  4811.3  290.06  4816.4  291.87  4824.9  293.05
  4846.5  293.42  4850.5  294.16  4902.2  292.36  4919.8  290.13  4933.5  286.23
    4943  284.91  4988.3  283.63  4991.7  282.04  4994.5  281.54  4997.7  282.04
  5010.3  282.88  5023.3  285.95  5064.1  285.82  5069.6  286.83  5087.1  285.61
  5121.3  288.91  5138.9  289.21    5260  296.47  5328.4   299.5  5372.3   302.7
#Mann= 3 ,-1 , 0
    4637     .05       0  4991.7     .03       0  4997.7     .05       0
Bank Sta=4991.7,4997.7
XS Rating Curve= 0 ,0
Exp/Cntr=0.3,0.1

Type RM Length L Ch R = 1 ,1470    ,485,485,485
BEGIN DESCRIPTION:
UNT085 IN ROCK 3.0
END DESCRIPTION:
XS GIS Cut Line= 3
      3657423.34     10141527.65      3657842.11     10141341.64
      3658177.87     10141251.79
#Sta/Elev= 30
  4569.7   302.6  4648.3  299.12  4700.2  292.75  4741.3  291.69  4746.8  292.67
  4764.5  291.61    4770  293.26    4822   291.2  4845.3  289.69  4863.1  287.14
  4885.7  285.27  4891.8  283.85  4920.5  281.34  4990.3  279.05  4992.8  276.64
  4995.5  276.14  4998.8  276.64  5013.6  278.79  5030.5  278.53  5045.4  281.49
    5059   282.7  5079.7  283.39  5131.4  287.53  5205.5  290.58  5224.6  290.77
  5240.4   289.9  5245.6  290.76  5275.3  290.83  5280.4  291.81  5375.5  295.15
#Mann= 3 ,-1 , 0
  4569.7     .05       0  4992.8     .03       0  4998.8     .05       0
Bank Sta=4992.8,4998.8
XS Rating Curve= 0 ,0
Exp/Cntr=0.3,0.1

Type RM Length L Ch R = 1 ,985     ,493,493,493
BEGIN DESCRIPTION:
UNT085 IN ROCK 2.0
END DESCRIPTION:
XS GIS Cut Line= 3
      3657564.02     10141860.97      3657942.11     10141741.64
      3658303.47     10141626.63
#Sta/Elev= 30
  4624.9  292.81  4703.6  290.16  4727.8  290.21  4748.7  288.46  4805.9  285.61
  4832.6  283.29  4838.2  282.35  4843.5  282.29  4853.6  281.26  4870.6  278.97
  4895.5  277.05  4935.3  275.47  4940.5  275.87  4967.6  275.61  4989.9  274.13
    4997  273.23  4999.7  272.73    5003  273.23  5010.9  274.39    5024  274.99
  5031.9  276.33  5037.5  277.81  5069.7  279.49  5094.8  279.89  5171.6   283.3
  5315.2  287.65    5365  288.33  5370.3  288.68  5397.2  288.98  5400.6  289.33
#Mann= 3 ,-1 , 0
  4624.9     .05       0    4997     .03       0    5003     .05       0
Bank Sta=4997,5003
XS Rating Curve= 0 ,0
Exp/Cntr=0.3,0.1

Type RM Length L Ch R = 1 ,492     ,42,42,42
BEGIN DESCRIPTION:
Mapping XS ef5e0b6a
END DESCRIPTION:
XS GIS Cut Line= 4
      3657774.97     10142165.92      3658030.17     10142199.78
      3658084.86     10142171.13      3658314.05     10141892.45
#Sta/Elev= 30
  4720.5   283.8  4724.3  283.33  4729.4  283.63    4758  282.09  4797.6  280.69
  4818.5  279.31    4876  273.24  4881.1  275.08  4899.2  273.39  4919.4  272.24
  4949.3  271.56  4954.4  272.46  4959.7  272.31  4969.8  271.23  4976.4  270.83
  5058.7   270.8  5062.2  270.73  5064.9  270.23  5068.2  270.73  5087.4  270.87
  5116.1  272.59  5122.6  273.28  5136.9  274.15  5172.1  275.72  5258.1   278.1
  5336.3  279.81  5371.5  280.94    5378  280.88  5385.8  281.35  5400.5   281.7
#Mann= 3 ,-1 , 0
  4720.5     .05       0  4954.4     .03       0  5116.1     .05       0
Bank Sta=4954.4,5116.1
XS Rating Curve= 0 ,0
Exp/Cntr=0.3,0.1

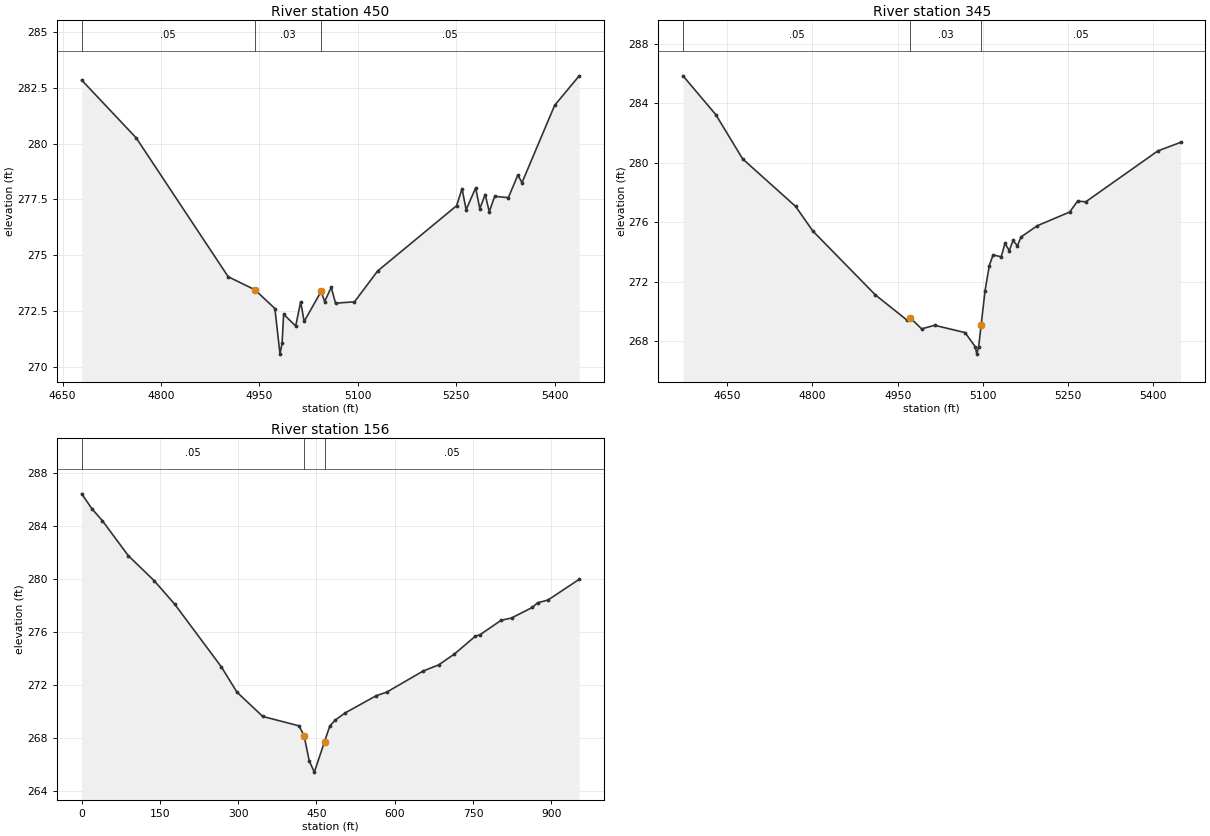
Type RM Length L Ch R = 1 ,450     ,105,105,105
BEGIN DESCRIPTION:
Mapping XS 713e126d
END DESCRIPTION:
XS GIS Cut Line= 4
       3657759.3     10142204.98       3658045.8     10142232.33
      3658129.13     10142203.68      3658363.53     10141901.57
#Sta/Elev= 30
    4679  282.84  4762.2  280.25  4902.4  274.04    4943  273.46  4973.5  272.62
  4981.3  270.58  4984.5  271.08  4986.8  272.36  5005.2  271.84  5012.8  272.92
  5018.1  272.04    5044  273.39  5049.3  272.93  5059.4  273.57  5065.9  272.86
  5094.8  272.92  5130.1   274.3  5250.5  277.22  5258.7  277.98    5265  277.04
  5279.5  278.02  5285.8  277.09    5294  277.72  5300.3  276.95  5308.5  277.64
  5329.3  277.58  5343.8  278.59  5350.1  278.25  5399.9  281.71  5437.3  283.03
#Mann= 3 , 0 , 0
    4679     .05       0    4943     .03       0    5044     .05       0
Bank Sta=4943,5044
XS Rating Curve= 0 ,0
Exp/Cntr=0.3,0.1

Type RM Length L Ch R = 1 ,345     ,189,189,189
BEGIN DESCRIPTION:
UNT085 IN ROCK 1.0
END DESCRIPTION:
XS GIS Cut Line= 4
      3657704.66     10142287.02      3658079.65     10142320.87
      3658159.08     10142302.64       3658436.4     10141990.17
#Sta/Elev= 30
  4572.1  285.86  4629.8  283.25  4677.1  280.27  4770.4  277.07  4800.5  275.42
  4910.9  271.11    4967   269.4  4972.2  269.57  4992.2  268.83    5015  269.07
  5068.6  268.58  5086.5  267.63  5089.3  267.13  5092.5  267.63    5097  269.11
  5103.7  271.38  5111.3  273.09  5117.9  273.81  5132.2  273.68  5138.8  274.58
  5146.4   274.1  5153.1  274.78  5160.6  274.42  5167.3  275.02  5195.7  275.77
  5252.6  276.69  5266.8  277.43    5281  277.38  5408.1  280.81  5447.9  281.38
#Mann= 3 , 0 , 0
  4572.1     .05       0  4972.2     .03       0    5097     .05       0
Bank Sta=4972.2,5097
XS Rating Curve= 0 ,0
Exp/Cntr=0.3,0.1

Type RM Length L Ch R = 1 ,156     ,0,0,0
XS GIS Cut Line= 4
     3657703.298    10142389.956      3658113.02    10142454.192
     3658199.826    10142438.567     3658446.354    10142065.304
#Sta/Elev= 30
       0286.454919.83059285.316439.66118 284.42589.23765 281.782138.8141279.8896
178.4753278.0987 267.713273.3641297.4588271.4572347.0353269.6141416.4424268.9039
426.2424 268.161436.0425266.2545445.8426265.4024465.4427  267.71475.2428268.8661
485.0428269.3087504.6429269.8754564.4799271.1858584.4255271.4509654.2354273.0473
684.1538273.5154714.0723274.3309753.9636275.6701763.9364275.8103803.8278276.8905
823.7734277.0615863.6647 277.864873.6375278.2125893.5832278.4202953.4201279.9899
#Mann= 3 , 0 , 0
       0     .05       0426.2424    .035       0465.4427     .05       0
Bank Sta=426.2424,465.4427
XS Rating Curve= 0 ,0
Exp/Cntr=0.3,0.1
Stream Node=UNT085 IN ROCK  ,Reach-1         , 0 , 0 ,Upstream end
Stream Node=UNT085 IN ROCK  ,Reach-1         , 0 , 1 ,Downstream end

Chan Stop Cuts=-1
Use User Specified Reach Order=0
Composite Channel Slope=5