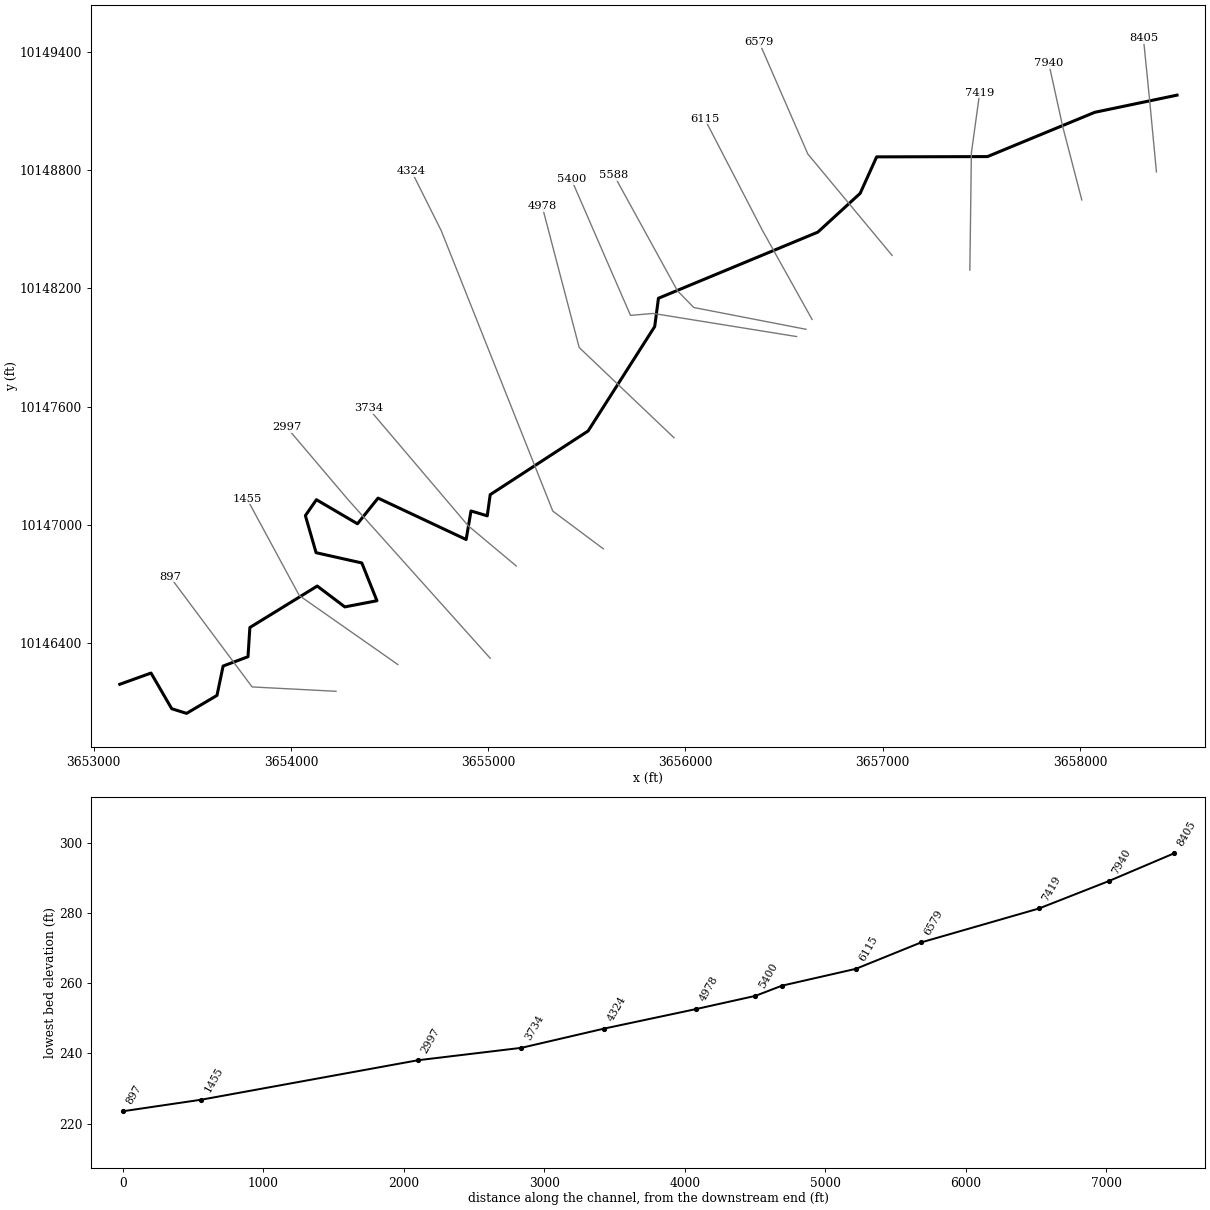
--- UNT086 IN ROCK.prj (project) ---

Proj Title=UNT086 IN ROCK Base Level Engineering
Current Plan=p01
Default Exp/Contr=0.3,0.1
English Units
Geom File=g01
Flow File=f01
Plan File=p01
Y Axis Title=Elevation
X Axis Title(PF)=Main Channel Distance
X Axis Title(XS)=Station
BEGIN DESCRIPTION:
UNT086 IN ROCK
END DESCRIPTION:
DSS Export Rating Curves= 0
DSS Export Rating Curve Sorted= 0
DSS Export Volume Flow Curves= 0
DXF OffsetX= 0
DXF OffsetY= 0
DXF ScaleX= 1
DXF ScaleY= 10

--- UNT086 IN ROCK.p01 (plan) ---

Plan Title=Multiple Run
Short Identifier=Multiple
Geom File=g01
Flow File=f01
Subcritical Flow
K Sum by GR= 0
Std Step Tol= 0.01
Critical Tol= 0.01
Num of Std Step Trials= 20
Max Error Tol= 0.3
Flow Tol Ratio= 0.001
Split Flow NTrial= 30
Split Flow Tol= 0.02
Split Flow Ratio= 0.02
Log Output Level= 0
Friction Slope Method= 1
Unsteady Friction Slope Method= 2
Unsteady Bridges Friction Slope Method= 1
Parabolic Critical Depth
Global Vel Dist=  1 , 1 , 1
Global Log Level= 0
CheckData=True
Encroach Param= -1, 0, 0, 0
BEGIN DESCRIPTION:
Multiple Run
END DESCRIPTION:

--- UNT086 IN ROCK.f01 (steady flow) ---

Flow Title=Multiple
Program Version=4.10
Number of Profiles= 7
Profile Names=10-year,25-year,50-year,1pct_min,100-year,1pct_plu,500-year
River Rch & RM=UNT086 IN ROCK,Reach-1         ,8405
     245     313     366     316     427     577     580
River Rch & RM=UNT086 IN ROCK,Reach-1         ,6579
     480     643     776     689     932    1260    1343
River Rch & RM=UNT086 IN ROCK,Reach-1         ,6115
     480     643     776     689     932    1260    1343
River Rch & RM=UNT086 IN ROCK,Reach-1         ,4324
     741    1015    1244    1118    1512    2045    2237
Boundary for River Rch & Prof#=UNT086 IN ROCK,Reach-1         , 1
Up Type= 0
Dn Type= 3
Dn Slope=0.005
Boundary for River Rch & Prof#=UNT086 IN ROCK,Reach-1         , 2
Up Type= 0
Dn Type= 3
Dn Slope=0.005
Boundary for River Rch & Prof#=UNT086 IN ROCK,Reach-1         , 3
Up Type= 0
Dn Type= 3
Dn Slope=0.005
Boundary for River Rch & Prof#=UNT086 IN ROCK,Reach-1         , 4
Up Type= 0
Dn Type= 3
Dn Slope=0.005
Boundary for River Rch & Prof#=UNT086 IN ROCK,Reach-1         , 5
Up Type= 0
Dn Type= 3
Dn Slope=0.005
Boundary for River Rch & Prof#=UNT086 IN ROCK,Reach-1         , 6
Up Type= 0
Dn Type= 3
Dn Slope=0.005
Boundary for River Rch & Prof#=UNT086 IN ROCK,Reach-1         , 7
Up Type= 0
Dn Type= 3
Dn Slope=0.005
DSS Import GetInterval= 0
DSS Import GetPeak= 0
DSS Import FillOption= 0

--- UNT086 IN ROCK.g01 (geometry) ---

Geom Title=Existing Conditions
Program Version=4.10

River Reach=UNT086 IN ROCK  ,Reach-1
Reach XY= 30
       3658492.6      10149178.8      3658075.41     10149091.73
      3657531.46     10148867.19      3656969.55     10148865.81
      3656885.94     10148680.77      3656671.18     10148484.11
      3655863.24      10148148.9      3655844.29     10148005.55
      3655506.62     10147476.03       3655010.2     10147153.03
      3654995.19     10147045.75      3654912.81     10147070.39
      3654888.19     10146925.75      3654441.48     10147135.64
      3654337.25     10147005.39      3654129.08     10147127.57
      3654073.09     10147046.84       3654127.4     10146858.82
      3654359.23     10146806.84       3654435.9     10146615.27
      3654272.98     10146584.01      3654133.27     10146689.73
      3653791.62     10146479.47      3653782.14     10146331.48
      3653655.98     10146284.11       3653624.9     10146135.21
      3653470.64     10146044.15      3653395.39     10146067.77
      3653290.47      10146248.6      3653132.11     10146191.64

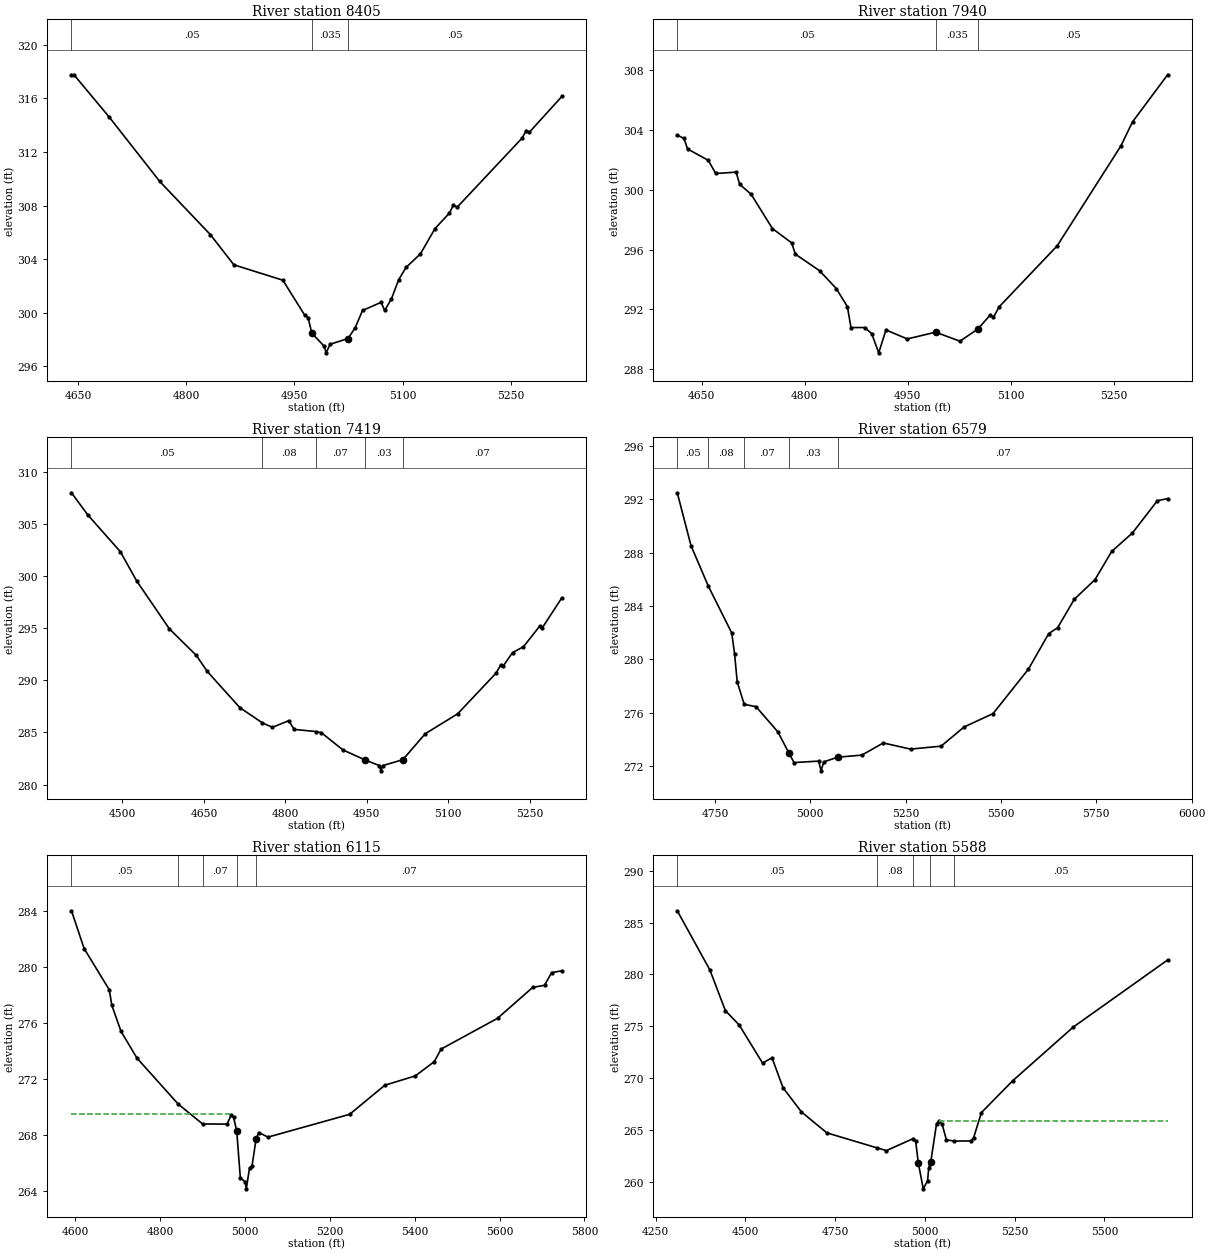
Type RM Length L Ch R = 1 ,8405    ,465,465,465
BEGIN DESCRIPTION:
UNT086 IN ROCK 15.0
END DESCRIPTION:
XS GIS Cut Line= 3
      3658388.13     10148789.79      3658354.19     10149147.38
      3658322.17     10149466.78
#Sta/Elev= 30
  4640.8  317.76  4644.2  317.76  4692.9  314.62  4763.2   309.8  4833.5  305.83
    4866  303.58    4934  302.43  4964.1  299.84  4969.1  299.63  4974.1  298.48
  4991.2  297.51    4994  297.01  4999.6  297.65  5024.4  298.08  5034.4  298.89
  5044.5  300.17  5070.3  300.78  5075.3  300.17  5084.7  301.05  5094.7  302.47
  5104.8  303.38  5124.9   304.4    5145  306.28  5165.1  307.44  5170.7  308.05
  5175.7  307.87  5265.6  313.02  5271.1  313.54  5276.1  313.48    5321  316.14
#Mann= 3 , 0 , 0
  4640.8     .05       0  4974.1    .035       0  5024.4     .05       0
Bank Sta=4974.1,5024.4
XS Rating Curve= 0 ,0
Exp/Cntr=0.3,0.1

Type RM Length L Ch R = 1 ,7940    ,495,495,495
BEGIN DESCRIPTION:
UNT086 IN ROCK 14.0
END DESCRIPTION:
XS GIS Cut Line= 3
      3658009.65     10148647.46      3657912.53     10149020.84
      3657842.11      10149341.6
#Sta/Elev= 30
  4614.2  303.66    4624  303.43  4629.2  302.73  4659.4  301.97  4670.2  301.09
  4699.9  301.18  4705.1  300.37  4721.8   299.7  4752.8  297.41  4780.9  296.45
  4786.1   295.7  4821.5  294.59  4845.8   293.4    4862  292.19  4867.2  290.79
  4887.2  290.79  4897.4  290.39  4907.6   289.1  4918.2  290.63  4949.2  290.03
  4990.5  290.48  5025.9  289.88    5052  290.69  5069.7  291.61  5074.8  291.47
  5082.7  292.16  5167.5  296.25  5260.2  302.92  5277.3  304.54  5328.4  307.69
#Mann= 3 , 0 , 0
  4614.2     .05       0  4990.5    .035       0    5052     .05       0
Bank Sta=4990.5,5052
XS Rating Curve= 0 ,0
Exp/Cntr=0.3,0.1

Type RM Length L Ch R = 1 ,7419    ,840,840,840
BEGIN DESCRIPTION:
UNT086 IN ROCK 13.0
END DESCRIPTION:
XS GIS Cut Line= 3
      3657442.11     10148291.67      3657449.86     10148885.42
       3657492.1     10149191.62
#Sta/Elev= 30
  4406.2  307.98  4436.2  305.86  4496.2  302.33  4526.2  299.53  4586.2  294.95
  4636.2  292.38  4656.2  290.85  4716.2  287.38  4757.7  285.92  4776.2  285.49
  4806.2  286.13  4816.2  285.29    4856  285.09  4866.2  284.98  4906.2  283.32
  4946.2  282.38  4973.2  281.82    4976  281.32  4979.2  281.82  5016.4  282.39
  5057.4  284.87  5117.3  286.79    5188  290.69  5196.2  291.44  5201.2  291.37
  5218.3  292.66  5238.5  293.22  5268.1  295.18  5273.2  295.04  5309.1  297.91
#Mann= 5 ,-1 , 0
  4406.2     .05       0  4757.7     .08       0    4856     .07       0
  4946.2     .03       0  5016.4     .07       0
Bank Sta=4946.2,5016.4
XS Rating Curve= 0 ,0
Exp/Cntr=0.3,0.1

Type RM Length L Ch R = 1 ,6579    ,464,464,464
BEGIN DESCRIPTION:
UNT086 IN ROCK 12.0
END DESCRIPTION:
XS GIS Cut Line= 3
      3657047.87     10148366.15      3656620.77     10148880.06
      3656374.22     10149446.08
#Sta/Elev= 30
  4651.3  292.49  4687.4  288.52  4732.9  285.48  4794.1  281.98  4801.5  280.43
  4808.5  278.31  4826.8  276.63  4857.9  276.45  4915.2  274.56  4943.9  272.98
  4957.5  272.26    5022  272.37  5028.3  271.64  5035.5  272.31  5071.5  272.66
  5135.3  272.82  5191.5  273.73  5262.9  273.27  5343.1  273.49  5403.4  274.93
  5479.2  275.93  5572.1  279.27  5625.2  281.93  5648.5  282.37  5692.1   284.5
  5746.6  285.98  5790.3  288.09  5844.8  289.48  5910.2   291.9  5936.9  292.05
#Mann= 5 ,-1 , 0
  4651.3     .05       0  4732.9     .08       0  4826.8     .07       0
  4943.9     .03       0  5071.5     .07       0
Bank Sta=4943.9,5071.5
XS Rating Curve= 0 ,0
Exp/Cntr=0.3,0.1

Type RM Length L Ch R = 1 ,6115    ,527,527,527
BEGIN DESCRIPTION:
UNT086 IN ROCK 11.0
END DESCRIPTION:
XS GIS Cut Line= 3
      3656642.12     10148041.61      3656389.23     10148495.27
       3656096.8     10149059.96
#Sta/Elev= 30
  4591.3  284.01    4621  281.31  4680.5  278.35  4686.2  277.26  4707.9  275.39
  4745.6  273.47  4842.8  270.18  4900.3  268.76  4957.7  268.75  4967.4  269.38
  4973.1  269.25  4980.6  268.25  4989.1  264.91  5000.5  264.62  5003.2  264.12
  5010.8  265.63  5016.5  265.72  5026.4  267.72  5032.5  268.15  5054.2  267.82
  5246.6  269.45  5329.5  271.53  5401.5   272.2  5445.8  273.21  5462.3  274.12
  5595.1  276.32    5678  278.53  5705.8  278.68  5722.3  279.58  5746.6  279.72
#Mann= 5 ,-1 , 0
  4591.3     .05       0  4842.8     .08       0  4900.3     .07       0
  4980.6     .05       0  5026.4     .07       0
#XS Ineff= 2 , 0
         4967.11  269.46
Permanent Ineff=
       F       F
Bank Sta=4980.6,5026.4
XS Rating Curve= 0 ,0
Exp/Cntr=0.3,0.1

Type RM Length L Ch R = 1 ,5588    ,188,188,188
BEGIN DESCRIPTION:
UNT086 IN ROCK 10.0
END DESCRIPTION:
XS GIS Cut Line= 4
       3656611.3      10147991.6      3656042.41     10148102.01
       3655959.9     10148186.27      3655638.13     10148772.42
#Sta/Elev= 30
  4309.9  286.14  4400.8  280.43    4444   276.5  4482.3  275.13  4547.4  271.45
  4573.9  271.95  4604.5  269.07  4655.9  266.73  4726.7  264.71  4866.8  263.26
  4892.7     263  4967.2  264.16  4974.2  263.88  4981.3  261.85  4995.2  259.31
  5007.3   260.1  5010.5  261.33  5013.7  261.67  5016.2  261.93  5032.3   265.6
    5038  265.84  5047.7  265.56  5059.8  264.03  5081.9  263.92  5127.5  263.93
  5135.5  264.24  5157.3  266.67  5244.5  269.74  5413.2  274.92    5676  281.39
#Mann= 5 ,-1 , 0
  4309.9     .05       0  4866.8     .08       0  4967.2     .05       0
  5013.7     .08       0  5081.9     .05       0
#XS Ineff= 2 , 0
                         5039.09          265.82
Permanent Ineff=
       F       F
Bank Sta=4981.3,5016.2
XS Rating Curve= 0 ,0
Exp/Cntr=0.3,0.1

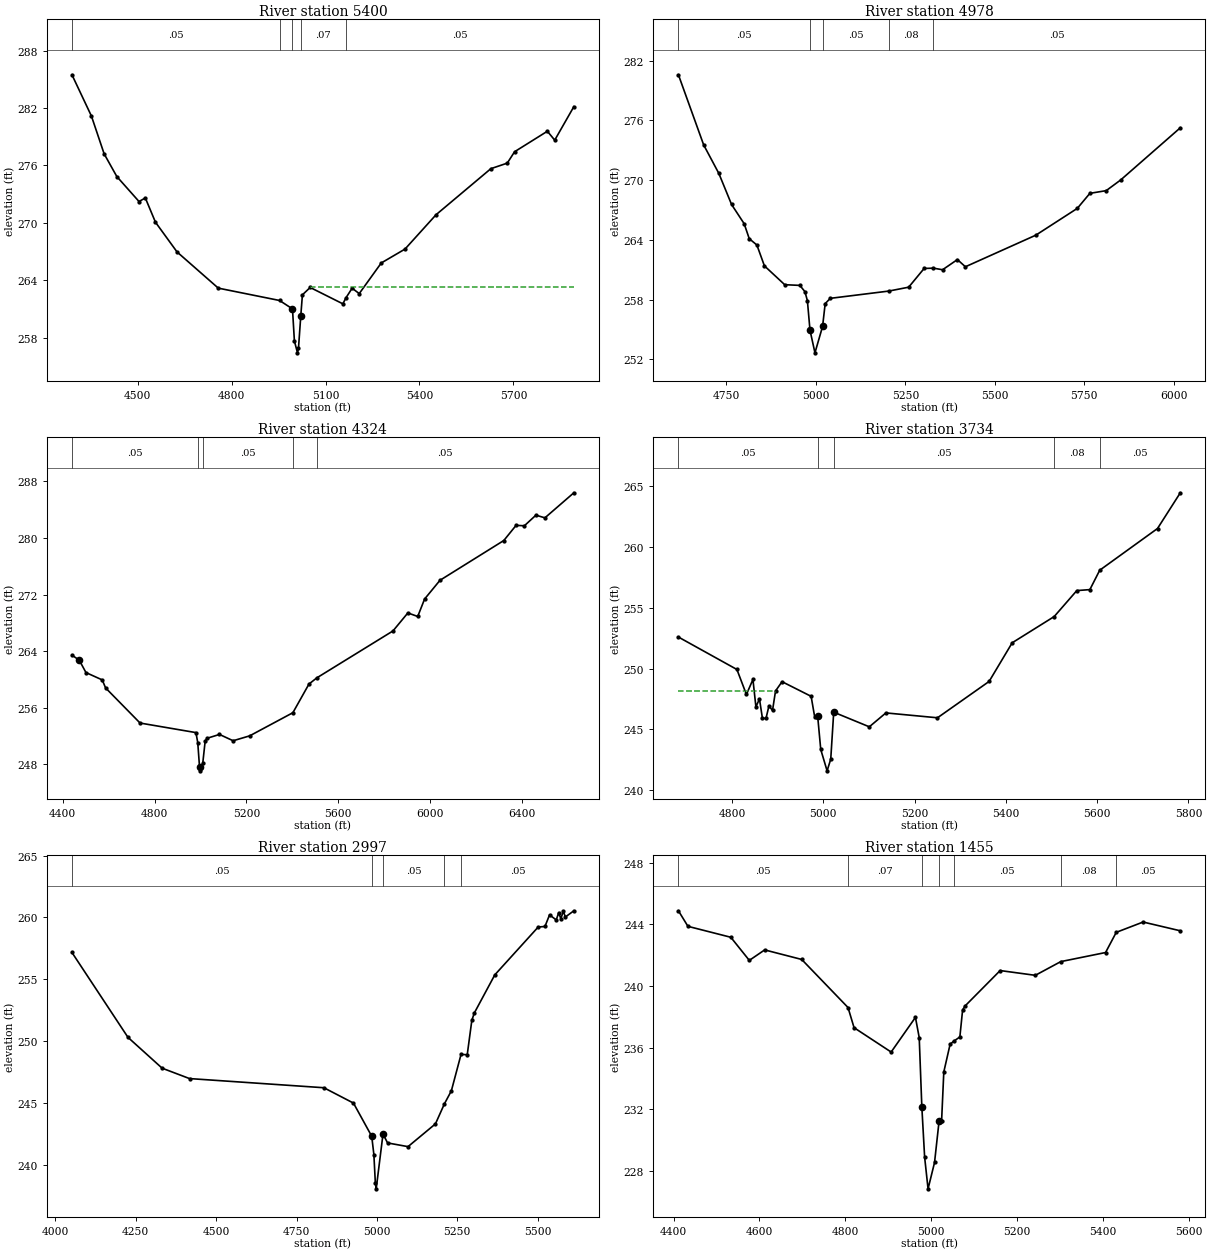
Type RM Length L Ch R = 1 ,5400    ,422,422,422
BEGIN DESCRIPTION:
Mapping XS 4d6e2e73
END DESCRIPTION:
XS GIS Cut Line= 4
      3656563.55     10147954.71      3655836.53      10148071.9
      3655721.51     10148062.14      3655422.04     10148751.13
#Sta/Elev= 30
    4290  285.47  4352.2  281.16  4392.8  277.21  4433.3  274.84  4504.2  272.23
  4524.4   272.6  4556.7  270.07  4625.7  266.96  4757.4  263.18  4953.1  261.89
  4994.4  261.01  5000.5  257.66  5010.4  256.42  5013.6  256.92  5020.8  260.24
  5026.1  262.48  5050.9  263.25  5155.3  261.54  5165.6  262.19  5184.9  263.17
  5207.6  262.61    5278  265.81  5353.8  267.26    5453  270.85    5628  275.66
  5680.4  276.24  5703.8  277.43  5808.5  279.57    5832  278.64  5893.1  282.14
#Mann= 5 ,-1 , 0
    4290     .05       0  4953.1     .07       0  4994.4     .05       0
  5020.8     .07       0  5165.6     .05       0
#XS Ineff= 2 , 0
                         5052.57          263.26
Permanent Ineff=
       F       F
Bank Sta=4994.4,5020.8
XS Rating Curve= 0 ,0
Exp/Cntr=0.3,0.1

Type RM Length L Ch R = 1 ,4978    ,654,654,654
BEGIN DESCRIPTION:
UNT086 IN ROCK 8.0
END DESCRIPTION:
XS GIS Cut Line= 3
      3655942.09     10147441.66      3655461.38     10147899.16
      3655273.87     10148614.48
#Sta/Elev= 30
  4615.6  280.57  4686.2  273.53  4728.6  270.67  4764.2  267.55  4799.4  265.62
  4813.6  264.12    4835  263.48    4856  261.39  4912.7   259.5  4955.1  259.43
  4969.3   258.8  4976.2  257.89  4983.4  254.94  4997.3  252.66  5018.6  255.31
  5025.9   257.6  5040.1  258.13  5203.7  258.86  5259.3  259.25  5302.5  261.13
  5328.6  261.16  5354.1     261  5395.5  262.02  5417.9   261.3  5614.7  264.47
  5730.7  267.16  5765.9  268.67  5811.5  268.94  5851.9  270.01  6018.7  275.25
#Mann= 5 ,-1 , 0
  4615.6     .05       0  4983.4     .04       0  5018.6     .05       0
  5203.7     .08       0  5328.6     .05       0
Bank Sta=4983.4,5018.6
XS Rating Curve= 0 ,0
Exp/Cntr=0.3,0.1

Type RM Length L Ch R = 1 ,4324    ,590,590,590
BEGIN DESCRIPTION:
UNT086 IN ROCK 6.0
END DESCRIPTION:
XS GIS Cut Line= 4
       3655583.8     10146878.49      3655327.55     10147069.78
       3654761.9     10148491.64      3654611.91     10148791.61
#Sta/Elev= 30
  4440.3  263.44  4472.1  262.73  4501.3  260.98  4572.2  259.94  4586.8  258.81
  4736.9  253.85  4980.2   252.5  4988.1  251.08  4995.9   247.6  4998.6   247.1
  5009.9  248.19  5020.4   251.3  5028.8   251.7  5082.7  252.24  5142.1  251.35
  5214.1  252.04  5402.3  255.31  5472.4  259.36  5506.5  260.23  5838.2  266.86
  5902.9   269.4  5945.9   268.9  5975.7  271.36  6042.8  274.01  6320.8  279.63
  6374.2  281.77  6410.3  281.71  6460.6  283.21  6499.7  282.83  6625.7  286.37
#Mann= 5 ,-1 , 0
  4440.3     .05       0  4988.1     .04       0  5009.9     .05       0
  5402.3     .08       0  5506.5     .05       0
Bank Sta=4472.1,4995.9
XS Rating Curve= 0 ,0
Exp/Cntr=0.3,0.1

Type RM Length L Ch R = 1 ,3734    ,737,737,737
BEGIN DESCRIPTION:
UNT086 IN ROCK 5.0
END DESCRIPTION:
XS GIS Cut Line= 3
       3655142.1     10146791.65      3654898.58     10146995.37
      3654392.13     10147591.61
#Sta/Elev= 30
  4682.5  252.58  4810.7  249.92  4831.5  247.87  4845.8   249.1  4852.3  246.86
  4860.1   247.5  4866.6  245.92  4874.4  245.91  4880.9  246.94  4888.7  246.56
  4895.3  248.16  4909.6  248.92  4973.3  247.72  4981.1  246.03  4987.6   246.1
  4994.4  243.36  5008.3  241.61  5016.3  242.57  5022.8  246.42  5100.8  245.22
  5137.1  246.36  5250.2  245.96  5363.3  248.94  5413.9  252.11  5505.9  254.26
  5555.5  256.39  5584.1  256.47  5605.7  258.06  5732.3  261.48  5782.3  264.41
#Mann= 5 ,-1 , 0
  4682.5     .05       0  4987.6    .035       0  5022.8     .05       0
  5505.9     .08       0  5605.7     .05       0
#XS Ineff= 2 , 0
         4894.55  248.17
Permanent Ineff=
       F       F
Bank Sta=4987.6,5022.8
XS Rating Curve= 0 ,0
Exp/Cntr=0.3,0.1

Type RM Length L Ch R = 1 ,2997    ,1542,1542,1542
BEGIN DESCRIPTION:
UNT086 IN ROCK 3.0
END DESCRIPTION:
XS GIS Cut Line= 3
      3655010.35     10146323.39      3654289.62     10147127.73
      3653978.43     10147494.62
#Sta/Elev= 30
  4051.4  257.17  4225.7  250.31  4331.9  247.82  4417.1  246.98    4835  246.24
    4927     245  4983.8  242.32  4990.5  240.84    4995  238.57  4997.7  238.07
  5018.9   242.5  5033.1  241.78  5096.7  241.48    5182  243.32  5210.1  244.95
  5231.5  245.99  5261.6  248.93  5280.9  248.91  5295.2  251.69  5302.9  252.28
  5366.6  255.36  5501.7  259.23  5522.6  259.27  5536.9  260.21  5557.7   259.8
  5565.4  260.39    5572   259.9  5579.7  260.49  5586.3  260.04  5612.5  260.54
#Mann= 5 ,-1 , 0
  4051.4     .05       0  4983.8    .035       0  5018.9     .05       0
  5210.1     .08       0  5261.6     .05       0
Bank Sta=4983.8,5018.9
XS Rating Curve= 0 ,0
Exp/Cntr=0.3,0.1

Type RM Length L Ch R = 1 ,1455    ,558,558,558
BEGIN DESCRIPTION:
UNT086 IN ROCK 2.0
END DESCRIPTION:
XS GIS Cut Line= 3
       3654542.1     10146291.65      3654042.11     10146641.64
      3653776.21     10147133.56
#Sta/Elev= 30
  4411.3  244.88  4433.5  243.87  4533.4  243.16  4576.5  241.66  4612.3  242.34
  4698.6  241.72  4806.5   238.6  4820.6  237.29    4907  235.71  4963.6  237.96
  4972.4  236.65  4978.5  232.15    4985  228.89    4993  226.83  5008.1  228.54
  5018.6  231.21  5024.5  231.21  5029.7  234.42  5044.4  236.22  5053.2  236.42
  5067.1  236.69  5073.5  238.44  5079.2   238.7    5161     241  5242.9  240.69
  5302.2  241.58  5406.6  242.17  5431.5  243.48  5494.1  244.15  5580.8  243.58
#Mann= 7 ,-1 , 0
  4411.3     .05       0  4806.5     .07       0  4978.5    .035       0
  5018.6     .07       0  5053.2     .05       0  5302.2     .08       0
  5431.5     .05       0
Bank Sta=4978.5,5018.6
XS Rating Curve= 0 ,0
Exp/Cntr=0.3,0.1

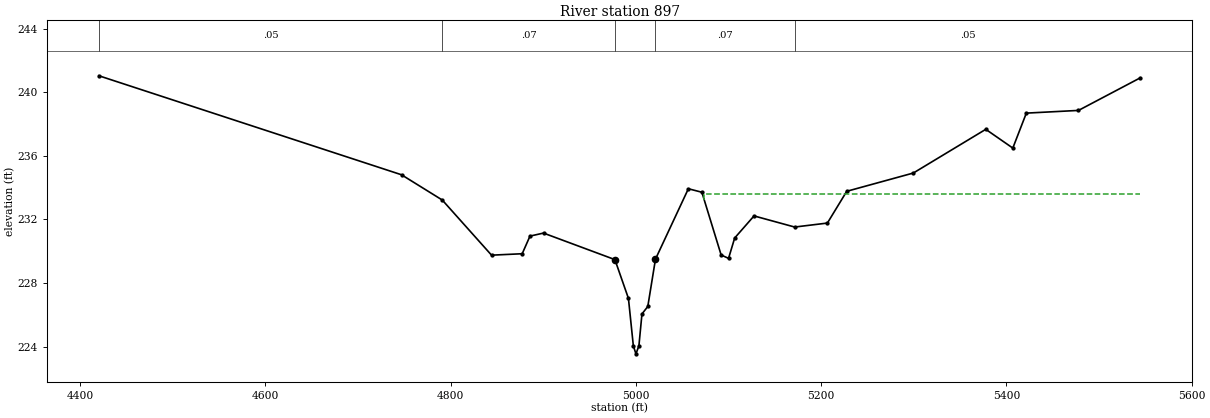
Type RM Length L Ch R = 1 ,897     ,0,0,0
BEGIN DESCRIPTION:
UNT086 IN ROCK 1.0
END DESCRIPTION:
XS GIS Cut Line= 3
      3654228.41      10146156.1      3653802.98     10146178.17
      3653385.68     10146738.06
#Sta/Elev= 30
  4420.2  241.04  4746.9  234.81  4790.9  233.22  4844.1  229.75  4877.2  229.84
  4885.6  230.95  4900.2  231.14  4977.3  229.47  4991.9  227.03  4997.2  224.04
    5000  223.54  5003.2  224.04  5006.5  226.05  5012.8  226.52  5021.1   229.5
  5056.6  233.93  5071.2  233.71    5092  229.76    5100  229.55  5106.6  230.83
  5127.5  232.22  5171.4  231.52  5206.7  231.77  5227.6  233.77  5299.5  234.92
  5377.7  237.67  5406.9  236.49  5421.5  238.69  5477.8  238.86  5544.5  240.91
#Mann= 5 ,-1 , 0
  4420.2     .05       0  4790.9     .07       0  4977.3    .035       0
  5021.1     .07       0  5171.4     .05       0
#XS Ineff= 2 , 0
                         5073.64          233.58
Permanent Ineff=
       F       F
Bank Sta=4977.3,5021.1
XS Rating Curve= 0 ,0
Exp/Cntr=0.3,0.1
Stream Node=UNT086 IN ROCK  ,Reach-1         , 0 , 0 ,Upstream end
Stream Node=UNT086 IN ROCK  ,Reach-1         , 0 , 1 ,Downstream end

Chan Stop Cuts=-1
Use User Specified Reach Order=0
Composite Channel Slope=5