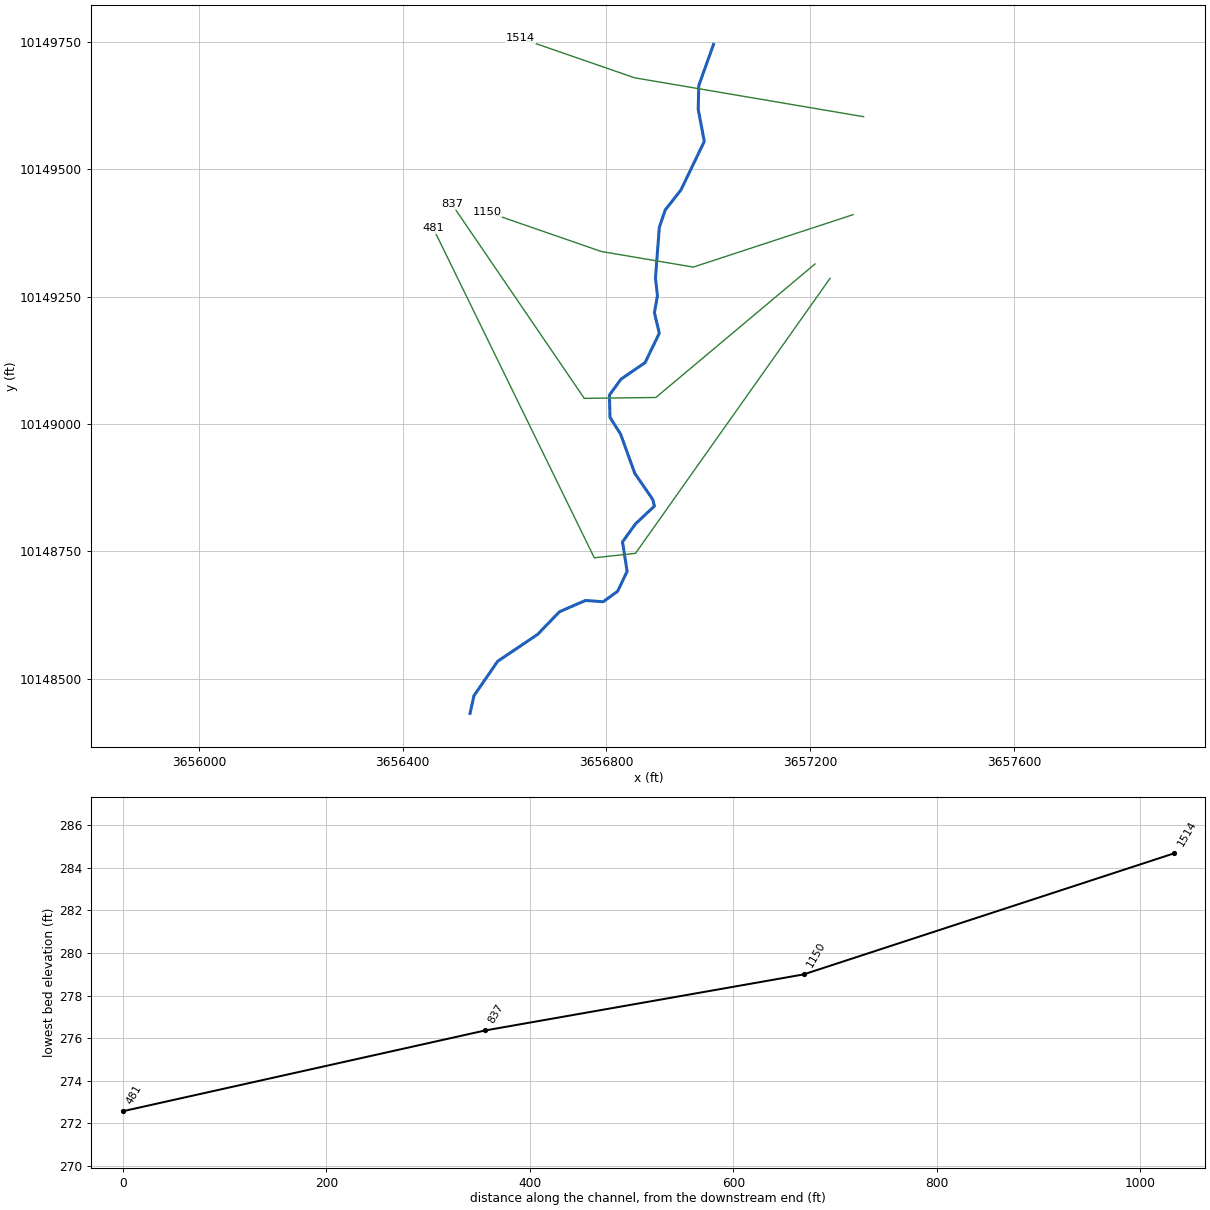
--- UNT087 IN ROCK.prj (project) ---

Proj Title=UNT087 IN ROCK Base Level Engineering
Current Plan=p01
Default Exp/Contr=0.3,0.1
English Units
Geom File=g01
Flow File=f01
Plan File=p01
BEGIN DESCRIPTION:
UNT087 IN ROCK
END DESCRIPTION:

--- UNT087 IN ROCK.p01 (plan) ---

Plan Title=Multiple Run
Short Identifier=Multiple
Geom File=g01
Flow File=f01
Subcritical Flow
K Sum by GR= 0
Std Step Tol= 0.01
Critical Tol= 0.01
Num of Std Step Trials= 20
Max Error Tol= 0.3
Flow Tol Ratio= 0.001
Split Flow NTrial= 30
Split Flow Tol= 0.02
Split Flow Ratio= 0.02
Log Output Level= 0
Friction Slope Method= 1
Unsteady Friction Slope Method= 2
Unsteady Bridges Friction Slope Method= 1
Parabolic Critical Depth
Global Vel Dist=  1 , 1 , 1
Global Log Level= 0
CheckData=True
Encroach Param= -1, 0, 0, 0
BEGIN DESCRIPTION:
Multiple Run
END DESCRIPTION:

--- UNT087 IN ROCK.f01 (steady flow) ---

Flow Title=Multiple
Number of Profiles=7
Profile Names=10-year,25-year,50-year,1pct_min,100-year,1pct_plu,500-year
River Rch & RM= UNT087 IN ROCK,Reach-1,1514
     185     232     269     229     310     419     411
Boundary for River Rch & Prof#=UNT087 IN ROCK,Reach-1,1
Up Type=0
Dn Type=3
Dn Slope=0.005
Boundary for River Rch & Prof#=UNT087 IN ROCK,Reach-1,2
Up Type=0
Dn Type=3
Dn Slope=0.005
Boundary for River Rch & Prof#=UNT087 IN ROCK,Reach-1,3
Up Type=0
Dn Type=3
Dn Slope=0.005
Boundary for River Rch & Prof#=UNT087 IN ROCK,Reach-1,4
Up Type=0
Dn Type=3
Dn Slope=0.005
Boundary for River Rch & Prof#=UNT087 IN ROCK,Reach-1,5
Up Type=0
Dn Type=3
Dn Slope=0.005
Boundary for River Rch & Prof#=UNT087 IN ROCK,Reach-1,6
Up Type=0
Dn Type=3
Dn Slope=0.005
Boundary for River Rch & Prof#=UNT087 IN ROCK,Reach-1,7
Up Type=0
Dn Type=3
Dn Slope=0.005

--- UNT087 IN ROCK.g01 (geometry) ---

Geom Title=Existing Conditions

River Reach=UNT087 IN ROCK,Reach-1
Reach XY= 30
      3657010.19     10149745.15      3656981.25     10149664.45
      3656980.17     10149617.79      3656992.10     10149554.86
      3656946.21     10149459.39      3656915.44     10149420.26
      3656903.80     10149386.18      3656896.24     10149286.56
      3656900.12     10149251.90      3656894.19     10149218.56
      3656903.74     10149178.20      3656875.90     10149120.54
      3656828.52     10149087.94      3656805.78     10149056.65
      3656806.96     10149012.89      3656827.76     10148980.02
      3656855.66     10148902.96      3656891.01     10148851.56
      3656894.07     10148838.52      3656857.32     10148804.07
      3656831.49     10148768.40      3656840.56     10148710.49
      3656821.94     10148671.40      3656793.52     10148650.84
      3656758.68     10148653.35      3656707.78     10148631.24
      3656664.75     10148586.72      3656586.17     10148533.78
      3656539.77     10148466.19      3656532.11     10148431.64

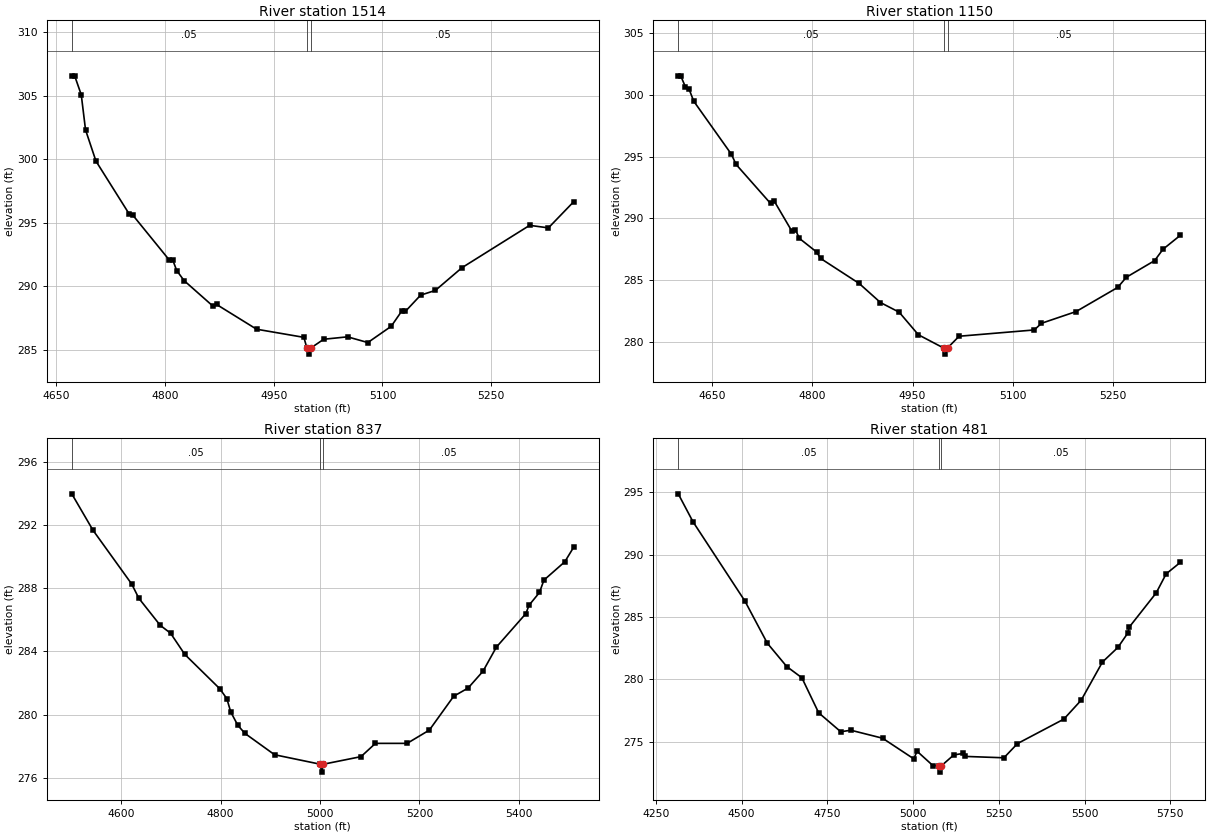
Type RM Length L Ch R = 1,1514,364,364,364
BEGIN DESCRIPTION:
UNT087 IN ROCK 3.0
END DESCRIPTION:
XS GIS Cut Line= 3
      3657305.00     10149603.32      3656855.31     10149679.72
      3656631.38     10149757.23
#Sta/Elev= 30
  4671.1  306.56  4675.1  306.56  4684.2  305.07  4690.1  302.31  4704.5  299.85
  4750.4  295.69  4755.4  295.60  4805.6  292.08  4810.7  292.04  4816.0  291.24
  4826.2  290.45  4865.9  288.45  4870.9  288.58  4926.2  286.63  4991.5  285.99
  4995.6  285.17  4998.4  284.67  5001.6  285.17  5018.9  285.84  5051.8  286.03
  5079.8  285.58  5112.1  286.86  5126.3  288.03  5131.6  288.03  5152.7  289.31
  5173.0  289.68  5209.8  291.47  5303.2  294.80  5329.1  294.60  5364.2  296.67
#Mann=3,-1,0
  4671.1    0.05       0  4995.6    0.03       0  5001.6    0.05       0
Bank Sta=4995.6,5001.6
Exp/Cntr=0.3,0.1

Type RM Length L Ch R = 1,1150,313,313,313
BEGIN DESCRIPTION:
UNT087 IN ROCK 2.0
END DESCRIPTION:
XS GIS Cut Line= 4
      3657284.16     10149410.91      3656970.45     10149308.00
      3656789.84     10149338.68      3656565.84     10149416.22
#Sta/Elev= 30
  4599.7  301.55  4603.4  301.55  4610.3  300.67  4615.5  300.52  4622.9  299.49
  4679.2  295.19  4686.1  294.37  4737.6  291.21  4742.8  291.43  4769.4  288.97
  4774.7  289.09  4780.8  288.37  4806.5  287.27  4812.4  286.75  4870.1  284.72
  4902.0  283.17  4929.9  282.39  4958.6  280.56  4996.2  279.49  4998.9  278.99
  5002.2  279.49  5019.5  280.44  5131.8  280.95  5142.6  281.49  5194.3  282.44
  5256.6  284.40  5269.4  285.22  5311.7  286.57  5324.2  287.49  5350.1  288.62
#Mann=3,-1,0
  4599.7    0.05       0  4996.2    0.03       0  5002.2    0.05       0
Bank Sta=4996.2,5002.2
Exp/Cntr=0.3,0.1

Type RM Length L Ch R = 1,837,356,356,356
BEGIN DESCRIPTION:
Mapping XS 28b59443
END DESCRIPTION:
XS GIS Cut Line= 4
      3657209.55     10149314.15      3656897.03     10149051.98
      3656756.41     10149050.24      3656496.57     10149431.34
#Sta/Elev= 30
  4500.8  293.97  4543.4  291.67  4621.4  288.26  4635.7  287.36  4678.7  285.65
  4699.5  285.15  4728.1  283.81  4798.4  281.64  4812.7  281.01  4820.5  280.17
  4834.8  279.32  4849.1  278.81  4908.7  277.46  5000.7  276.86  5003.4  276.36
  5006.7  276.86  5082.5  277.34  5111.6  278.18  5175.3  278.18  5220.0  279.02
  5268.9  281.16  5297.9  281.68  5327.8  282.74  5354.8  284.27  5414.1  286.39
  5420.5  286.92  5441.5  287.73  5450.4  288.51  5492.4  289.67  5510.6  290.61
#Mann=3,-1,0
  4500.8    0.05       0  5000.7    0.03       0  5006.7    0.05       0
Bank Sta=5000.7,5006.7
Exp/Cntr=0.3,0.1

Type RM Length L Ch R = 1,481,0,0,0
BEGIN DESCRIPTION:
UNT087 IN ROCK 1.0
END DESCRIPTION:
XS GIS Cut Line= 4
      3657239.02     10149285.89      3656857.10     10148745.99
      3656776.12     10148737.13      3656459.52     10149384.91
#Sta/Elev= 30
  4315.1  294.89  4358.1  292.65  4509.5  286.29  4574.8  282.91  4631.4  281.04
  4675.5  280.14  4724.5  277.33  4788.9  275.81  4818.5  275.93  4910.8  275.29
  5001.6  273.64  5011.6  274.24  5057.4  273.10  5076.0  273.07  5078.8  272.57
  5082.0  273.07  5118.5  273.95  5146.6  274.07  5152.1  273.83  5264.7  273.72
  5304.2  274.86  5439.3  276.82  5489.9  278.34  5551.9  281.40  5596.9  282.57
  5625.0  283.69  5630.6  284.22  5708.5  286.94  5737.6  288.47  5778.9  289.39
#Mann=3,-1,0
  4315.1    0.05       0  5076.0    0.03       0  5082.0    0.05       0
Bank Sta=5076,5082
Exp/Cntr=0.3,0.1

Chan Stop Cuts=-1