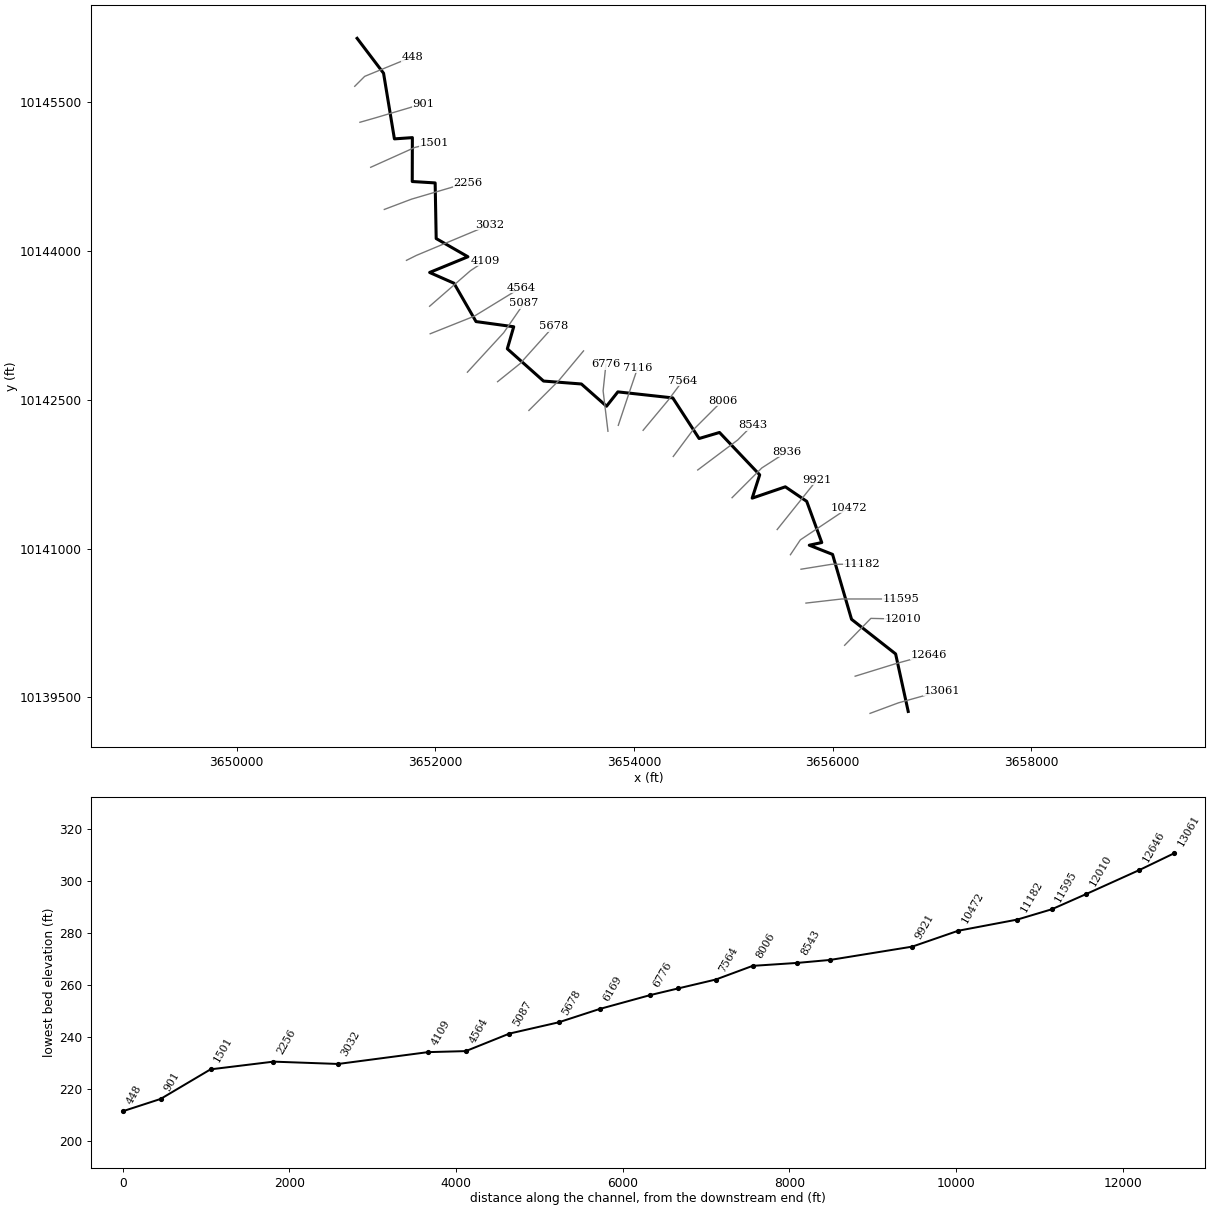
--- UNT088 IN ROCK.prj (project) ---

Proj Title=UNT088 IN ROCK Base Level Engineering
Current Plan=p01
Default Exp/Contr=0.3,0.1
English Units
Geom File=g01
Flow File=f01
Plan File=p01
BEGIN DESCRIPTION:
UNT088 IN ROCK
END DESCRIPTION:

--- UNT088 IN ROCK.p01 (plan) ---

Plan Title=Multiple Run
Short Identifier=Multiple
Geom File=g01
Flow File=f01
Subcritical Flow
K Sum by GR= 0
Std Step Tol= 0.01
Critical Tol= 0.01
Num of Std Step Trials= 20
Max Error Tol= 0.3
Flow Tol Ratio= 0.001
Split Flow NTrial= 30
Split Flow Tol= 0.02
Split Flow Ratio= 0.02
Log Output Level= 0
Friction Slope Method= 1
Unsteady Friction Slope Method= 2
Unsteady Bridges Friction Slope Method= 1
Parabolic Critical Depth
Global Vel Dist=  1 , 1 , 1
Global Log Level= 0
CheckData=True
Encroach Param= -1, 0, 0, 0
BEGIN DESCRIPTION:
Multiple Run
END DESCRIPTION:

--- UNT088 IN ROCK.f01 (steady flow) ---

Flow Title=Multiple
Number of Profiles=7
Profile Names=10-year,25-year,50-year,1pct_min,100-year,1pct_plu,500-year
River Rch & RM= UNT088 IN ROCK,Reach-1,13061
     450     600     722     639     864    1169    1238
River Rch & RM= UNT088 IN ROCK,Reach-1,6169
     771    1060    1301    1172    1584    2143    2353
Boundary for River Rch & Prof#=UNT088 IN ROCK,Reach-1,1
Up Type=0
Dn Type=3
Dn Slope=0.005
Boundary for River Rch & Prof#=UNT088 IN ROCK,Reach-1,2
Up Type=0
Dn Type=3
Dn Slope=0.005
Boundary for River Rch & Prof#=UNT088 IN ROCK,Reach-1,3
Up Type=0
Dn Type=3
Dn Slope=0.005
Boundary for River Rch & Prof#=UNT088 IN ROCK,Reach-1,4
Up Type=0
Dn Type=3
Dn Slope=0.005
Boundary for River Rch & Prof#=UNT088 IN ROCK,Reach-1,5
Up Type=0
Dn Type=3
Dn Slope=0.005
Boundary for River Rch & Prof#=UNT088 IN ROCK,Reach-1,6
Up Type=0
Dn Type=3
Dn Slope=0.005
Boundary for River Rch & Prof#=UNT088 IN ROCK,Reach-1,7
Up Type=0
Dn Type=3
Dn Slope=0.005

--- UNT088 IN ROCK.g01 (geometry) ---

Geom Title=Existing Conditions

River Reach=UNT088 IN ROCK,Reach-1
Reach XY= 30
      3656761.61     10139358.30      3656634.84     10139937.99
      3656190.92     10140287.03      3655999.94     10140940.87
      3655765.40     10141033.59      3655891.10     10141060.41
      3655739.50     10141475.53      3655524.36     10141621.97
      3655190.39     10141507.77      3655266.11     10141742.64
      3654861.23     10142169.71      3654656.02     10142108.81
      3654390.84     10142518.04      3653837.70     10142578.75
      3653723.65     10142434.18      3653470.50     10142658.29
      3653089.35     10142687.83      3652724.71     10143012.91
      3652789.07     10143235.09      3652409.49     10143287.22
      3652187.33     10143673.79      3651942.14     10143782.07
      3652327.97     10143940.49      3652008.37     10144123.96
      3651997.92     10144684.60      3651767.25     10144698.73
      3651768.49     10145141.01      3651587.62     10145128.48
      3651478.31     10145790.08      3651212.11     10146141.64

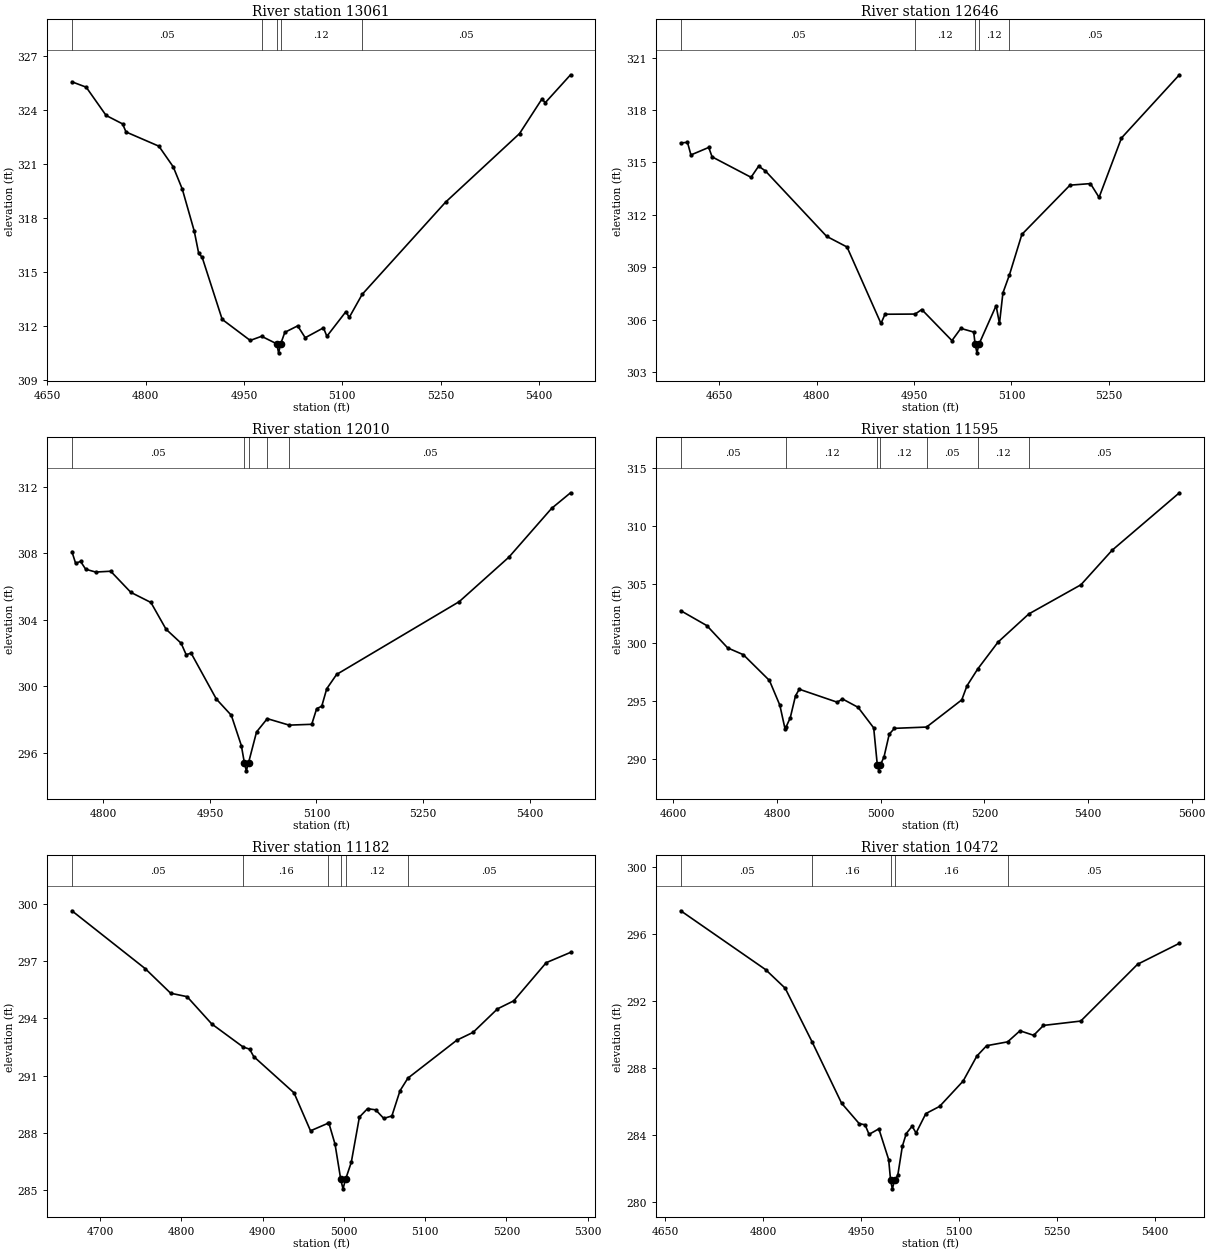
Type RM Length L Ch R = 1,13061,415,415,415
BEGIN DESCRIPTION:
UNT088 IN ROCK 25.0
END DESCRIPTION:
XS GIS Cut Line= 3
      3656377.31     10139338.82      3656662.38     10139444.72
      3657101.57     10139567.75
#Sta/Elev= 30
  4687.8  325.57  4709.6  325.27  4739.9  323.70  4765.0  323.23  4770.3  322.78
  4820.4  321.99  4842.3  320.84  4856.1  319.60  4874.3  317.27  4881.1  316.03
  4886.4  315.81  4916.9  312.36  4959.6  311.19  4977.0  311.42  5000.1  311.00
  5002.9  310.50  5006.1  311.00  5012.4  311.64  5032.0  312.00  5043.5  311.34
  5071.3  311.89  5076.5  311.42  5105.5  312.79  5110.6  312.47  5130.3  313.75
  5257.5  318.88  5370.2  322.69  5404.3  324.61  5409.5  324.41  5448.0  325.96
#Mann=5,-1,0
  4687.8    0.05       0  4977.0    0.12       0  5000.1    0.07       0
  5006.1    0.12       0  5130.3    0.05       0
Bank Sta=5000.1,5006.1
Exp/Cntr=0.3,0.1

Type RM Length L Ch R = 1,12646,636,636,636
BEGIN DESCRIPTION:
UNT088 IN ROCK 24.0
END DESCRIPTION:
XS GIS Cut Line= 3
      3656227.46     10139713.47      3656642.11     10139841.64
      3656964.23     10139929.92
#Sta/Elev= 30
  4590.7  316.12  4601.1  316.15  4606.4  315.43  4633.8  315.86  4639.0  315.32
  4699.0  314.15  4710.7  314.79  4721.2  314.51  4815.4  310.77  4846.8  310.16
  4899.1  305.78  4905.3  306.31  4951.8  306.32  4961.9  306.58  5008.4  304.80
  5022.1  305.50  5041.9  305.29  5044.1  304.60  5046.9  304.10  5050.1  304.60
  5076.4  306.80  5081.6  305.78  5086.9  307.53  5097.0  308.57  5116.1  310.88
  5190.2  313.70  5221.7  313.79  5235.0  313.00  5269.5  316.40  5358.7  320.02
#Mann=5,-1,0
  4590.7    0.05       0  4951.8    0.12       0  5044.1    0.07       0
  5050.1    0.12       0  5097.0    0.05       0
Bank Sta=5044.1,5050.1
Exp/Cntr=0.3,0.1

Type RM Length L Ch R = 1,12010,415,415,415
BEGIN DESCRIPTION:
UNT088 IN ROCK 23.0
END DESCRIPTION:
XS GIS Cut Line= 3
      3656121.45     10140024.96      3656385.62     10140296.25
      3656708.75     10140287.96
#Sta/Elev= 30
  4755.8  308.09  4761.0  307.39  4768.0  307.50  4775.2  307.03  4789.3  306.86
  4810.4  306.91  4838.7  305.64  4867.0  305.03  4888.3  303.42  4909.5  302.58
  4916.6  301.89  4923.6  301.98  4959.1  299.22  4980.2  298.24  4994.3  296.42
  4998.5  295.40  5001.3  294.90  5004.5  295.40  5015.7  297.24  5030.8  298.04
  5061.6  297.65  5093.4  297.70  5100.3  298.64  5107.5  298.79  5114.5  299.84
  5128.4  300.70  5301.0  305.08  5371.0  307.76  5431.0  310.69  5457.7  311.63
#Mann=5,-1,0
  4755.8    0.05       0  4998.5   0.035       0  5004.5    0.05       0
  5030.8    0.12       0  5061.6    0.05       0
Bank Sta=4998.5,5004.5
Exp/Cntr=0.3,0.1

Type RM Length L Ch R = 1,11595,413,413,413
BEGIN DESCRIPTION:
UNT088 IN ROCK 22.0
END DESCRIPTION:
XS GIS Cut Line= 3
      3655732.07     10140450.27      3656092.11     10140491.64
      3656692.10     10140491.64
#Sta/Elev= 30
  4614.0  302.74  4664.4  301.46  4704.6  299.55  4734.8  298.97  4785.2  296.76
  4805.3  294.64  4815.4  292.59  4817.0  292.75  4825.4  293.57  4835.5  295.45
  4842.8  296.01  4916.0  294.90  4926.1  295.18  4956.3  294.46  4986.4  292.70
  4993.4  289.52  4996.2  289.02  4999.4  289.52  5006.4  290.23  5016.4  292.16
  5026.4  292.66  5088.4  292.77  5156.4  295.10  5166.4  296.30  5187.1  297.74
  5226.4  300.05  5285.8  302.46  5386.4  304.96  5446.4  307.91  5576.4  312.84
#Mann=7,-1,0
  4614.0    0.05       0  4817.0    0.12       0  4993.4    0.07       0
  4999.4    0.12       0  5088.4    0.05       0  5187.1    0.12       0
  5285.8    0.05       0
Bank Sta=4993.4,4999.4
Exp/Cntr=0.3,0.1

Type RM Length L Ch R = 1,11182,710,710,710
BEGIN DESCRIPTION:
UNT088 IN ROCK 21.0
END DESCRIPTION:
XS GIS Cut Line= 3
      3655682.08     10140791.61      3655992.11     10140841.64
      3656292.07     10140841.64
#Sta/Elev= 30
  4665.1  299.64  4755.3  296.61  4786.7  295.32  4806.9  295.14  4837.3  293.71
  4876.0  292.50  4883.9  292.39  4889.0  292.00  4938.6  290.10  4958.9  288.11
  4980.1  288.50  4981.6  288.50  4989.1  287.41  4996.1  285.57  4998.9  285.07
  5002.1  285.57  5009.1  286.46  5019.1  288.83  5029.1  289.27  5039.1  289.21
  5049.1  288.76  5059.1  288.89  5069.1  290.21  5078.8  290.87  5139.1  292.86
  5159.1  293.27  5189.1  294.50  5209.1  294.92  5249.1  296.92  5279.1  297.46
#Mann=6,-1,0
  4665.1    0.05       0  4876.0    0.16       0  4980.1    0.12       0
  4996.1    0.07       0  5002.1    0.12       0  5078.8    0.05       0
Bank Sta=4996.1,5002.1
Exp/Cntr=0.3,0.1

Type RM Length L Ch R = 1,10472,551,551,551
BEGIN DESCRIPTION:
UNT088 IN ROCK 20.0
END DESCRIPTION:
XS GIS Cut Line= 3
      3655575.57     10140937.61      3655675.55     10141087.57
      3656160.83     10141411.87
#Sta/Elev= 30
  4674.0  297.36  4804.0  293.85  4834.0  292.74  4875.6  289.51  4920.4  285.88
  4947.4  284.66  4956.4  284.59  4962.5  284.02  4977.5  284.35  4992.5  282.52
  4995.5  281.27  4998.2  280.77  5001.5  281.27  5006.5  281.58  5013.5  283.31
  5019.5  284.07  5028.5  284.51  5034.5  284.10  5049.5  285.26  5070.6  285.69
  5106.6  287.20  5127.6  288.69  5142.6  289.31  5174.8  289.54  5193.7  290.20
  5214.7  289.93  5229.7  290.52  5286.8  290.78  5373.9  294.17  5437.9  295.42
#Mann=5,-1,0
  4674.0    0.05       0  4875.6    0.16       0  4995.5    0.07       0
  5001.5    0.16       0  5174.8    0.05       0
Bank Sta=4995.5,5001.5
Exp/Cntr=0.3,0.1

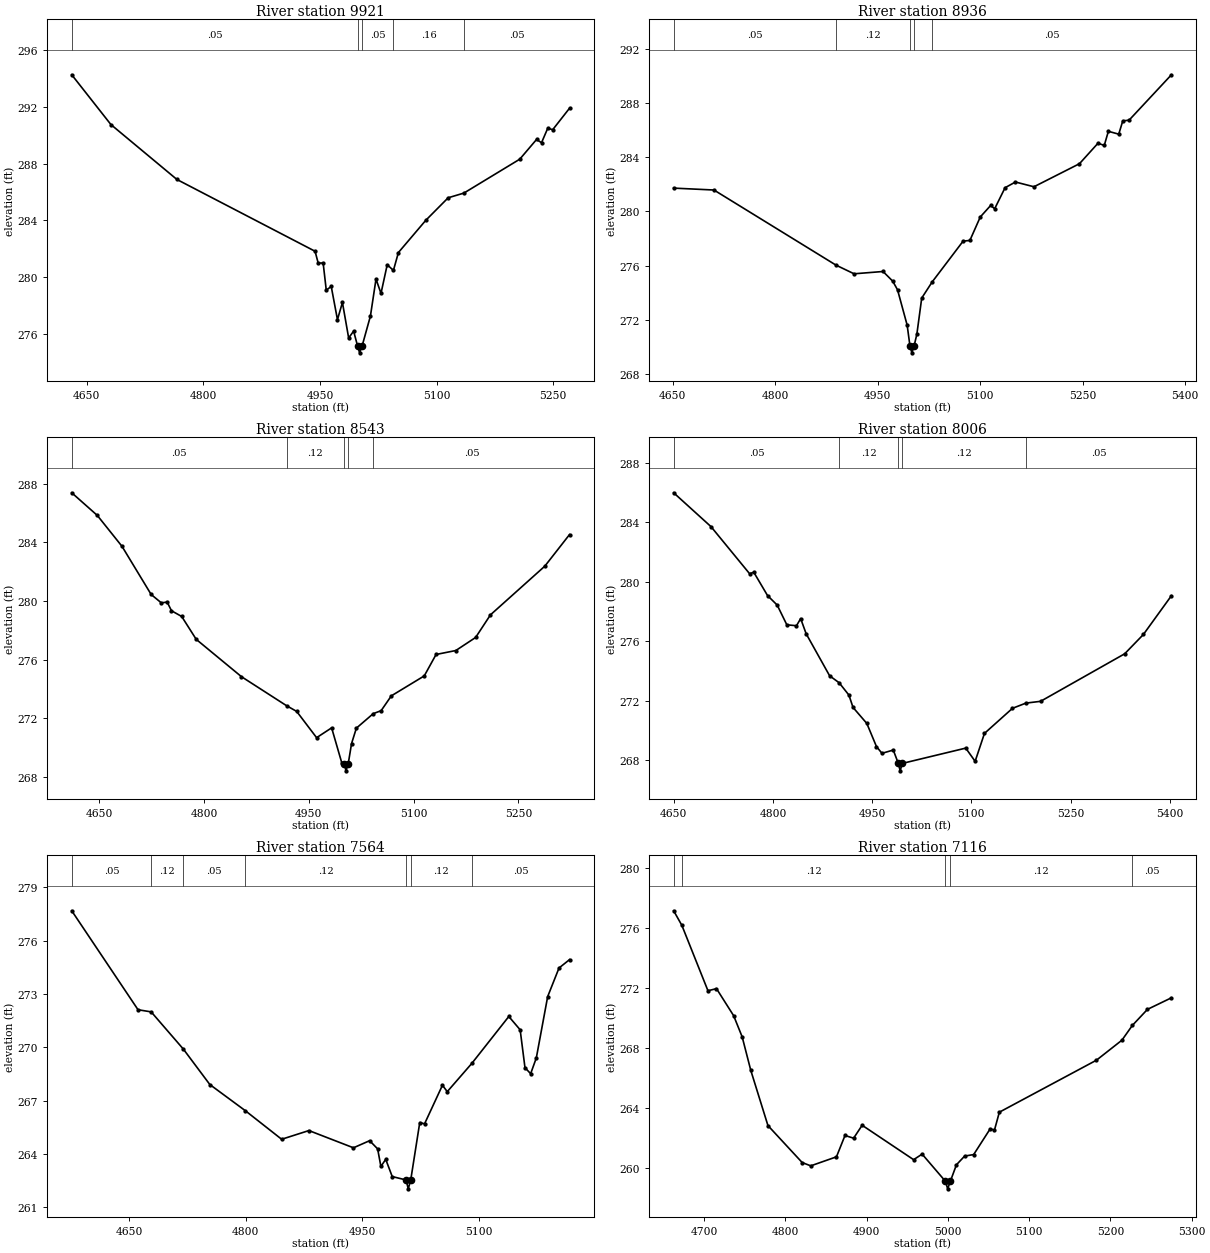
Type RM Length L Ch R = 1,9921,985,985,985
BEGIN DESCRIPTION:
UNT088 IN ROCK 19.0
END DESCRIPTION:
XS GIS Cut Line= 3
      3655442.10     10141191.64      3655642.11     10141441.64
      3655842.10     10141691.63
#Sta/Elev= 30
  4630.7  294.27  4681.1  290.76  4766.0  286.89  4943.7  281.83  4947.7  281.00
  4954.1  281.00  4958.1  279.09  4964.5  279.35  4972.5  277.01  4978.9  278.22
  4986.9  275.72  4993.3  276.20  4998.3  275.17  5001.0  274.67  5004.3  275.17
  5014.9  277.26  5022.1  279.87  5028.5  278.86  5036.5  280.88  5044.5  280.48
  5050.9  281.74  5086.1  284.01  5114.9  285.60  5135.1  285.93  5207.0  288.32
  5228.6  289.71  5235.0  289.48  5243.0  290.50  5249.4  290.40  5271.0  291.91
#Mann=5,-1,0
  4630.7    0.05       0  4998.3    0.03       0  5004.3    0.05       0
  5044.5    0.16       0  5135.1    0.05       0
Bank Sta=4998.3,5004.3
Exp/Cntr=0.3,0.1

Type RM Length L Ch R = 1,8936,393,393,393
BEGIN DESCRIPTION:
UNT088 IN ROCK 17.0
END DESCRIPTION:
XS GIS Cut Line= 3
      3654987.85     10141512.45      3655287.85     10141812.46
      3655543.66     10141977.31
#Sta/Elev= 30
  4651.2  281.71  4710.2  281.57  4888.8  276.03  4915.3  275.39  4957.7  275.56
  4971.8  274.85  4978.9  274.21  4993.0  271.60  4997.1  270.06  4999.9  269.56
  5003.1  270.06  5007.2  270.94  5014.3  273.60  5029.6  274.79  5074.9  277.80
  5084.8  277.85  5100.0  279.58  5115.2  280.43  5121.1  280.19  5136.3  281.74
  5151.5  282.16  5178.6  281.81  5245.2  283.51  5272.3  285.02  5281.5  284.86
  5287.5  285.90  5302.7  285.69  5308.6  286.67  5317.8  286.72  5379.8  290.07
#Mann=5,-1,0
  4651.2    0.05       0  4888.8    0.12       0  4997.1    0.07       0
  5003.1    0.12       0  5029.6    0.05       0
Bank Sta=4997.1,5003.1
Exp/Cntr=0.3,0.1

Type RM Length L Ch R = 1,8543,537,537,537
BEGIN DESCRIPTION:
UNT088 IN ROCK 16.0
END DESCRIPTION:
XS GIS Cut Line= 3
      3654642.07     10141791.62      3655045.21     10142094.56
      3655192.07     10142241.61
#Sta/Elev= 30
  4610.9  287.37  4647.4  285.83  4682.8  283.72  4724.5  280.44  4739.0  279.87
  4747.4  279.92  4753.6  279.33  4768.2  278.94  4789.0  277.38  4853.6  274.84
  4918.2  272.86  4932.7  272.47  4961.2  270.68  4982.7  271.35  4997.3  268.95
  5000.5  268.92  5003.3  268.42  5006.5  268.92  5011.2  270.28  5018.1  271.33
  5042.3  272.32  5053.5  272.52  5068.1  273.53  5115.2  274.89  5132.1  276.35
  5160.4  276.62  5188.7  277.51  5209.9  279.05  5287.7  282.37  5323.0  284.52
#Mann=5,-1,0
  4610.9    0.05       0  4918.2    0.12       0  5000.5    0.07       0
  5006.5    0.12       0  5042.3    0.05       0
Bank Sta=5000.5,5006.5
Exp/Cntr=0.3,0.1

Type RM Length L Ch R = 1,8006,442,442,442
BEGIN DESCRIPTION:
UNT088 IN ROCK 15.0
END DESCRIPTION:
XS GIS Cut Line= 3
      3654395.80     10141928.02      3654592.11     10142191.64
      3654892.07     10142491.61
#Sta/Elev= 30
  4649.7  286.00  4706.2  283.72  4764.6  280.55  4770.9  280.65  4791.7  279.08
  4806.3  278.44  4820.9  277.11  4835.5  277.05  4841.8  277.53  4850.1  276.51
  4885.6  273.68  4900.0  273.21  4914.8  272.38  4921.0  271.55  4941.9  270.47
  4956.5  268.91  4964.8  268.46  4981.9  268.68  4989.5  267.78  4992.3  267.28
  4995.5  267.78  5091.5  268.81  5105.7  267.92  5119.8  269.80  5162.2  271.49
  5182.5  271.84  5204.7  271.96  5331.9  275.16  5360.2  276.46  5402.6  279.07
#Mann=5,-1,0
  4649.7    0.05       0  4900.0    0.12       0  4989.5    0.07       0
  4995.5    0.12       0  5182.5    0.05       0
Bank Sta=4989.5,4995.5
Exp/Cntr=0.3,0.1

Type RM Length L Ch R = 1,7564,448,448,448
BEGIN DESCRIPTION:
UNT088 IN ROCK 14.0
END DESCRIPTION:
XS GIS Cut Line= 3
      3654092.11     10142191.65      3654342.11     10142491.64
      3654492.10     10142691.64
#Sta/Elev= 30
  4576.1  277.68  4661.4  272.11  4678.3  271.99  4719.8  269.89  4753.8  267.90
  4799.4  266.43  4846.2  264.82  4881.3  265.31  4938.6  264.34  4959.4  264.74
  4969.7  264.28  4973.9  263.29  4980.1  263.69  4988.5  262.72  5006.3  262.53
  5009.1  262.03  5012.3  262.53  5023.9  265.76  5030.1  265.69  5053.1  267.86
  5059.3  267.50  5090.9  269.09  5138.5  271.73  5153.1  270.98  5159.3  268.85
  5166.6  268.51  5173.9  269.40  5188.5  272.85  5203.1  274.46  5216.6  274.93
#Mann=7,-1,0
  4576.1    0.05       0  4678.3    0.12       0  4719.8    0.05       0
  4799.4    0.12       0  5006.3    0.07       0  5012.3    0.12       0
  5090.9    0.05       0
Bank Sta=5006.3,5012.3
Exp/Cntr=0.3,0.1

Type RM Length L Ch R = 1,7116,340,340,340
BEGIN DESCRIPTION:
UNT088 IN ROCK 13.0
END DESCRIPTION:
XS GIS Cut Line= 3
      3653842.10     10142241.63      3653942.11     10142541.64
      3654037.47     10142822.03
#Sta/Elev= 30
  4662.7  277.14  4672.8  276.17  4704.9  271.82  4715.4  271.96  4736.5  270.16
  4747.0  268.75  4757.6  266.52  4778.7  262.85  4820.8  260.39  4831.4  260.17
  4863.0  260.77  4873.5  262.19  4884.1  262.01  4894.6  262.87  4957.9  260.58
  4968.4  260.95  4997.1  259.14  4999.8  258.64  5003.1  259.14  5010.6  260.24
  5020.7  260.82  5031.8  260.92  5052.1  262.63  5057.4  262.55  5063.4  263.74
  5182.9  267.20  5214.2  268.53  5227.0  269.51  5245.6  270.58  5275.1  271.35
#Mann=5,-1,0
  4662.7    0.05       0  4672.8    0.12       0  4997.1    0.07       0
  5003.1    0.12       0  5227.0    0.05       0
Bank Sta=4997.1,5003.1
Exp/Cntr=0.3,0.1

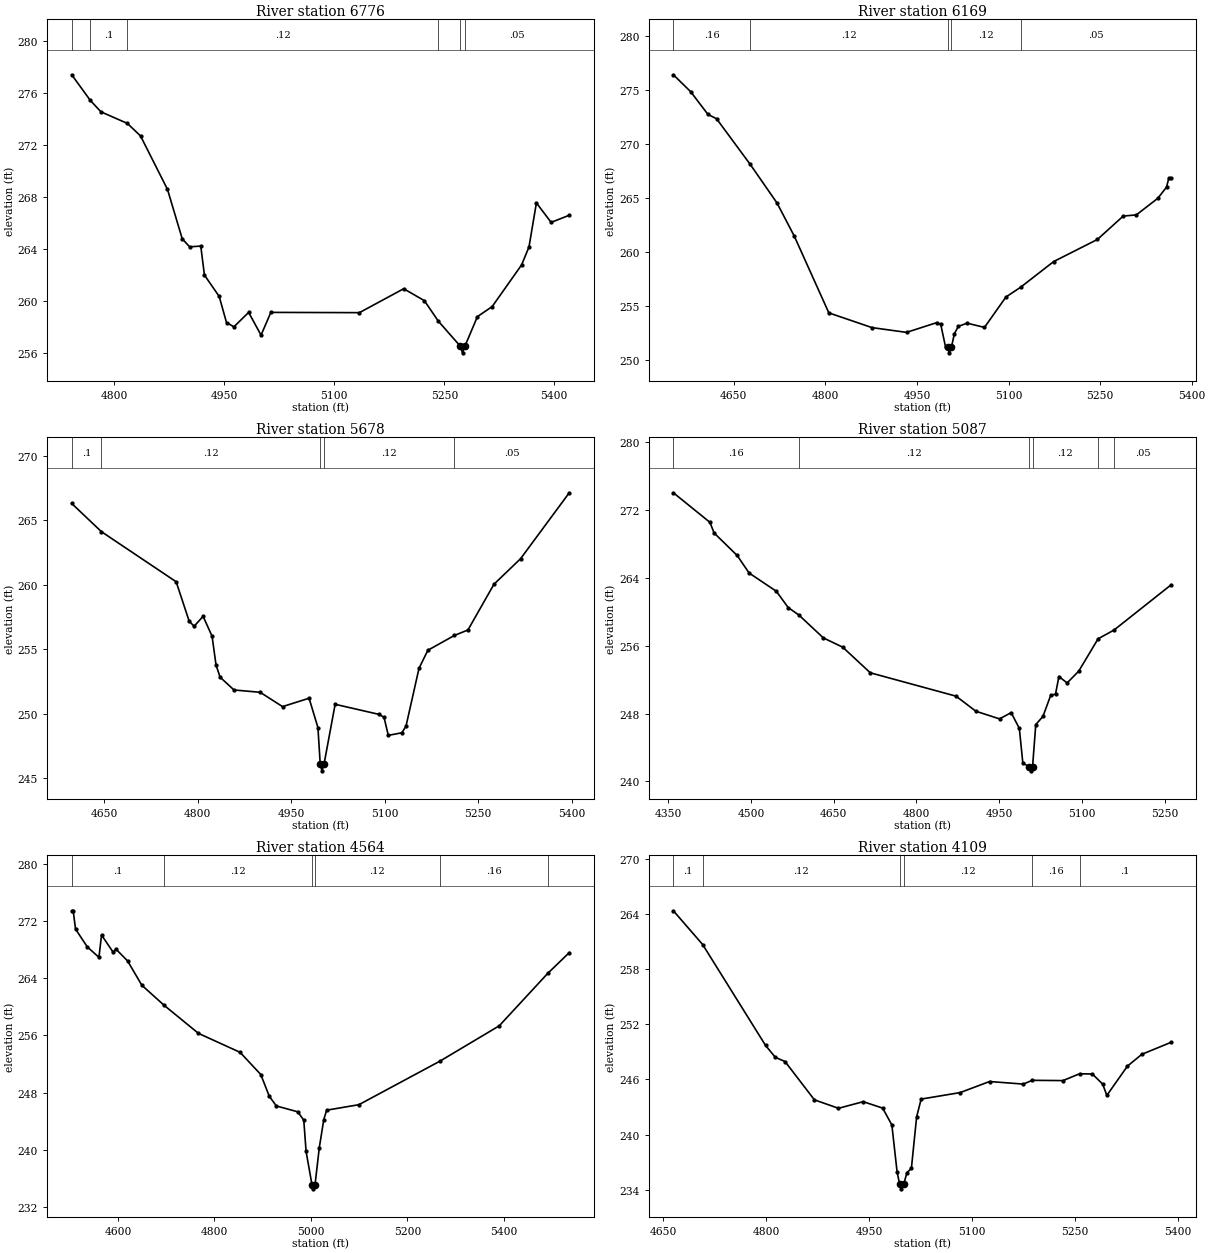
Type RM Length L Ch R = 1,6776,607,607,607
BEGIN DESCRIPTION:
UNT088 IN ROCK 12.0
END DESCRIPTION:
XS GIS Cut Line= 3
      3653738.09     10142182.01      3653689.27     10142588.81
      3653717.64     10142856.19
#Sta/Elev= 30
  4741.8  277.42  4767.0  275.46  4781.7  274.57  4817.7  273.68  4835.6  272.72
  4872.4  268.61  4892.5  264.81  4902.6  264.19  4917.8  264.25  4922.8  262.02
  4942.9  260.38  4952.9  258.37  4963.0  258.04  4983.1  259.15  5000.0  257.40
  5013.4  259.15  5134.2  259.13  5194.6  260.97  5222.8  260.05  5241.9  258.47
  5272.0  256.54  5274.8  256.04  5278.0  256.54  5295.1  258.82  5315.3  259.60
  5355.5  262.81  5365.5  264.19  5375.6  267.57  5395.7  266.07  5420.4  266.62
#Mann=6,-1,0
  4741.8    0.05       0  4767.0     0.1       0  4817.7    0.12       0
  5241.9    0.05       0  5272.0    0.07       0  5278.0    0.05       0
Bank Sta=5272,5278
Exp/Cntr=0.3,0.1

Type RM Length L Ch R = 1,6169,491,491,491
BEGIN DESCRIPTION:
UNT088 IN ROCK 11.0
END DESCRIPTION:
XS GIS Cut Line= 3
      3652942.10     10142391.64      3653242.11     10142691.64
      3653492.12     10142991.66
#Sta/Elev= 30
  4551.1  276.38  4579.4  274.82  4607.7  272.72  4621.8  272.32  4677.0  268.10
  4720.8  264.54  4749.1  261.48  4805.7  254.39  4876.4  253.03  4932.9  252.59
  4982.5  253.49  4989.0  253.32  4996.8  251.25  5000.4  251.20  5003.1  250.70
  5006.4  251.20  5011.2  252.45  5017.7  253.14  5032.0  253.44  5060.6  253.05
  5095.8  255.86  5119.6  256.75  5173.9  259.13  5245.5  261.17  5287.8  263.33
  5309.3  263.44  5344.4  264.97  5358.7  266.00  5362.6  266.86  5365.9  266.86
#Mann=5,-1,0
  4551.1    0.16       0  4677.0    0.12       0  5000.4    0.07       0
  5006.4    0.12       0  5119.6    0.05       0
Bank Sta=5000.4,5006.4
Exp/Cntr=0.3,0.1

Type RM Length L Ch R = 1,5678,591,591,591
BEGIN DESCRIPTION:
UNT088 IN ROCK 10.0
END DESCRIPTION:
XS GIS Cut Line= 3
      3652626.61     10142681.49      3652853.18     10142863.80
      3653192.11     10143241.65
#Sta/Elev= 30
  4597.9  266.31  4645.4  264.13  4765.5  260.24  4786.3  257.19  4794.3  256.79
  4808.7  257.56  4823.1  256.02  4829.5  253.78  4836.0  252.84  4858.3  251.85
  4900.3  251.67  4936.2  250.56  4978.8  251.21  4993.0  248.93  4996.7  246.08
  4999.5  245.58  5002.7  246.08  5020.6  250.74  5091.7  249.95  5099.1  249.72
  5105.9  248.33  5127.6  248.53  5134.3  249.04  5155.2  253.53  5169.4  254.93
  5212.1  256.08  5233.7  256.50  5275.5  260.05  5318.2  262.03  5396.3  267.14
#Mann=5,-1,0
  4597.9     0.1       0  4645.4    0.12       0  4996.7    0.07       0
  5002.7    0.12       0  5212.1    0.05       0
Bank Sta=4996.7,5002.7
Exp/Cntr=0.3,0.1

Type RM Length L Ch R = 1,5087,523,523,523
BEGIN DESCRIPTION:
UNT088 IN ROCK 9.0
END DESCRIPTION:
XS GIS Cut Line= 3
      3652322.77     10142777.27      3652688.04     10143175.04
      3652893.09     10143472.48
#Sta/Elev= 30
  4359.6  274.06  4425.9  270.57  4433.3  269.32  4475.2  266.66  4496.8  264.59
  4546.1  262.44  4567.7  260.51  4586.9  259.64  4631.2  256.94  4666.4  255.84
  4716.3  252.82  4871.7  250.06  4907.7  248.28  4950.5  247.38  4971.5  248.12
  4986.3  246.26  4992.7  242.15  5004.3  241.75  5007.0  241.25  5010.3  241.75
  5016.1  246.71  5029.1  247.67  5043.1  250.15  5051.9  250.31  5058.0  252.38
  5072.9  251.62  5093.9  253.01  5129.0  256.83  5157.8  257.86  5260.9  263.18
#Mann=6,-1,0
  4359.6    0.16       0  4586.9    0.12       0  5004.3    0.07       0
  5010.3    0.12       0  5129.0    0.16       0  5157.8    0.05       0
Bank Sta=5004.3,5010.3
Exp/Cntr=0.3,0.1

Type RM Length L Ch R = 1,4564,455,455,455
BEGIN DESCRIPTION:
UNT088 IN ROCK 8.0
END DESCRIPTION:
XS GIS Cut Line= 3
      3651948.11     10143164.39      3652392.11     10143341.64
      3652863.88     10143630.60
#Sta/Elev= 30
  4504.3  273.44  4507.3  273.44  4512.2  270.88  4536.4  268.40  4560.7  266.92
  4566.1  270.05  4590.3  267.62  4595.7  268.09  4620.0  266.43  4649.6  263.02
  4695.8  260.21  4767.0  256.28  4853.2  253.63  4896.2  250.52  4913.7  247.49
  4928.5  246.12  4972.9  245.30  4985.3  244.13  4990.1  239.75  5002.5  235.02
  5005.3  234.52  5008.5  235.02  5017.5  240.30  5026.8  244.22  5032.7  245.53
  5099.6  246.30  5267.2  252.38  5390.5  257.34  5491.2  264.69  5535.6  267.58
#Mann=6,-1,0
  4504.3     0.1       0  4695.8    0.12       0  5002.5    0.07       0
  5008.5    0.12       0  5267.2    0.16       0  5491.2    0.05       0
Bank Sta=5002.5,5008.5
Exp/Cntr=0.3,0.1

Type RM Length L Ch R = 1,4109,1077,1077,1077
BEGIN DESCRIPTION:
UNT088 IN ROCK 7.0
END DESCRIPTION:
XS GIS Cut Line= 3
      3651942.09     10143441.63      3652353.00     10143799.68
      3652503.00     10143899.68
#Sta/Elev= 30
  4664.8  264.33  4707.5  260.66  4799.1  249.71  4813.4  248.41  4827.6  247.95
  4870.4  243.79  4905.5  242.87  4941.6  243.59  4969.9  242.89  4983.3  241.06
  4990.9  235.98  4994.6  234.62  4997.3  234.12  5000.6  234.62  5005.2  235.86
  5011.8  236.36  5019.4  241.93  5026.0  243.87  5083.0  244.58  5125.7  245.78
  5175.1  245.50  5187.8  245.91  5232.8  245.88  5256.9  246.62  5275.6  246.60
  5290.7  245.49  5296.7  244.27  5326.7  247.45  5347.8  248.74  5390.1  250.03
#Mann=6,-1,0
  4664.8     0.1       0  4707.5    0.12       0  4994.6    0.07       0
  5000.6    0.12       0  5187.8    0.16       0  5256.9     0.1       0
Bank Sta=4994.6,5000.6
Exp/Cntr=0.3,0.1

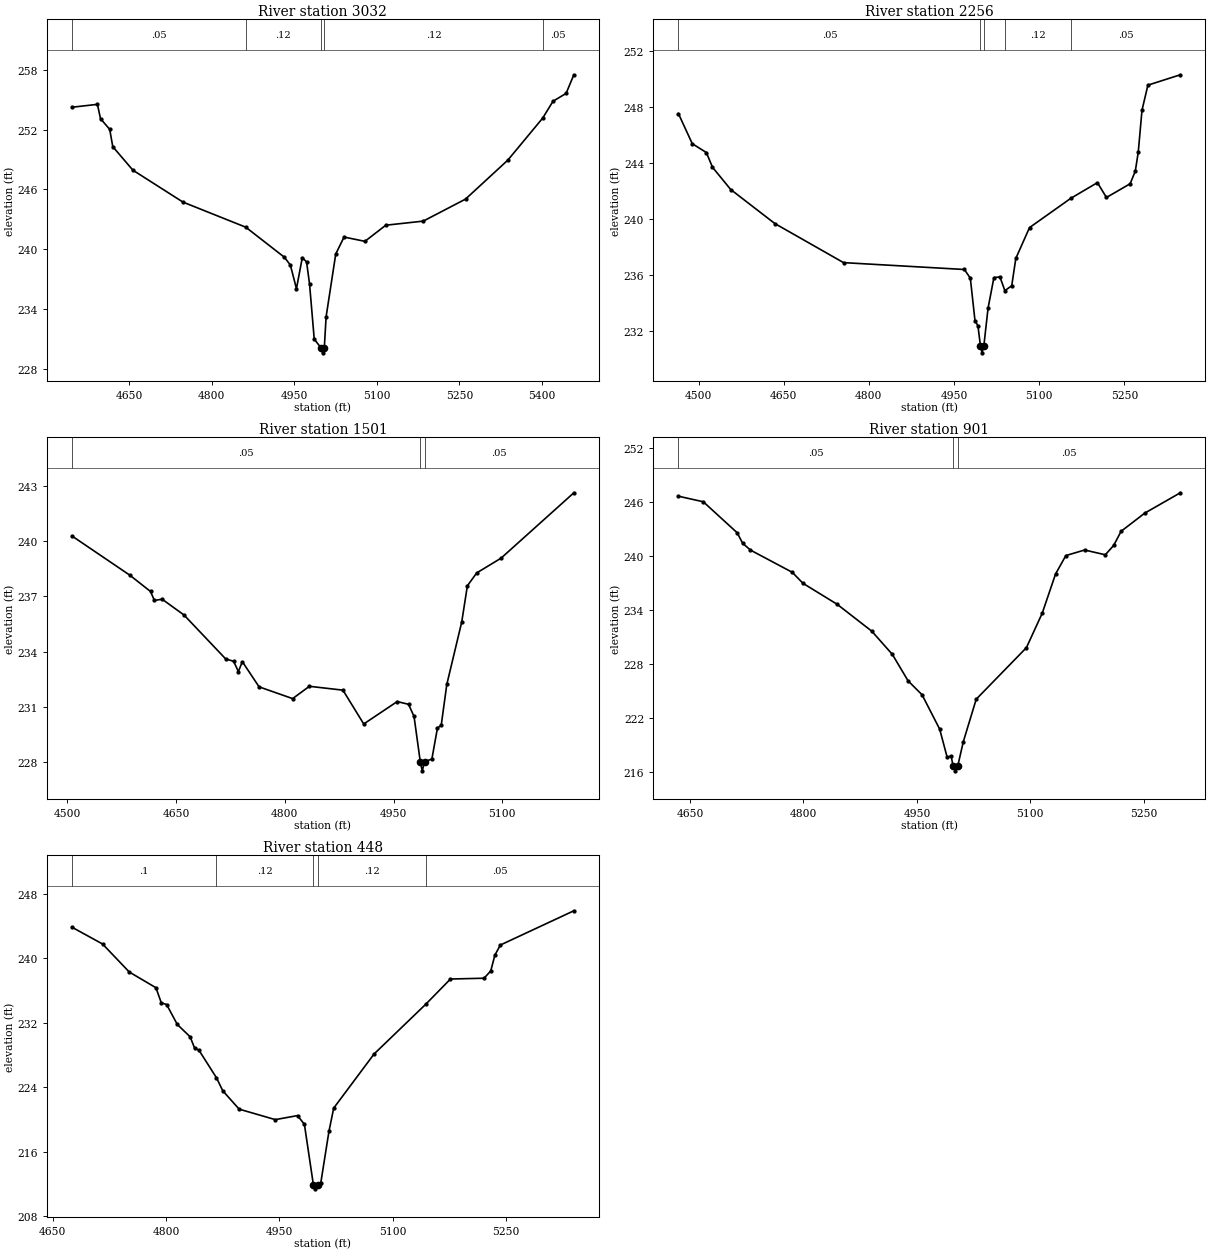
Type RM Length L Ch R = 1,3032,776,776,776
BEGIN DESCRIPTION:
UNT088 IN ROCK 5.0
END DESCRIPTION:
XS GIS Cut Line= 3
      3651709.12     10143904.24      3651809.08     10143954.22
      3652547.34     10144263.27
#Sta/Elev= 30
  4546.0  254.25  4592.3  254.54  4597.9  253.10  4614.6  252.03  4620.2  250.29
  4656.7  247.93  4747.8  244.72  4861.9  242.20  4932.1  239.18  4942.9  238.40
  4954.0  236.02  4964.6  239.15  4972.4  238.71  4977.8  236.48  4986.3  230.96
  4998.6  230.08  5001.4  229.58  5004.6  230.08  5007.9  233.21  5025.4  239.51
  5040.5  241.21  5078.4  240.78  5116.4  242.40  5184.4  242.81  5261.2  245.02
  5338.0  248.93  5401.5  253.16  5420.2  254.85  5444.0  255.64  5458.1  257.51
#Mann=5,-1,0
  4546.0    0.05       0  4861.9    0.12       0  4998.6    0.07       0
  5004.6    0.12       0  5401.5    0.05       0
Bank Sta=4998.6,5004.6
Exp/Cntr=0.3,0.1

Type RM Length L Ch R = 1,2256,755,755,755
BEGIN DESCRIPTION:
UNT088 IN ROCK 4.0
END DESCRIPTION:
XS GIS Cut Line= 3
      3651486.00     10144417.37      3651758.90     10144520.69
      3652326.88     10144687.95
#Sta/Elev= 30
  4464.6  247.55  4489.0  245.40  4513.8  244.77  4524.6  243.72  4556.7  242.13
  4634.4  239.70  4755.4  236.91  4968.2  236.42  4978.7  235.80  4986.9  232.76
  4992.1  232.40  4996.5  230.97  4999.3  230.47  5002.5  230.97  5009.9  233.66
  5020.2  235.84  5030.8  235.89  5039.5  234.91  5051.6  235.26  5058.8  237.21
  5082.9  239.41  5155.6  241.50  5202.5  242.62  5218.4  241.56  5260.1  242.54
  5269.2  243.44  5274.4  244.79  5281.0  247.79  5291.4  249.58  5348.5  250.32
#Mann=5,-1,0
  4464.6    0.05       0  4996.5    0.03       0  5002.5    0.05       0
  5039.5    0.12       0  5155.6    0.05       0
Bank Sta=4996.5,5002.5
Exp/Cntr=0.3,0.1

Type RM Length L Ch R = 1,1501,600,600,600
BEGIN DESCRIPTION:
UNT088 IN ROCK 3.0
END DESCRIPTION:
XS GIS Cut Line= 3
      3651348.67     10144841.99      3651792.11     10145041.64
      3651992.14     10145091.65
#Sta/Elev= 30
  4506.3  240.29  4586.0  238.16  4614.7  237.27  4620.1  236.78  4630.7  236.85
  4660.9  235.99  4718.4  233.60  4729.4  233.47  4735.9  232.91  4741.4  233.45
  4764.5  232.08  4810.8  231.44  4833.9  232.11  4880.2  231.90  4908.9  230.06
  4955.1  231.28  4970.7  231.13  4978.3  230.47  4986.9  228.01  4989.6  227.51
  4992.9  228.01  5002.9  228.15  5010.6  229.84  5015.8  229.99  5023.5  232.21
  5044.1  235.61  5051.9  237.58  5064.8  238.28  5098.3  239.08  5198.8  242.64
#Mann=3,-1,0
  4506.3    0.05       0  4986.9    0.03       0  4992.9    0.05       0
Bank Sta=4986.9,4992.9
Exp/Cntr=0.3,0.1

Type RM Length L Ch R = 1,901,453,453,453
BEGIN DESCRIPTION:
UNT088 IN ROCK 2.0
END DESCRIPTION:
XS GIS Cut Line= 3
      3651240.48     10145295.74      3651400.62     10145341.60
      3651877.20     10145483.01
#Sta/Elev= 30
  4634.6  246.65  4667.5  246.03  4712.4  242.58  4719.5  241.42  4729.9  240.66
  4785.2  238.19  4799.3  236.97  4844.5  234.64  4890.3  231.65  4917.5  229.07
  4938.3  226.13  4956.8  224.58  4980.1  220.76  4990.0  217.63  4995.2  217.79
  4997.9  216.63  5000.7  216.13  5003.9  216.63  5011.3  219.36  5028.4  224.09
  5094.8  229.82  5115.7  233.65  5133.3  238.00  5146.9  240.05  5171.7  240.67
  5199.1  240.14  5210.2  241.18  5220.0  242.75  5251.3  244.77  5298.3  247.03
#Mann=3,-1,0
  4634.6    0.05       0  4997.9    0.03       0  5003.9    0.05       0
Bank Sta=4997.9,5003.9
Exp/Cntr=0.3,0.1

Type RM Length L Ch R = 1,448,0,0,0
BEGIN DESCRIPTION:
UNT088 IN ROCK 1.0
END DESCRIPTION:
XS GIS Cut Line= 3
      3651188.16     10145658.32      3651288.13     10145758.29
      3651772.09     10145957.12
#Sta/Elev= 30
  4675.4  243.88  4715.9  241.80  4751.3  238.32  4786.6  236.37  4793.7  234.50
  4800.8  234.28  4814.9  231.81  4831.9  230.28  4838.0  228.83  4843.4  228.64
  4866.8  225.19  4875.1  223.58  4896.8  221.30  4944.7  220.00  4974.1  220.50
  4983.2  219.42  4995.1  211.91  4997.8  211.41  5001.1  211.91  5004.9  212.14
  5015.7  218.54  5022.0  221.43  5075.4  228.14  5144.0  234.33  5176.6  237.45
  5221.1  237.55  5230.0  238.46  5235.4  240.41  5242.7  241.67  5340.0  245.92
#Mann=5,-1,0
  4675.4     0.1       0  4866.8    0.12       0  4995.1    0.07       0
  5001.1    0.12       0  5144.0    0.05       0
Bank Sta=4995.1,5001.1
Exp/Cntr=0.3,0.1

Chan Stop Cuts=-1