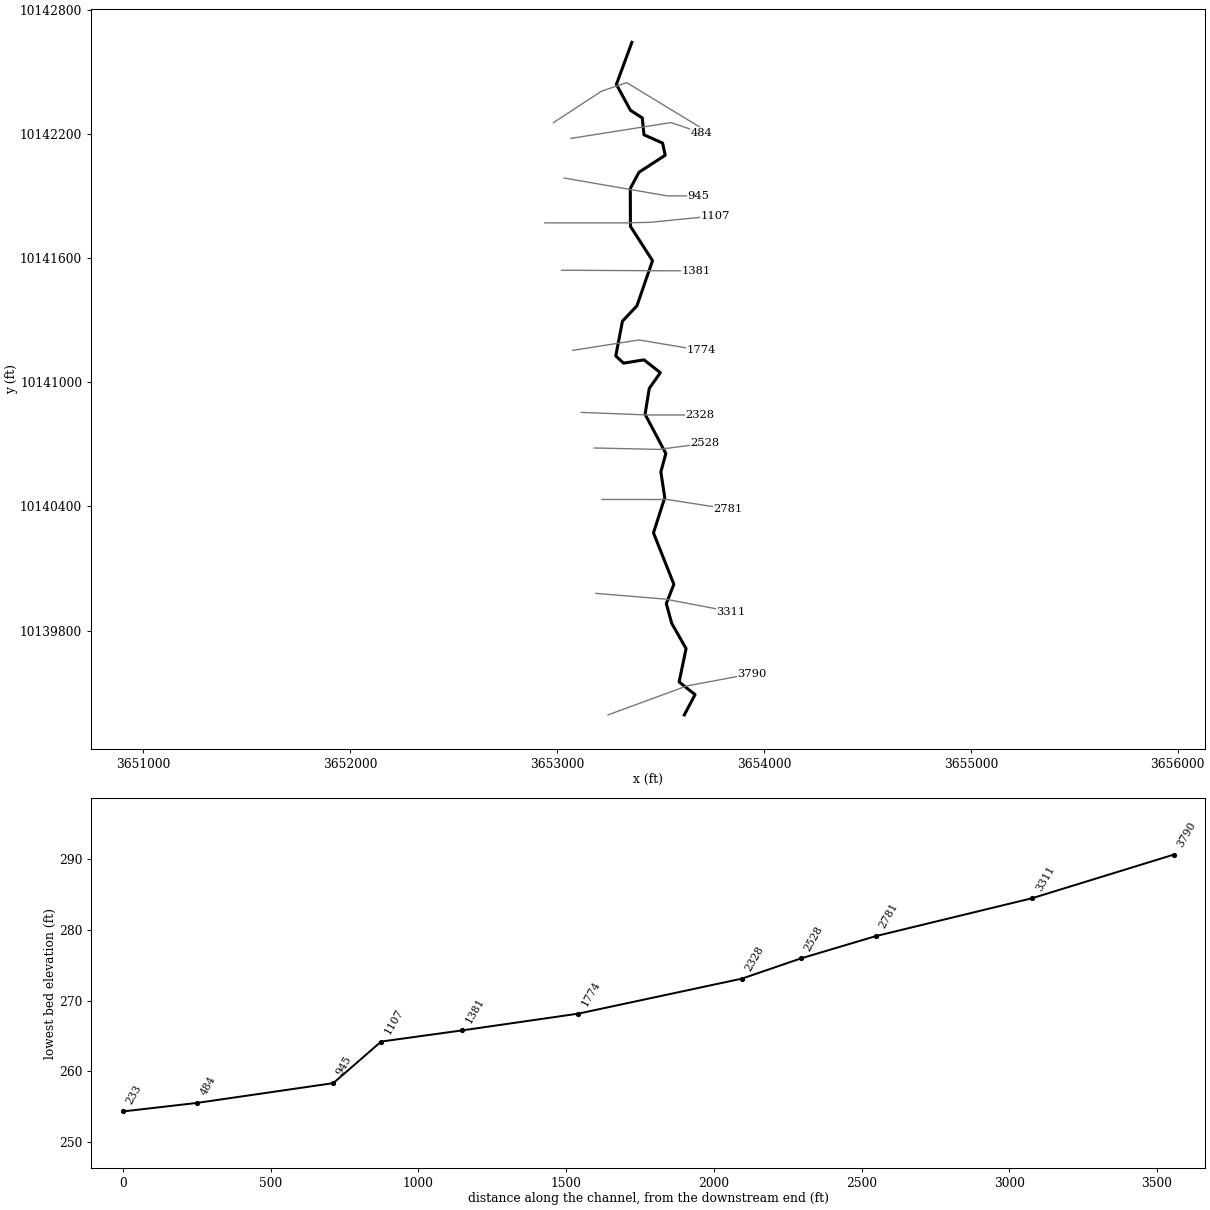
--- UNT089 IN ROCK.prj (project) ---

Proj Title=UNT089 IN ROCK Base Level Engineering
Current Plan=p01
Default Exp/Contr=0.3,0.1
English Units
Geom File=g01
Flow File=f01
Plan File=p01
Y Axis Title=Elevation
X Axis Title(PF)=Main Channel Distance
X Axis Title(XS)=Station
BEGIN DESCRIPTION:
UNT089 IN ROCK
END DESCRIPTION:
DSS Export Rating Curves= 0
DSS Export Rating Curve Sorted= 0
DSS Export Volume Flow Curves= 0
DXF OffsetX= 0
DXF OffsetY= 0
DXF ScaleX= 1
DXF ScaleY= 10

--- UNT089 IN ROCK.p01 (plan) ---

Plan Title=Multiple Run
Short Identifier=Multiple
Geom File=g01
Flow File=f01
Subcritical Flow
K Sum by GR= 0
Std Step Tol= 0.01
Critical Tol= 0.01
Num of Std Step Trials= 20
Max Error Tol= 0.3
Flow Tol Ratio= 0.001
Split Flow NTrial= 30
Split Flow Tol= 0.02
Split Flow Ratio= 0.02
Log Output Level= 0
Friction Slope Method= 1
Unsteady Friction Slope Method= 2
Unsteady Bridges Friction Slope Method= 1
Parabolic Critical Depth
Global Vel Dist=  1 , 1 , 1
Global Log Level= 0
CheckData=True
Encroach Param= -1, 0, 0, 0
BEGIN DESCRIPTION:
Multiple Run
END DESCRIPTION:

--- UNT089 IN ROCK.f01 (steady flow) ---

Flow Title=Multiple
Number of Profiles=7
Profile Names=10-year,25-year,50-year,1pct_min,100-year,1pct_plu,500-year
River Rch & RM= UNT089 IN ROCK,Reach-1,3790
     242     307     358     307     415     562     559
Boundary for River Rch & Prof#=UNT089 IN ROCK,Reach-1,1
Up Type=0
Dn Type=3
Dn Slope=0.005
Boundary for River Rch & Prof#=UNT089 IN ROCK,Reach-1,2
Up Type=0
Dn Type=3
Dn Slope=0.005
Boundary for River Rch & Prof#=UNT089 IN ROCK,Reach-1,3
Up Type=0
Dn Type=3
Dn Slope=0.005
Boundary for River Rch & Prof#=UNT089 IN ROCK,Reach-1,4
Up Type=0
Dn Type=3
Dn Slope=0.005
Boundary for River Rch & Prof#=UNT089 IN ROCK,Reach-1,5
Up Type=0
Dn Type=3
Dn Slope=0.005
Boundary for River Rch & Prof#=UNT089 IN ROCK,Reach-1,6
Up Type=0
Dn Type=3
Dn Slope=0.005
Boundary for River Rch & Prof#=UNT089 IN ROCK,Reach-1,7
Up Type=0
Dn Type=3
Dn Slope=0.005

--- UNT089 IN ROCK.g01 (geometry) ---

Geom Title=Existing Conditions
Program Version=4.10

River Reach=UNT089 IN ROCK  ,Reach-1
Reach XY= 30
      3653615.43     10139392.93      3653667.31     10139490.97
      3653590.33     10139551.98      3653623.91     10139713.19
      3653554.56     10139834.95      3653528.42     10139930.21
      3653564.88     10140023.96      3653466.36     10140272.29
      3653520.92     10140442.25      3653502.03     10140566.59
      3653526.16     10140655.65      3653425.81      10140845.2
      3653446.11     10140970.09      3653499.64     10141046.12
      3653420.62     10141108.01      3653322.09     10141092.16
      3653284.22     10141126.71      3653316.48     10141294.62
      3653386.46     10141369.19      3653461.76     10141587.04
      3653355.08     10141752.95      3653354.36     10141935.62
      3653396.19     10142013.91      3653523.02     10142096.52
      3653510.36      10142155.2      3653420.46     10142195.14
      3653412.24     10142276.63      3653355.11     10142313.67
      3653287.22     10142438.55      3653362.11     10142641.64

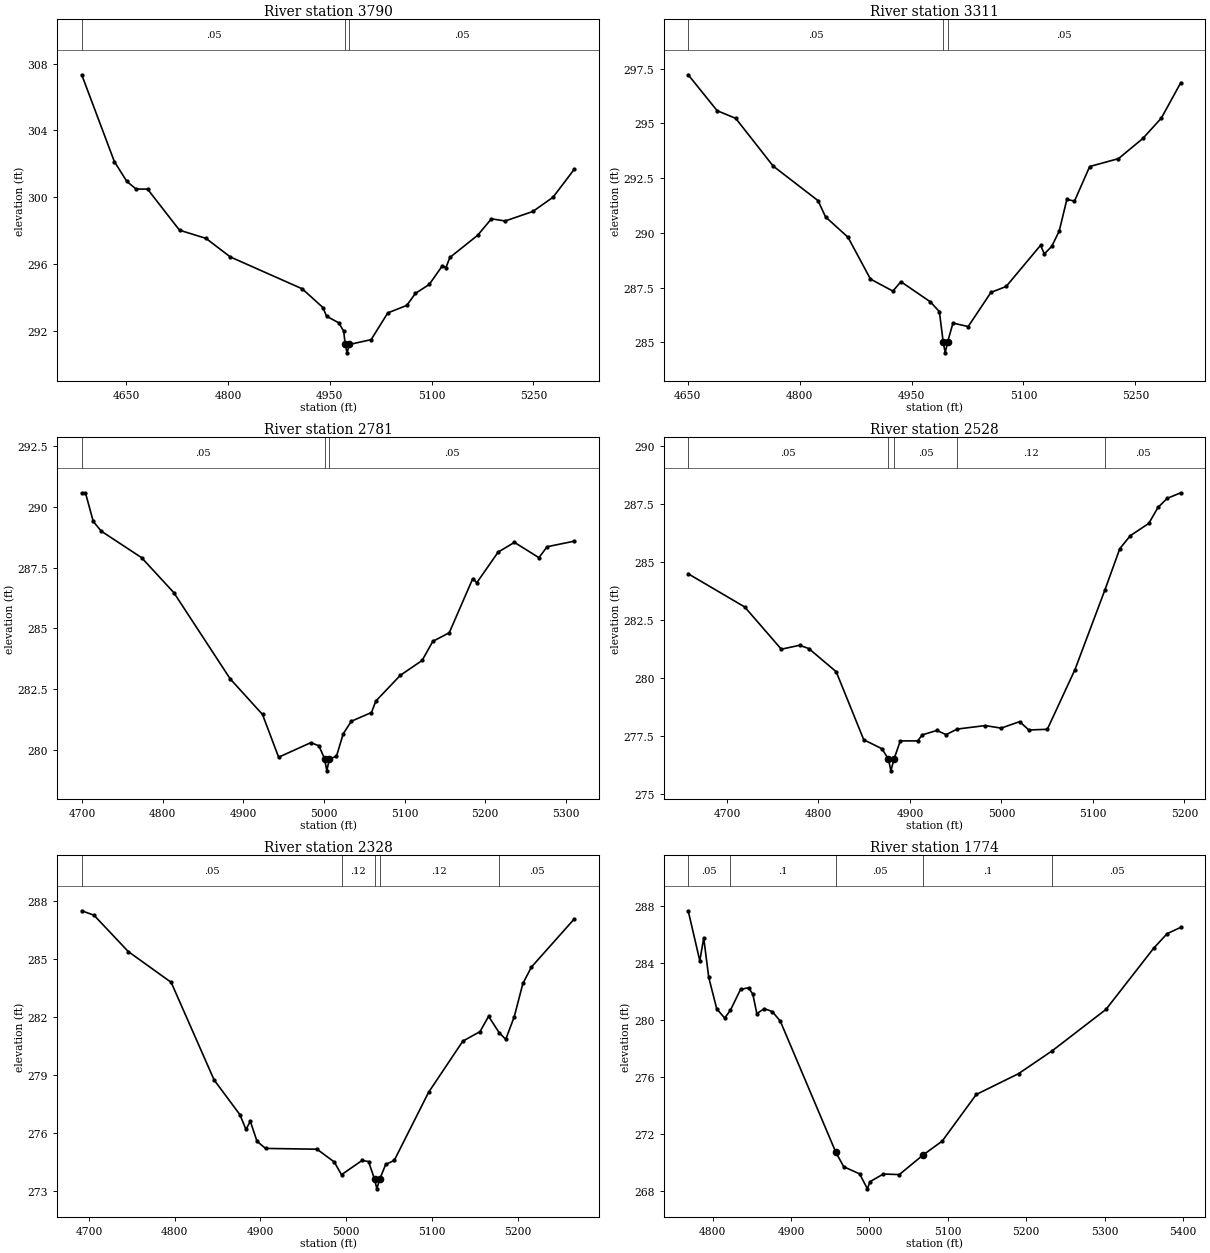
Type RM Length L Ch R = 1 ,3790    ,479,479,479
BEGIN DESCRIPTION:
UNT089 IN ROCK 8.0
END DESCRIPTION:
XS GIS Cut Line= 3
      3653246.94     10139392.94      3653627.16     10139532.58
      3653942.12     10139591.64
#Sta/Elev= 30
  4584.7  307.33  4632.8  302.13  4651.1  300.95  4664.8  300.49  4681.6  300.49
  4728.7  298.03  4767.7  297.54  4803.5  296.43  4909.5  294.52    4940   293.4
  4945.3  292.88  4963.1  292.49  4970.5  291.99  4972.8  291.19  4975.5  290.69
  4978.8  291.19  5010.9  291.48  5035.5  293.08  5063.5  293.53  5076.2  294.25
  5096.5  294.78    5116  295.91  5121.1  295.79    5127   296.4  5167.7  297.72
  5188.1  298.71  5208.4  298.58  5249.1  299.15  5278.8     300  5310.2  301.68
#Mann= 3 ,-1 , 0
  4584.7     .05       0  4972.8     .03       0  4978.8     .05       0
Bank Sta=4972.8,4978.8
XS Rating Curve= 0 ,0
Exp/Cntr=0.3,0.1

Type RM Length L Ch R = 1 ,3311    ,530,530,530
BEGIN DESCRIPTION:
UNT089 IN ROCK 7.0
END DESCRIPTION:
XS GIS Cut Line= 3
      3653188.65     10139979.87      3653524.14     10139952.03
      3653842.11     10139891.64
#Sta/Elev= 30
  4650.6  297.22  4689.4  295.58  4714.3  295.23  4764.5  293.05  4824.7  291.47
  4834.7  290.73  4864.8   289.8  4894.9  287.89    4925  287.34  4935.7  287.77
  4975.2  286.85  4987.3   286.4  4992.4  285.02  4995.1  284.52  4998.4  285.02
  5005.5  285.88  5025.9  285.72  5056.4  287.28  5076.8  287.55  5122.9  289.43
    5128  289.04  5137.9  289.38    5148  290.09  5158.2  291.53  5168.4  291.45
  5188.8  293.03  5227.4  293.39    5260  294.31  5284.8  295.24  5310.9  296.86
#Mann= 3 ,-1 , 0
  4650.6     .05       0  4992.4     .03       0  4998.4     .05       0
Bank Sta=4992.4,4998.4
XS Rating Curve= 0 ,0
Exp/Cntr=0.3,0.1

Type RM Length L Ch R = 1 ,2781    ,253,253,253
BEGIN DESCRIPTION:
UNT089 IN ROCK 6.0
END DESCRIPTION:
XS GIS Cut Line= 3
       3653217.8     10140433.62      3653533.76      10140433.3
      3653825.48     10140387.83
#Sta/Elev= 30
  4699.5  290.58  4704.1  290.58  4713.8   289.4  4723.8     289  4773.8  287.91
  4813.8  286.47  4883.8  282.92  4923.8  281.46  4943.8   279.7  4983.8   280.3
  4993.8  280.17  5000.8  279.64  5003.6  279.14  5006.8  279.64  5015.5  279.73
  5023.9  280.66    5034  281.18    5059  281.54  5064.4  282.01  5094.8  283.07
  5121.8  283.68  5135.2  284.47  5155.5  284.82  5184.7  287.05  5189.7  286.88
  5216.2  288.14  5236.4  288.54  5266.8  287.91  5276.9  288.36  5310.7  288.59
#Mann= 3 ,-1 , 0
  4699.5     .05       0  5000.8     .03       0  5006.8     .05       0
Bank Sta=5000.8,5006.8
XS Rating Curve= 0 ,0
Exp/Cntr=0.3,0.1

Type RM Length L Ch R = 1 ,2528    ,200,200,200
BEGIN DESCRIPTION:
Mapping XS 6c2b8f99
END DESCRIPTION:
XS GIS Cut Line= 3
       3653180.3     10140682.31      3653492.81     10140675.36
      3653716.79     10140704.88
#Sta/Elev= 30
  4657.6  284.48  4719.4  283.05  4759.4  281.23  4779.4   281.4  4789.4  281.26
  4819.4  280.26  4849.5  277.33  4869.5  276.94  4876.5  276.49  4879.2  275.99
  4882.5  276.49  4889.5  277.28  4908.5  277.28  4913.5  277.54  4929.5  277.73
  4939.5  277.55  4951.7  277.79  4982.3  277.94  4999.7  277.83  5019.9  278.11
    5030  277.75  5050.2  277.78  5080.4  280.35  5113.3   283.8  5129.4  285.56
  5140.9  286.12  5161.1  286.65  5171.2  287.34  5181.3  287.73  5196.1  287.97
#Mann= 5 ,-1 , 0
  4657.6     .05       0  4876.5     .07       0  4882.5     .05       0
  4951.7     .12       0  5113.3     .05       0
Bank Sta=4876.5,4882.5
XS Rating Curve= 0 ,0
Exp/Cntr=0.3,0.1

Type RM Length L Ch R = 1 ,2328    ,554,554,554
BEGIN DESCRIPTION:
UNT089 IN ROCK 5.0
END DESCRIPTION:
XS GIS Cut Line= 3
      3653117.86     10140854.06      3653442.11     10140841.64
      3653692.13     10140841.64
#Sta/Elev= 30
  4691.6   287.5  4705.9  287.27  4745.9  285.39  4795.9   283.8    4846  278.75
    4876  276.96  4883.2  276.19  4888.2  276.62    4896  275.58    4906  275.21
    4966  275.17  4986.1  274.51  4994.6  273.85  5018.6  274.59  5026.1  274.53
  5033.1  273.62  5035.8  273.12  5039.1  273.62  5046.1  274.38  5056.1  274.59
  5096.1  278.11  5136.1  280.76  5156.1  281.25  5166.1  282.04  5178.4   281.2
  5186.1  280.85  5196.1  282.03  5206.1  283.74  5216.1  284.59  5266.1  287.08
#Mann= 5 ,-1 , 0
  4691.6     .05       0  4994.6     .12       0  5033.1     .07       0
  5039.1     .12       0  5178.4     .05       0
Bank Sta=5033.1,5039.1
XS Rating Curve= 0 ,0
Exp/Cntr=0.3,0.1

Type RM Length L Ch R = 1 ,1774    ,393,393,393
BEGIN DESCRIPTION:
UNT089 IN ROCK 4.0
END DESCRIPTION:
XS GIS Cut Line= 3
      3653076.18     10141153.77      3653396.17     10141204.08
      3653696.21     10141154.08
#Sta/Elev= 30
    4769  287.67  4783.8  284.16  4788.8  285.76  4795.2  282.99  4805.4  280.79
  4815.5  280.14  4822.9   280.7  4835.7  282.15  4845.9  282.27  4851.4  281.82
  4856.5  280.46  4866.1   280.8  4876.2   280.6  4886.4  279.93  4957.2  270.73
  4967.3  269.71  4987.6  269.21  4997.5  268.16  5000.7  268.66  5017.9   269.2
  5038.2  269.16  5068.6  270.54  5092.9  271.51  5136.3  274.78  5190.2  276.24
  5233.5  277.86  5301.7  280.75  5362.5  285.04  5379.6  286.06  5397.1  286.51
#Mann= 5 ,-1 , 0
    4769     .05       0  4822.9      .1       0  4957.2     .05       0
  5068.6      .1       0  5233.5     .05       0
Bank Sta=4957.2,5068.6
XS Rating Curve= 0 ,0
Exp/Cntr=0.3,0.1

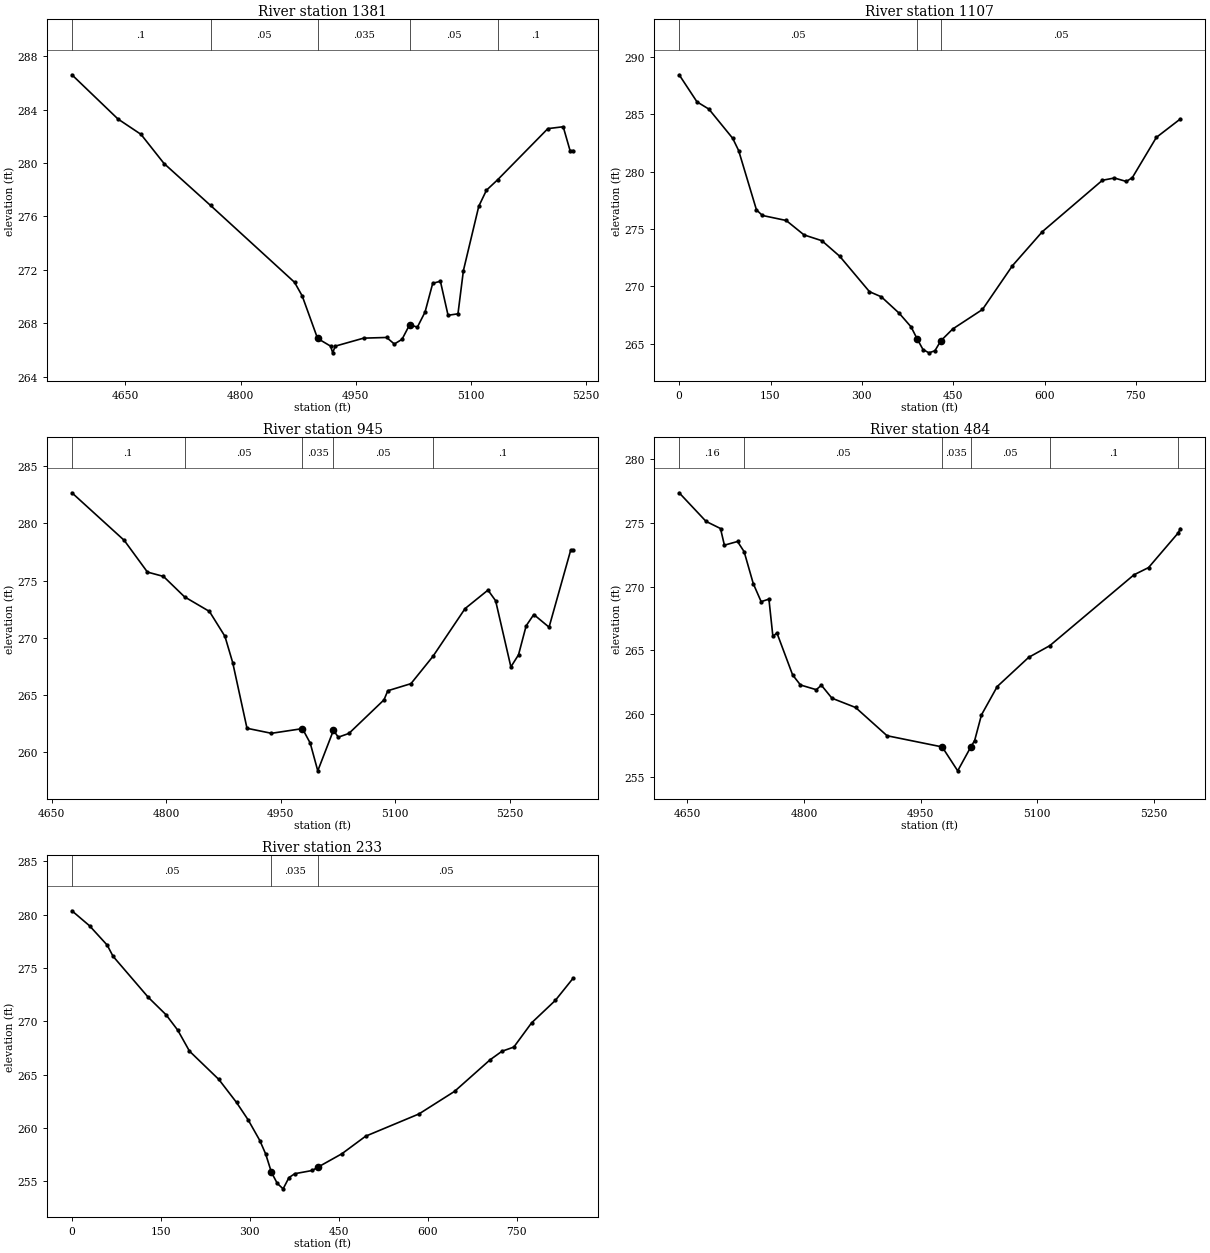
Type RM Length L Ch R = 1 ,1381    ,274,274,274
BEGIN DESCRIPTION:
UNT089 IN ROCK 3.0
END DESCRIPTION:
XS GIS Cut Line= 3
      3653022.15     10141540.91      3653525.06     10141538.21
      3653675.04     10141538.21
#Sta/Elev= 30
  4580.3   286.6  4640.3  283.29  4670.3  282.14  4700.3  279.96  4760.9  276.82
  4870.3  271.07  4880.3  270.05  4900.3  266.87  4917.3  266.29    4920  265.79
  4923.3  266.29  4960.3  266.89  4990.3  266.94  5000.3  266.45  5010.3   266.8
  5020.3   267.9  5030.3  267.71  5040.3  268.84  5050.3  270.99  5060.3  271.15
  5070.3   268.6  5083.2  268.71  5090.3  271.95  5110.3  276.76  5120.3  277.96
    5135  278.75  5200.3  282.57  5220.3  282.71  5229.2  280.93  5233.2  280.93
#Mann= 5 ,-1 , 0
  4580.3      .1       0  4760.9     .05       0  4900.3    .035       0
  5020.3     .05       0    5135      .1       0
Bank Sta=4900.3,5020.3
XS Rating Curve= 0 ,0
Exp/Cntr=0.3,0.1

Type RM Length L Ch R = 1 ,1107    ,162,162,162
XS GIS Cut Line= 4
     3652941.801    10141769.614     3653322.009    10141769.614
     3653448.311    10141772.218     3653763.416    10141803.468
#Sta/Elev= 30
       0 288.44229.29699286.081148.82832285.450987.89098282.906497.65665281.8408
126.9536276.6653136.7193 276.181 175.782275.7429 205.079274.4857234.3759273.9801
263.6729272.6232312.5013269.5391332.0326269.0894361.3296267.6587380.8609266.4686
 390.628265.4422 400.395264.4972410.1621264.2084419.9291 264.388429.6962 265.258
449.2303266.2887498.0656 267.987547.2276271.8007596.4713274.7737694.9588279.2472
714.6563279.4461734.3538279.1425744.2025279.4831783.5975282.9849822.9925284.5916
#Mann= 3 , 0 , 0
       0     .05       0 390.628    .035       0429.6962     .05       0
Bank Sta=390.628,429.6962
XS Rating Curve= 0 ,0
Exp/Cntr=0.3,0.1

Type RM Length L Ch R = 1 ,945     ,461,461,461
BEGIN DESCRIPTION:
UNT089 IN ROCK 2.0
END DESCRIPTION:
XS GIS Cut Line= 3
      3653034.61     10141986.32      3653533.64     10141900.01
      3653683.61     10141900.01
#Sta/Elev= 30
  4676.5  282.69    4745  278.52  4775.4  275.74  4796.4  275.36    4824  273.57
  4856.6  272.29  4876.9  270.11  4887.1   267.8  4905.8  262.05  4937.8  261.61
  4978.4  262.02  4988.6  260.75  4998.5  258.32    5019  261.87  5025.4  261.27
  5039.3   261.6  5085.2  264.54  5090.2  265.34  5120.5  265.96  5149.3  268.35
  5191.4  272.54  5221.4  274.16  5231.4  273.23  5251.4  267.43  5261.4  268.49
  5271.4  271.03  5281.4  272.02  5301.4  270.91  5329.7  277.65  5332.9  277.65
#Mann= 5 ,-1 , 0
  4676.5      .1       0    4824     .05       0  4978.4    .035       0
    5019     .05       0  5149.3      .1       0
Bank Sta=4978.4,5019
XS Rating Curve= 0 ,0
Exp/Cntr=0.3,0.1

Type RM Length L Ch R = 1 ,484     ,251,251,251
BEGIN DESCRIPTION:
UNT089 IN ROCK 1.0
END DESCRIPTION:
XS GIS Cut Line= 3
      3653067.88     10142177.81      3653550.34     10142254.13
      3653698.75     10142204.66
#Sta/Elev= 30
  4639.4  277.38    4674  275.13  4692.6  274.57  4697.6  273.26  4714.5  273.55
    4723  272.75  4734.8  270.23  4744.9  268.82  4754.9  269.02    4760  266.09
  4765.2  266.36  4785.4  263.06  4795.5  262.27  4815.8   261.9  4822.4  262.25
    4836  261.23  4866.4   260.5  4906.9  258.28  4977.8   257.4  4997.8  255.52
  5014.6  257.39  5019.6   257.9  5028.4  259.92  5048.7  262.15  5089.1  264.44
  5116.3  265.36  5224.6  270.93  5243.4   271.5  5281.6  274.23  5284.3  274.57
#Mann= 6 ,-1 , 0
  4639.4     .16       0    4723     .05       0  4977.8    .035       0
  5014.6     .05       0  5116.3      .1       0  5281.6     .05       0
Bank Sta=4977.8,5014.6
XS Rating Curve= 0 ,0
Exp/Cntr=0.3,0.1

Type RM Length L Ch R = 1 ,233     ,0,0,0
XS GIS Cut Line= 4
     3652983.142    10142253.881     3653215.347     10142405.79
     3653336.875    10142447.023     3653712.309    10142219.158
#Sta/Elev= 30
       0280.3526 29.7301278.9457 59.4602277.137969.37023276.0887128.8304272.2409
158.5605270.6224178.3806269.1737198.2007267.2049247.7508264.5512277.4809262.4014
 297.121260.7664316.7611258.8347326.5811257.5801336.4012255.8467346.2213254.8164
356.0413254.3101365.8614255.3616375.6814255.7283405.1415256.0283415.1356256.3544
455.1117257.5964495.0877259.2388585.0339261.3248644.9981263.4374704.9622266.3979
724.9503 267.196744.9384267.5881774.9204269.8568814.8965271.9581844.8785274.0334
#Mann= 3 , 0 , 0
       0     .05       0336.4012    .035       0415.1356     .05       0
Bank Sta=336.4012,415.1356
XS Rating Curve= 0 ,0
Exp/Cntr=0.3,0.1

Chan Stop Cuts=-1
Use User Specified Reach Order=0
Composite Channel Slope=5