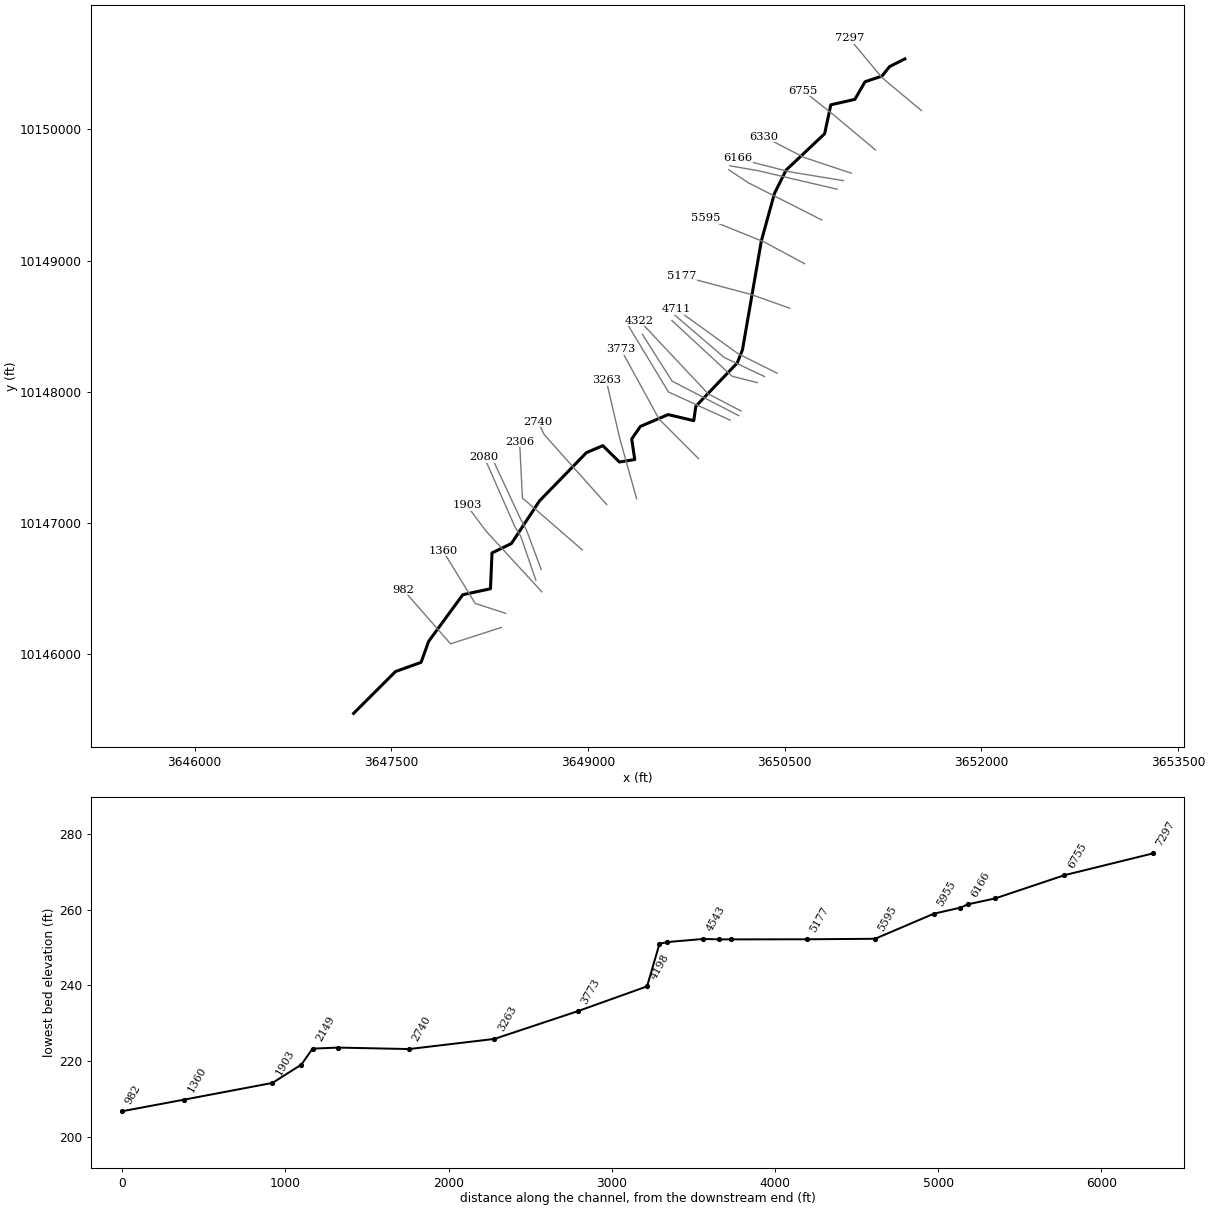
--- UNT090 IN ROCK.prj (project) ---

Proj Title=UNT090 IN ROCK Base Level Engineering
Current Plan=p01
Default Exp/Contr=0.3,0.1
English Units
Geom File=g01
Flow File=f01
Plan File=p01
Y Axis Title=Elevation
X Axis Title(PF)=Main Channel Distance
X Axis Title(XS)=Station
BEGIN DESCRIPTION:
UNT090 IN ROCK
END DESCRIPTION:
DSS Export Rating Curves= 0
DSS Export Rating Curve Sorted= 0
DSS Export Volume Flow Curves= 0
DXF OffsetX= 0
DXF OffsetY= 0
DXF ScaleX= 1
DXF ScaleY= 10

--- UNT090 IN ROCK.p01 (plan) ---

Plan Title=Multiple Run
Short Identifier=Multiple
Geom File=g01
Flow File=f01
Subcritical Flow
K Sum by GR= 0
Std Step Tol= 0.01
Critical Tol= 0.01
Num of Std Step Trials= 20
Max Error Tol= 0.3
Flow Tol Ratio= 0.001
Split Flow NTrial= 30
Split Flow Tol= 0.02
Split Flow Ratio= 0.02
Log Output Level= 0
Friction Slope Method= 1
Unsteady Friction Slope Method= 2
Unsteady Bridges Friction Slope Method= 1
Parabolic Critical Depth
Global Vel Dist=  1 , 1 , 1
Global Log Level= 0
CheckData=True
Encroach Param= -1, 0, 0, 0
BEGIN DESCRIPTION:
Multiple Run
END DESCRIPTION:

--- UNT090 IN ROCK.f01 (steady flow) ---

Flow Title=Multiple
Number of Profiles=7
Profile Names=10-year,25-year,50-year,1pct_min,100-year,1pct_plu,500-year
River Rch & RM= UNT090 IN ROCK,Reach-1,7297
     394     518     617     540     731     988    1026
Boundary for River Rch & Prof#=UNT090 IN ROCK,Reach-1,1
Up Type=0
Dn Type=3
Dn Slope=0.005
Boundary for River Rch & Prof#=UNT090 IN ROCK,Reach-1,2
Up Type=0
Dn Type=3
Dn Slope=0.005
Boundary for River Rch & Prof#=UNT090 IN ROCK,Reach-1,3
Up Type=0
Dn Type=3
Dn Slope=0.005
Boundary for River Rch & Prof#=UNT090 IN ROCK,Reach-1,4
Up Type=0
Dn Type=3
Dn Slope=0.005
Boundary for River Rch & Prof#=UNT090 IN ROCK,Reach-1,5
Up Type=0
Dn Type=3
Dn Slope=0.005
Boundary for River Rch & Prof#=UNT090 IN ROCK,Reach-1,6
Up Type=0
Dn Type=3
Dn Slope=0.005
Boundary for River Rch & Prof#=UNT090 IN ROCK,Reach-1,7
Up Type=0
Dn Type=3
Dn Slope=0.005

--- UNT090 IN ROCK.g01 (geometry) ---

Geom Title=Existing Conditions
Program Version=4.10

River Reach=UNT090 IN ROCK  ,Reach-1
Reach XY= 30
      3651415.55     10150534.77      3651299.31     10150476.74
      3651241.02     10150404.18      3651112.13       10150361.
      3651034.77     10150226.96      3650851.19     10150185.41
      3650803.92     10149964.96      3650509.76     10149687.87
      3650421.22     10149509.92       3650321.4     10149148.81
      3650177.73     10148320.69       3650137.8     10148219.99
      3649821.83     10147890.13      3649806.21     10147780.75
      3649610.89     10147826.76       3649399.3     10147736.71
      3649333.04     10147641.05       3649356.1     10147484.63
      3649239.23     10147465.69      3649112.83     10147590.14
      3648988.24     10147537.34      3648629.99     10147169.64
      3648415.78      10146845.2      3648267.62      10146773.3
      3648255.94     10146500.57      3648045.21     10146455.22
      3647784.71     10146100.53      3647726.88     10145940.19
      3647531.98     10145870.38      3647212.11     10145551.64

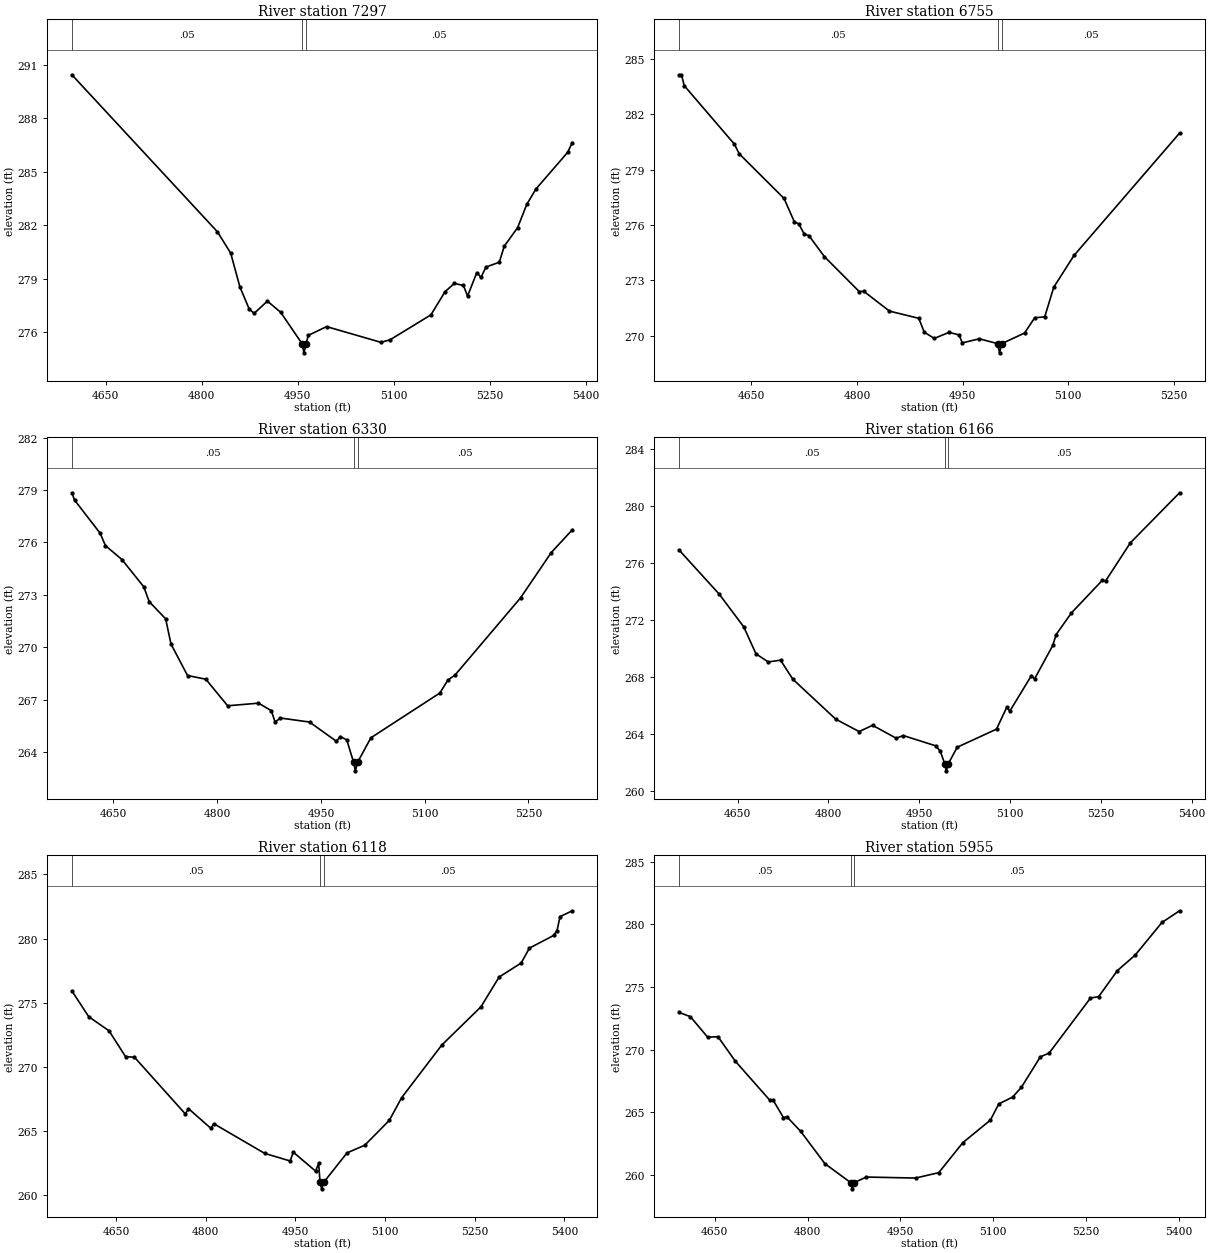
Type RM Length L Ch R = 1 ,7297    ,542,542,542
BEGIN DESCRIPTION:
UNT090 IN ROCK 15.0
END DESCRIPTION:
XS GIS Cut Line= 3
      3651542.08     10150141.66      3651242.11     10150391.64
       3650992.1     10150691.65
#Sta/Elev= 30
  4597.5  290.43  4824.6  281.63  4845.4  280.43  4859.8  278.53  4874.1  277.31
  4881.9  277.05  4902.7  277.74  4923.5  277.11    4957  275.34  4959.7  274.84
    4963  275.34  4966.5  275.82  4995.1  276.31  5079.8  275.43  5094.1  275.57
  5157.9  276.97    5180  278.27  5194.3  278.73  5208.6  278.62  5215.1  278.02
  5229.5  279.34    5236  279.07  5243.8  279.65  5264.6  279.92  5272.4  280.82
  5293.2  281.86  5307.6  283.17  5321.9  284.03  5371.3  286.08  5378.5  286.63
#Mann= 3 ,-1 , 0
  4597.5     .05       0    4957     .03       0    4963     .05       0
Bank Sta=4957,4963
XS Rating Curve= 0 ,0
Exp/Cntr=0.3,0.1

Type RM Length L Ch R = 1 ,6755    ,425,425,425
BEGIN DESCRIPTION:
UNT090 IN ROCK 14.0
END DESCRIPTION:
XS GIS Cut Line= 3
      3651192.14     10149841.61      3650880.23     10150102.46
      3650642.13     10150291.62
#Sta/Elev= 30
  4547.5  284.14  4550.8  284.14  4554.7  283.55  4625.8  280.39  4632.8  279.86
  4696.5  277.44  4710.9  276.19  4717.4  276.06  4725.2  275.51  4731.7  275.43
  4753.8  274.29  4803.2   272.4  4809.8  272.41  4846.2  271.34  4887.8  270.95
  4895.6   270.2  4909.9  269.86  4930.8  270.19  4945.1  270.05  4949.6  269.62
  4973.9  269.84  4999.7  269.58  5002.5  269.08  5005.7  269.58    5038  270.15
  5052.4  270.98  5066.7  271.03  5079.6  272.64  5108.4  274.36  5258.2  280.98
#Mann= 3 ,-1 , 0
  4547.5     .05       0  4999.7     .03       0  5005.7     .05       0
Bank Sta=4999.7,5005.7
XS Rating Curve= 0 ,0
Exp/Cntr=0.3,0.1

Type RM Length L Ch R = 1 ,6330    ,164,164,164
BEGIN DESCRIPTION:
UNT090 IN ROCK 13.0
END DESCRIPTION:
XS GIS Cut Line= 3
      3651008.07     10149664.48      3650647.59     10149784.75
      3650342.13     10149941.63
#Sta/Elev= 30
  4589.9  278.84  4593.8  278.42  4630.7  276.53  4638.4  275.82  4662.3  275.02
  4693.9  273.46  4701.6  272.62  4725.5  271.63  4733.2  270.19  4757.1  268.39
  4783.5  268.18  4815.1  266.66  4859.7  266.81  4878.3  266.38  4883.6  265.73
  4891.4  265.96  4933.5  265.73  4972.3  264.63  4977.9   264.9  4987.3  264.71
  4997.1  263.44  4999.8  262.94  5003.1  263.44  5022.2  264.83  5121.9  267.39
  5133.5  268.13  5144.1  268.43  5238.5  272.83  5282.9  275.42  5313.3  276.72
#Mann= 3 ,-1 , 0
  4589.9     .05       0  4997.1     .03       0  5003.1     .05       0
Bank Sta=4997.1,5003.1
XS Rating Curve= 0 ,0
Exp/Cntr=0.3,0.1

Type RM Length L Ch R = 1 ,6166    ,48,48,48
BEGIN DESCRIPTION:
Mapping XS 87a4350a
END DESCRIPTION:
XS GIS Cut Line= 3
      3650947.32     10149608.05      3650537.19     10149675.32
      3650139.18     10149776.98
#Sta/Elev= 30
  4553.6  276.92  4619.7  273.83  4660.2  271.53  4680.5  269.63  4700.8  269.06
    4721  269.19  4741.3  267.85  4812.2  265.04  4850.8  264.17    4873  264.61
  4912.1   263.7  4923.7  263.89  4977.1  263.17  4984.8   262.8  4992.1  261.91
  4994.8  261.41  4998.1  261.91  5012.8  263.07  5077.7  264.34  5094.5  265.87
  5099.6   265.6  5135.3   268.1  5140.5  267.87  5170.6  270.22  5176.2  270.99
  5201.5  272.51  5252.7  274.81  5257.8  274.75  5298.7  277.43    5380  280.95
#Mann= 3 ,-1 , 0
  4553.6     .05       0  4992.1     .04       0  4998.1     .05       0
Bank Sta=4992.1,4998.1
XS Rating Curve= 0 ,0
Exp/Cntr=0.3,0.1

Type RM Length L Ch R = 1 ,6118    ,163,163,163
BEGIN DESCRIPTION:
Mapping XS 29142396
END DESCRIPTION:
XS GIS Cut Line= 4
      3650899.56     10149542.95      3650517.66     10149631.91
      3650296.31       10149684.      3650081.47     10149720.89
#Sta/Elev= 30
  4575.8  275.93    4604  273.92    4638  272.82  4665.6  270.81  4680.6  270.76
  4765.8  266.34  4770.9  266.76  4808.3  265.23  4813.5  265.58  4898.6  263.27
  4941.2  262.68  4946.3  263.37  4983.7  261.89  4988.8  262.49  4991.2  261.01
  4993.9  260.51  4997.2  261.01  5036.3  263.31  5066.1  263.91  5107.2  265.85
  5127.7  267.61  5194.9  271.71  5260.5  274.69  5290.9  277.01  5327.8   278.1
  5341.6  279.26  5382.2  280.25  5387.8  280.62  5392.8  281.71  5413.3  282.17
#Mann= 3 ,-1 , 0
  4575.8     .05       0  4991.2     .04       0  4997.2     .05       0
Bank Sta=4991.2,4997.2
XS Rating Curve= 0 ,0
Exp/Cntr=0.3,0.1

Type RM Length L Ch R = 1 ,5955    ,360,360,360
BEGIN DESCRIPTION:
UNT090 IN ROCK 12.0
END DESCRIPTION:
XS GIS Cut Line= 3
      3650783.08     10149308.39      3650222.35     10149591.64
      3650072.34     10149691.65
#Sta/Elev= 30
  4592.6  272.97  4610.7  272.64  4638.6     271  4655.3  271.04  4683.3  269.09
  4738.8  265.99  4744.5  265.97  4761.1  264.59  4766.7  264.65    4789  263.49
    4828  260.92  4869.6  259.41  4872.4  258.91  4875.6  259.41  4894.9  259.85
  4974.6  259.77    5012   260.2  5050.9  262.59  5095.5  264.39    5109  265.68
  5131.5  266.23  5145.7  267.02  5176.3  269.44  5190.3  269.73  5257.2  274.12
  5270.5  274.24  5300.6  276.31  5329.3  277.54  5372.7  280.15  5401.1  281.08
#Mann= 3 ,-1 , 0
  4592.6     .05       0  4869.6     .03       0  4875.6     .05       0
Bank Sta=4869.6,4875.6
XS Rating Curve= 0 ,0
Exp/Cntr=0.3,0.1

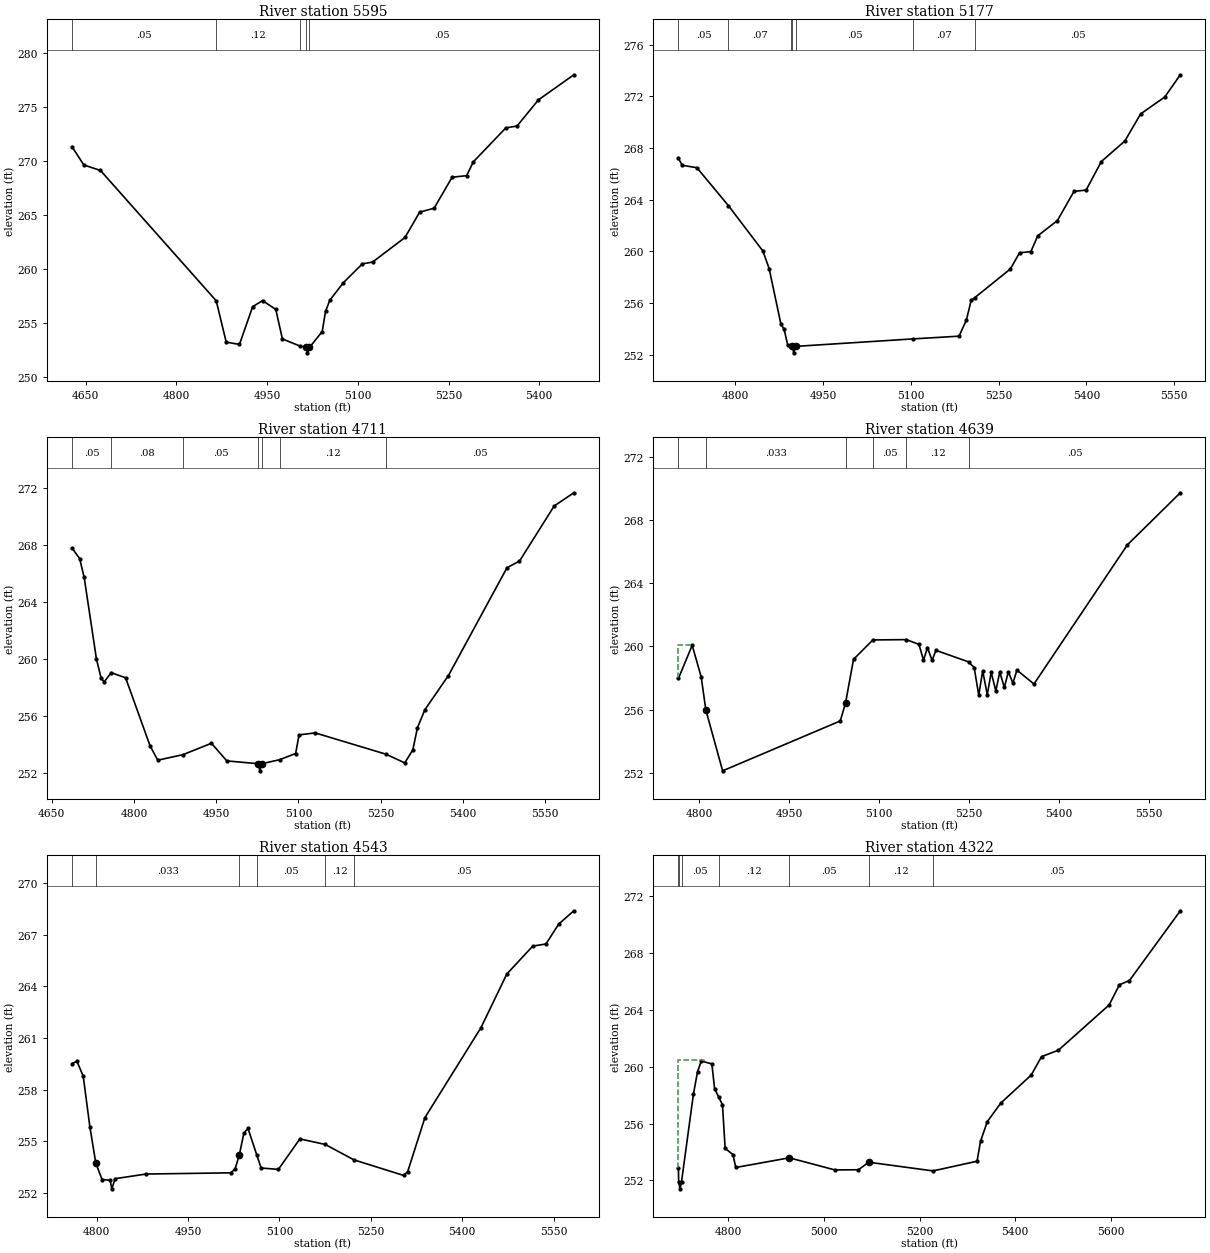
Type RM Length L Ch R = 1 ,5595    ,418,418,418
BEGIN DESCRIPTION:
UNT090 IN ROCK 11.0
END DESCRIPTION:
XS GIS Cut Line= 3
      3650651.21     10148975.62      3650342.11     10149141.64
      3649897.79     10149320.94
#Sta/Elev= 30
  4627.2  271.34  4646.9  269.65  4674.4  269.14  4865.8  257.09  4882.3  253.27
  4904.2  253.06  4926.1  256.55  4942.4  257.11  4964.3  256.29  4975.2  253.57
  5004.1  252.91    5014  252.78  5016.7  252.28    5020  252.78  5041.1  254.25
  5046.5  256.11  5053.6  257.14  5076.1  258.77  5107.5  260.51  5124.3  260.67
    5178  262.95  5202.2  265.29  5226.1  265.65  5255.9  268.52    5280  268.66
  5290.8  269.93  5344.7  273.08  5363.2  273.25  5398.6  275.67  5457.2  277.99
#Mann= 5 ,-1 , 0
  4627.2     .05       0  4865.8     .12       0  5004.1     .05       0
    5014     .07       0    5020     .05       0
Bank Sta=5014,5020
XS Rating Curve= 0 ,0
Exp/Cntr=0.3,0.1

Type RM Length L Ch R = 1 ,5177    ,466,466,466
BEGIN DESCRIPTION:
UNT090 IN ROCK 10.0
END DESCRIPTION:
XS GIS Cut Line= 3
      3650538.22     10148636.55      3650242.11     10148741.64
      3649716.44     10148881.23
#Sta/Elev= 30
  4702.5   267.2    4709  266.66  4734.1  266.47  4788.1  263.53  4846.9  260.03
  4857.6  258.67  4877.8  254.36  4883.1  253.98  4889.4  252.76  4894.3  252.69
    4897  252.65  4899.7  252.15    4903  252.65  5104.1  253.23  5182.3  253.44
  5194.9  254.69    5203  256.21  5209.2  256.42  5270.1  258.64  5285.7  259.89
  5305.1  259.98  5316.8   261.2  5350.4  262.38  5378.8  264.64  5399.5  264.74
  5425.6  266.95  5465.8  268.54  5492.7  270.63    5534  271.94  5560.6  273.66
#Mann= 7 ,-1 , 0
  4702.5     .05       0  4788.1     .07       0  4894.3     .05       0
    4897    .033       0    4903     .05       0  5104.1     .07       0
  5209.2     .05       0
Bank Sta=4897,4903
XS Rating Curve= 0 ,0
Exp/Cntr=0.3,0.1

Type RM Length L Ch R = 1 ,4711    ,72,72,72
BEGIN DESCRIPTION:
UNT090 IN ROCK 9.0
END DESCRIPTION:
XS GIS Cut Line= 3
      3650442.09     10148141.65      3650142.11     10148291.64
      3649671.72     10148630.28
#Sta/Elev= 30
  4687.1  267.81  4701.1  267.06  4709.4  265.73  4731.8  259.98  4740.2  258.66
  4745.8  258.38  4758.7  259.03  4784.9  258.67  4829.6  253.87  4843.6  252.87
  4889.6  253.26  4941.4  254.06  4969.4  252.82  5026.9  252.62  5029.6  252.12
  5032.9  252.62  5065.5   252.9  5094.9  253.34  5101.1  254.65  5130.5  254.79
  5259.7  253.29  5293.8  252.68  5308.5  253.59    5317  255.16  5330.5  256.42
  5373.5  258.83  5480.3  266.42    5503  266.88  5566.2  270.76  5602.1  271.69
#Mann= 7 ,-1 , 0
  4687.1     .05       0  4758.7     .08       0  4889.6     .05       0
  5026.9    .033       0  5032.9     .05       0  5065.5     .12       0
  5259.7     .05       0
Bank Sta=5026.9,5032.9
XS Rating Curve= 0 ,0
Exp/Cntr=0.3,0.1

Type RM Length L Ch R = 1 ,4639    ,96,96,96
BEGIN DESCRIPTION:
Mapping XS e690968f
END DESCRIPTION:
XS GIS Cut Line= 3
      3650346.43     10148116.14       3650038.3     10148261.52
      3649660.73     10148584.85
#Sta/Elev= 30
  4765.3  257.97  4788.3  260.07  4803.3  258.07  4811.1  255.97  4839.1  252.12
  5035.5  255.28  5044.3  256.42  5057.6  259.18  5089.9  260.41  5145.7  260.43
  5166.8  260.13  5174.4  259.13    5181  259.92  5188.7  259.12  5195.2  259.75
  5249.7  259.02    5259  258.66  5266.6  256.91  5273.2  258.45  5280.9  256.94
  5287.4  258.36  5295.1  257.18  5301.7  258.37  5309.4   257.4    5316  258.39
  5323.7  257.67  5330.3   258.5  5358.8  257.62  5514.7  266.43  5603.1  269.73
#Mann= 6 ,-1 , 0
  4765.3     .08       0  4811.1    .033       0  5044.3     .08       0
  5089.9     .05       0  5145.7     .12       0  5249.7     .05       0
#XS Ineff= 2 , 0
          4787.5  260.09
Permanent Ineff=
       F       F
Bank Sta=4811.1,5044.3
XS Rating Curve= 0 ,0
Exp/Cntr=0.3,0.1

Type RM Length L Ch R = 1 ,4543    ,221,221,221
BEGIN DESCRIPTION:
Mapping XS e1c9f64f
END DESCRIPTION:
XS GIS Cut Line= 3
      3650290.04     10148070.55      3650099.07      10148118.3
      3649639.01     10148543.63
#Sta/Elev= 30
  4759.6  259.51  4767.8  259.65  4778.1  258.78  4789.1  255.82  4798.7  253.74
    4809  252.78  4822.2  252.74    4825  252.24  4830.4  252.83  4881.2   253.1
  5020.4  253.17  5027.4  253.41  5034.2  254.21  5041.6  255.47  5048.4  255.75
  5062.6  254.23    5070  253.45  5098.3  253.37  5133.5  255.14    5175  254.82
  5222.4  253.92  5303.6  253.02  5310.4  253.24  5338.7  256.38  5430.6   261.6
  5473.1  264.72  5515.6  266.34  5537.2  266.46  5558.2  267.62    5583  268.39
#Mann= 6 ,-1 , 0
  4759.6     .08       0  4798.7    .033       0  5034.2     .08       0
  5062.6     .05       0    5175     .12       0  5222.4     .05       0
Bank Sta=4798.7,5034.2
XS Rating Curve= 0 ,0
Exp/Cntr=0.3,0.1

Type RM Length L Ch R = 1 ,4322    ,48,48,48
BEGIN DESCRIPTION:
UNT090 IN ROCK 8.0
END DESCRIPTION:
XS GIS Cut Line= 3
      3650167.55     10147853.61      3649917.01     10147983.87
      3649392.11     10148541.64
#Sta/Elev= 30
  4696.4  252.89  4696.9  251.91  4699.7  251.41  4702.9  251.91  4727.7  258.05
  4736.3  259.64  4744.2  260.39  4766.3  260.19  4771.9  258.46  4780.5  257.86
  4788.4  257.32    4794  254.25  4810.5  253.81  4816.1  252.91    4928  253.59
  5023.1  252.74  5072.4  252.75  5093.9  253.28  5228.2  252.67  5320.1  253.35
  5327.4  254.75  5341.5  256.13  5369.8  257.44  5433.4  259.41  5454.8   260.7
    5490  261.15    5596  264.33  5617.5  265.75  5638.5  266.05  5744.7  270.95
#Mann= 7 ,-1 , 0
  4696.4     .05       0  4696.9     .07       0  4702.9     .05       0
  4780.5     .12       0    4928     .05       0  5093.9     .12       0
  5228.2     .05       0
#XS Ineff= 2 , 0
         4750.68  260.48
Permanent Ineff=
       F       F
Bank Sta=4928,5093.9
XS Rating Curve= 0 ,0
Exp/Cntr=0.3,0.1

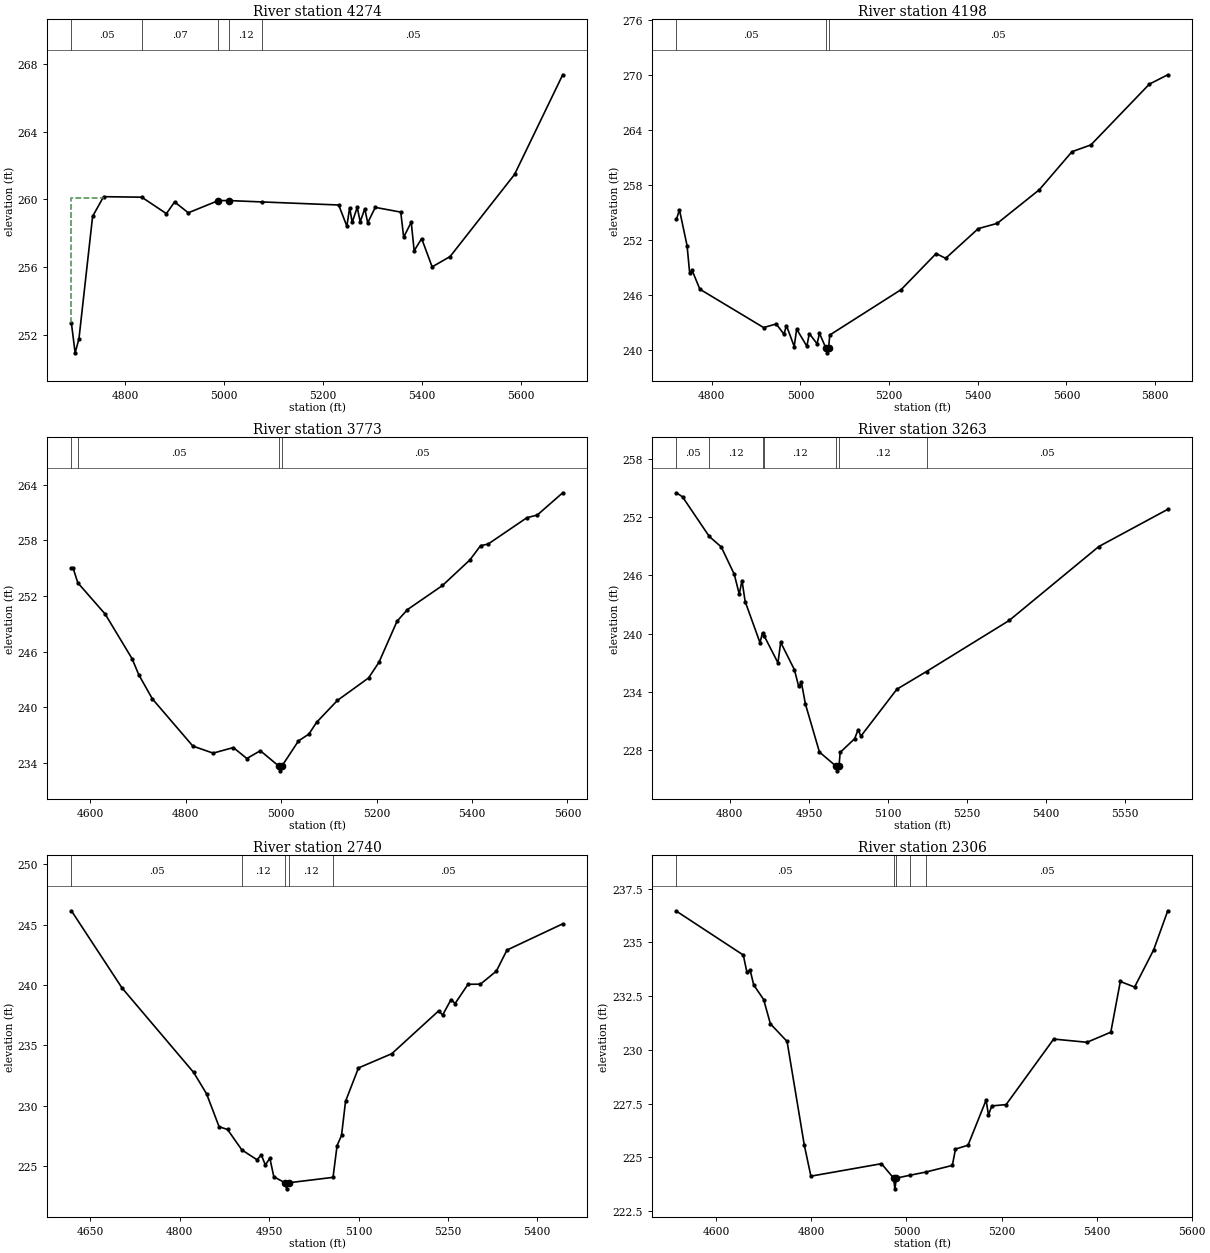
Type RM Length L Ch R = 1 ,4274    ,76,76,76
BEGIN DESCRIPTION:
Mapping XS 4963f780
END DESCRIPTION:
XS GIS Cut Line= 3
      3650148.95     10147818.83      3649641.17      10148081.4
      3649414.21     10148438.05
#Sta/Elev= 30
  4690.6   252.7  4698.1  250.95  4705.8  251.77  4733.5     259  4755.7  260.16
    4833  260.13  4882.9  259.16  4899.4  259.85  4927.2  259.21    4988  259.93
  5010.2  259.93  5076.6  259.85  5231.6  259.67  5248.1  258.42  5253.7  259.51
  5258.9  258.65  5269.1  259.53  5275.1  258.68  5284.4  259.45  5290.3  258.62
  5305.6  259.53  5357.2  259.25  5363.1  257.77  5378.4  258.66  5384.3  256.97
  5399.5  257.69  5420.7  256.02  5457.1  256.63  5587.5  261.47    5685  267.35
#Mann= 5 ,-1 , 0
  4690.6     .05       0    4833     .07       0    4988     .05       0
  5010.2     .12       0  5076.6     .05       0
#XS Ineff= 2 , 0
         4756.82  260.09
Permanent Ineff=
       F       F
Bank Sta=4988,5010.2
XS Rating Curve= 0 ,0
Exp/Cntr=0.3,0.1

Type RM Length L Ch R = 1 ,4198    ,425,425,425
BEGIN DESCRIPTION:
Mapping XS 109a07bd
END DESCRIPTION:
XS GIS Cut Line= 3
      3650083.86      10147784.1      3649612.95     10147998.94
      3649307.02     10148504.49
#Sta/Elev= 30
  4720.2  254.28    4727  255.29  4744.1   251.4    4750  248.41  4755.5   248.7
    4773  246.64  4916.8  242.46  4945.3  242.85  4962.8  241.73  4968.3  242.68
  4985.9  240.39  4991.4  242.29  5014.4  240.42  5019.9   241.8  5037.5  240.69
  5042.9  241.83  5057.5   240.2  5060.2   239.7  5063.5   240.2    5066  241.64
  5227.2   246.6  5306.1  250.53  5327.5  250.01  5401.2  253.25  5443.9  253.82
  5538.9  257.49  5612.6  261.64  5655.3  262.38  5787.2  269.01  5828.7  270.03
#Mann= 3 ,-1 , 0
  4720.2     .05       0  5057.5     .03       0  5063.5     .05       0
Bank Sta=5057.5,5063.5
XS Rating Curve= 0 ,0
Exp/Cntr=0.3,0.1

Type RM Length L Ch R = 1 ,3773    ,510,510,510
BEGIN DESCRIPTION:
UNT090 IN ROCK 7.0
END DESCRIPTION:
XS GIS Cut Line= 3
      3649842.07     10147491.67      3649542.11     10147791.64
      3649251.06     10148322.58
#Sta/Elev= 30
  4560.4  255.01  4563.9  255.01  4573.8  253.42  4631.1  250.05  4687.6  245.23
  4701.8  243.48  4730.1   240.9  4814.9  235.81  4857.3  235.05  4899.8  235.65
  4928.1  234.47  4956.3  235.31  4995.4  233.64  4998.1  233.14  5001.4  233.64
  5036.3  236.37  5058.1   237.1  5074.2  238.37  5117.8  240.73  5183.2  243.16
    5205  244.85  5242.9  249.28  5264.7  250.53  5338.1  253.13  5395.6  255.89
    5418  257.43  5433.5  257.59    5515  260.44  5536.8  260.73  5590.1  263.13
#Mann= 4 ,-1 , 0
  4560.4     .08       0  4573.8     .05       0  4995.4     .03       0
  5001.4     .05       0
Bank Sta=4995.4,5001.4
XS Rating Curve= 0 ,0
Exp/Cntr=0.3,0.1

Type RM Length L Ch R = 1 ,3263    ,523,523,523
BEGIN DESCRIPTION:
UNT090 IN ROCK 6.0
END DESCRIPTION:
XS GIS Cut Line= 3
      3649370.34     10147186.12      3649242.11      10147644.5
      3649138.44     10148088.48
#Sta/Elev= 30
  4698.8  254.54  4710.3  254.12    4761  250.03  4783.7  248.95  4808.4  246.13
  4817.9  244.07  4823.1  245.47  4829.1  243.31  4857.2  239.06    4862  240.06
  4865.1  239.77  4891.3  236.98  4896.5  239.09  4922.6  236.26  4930.6  234.54
  4935.8  234.95  4943.4  232.72    4970  227.76  5001.1  226.32  5003.9  225.82
  5007.1  226.32  5009.3  227.72  5036.8  229.14  5043.4  230.08  5048.6   229.4
  5116.9  234.25  5173.1  236.08  5329.9  241.35    5500  248.99  5630.7  252.83
#Mann= 7 ,-1 , 0
  4698.8     .05       0    4761     .12       0    4862     .05       0
  4865.1     .12       0  5001.1     .07       0  5007.1     .12       0
  5173.1     .05       0
Bank Sta=5001.1,5007.1
XS Rating Curve= 0 ,0
Exp/Cntr=0.3,0.1

Type RM Length L Ch R = 1 ,2740    ,434,434,434
BEGIN DESCRIPTION:
UNT090 IN ROCK 5.0
END DESCRIPTION:
XS GIS Cut Line= 3
      3649142.11     10147141.64      3648666.07     10147673.96
      3648616.58     10147772.94
#Sta/Elev= 30
    4618  246.14  4702.9  239.76  4823.2  232.77  4844.9     231  4865.9  228.28
  4880.1  228.05  4904.1  226.36  4929.4  225.55  4936.9  225.93  4943.6  225.11
  4951.1  225.68  4957.8  224.14  4976.5  223.64  4979.3  223.14  4982.5  223.64
  5057.2  224.09    5064  226.72  5071.5  227.56  5078.2  230.38  5099.9  233.14
  5155.9  234.32  5234.5  237.86  5241.2  237.52  5255.4   238.8  5262.1  238.47
  5283.8  240.06  5304.7  240.07  5331.4  241.15  5349.2  242.89  5442.8  245.06
#Mann= 5 ,-1 , 0
    4618     .05       0  4904.1     .12       0  4976.5     .07       0
  4982.5     .12       0  5057.2     .05       0
Bank Sta=4976.5,4982.5
XS Rating Curve= 0 ,0
Exp/Cntr=0.3,0.1

Type RM Length L Ch R = 1 ,2306    ,157,157,157
BEGIN DESCRIPTION:
UNT090 IN ROCK 4.0
END DESCRIPTION:
XS GIS Cut Line= 3
      3648955.96     10146796.83      3648499.67     10147191.65
      3648477.97      10147621.3
#Sta/Elev= 30
  4516.1  236.45  4656.7  234.41  4664.3  233.61    4671  233.72  4678.6  233.02
  4699.5  232.34  4713.7  231.21  4748.8  230.39    4785  225.57  4798.9  224.12
  4947.4   224.7  4972.9  224.03  4975.6  223.53  4978.9  224.03  5006.6  224.16
  5040.5  224.31  5096.5  224.62  5103.1  225.38  5129.5  225.56  5167.5  227.66
  5172.5  226.97  5179.6  227.39  5209.6  227.45  5309.7   230.5  5379.8  230.35
  5429.9  230.82  5449.9  233.18  5479.9  232.92    5520  234.65  5549.7  236.47
#Mann= 5 ,-1 , 0
  4516.1     .05       0  4972.9    .033       0  4978.9     .05       0
  5006.6     .12       0  5040.5     .05       0
Bank Sta=4972.9,4978.9
XS Rating Curve= 0 ,0
Exp/Cntr=0.3,0.1

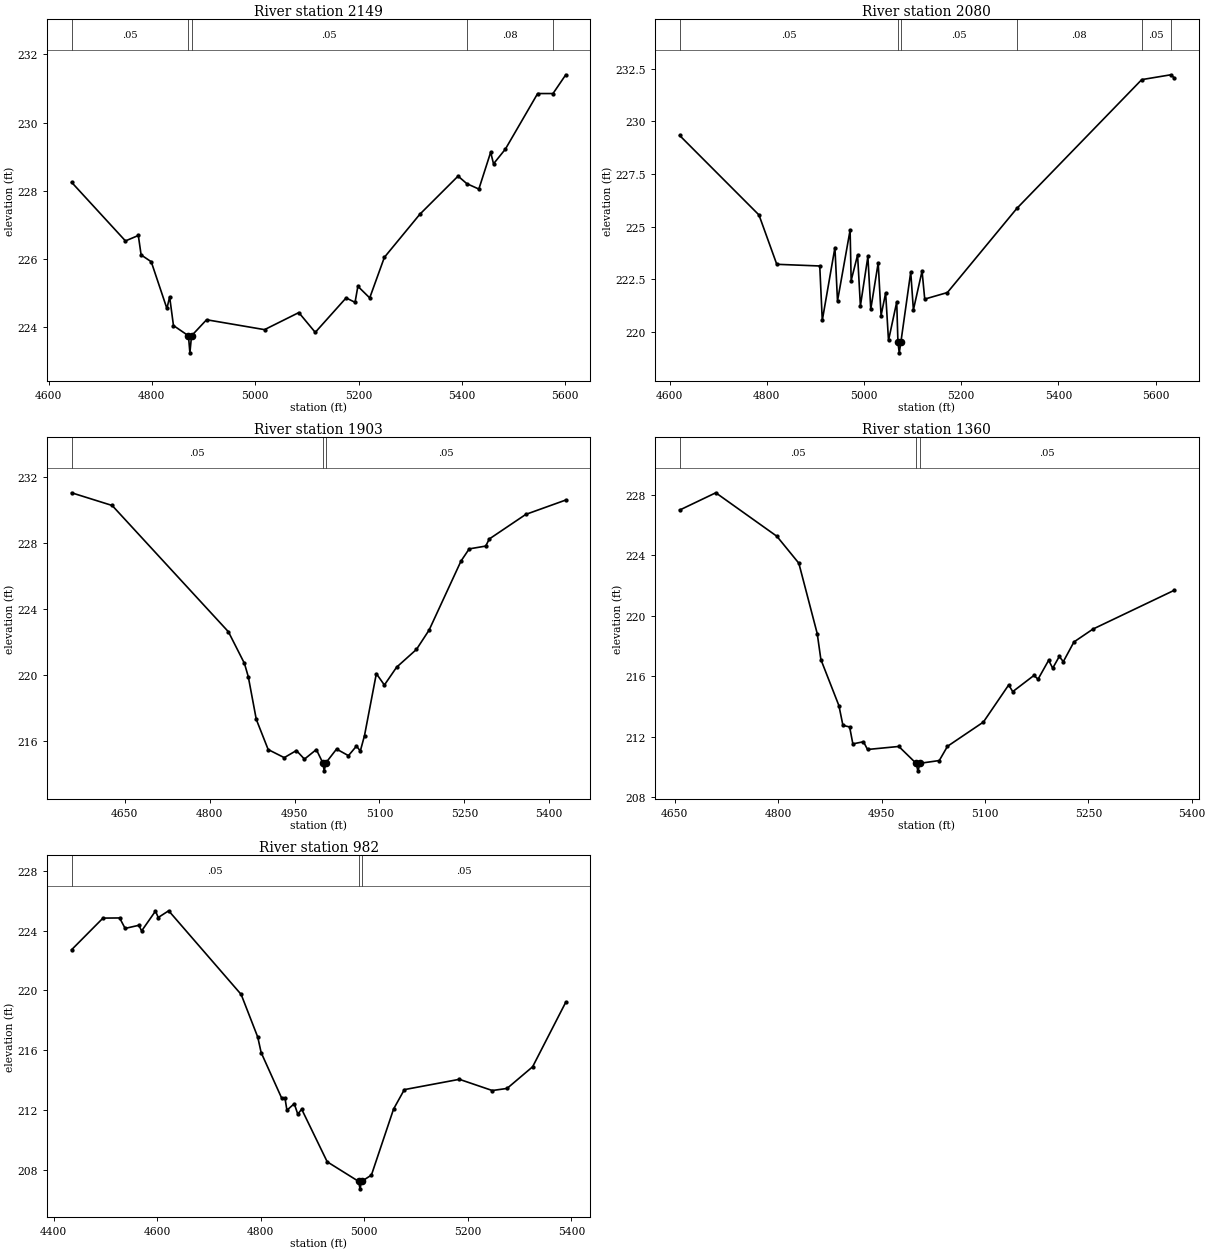
Type RM Length L Ch R = 1 ,2149    ,69,69,69
BEGIN DESCRIPTION:
Mapping XS cdc76607
END DESCRIPTION:
XS GIS Cut Line= 4
       3648642.9     10146646.95      3648530.06     10146948.59
      3648484.48     10147033.23      3648256.88     10147520.95
#Sta/Elev= 30
  4644.6  228.25  4748.9  226.53  4773.8  226.69  4779.2  226.12  4798.8  225.92
  4829.1  224.55  4834.4  224.89  4841.8  224.05  4870.8  223.75  4873.6  223.25
  4876.8  223.75  4905.9  224.22  5018.1  223.93  5084.4  224.43  5116.2  223.85
  5175.9  224.86  5193.2  224.73  5198.7   225.2  5221.6  224.86    5250  226.05
  5318.5  227.31  5392.6  228.43  5409.4  228.21  5432.8  228.05  5455.7  229.13
  5461.2  228.79  5484.1  229.22  5546.6  230.85  5576.3  230.85    5601   231.4
#Mann= 5 ,-1 , 0
  4644.6     .05       0  4870.8     .03       0  4876.8     .05       0
  5409.4     .08       0  5576.3     .05       0
Bank Sta=4870.8,4876.8
XS Rating Curve= 0 ,0
Exp/Cntr=0.3,0.1

Type RM Length L Ch R = 1 ,2080    ,177,177,177
BEGIN DESCRIPTION:
Mapping XS b5f1d7fc
END DESCRIPTION:
XS GIS Cut Line= 4
      3648601.67     10146566.66      3648486.65     10146900.85
      3648443.25     10146970.29      3648208.86       10147502.
#Sta/Elev= 30
  4620.9  229.33    4784  225.56  4820.6  223.22    4909  223.14  4914.2  220.56
  4940.2  224.01  4945.5  221.48  4971.4  224.84  4973.6  222.45  4986.8  223.66
  4992.6  221.25    5008  223.59  5013.9  221.09  5029.2  223.29  5035.1  220.79
  5044.5  221.86  5050.4  219.61  5067.3  221.43  5069.8  219.52  5072.5  219.02
  5075.8  219.52  5096.1  222.85  5101.6  221.06  5119.4   222.9  5124.9  221.57
  5171.5  221.88  5314.3  225.87  5571.2  231.98  5631.1  232.21  5637.3  232.08
#Mann= 6 ,-1 , 0
  4620.9     .05       0  5069.8     .03       0  5075.8     .05       0
  5314.3     .08       0  5571.2     .05       0  5631.1     .08       0
Bank Sta=5069.8,5075.8
XS Rating Curve= 0 ,0
Exp/Cntr=0.3,0.1

Type RM Length L Ch R = 1 ,1903    ,543,543,543
BEGIN DESCRIPTION:
UNT090 IN ROCK 3.0
END DESCRIPTION:
XS GIS Cut Line= 3
      3648648.25     10146476.66        3648225.      10146936.2
      3648076.05      10147134.8
#Sta/Elev= 30
  4556.1  231.04  4627.8  230.27  4833.1  222.62  4861.5   220.7  4868.3  219.89
  4882.4  217.31  4903.4  215.48  4931.8  214.99  4953.3  215.42  4967.5   214.9
  4988.5  215.48  4999.7  214.69  5002.4  214.19  5005.7  214.69  5024.2  215.51
  5045.2  215.11  5059.4  215.69  5066.2  215.39  5073.6  216.33  5094.5  220.08
  5108.7  219.39  5130.3  220.47  5165.4  221.55  5187.7  222.72    5244   226.9
  5258.5  227.64  5287.7  227.81    5294  228.24  5358.5  229.73  5429.1   230.6
#Mann= 3 ,-1 , 0
  4556.1     .05       0  4999.7     .04       0  5005.7     .05       0
Bank Sta=4999.7,5005.7
XS Rating Curve= 0 ,0
Exp/Cntr=0.3,0.1

Type RM Length L Ch R = 1 ,1360    ,378,378,378
BEGIN DESCRIPTION:
UNT090 IN ROCK 2.0
END DESCRIPTION:
XS GIS Cut Line= 3
      3648371.95      10146313.4      3648139.68     10146388.73
       3647892.1     10146791.66
#Sta/Elev= 30
    4657  226.98  4709.4  228.12    4798  225.25  4829.9  223.47  4856.6  218.82
  4861.9  217.11  4888.1  214.06  4893.9  212.76  4903.6  212.66  4908.3  211.54
  4923.7  211.68  4929.6  211.17    4975  211.37    5000  210.26  5002.7  209.76
    5006  210.26  5033.7  210.44  5045.6  211.38  5097.7  212.98  5134.4  215.43
  5140.3  214.99  5171.1  216.06    5177  215.81  5192.4  217.06  5198.3  216.54
  5207.8  217.31  5213.7  216.97  5229.1  218.27  5256.7  219.12  5374.1  221.67
#Mann= 3 ,-1 , 0
    4657     .05       0    5000     .03       0    5006     .05       0
Bank Sta=5000,5006
XS Rating Curve= 0 ,0
Exp/Cntr=0.3,0.1

Type RM Length L Ch R = 1 ,982     ,0,0,0
BEGIN DESCRIPTION:
UNT090 IN ROCK 1.0
END DESCRIPTION:
XS GIS Cut Line= 3
      3648340.65     10146206.65      3647951.32     10146081.06
      3647592.12     10146491.63
#Sta/Elev= 30
  4434.5  222.71  4495.2  224.83  4527.3  224.84    4538  224.14  4564.6  224.35
  4569.8  223.97  4596.6   225.3  4601.9  224.87  4622.1  225.32  4762.1  219.72
  4794.2  216.86  4800.7  215.83  4840.5  212.77  4846.8  212.77  4850.5  211.97
  4864.7  212.41  4871.4  211.71    4879  212.04  4928.3  208.52  4988.9  207.21
  4991.7  206.71  4994.9  207.21  5013.7  207.63  5056.5  212.05  5077.3  213.35
  5183.6  214.04  5247.2  213.29  5275.7  213.43  5325.1  214.88  5389.1   219.2
#Mann= 3 ,-1 , 0
  4434.5     .05       0  4988.9     .03       0  4994.9     .05       0
Bank Sta=4988.9,4994.9
XS Rating Curve= 0 ,0
Exp/Cntr=0.3,0.1

Chan Stop Cuts=-1
Use User Specified Reach Order=0
Composite Channel Slope=5