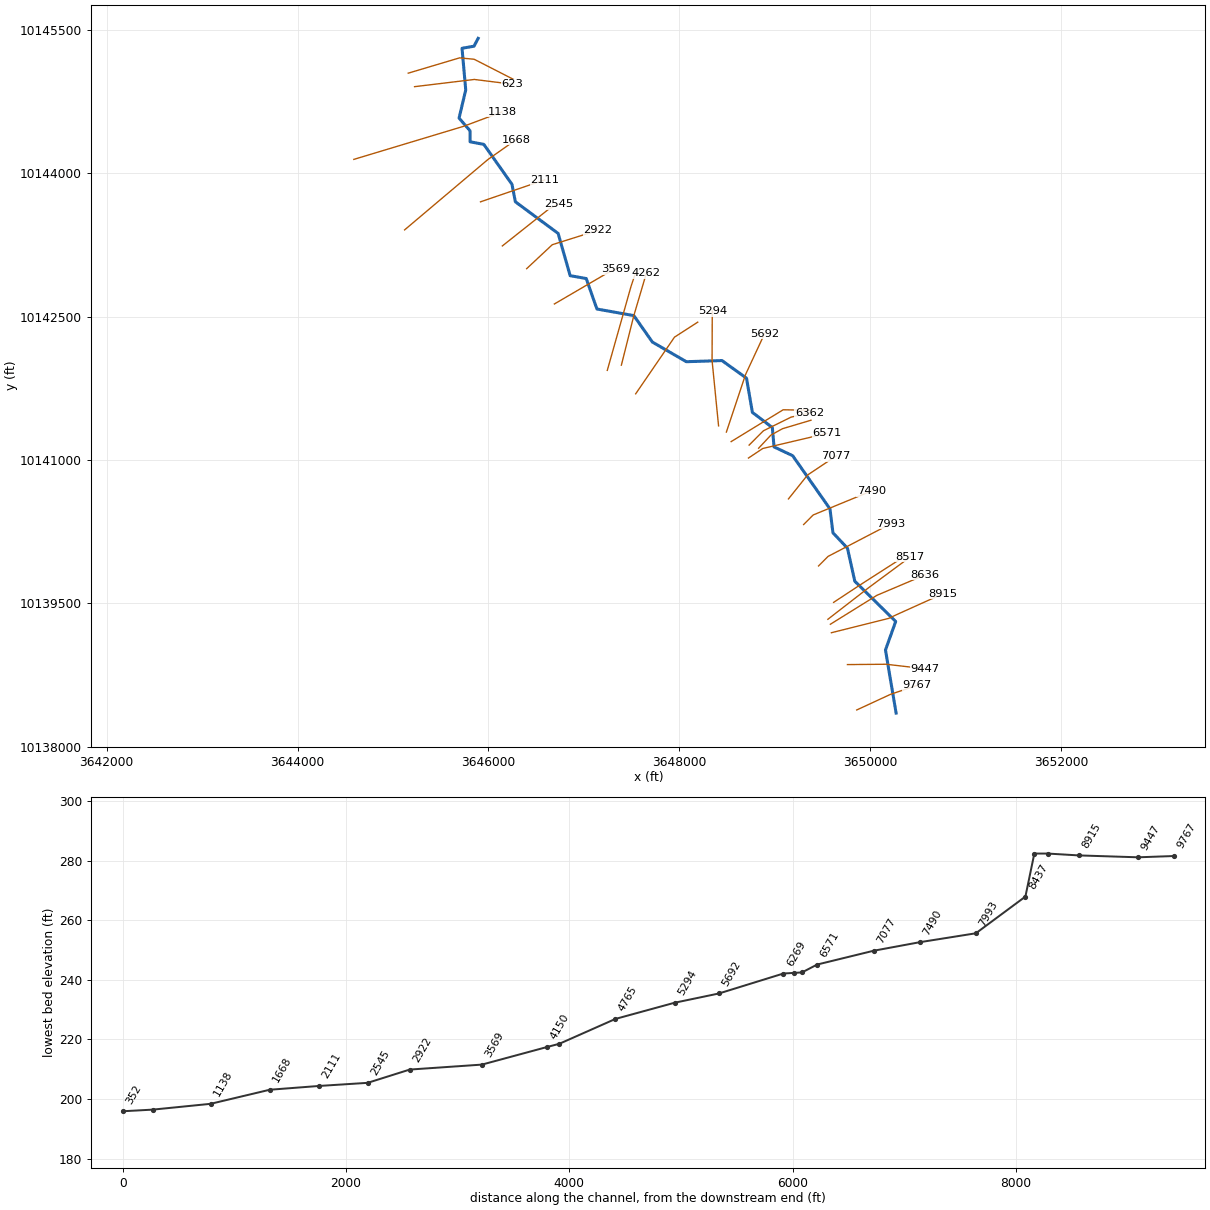
--- UNT091 IN ROCK.prj (project) ---

Proj Title=UNT091 IN ROCK Base Level Engineering
Current Plan=p01
Default Exp/Contr=0.3,0.1
English Units
Geom File=g01
Flow File=f01
Plan File=p01
Y Axis Title=Elevation
X Axis Title(PF)=Main Channel Distance
X Axis Title(XS)=Station
BEGIN DESCRIPTION:
UNT091 IN ROCK
END DESCRIPTION:
DSS Export Rating Curves= 0
DSS Export Rating Curve Sorted= 0
DSS Export Volume Flow Curves= 0
DXF OffsetX= 0
DXF OffsetY= 0
DXF ScaleX= 1
DXF ScaleY= 10

--- UNT091 IN ROCK.p01 (plan) ---

Plan Title=Multiple Run
Short Identifier=Multiple
Geom File=g01
Flow File=f01
Subcritical Flow
K Sum by GR= 0
Std Step Tol= 0.01
Critical Tol= 0.01
Num of Std Step Trials= 20
Max Error Tol= 0.3
Flow Tol Ratio= 0.001
Split Flow NTrial= 30
Split Flow Tol= 0.02
Split Flow Ratio= 0.02
Log Output Level= 0
Friction Slope Method= 1
Unsteady Friction Slope Method= 2
Unsteady Bridges Friction Slope Method= 1
Parabolic Critical Depth
Global Vel Dist=  1 , 1 , 1
Global Log Level= 0
CheckData=True
Encroach Param= -1, 0, 0, 0
BEGIN DESCRIPTION:
Multiple Run
END DESCRIPTION:

--- UNT091 IN ROCK.f01 (steady flow) ---

Flow Title=Multiple
Program Version=4.10
Number of Profiles= 7
Profile Names=10-year,25-year,50-year,1pct_min,100-year,1pct_plu,500-year
River Rch & RM=UNT091 IN ROCK,Reach-1         ,9767
     319     413     488     424     573     775     790
River Rch & RM=UNT091 IN ROCK,Reach-1         ,5692
     541     726     878     779    1054    1426    1520
River Rch & RM=UNT091 IN ROCK,Reach-1         ,4765
     906    1254    1546    1396    1888    2554    2822
River Rch & RM=UNT091 IN ROCK,Reach-1         ,623
    1025    1424    1760    1594    2155    2915    3236
Boundary for River Rch & Prof#=UNT091 IN ROCK,Reach-1         , 1
Up Type= 0
Dn Type= 3
Dn Slope=0.008
Boundary for River Rch & Prof#=UNT091 IN ROCK,Reach-1         , 2
Up Type= 0
Dn Type= 3
Dn Slope=0.008
Boundary for River Rch & Prof#=UNT091 IN ROCK,Reach-1         , 3
Up Type= 0
Dn Type= 3
Dn Slope=0.008
Boundary for River Rch & Prof#=UNT091 IN ROCK,Reach-1         , 4
Up Type= 0
Dn Type= 3
Dn Slope=0.008
Boundary for River Rch & Prof#=UNT091 IN ROCK,Reach-1         , 5
Up Type= 0
Dn Type= 3
Dn Slope=0.008
Boundary for River Rch & Prof#=UNT091 IN ROCK,Reach-1         , 6
Up Type= 0
Dn Type= 3
Dn Slope=0.008
Boundary for River Rch & Prof#=UNT091 IN ROCK,Reach-1         , 7
Up Type= 0
Dn Type= 3
Dn Slope=0.008
DSS Import GetInterval= 0
DSS Import GetPeak= 0
DSS Import FillOption= 0

--- UNT091 IN ROCK.g01 (geometry) ---

Geom Title=Existing Conditions
Program Version=4.10

River Reach=UNT091 IN ROCK  ,Reach-1
Reach XY= 30
      3650269.87     10138351.18      3650158.37     10139010.81
      3650265.45     10139309.39      3649837.19     10139730.43
      3649760.39     10140075.66      3649608.09      10140237.6
      3649577.08     10140487.57      3649186.35     10141044.05
      3648991.26     10141136.06       3648973.2     10141338.83
      3648764.37     10141497.33      3648702.97     10141855.27
      3648446.17     10142039.54      3648072.51     10142027.72
      3647717.13     10142233.09      3647522.69       10142510.
      3647135.98     10142579.06       3647024.1     10142897.96
      3646855.57     10142927.95      3646729.73     10143370.13
      3646281.78     10143701.16      3646246.31     10143883.86
      3645951.65     10144301.95      3645807.56     10144328.73
      3645807.15     10144444.21      3645692.11     10144576.92
      3645762.03     10144871.86      3645722.92     10145307.24
      3645848.55     10145329.15      3645892.11     10145411.64

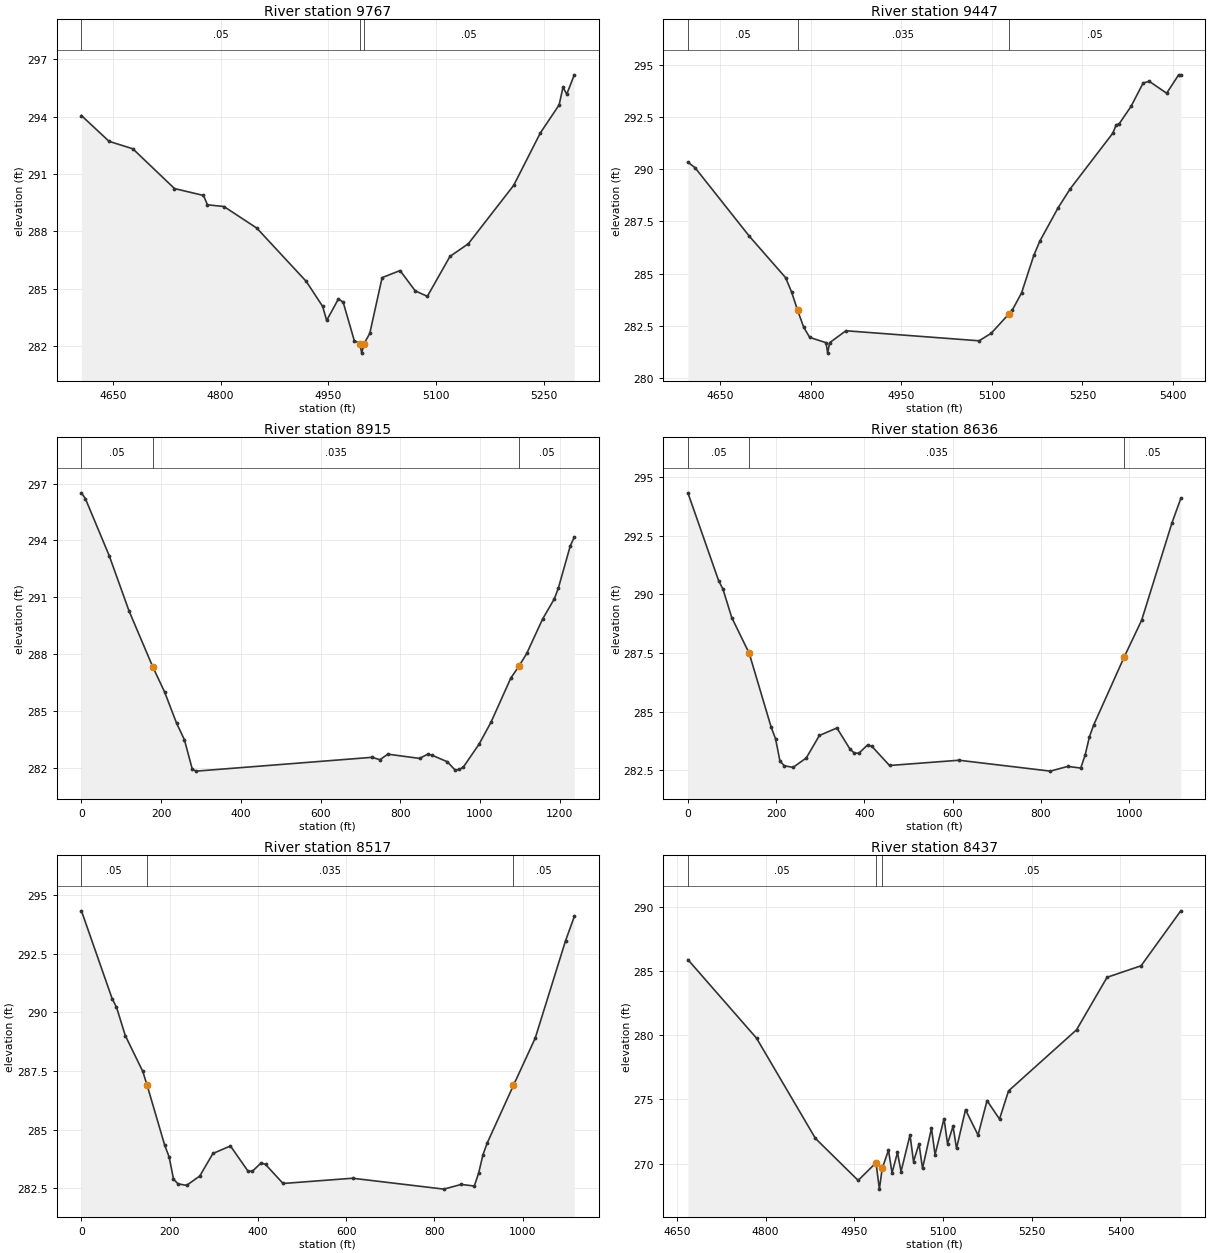
Type RM Length L Ch R = 1 ,9767    ,320,320,320
BEGIN DESCRIPTION:
UNT091 IN ROCK 22.0
END DESCRIPTION:
XS GIS Cut Line= 3
      3649857.12     10138383.36      3650212.84      10138547.6
      3650492.13     10138641.65
#Sta/Elev= 30
  4606.2  294.06  4644.7  292.71  4677.8  292.32  4735.8  290.24  4776.2  289.88
  4781.7  289.39  4804.7   289.3  4850.5  288.17  4919.4  285.38  4942.1  284.08
  4947.8  283.34  4964.2  284.47  4970.8  284.29  4986.2  282.29  4993.9  282.13
  4996.6  281.63  4999.9  282.13  5007.8  282.66    5025  285.58    5050  285.95
  5071.1  284.89    5088   284.6  5119.5  286.69    5145  287.35  5208.3  290.41
  5245.4  293.15  5271.6  294.62  5276.9  295.54  5282.2  295.18  5292.7  296.19
#Mann= 3 ,-1 , 0
  4606.2     .05       0  4993.9     .03       0  4999.9     .05       0
Bank Sta=4993.9,4999.9
XS Rating Curve= 0 ,0
Exp/Cntr=0.3,0.1

Type RM Length L Ch R = 1 ,9447    ,532,532,532
BEGIN DESCRIPTION:
UNT091 IN ROCK 21.0
END DESCRIPTION:
XS GIS Cut Line= 3
      3649760.35     10138858.36      3650165.22     10138861.78
      3650573.99     10138814.38
#Sta/Elev= 30
  4596.5  290.33  4608.3  290.07  4698.3  286.79  4758.3  284.81  4768.3  284.12
  4778.3  283.24  4788.3  282.44  4798.3  281.95  4825.3   281.7    4828   281.2
  4831.3   281.7  4858.3  282.27  5078.8  281.79  5098.9  282.15  5128.4  283.08
  5133.5  283.24  5149.3  284.09  5169.4  285.87  5179.5  286.56  5209.7  288.15
  5229.8  289.06  5300.3  291.72  5305.9  292.11  5310.9  292.17  5330.5     293
  5350.6  294.12  5360.7   294.2  5389.5  293.63  5409.4  294.51  5412.9  294.51
#Mann= 3 , 0 , 0
  4596.5     .05       0  4778.3    .035       0  5128.4     .05       0
Bank Sta=4778.3,5128.4
XS Rating Curve= 0 ,0
Exp/Cntr=0.3,0.1

Type RM Length L Ch R = 1 ,8915    ,279,279,279
BEGIN DESCRIPTION:
UNT091 IN ROCK 19.0
END DESCRIPTION:
XS GIS Cut Line= 4
     3649592.106    10139191.642     3650192.106    10139341.642
     3650269.875    10139378.465     3650759.552    10139599.286
#Sta/Elev= 30
       0296.5145 9.94096296.205569.58672293.2057119.2915290.2943178.9373287.3403
208.7601286.0095 238.583284.3746 258.465283.4891278.3469281.9279288.2878281.8353
729.7375282.5641749.1428282.4364769.0535282.7303848.6963282.5059 868.607282.7247
878.5624282.6864918.3838282.3283938.2945 281.879948.2499 281.927958.2053282.0427
998.0267283.26151027.893284.4164 1077.67286.7476 1097.58287.35431117.491288.0397
1157.312289.85481187.178 290.9381197.134291.5055    1227293.72981236.955294.1727
#Mann= 3 , 0 , 0
       0     .05       0178.9373    .035       0 1097.58     .05       0
Bank Sta=178.9373,1097.58
XS Rating Curve= 0 ,0
Exp/Cntr=0.3,0.1

Type RM Length L Ch R = 1 ,8636    ,119,119,119
BEGIN DESCRIPTION:
Mapping XS 42d1f0f8
END DESCRIPTION:
XS GIS Cut Line= 4
     3649581.166    10139280.275     3650015.317    10139550.003
     3650069.131    10139583.266      3650572.92    10139796.768
#Sta/Elev= 30
       0294.324969.54629290.583679.48148290.217999.35184289.0091139.0926287.4756
188.7685284.3303198.7037283.8371208.6389282.8938218.5741282.6856238.4444 282.619
  268.25283.0193298.0555283.9788337.7963284.2988367.6018283.3944 377.537283.2278
387.4722283.2223407.3426283.5756417.2777 283.512457.0185282.6994614.5299282.9234
821.5241282.4589860.9515282.6597890.5222282.5906 900.379283.1411910.2359283.9279
920.0928284.4374989.0908287.33141028.518288.89241097.516293.0571 1117.23294.0831
#Mann= 3 , 0 , 0
       0     .05       0139.0926    .035       0989.0908     .05       0
Bank Sta=139.0926,989.0908
XS Rating Curve= 0 ,0
Exp/Cntr=0.3,0.1

Type RM Length L Ch R = 1 ,8517    ,80,80,80
BEGIN DESCRIPTION:
Mapping XS 28e6cd61
END DESCRIPTION:
XS GIS Cut Line= 4
     3649555.125    10139332.359      3649919.43     10139614.21
     3649980.758    10139661.851      3650418.84     10139985.57
#Sta/Elev= 30
       0294.324969.54629290.583679.48148290.217999.35184289.0091139.0926287.4756
149.0278 286.879188.7685284.3303198.7037283.8371208.6389282.8938218.5741282.6856
238.4444 282.619  268.25283.0193298.0555283.9788337.7963284.2988 377.537283.2278
387.4722283.2223407.3426283.5756417.2777 283.512457.0185282.6994614.5299282.9234
821.5241282.4589860.9515282.6597890.5222282.5906 900.379283.1411910.2359283.9279
920.0928284.4374979.2339286.88221028.518288.89241097.516293.0571 1117.23294.0831
#Mann= 3 , 0 , 0
       0     .05       0149.0278    .035       0979.2339     .05       0
Bank Sta=149.0278,979.2339
XS Rating Curve= 0 ,0
Exp/Cntr=0.3,0.1

Type RM Length L Ch R = 1 ,8437    ,444,444,444
BEGIN DESCRIPTION:
UNT091 IN ROCK 18.0
END DESCRIPTION:
XS GIS Cut Line= 3
      3649615.25     10139509.29      3649892.11     10139691.64
      3650314.53     10139962.28
#Sta/Elev= 30
  4668.7  285.92  4784.7  279.79  4884.3  271.96  4956.5  268.68  4986.7  270.06
  4992.4     268  4997.2  269.63  5007.8  271.04  5013.8  269.27    5023  270.86
    5029  269.37  5044.2  272.23  5050.1  270.15  5059.4  271.54  5065.3  269.62
  5080.5  272.76  5086.5  270.69  5101.7   273.5  5107.6  271.55  5116.9  272.91
  5122.8  271.18    5138   274.2  5159.2  272.22  5174.4  274.91  5195.5  273.47
  5210.7  275.67  5325.7  280.44  5377.3  284.54  5434.8  285.44  5501.9  289.73
#Mann= 3 , 0 , 0
  4668.7     .05       0  4986.7    .035       0  4997.2     .05       0
Bank Sta=4986.7,4997.2
XS Rating Curve= 0 ,0
Exp/Cntr=0.3,0.1

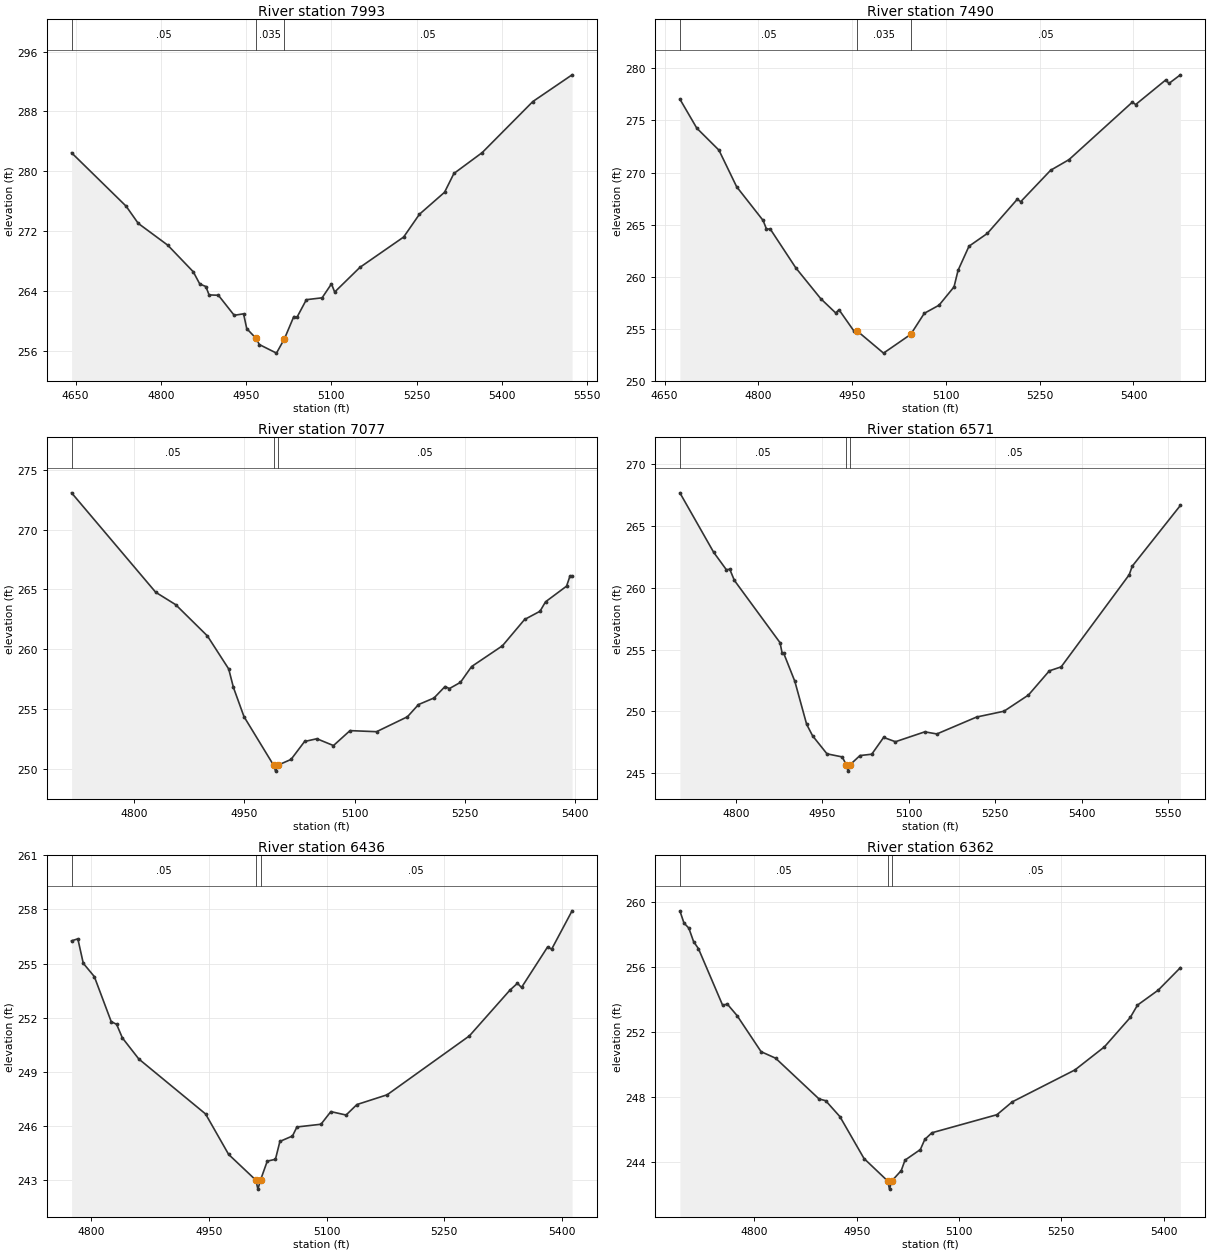
Type RM Length L Ch R = 1 ,7993    ,503,503,503
BEGIN DESCRIPTION:
UNT091 IN ROCK 17.0
END DESCRIPTION:
XS GIS Cut Line= 3
       3649457.4      10139890.5      3649557.39     10139990.49
      3650213.35      10140331.7
#Sta/Elev= 30
  4642.9  282.47    4739  275.32  4760.2  273.03  4812.2  270.11  4857.1  266.55
  4868.5  264.92  4879.2  264.58  4884.9  263.46  4901.3  263.41  4929.1  260.73
  4945.6  260.93  4951.2  258.94  4967.7  257.64  4973.3  256.82  5003.5  255.67
  5017.5  257.59    5034  260.56  5039.6  260.47  5056.1  262.82  5083.8  263.07
  5100.3  264.94  5105.9  263.84  5150.3  267.14  5227.3   271.2  5255.1  274.25
  5299.3  277.19  5315.7   279.7  5365.6   282.5  5454.7  289.33  5523.7   292.9
#Mann= 3 , 0 , 0
  4642.9     .05       0  4967.7    .035       0  5017.5     .05       0
Bank Sta=4967.7,5017.5
XS Rating Curve= 0 ,0
Exp/Cntr=0.3,0.1

Type RM Length L Ch R = 1 ,7490    ,413,413,413
BEGIN DESCRIPTION:
UNT091 IN ROCK 16.0
END DESCRIPTION:
XS GIS Cut Line= 3
      3649301.34     10140324.02      3649401.37     10140424.05
      3650011.07     10140674.76
#Sta/Elev= 30
  4674.4  277.05  4701.5  274.26  4736.9  272.15  4765.2  268.64  4807.6   265.4
  4812.9  264.58    4819  264.58  4859.9  260.85  4899.7   257.9  4923.6  256.53
    4929  256.83    4953  254.78  4958.4  254.78  5000.2  252.67  5043.7  254.47
  5065.4  256.49    5089  257.27    5113  259.03  5119.4  260.61  5136.9  262.93
  5166.3  264.16  5214.2  267.44  5219.6   267.2  5267.5  270.22  5296.9  271.24
  5398.1  276.75  5403.6  276.53  5451.5  278.88  5456.9  278.56  5475.1  279.38
#Mann= 3 , 0 , 0
  4674.4     .05       0  4958.4    .035       0  5043.7     .05       0
Bank Sta=4958.4,5043.7
XS Rating Curve= 0 ,0
Exp/Cntr=0.3,0.1

Type RM Length L Ch R = 1 ,7077    ,506,506,506
BEGIN DESCRIPTION:
UNT091 IN ROCK 15.0
END DESCRIPTION:
XS GIS Cut Line= 3
      3649142.13     10140591.68      3649342.11     10140841.64
      3649642.13     10141041.66
#Sta/Elev= 30
  4715.2  273.09  4829.6  264.77  4856.8  263.73    4900  261.11  4928.9  258.35
  4935.3  256.81  4949.7  254.36  4989.9   250.3  4992.6   249.8  4995.9   250.3
  5013.7  250.78  5032.1  252.28  5048.8  252.51  5071.4  251.94  5093.9  253.19
    5130   253.1    5172  254.35    5187  255.37  5208.1  255.92  5223.1  256.88
  5229.1  256.71  5244.1  257.23  5259.2  258.55  5301.2  260.29  5331.3  262.49
  5352.3  263.18  5359.8  263.97  5388.4  265.28  5392.9   266.1  5395.9   266.1
#Mann= 3 ,-1 , 0
  4715.2     .05       0  4989.9     .03       0  4995.9     .05       0
Bank Sta=4989.9,4995.9
XS Rating Curve= 0 ,0
Exp/Cntr=0.3,0.1

Type RM Length L Ch R = 1 ,6571    ,135,135,135
BEGIN DESCRIPTION:
UNT091 IN ROCK 14.0
END DESCRIPTION:
XS GIS Cut Line= 3
      3648723.38     10141019.67      3648873.36     10141119.65
      3649543.49     10141276.97
#Sta/Elev= 30
  4702.6  267.69  4761.2  262.88  4783.2  261.47  4789.2   261.5  4797.2   260.6
  4876.4  255.56  4880.1   254.7  4882.8   254.7  4902.1  252.43  4922.6  248.95
  4932.9  248.02  4957.9  246.56  4984.3  246.31  4991.6  245.66  4994.3  245.16
  4997.6  245.66  5015.1  246.42  5035.6  246.53  5056.2  247.89  5076.7  247.54
  5127.6  248.34  5148.6  248.17  5217.6  249.54  5265.1  250.01  5307.5  251.32
  5343.8  253.28  5364.3   253.6  5482.4  261.06  5487.6  261.75  5571.2  266.67
#Mann= 3 ,-1 , 0
  4702.6     .05       0  4991.6     .03       0  4997.6     .05       0
Bank Sta=4991.6,4997.6
XS Rating Curve= 0 ,0
Exp/Cntr=0.3,0.1

Type RM Length L Ch R = 1 ,6436    ,74,74,74
BEGIN DESCRIPTION:
Mapping XS 736a5525
END DESCRIPTION:
XS GIS Cut Line= 4
        3648830.     10141122.55      3648958.04     10141259.27
      3649079.56     10141326.54      3649378.05     10141415.22
#Sta/Elev= 30
  4775.1  256.26  4783.1  256.37    4790  255.02  4804.1  254.28  4825.6  251.79
  4832.5  251.64  4839.8  250.89  4860.8  249.72  4945.8  246.68  4975.2  244.44
  5009.8  243.02  5012.5  242.52  5015.8  243.02  5024.4  244.07  5034.8  244.17
  5040.5  245.16  5056.5  245.46  5062.2  245.96  5092.8  246.11  5105.4  246.81
  5124.8  246.62  5138.6   247.2  5177.1  247.74  5281.9     251  5333.5  253.53
  5343.1  253.91  5348.3  253.68  5381.5  255.92  5386.7   255.8  5412.7  257.92
#Mann= 3 ,-1 , 0
  4775.1     .05       0  5009.8     .03       0  5015.8     .05       0
Bank Sta=5009.8,5015.8
XS Rating Curve= 0 ,0
Exp/Cntr=0.3,0.1

Type RM Length L Ch R = 1 ,6362    ,93,93,93
BEGIN DESCRIPTION:
Mapping XS 42f80931
END DESCRIPTION:
XS GIS Cut Line= 4
      3648730.16     10141155.09      3648879.91     10141304.84
      3649170.71     10141448.07      3649363.86     10141491.47
#Sta/Elev= 30
  4690.8  259.45  4696.8   258.7  4703.9  258.39  4710.9  257.56    4718  257.13
  4753.4  253.66  4760.4  253.72  4774.6  253.02  4809.9   250.8  4831.2   250.4
  4894.8   247.9  4904.6  247.79  4925.5  246.81  4960.8  244.24  4995.5  242.86
  4998.2  242.36  5001.5  242.86  5015.4   243.5  5020.9  244.14  5043.4  244.79
  5049.9  245.41  5060.3  245.82  5155.7  246.93  5178.2  247.72  5270.1  249.68
  5313.4   251.1  5351.2   252.9  5361.8  253.66  5392.2  254.58  5424.7  255.96
#Mann= 3 ,-1 , 0
  4690.8     .05       0  4995.5     .03       0  5001.5     .05       0
Bank Sta=4995.5,5001.5
XS Rating Curve= 0 ,0
Exp/Cntr=0.3,0.1

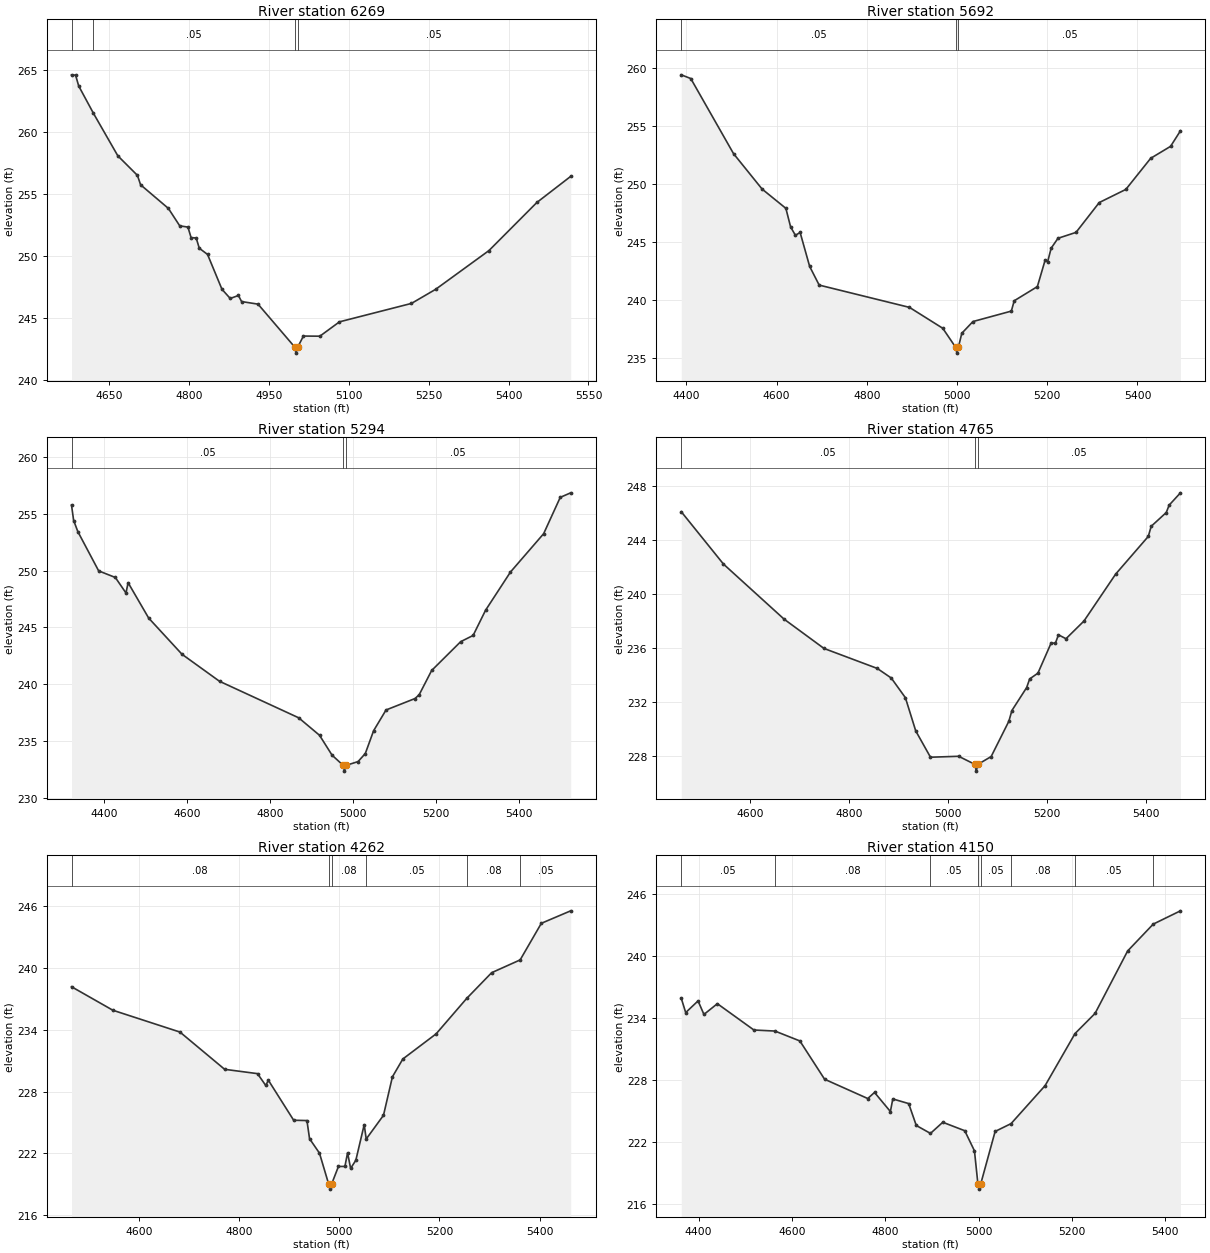
Type RM Length L Ch R = 1 ,6269    ,577,577,577
BEGIN DESCRIPTION:
UNT091 IN ROCK 13.0
END DESCRIPTION:
XS GIS Cut Line= 3
      3648542.14     10141191.66      3649086.78      10141524.6
       3649385.6     10141519.68
#Sta/Elev= 30
  4579.4  264.65  4587.1  264.62  4592.9  263.75  4620.7  261.53  4666.4   258.1
  4703.2  256.52  4709.1  255.76  4761.3  253.85  4782.6  252.44    4798  252.34
  4803.9  251.49  4813.5  251.46  4819.3  250.63  4834.8  250.13  4861.9  247.31
  4877.4  246.57  4892.8  246.81  4898.7  246.32  4929.6  246.11  4998.3  242.65
    5001  242.15  5004.3  242.65  5014.8  243.53  5045.7  243.52  5082.5  244.68
  5217.7  246.17  5263.1  247.31  5363.1  250.44  5453.1  254.33  5516.6  256.44
#Mann= 4 ,-1 , 0
  4579.4     .08       0  4620.7     .05       0  4998.3     .03       0
  5004.3     .05       0
Bank Sta=4998.3,5004.3
XS Rating Curve= 0 ,0
Exp/Cntr=0.3,0.1

Type RM Length L Ch R = 1 ,5692    ,398,398,398
BEGIN DESCRIPTION:
UNT091 IN ROCK 12.0
END DESCRIPTION:
XS GIS Cut Line= 3
      3648492.11     10141291.66      3648692.11     10141891.64
      3648892.34     10142321.46
#Sta/Elev= 30
  4388.7  259.42  4409.8   259.1  4504.6  252.63  4567.9  249.58  4620.6  247.92
  4631.1  246.32  4641.7   245.6  4652.2  245.84  4673.3  242.92  4694.4  241.31
  4894.6  239.39  4968.4  237.59    4997  235.95  4999.8  235.45    5003  235.95
  5010.6  237.16  5035.3  238.17  5120.4  239.07  5126.8  239.96  5178.1  241.18
  5195.4  243.47  5200.9  243.32  5208.7  244.49  5223.8  245.34  5263.8  245.85
  5315.3  248.42  5374.2  249.55  5429.3  252.23  5473.4  253.26  5495.3   254.6
#Mann= 3 ,-1 , 0
  4388.7     .05       0    4997     .03       0    5003     .05       0
Bank Sta=4997,5003
XS Rating Curve= 0 ,0
Exp/Cntr=0.3,0.1

Type RM Length L Ch R = 1 ,5294    ,529,529,529
BEGIN DESCRIPTION:
UNT091 IN ROCK 11.0
END DESCRIPTION:
XS GIS Cut Line= 3
      3648410.16     10141356.47      3648342.11     10142041.64
      3648344.19     10142556.89
#Sta/Elev= 30
  4321.2  255.78  4326.4  254.42  4336.5  253.44  4386.7  249.98  4426.9   249.4
  4452.6  248.03  4457.7  248.94  4507.3  245.82  4587.7  242.63  4678.1  240.25
  4869.1  237.03  4919.3  235.49  4949.5  233.74  4976.6  232.83  4979.3  232.33
  4982.6  232.83  5012.2  233.17  5029.7  233.88  5049.7  235.89  5079.7  237.72
  5149.7  238.73  5159.7  239.07  5189.7   241.2  5259.7  243.74  5289.7  244.29
  5319.7  246.51  5379.8  249.88  5459.8  253.26  5499.8  256.46    5525  256.86
#Mann= 3 ,-1 , 0
  4321.2     .05       0  4976.6     .03       0  4982.6     .05       0
Bank Sta=4976.6,4982.6
XS Rating Curve= 0 ,0
Exp/Cntr=0.3,0.1

Type RM Length L Ch R = 1 ,4765    ,503,503,503
BEGIN DESCRIPTION:
UNT091 IN ROCK 10.0
END DESCRIPTION:
XS GIS Cut Line= 3
       3647542.1     10141691.64      3647948.36     10142284.45
      3648192.11     10142441.64
#Sta/Elev= 30
  4460.7  246.12    4546  242.24  4668.5  238.16  4749.1  235.99  4856.7  234.51
    4885   233.8  4913.6  232.34  4934.5  229.88  4964.3  227.93  5021.2     228
  5054.1   227.4  5056.8   226.9  5060.1   227.4  5086.9  227.98  5122.7   230.6
  5128.8  231.39  5158.6  233.09  5164.7  233.73  5181.4  234.16  5207.7  236.36
  5216.9   236.4  5222.9     237  5238.1  236.71  5274.4  238.02  5338.5   241.5
  5404.4  244.29  5410.3  245.04  5440.7  246.06  5446.6  246.61  5469.4  247.52
#Mann= 3 ,-1 , 0
  4460.7     .05       0  5054.1     .04       0  5060.1     .05       0
Bank Sta=5054.1,5060.1
XS Rating Curve= 0 ,0
Exp/Cntr=0.3,0.1

Type RM Length L Ch R = 1 ,4262    ,112,112,112
BEGIN DESCRIPTION:
UNT091 IN ROCK 9.0
END DESCRIPTION:
XS GIS Cut Line= 3
      3647392.09      10141991.6      3647522.69       10142510.
      3647653.69     10142952.94
#Sta/Elev= 30
  4465.4  238.17  4547.9  235.89    4682  233.77  4771.1  230.16  4836.7  229.74
  4853.2  228.59  4858.4   229.1  4908.9  225.22  4935.4  225.19  4940.6  223.43
  4960.4  222.03  4978.7  219.04  4981.4  218.54  4984.7  219.04  4998.3  220.74
  5011.2  220.74  5016.5  222.07  5022.6  220.55    5033  221.34  5049.7  224.79
  5053.7   223.4  5088.2   225.7    5106  229.43  5126.8  231.16  5193.3   233.6
  5254.2  237.03  5304.1  239.53    5361  240.77  5403.3  244.32  5461.9  245.53
#Mann= 6 ,-1 , 0
  4465.4     .08       0  4978.7     .07       0  4984.7     .08       0
  5053.7     .05       0  5254.2     .08       0    5361     .05       0
Bank Sta=4978.7,4984.7
XS Rating Curve= 0 ,0
Exp/Cntr=0.3,0.1

Type RM Length L Ch R = 1 ,4150    ,581,581,581
BEGIN DESCRIPTION:
UNT091 IN ROCK 8.0
END DESCRIPTION:
XS GIS Cut Line= 3
      3647244.67     10141936.99       3647492.8     10142814.32
      3647542.81     10142964.36
#Sta/Elev= 30
  4362.7  235.94  4372.2  234.55  4398.7  235.68  4411.3  234.37  4440.1  235.41
  4518.4  232.86  4563.4  232.76  4616.9   231.8  4669.9  228.09  4762.4  226.22
  4776.9  226.81  4810.9  224.96  4816.1  226.18  4850.1  225.73  4866.4  223.61
  4896.8  222.84  4923.2  223.92  4970.3   223.1  4991.1  221.15  4998.5  217.94
  5001.2  217.44  5004.5  217.94  5035.4  223.03  5069.6  223.79  5142.5  227.47
  5206.7  232.52  5249.6  234.47  5319.4  240.52  5374.2  243.12  5432.6  244.41
#Mann= 8 ,-1 , 0
  4362.7     .05       0  4563.4     .08       0  4896.8     .05       0
  4998.5     .04       0  5004.5     .05       0  5069.6     .08       0
  5206.7     .05       0  5374.2     .08       0
Bank Sta=4998.5,5004.5
XS Rating Curve= 0 ,0
Exp/Cntr=0.3,0.1

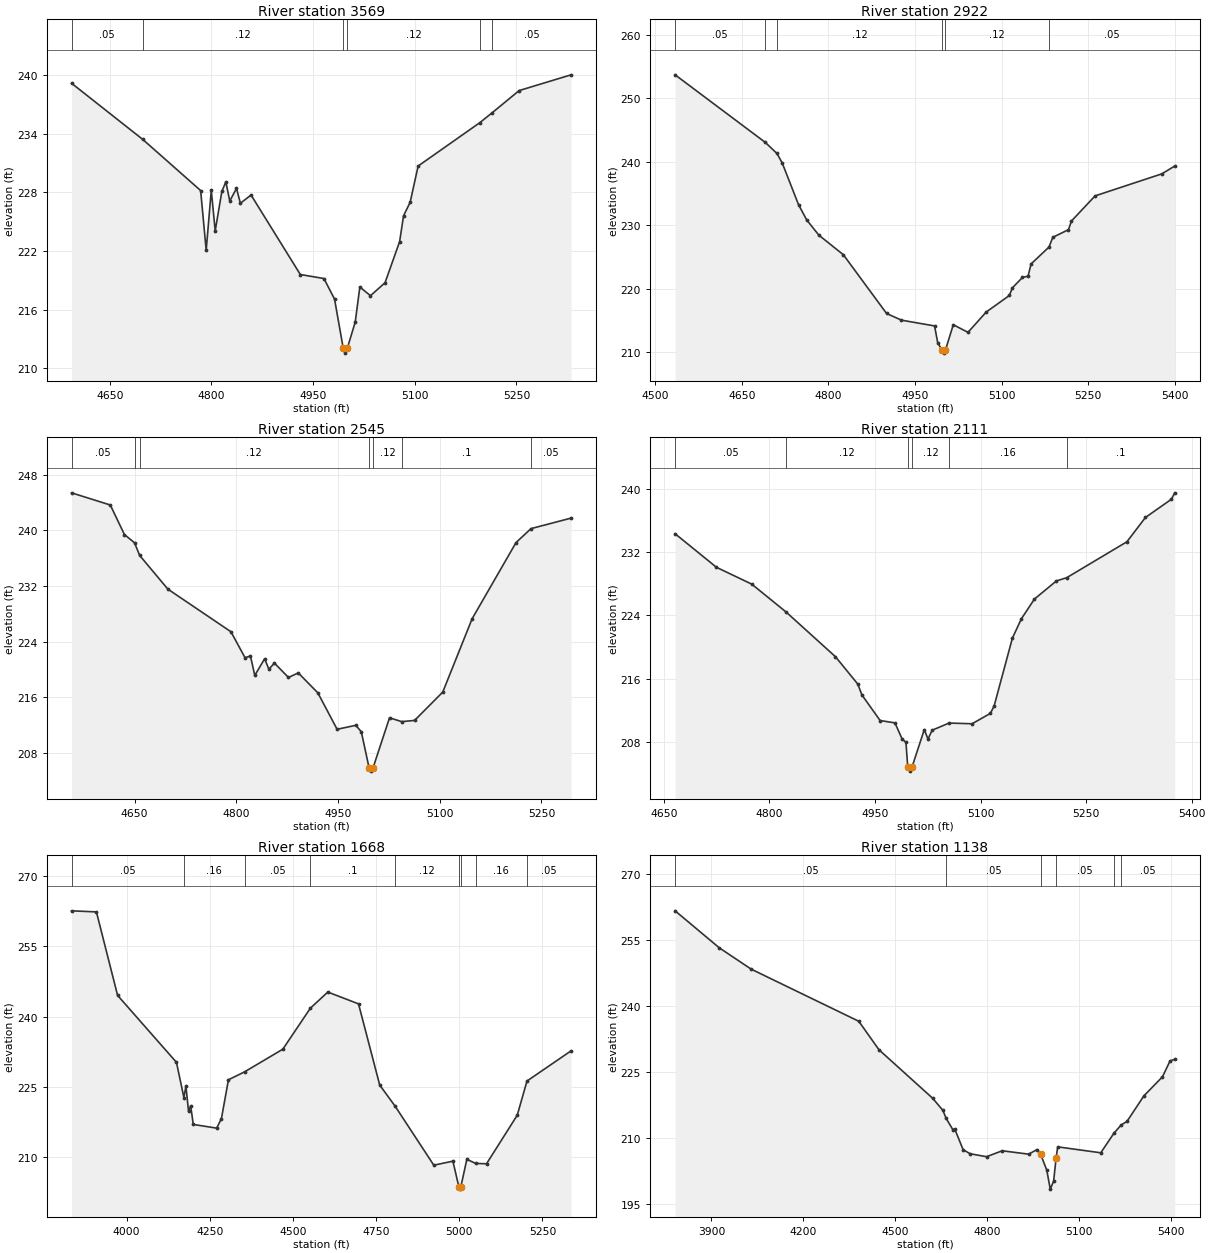
Type RM Length L Ch R = 1 ,3569    ,647,647,647
BEGIN DESCRIPTION:
UNT091 IN ROCK 7.0
END DESCRIPTION:
XS GIS Cut Line= 3
      3646690.49     10142631.88      3647231.22      10142947.2
      3647330.64      10142996.9
#Sta/Elev= 30
  4593.5  239.19  4698.7  233.43    4784   228.2  4792.2  222.08  4799.7  228.23
  4805.5  224.07  4815.3  228.11  4821.2  229.09    4827  227.13  4836.9  228.42
  4842.7   226.9  4858.4  227.74  4931.1   219.6  4965.9  219.19  4981.6  217.08
  4994.4  212.05  4997.1  211.55  5000.4  212.05  5012.1  214.73  5018.9  218.32
  5034.6  217.43  5056.1  218.76  5077.6  222.97  5083.4  225.62  5093.1  226.99
  5104.9  230.71  5196.1  235.16  5213.7  236.14    5254  238.44  5330.6  240.05
#Mann= 6 ,-1 , 0
  4593.5     .05       0  4698.7     .12       0  4994.4     .07       0
  5000.4     .12       0  5196.1      .1       0  5213.7     .05       0
Bank Sta=4994.4,5000.4
XS Rating Curve= 0 ,0
Exp/Cntr=0.3,0.1

Type RM Length L Ch R = 1 ,2922    ,377,377,377
BEGIN DESCRIPTION:
UNT091 IN ROCK 6.0
END DESCRIPTION:
XS GIS Cut Line= 3
      3646400.28     10143001.37      3646668.52     10143252.02
      3647143.51     10143401.55
#Sta/Elev= 30
  4534.5  253.68  4690.6  243.05  4710.9   241.3  4719.9  239.82  4748.2  233.25
  4762.4  230.84  4783.4  228.45  4825.9  225.36  4900.7  216.12  4926.4  215.07
  4983.8  214.16  4989.3  211.49  4996.7  210.38  4999.5  209.88  5002.7  210.38
  5016.2  214.35  5041.7  213.15  5073.1  216.34  5113.3  218.95  5118.6  220.16
    5136  221.79  5145.7     222  5150.9  223.92  5181.9  226.57  5188.6  228.11
  5215.7  229.31  5220.9  230.68  5261.8  234.63  5377.2  238.09  5399.6  239.32
#Mann= 6 ,-1 , 0
  4534.5     .05       0  4690.6     .16       0  4710.9     .12       0
  4996.7     .07       0  5002.7     .12       0  5181.9     .05       0
Bank Sta=4996.7,5002.7
XS Rating Curve= 0 ,0
Exp/Cntr=0.3,0.1

Type RM Length L Ch R = 1 ,2545    ,434,434,434
BEGIN DESCRIPTION:
UNT091 IN ROCK 5.0
END DESCRIPTION:
XS GIS Cut Line= 3
      3646145.14     10143238.82      3646636.09     10143627.98
      3646734.76     10143677.32
#Sta/Elev= 30
  4556.9  245.39  4614.1  243.64  4634.9   239.4  4649.8  238.22  4657.4   236.4
    4699  231.56    4792  225.44  4812.8  221.71  4820.8  221.95  4827.2  219.16
  4841.7  221.56    4848  220.05  4856.1  220.94  4876.9  218.87  4891.3  219.53
  4920.2  216.66  4948.6  211.43  4976.2     212  4984.3  211.07  4995.7  205.92
  4998.5  205.42  5001.7  205.92  5025.9  213.08  5043.8  212.53  5062.8   212.7
  5104.4  216.77  5147.7   227.3  5212.5  238.25  5234.6  240.25  5293.7  241.76
#Mann= 7 ,-1 , 0
  4556.9     .05       0  4649.8     .16       0  4657.4     .12       0
  4995.7     .07       0  5001.7     .12       0  5043.8      .1       0
  5234.6     .05       0
Bank Sta=4995.7,5001.7
XS Rating Curve= 0 ,0
Exp/Cntr=0.3,0.1

Type RM Length L Ch R = 1 ,2111    ,443,443,443
BEGIN DESCRIPTION:
UNT091 IN ROCK 4.0
END DESCRIPTION:
XS GIS Cut Line= 3
      3645916.46     10143700.62      3646440.02      10143879.6
      3646588.57     10143929.12
#Sta/Elev= 30
    4666   234.3  4724.8  230.07  4774.9  227.95  4823.4  224.46  4893.9   218.8
  4925.6  215.35  4931.4  213.99  4957.3  210.76  4978.4  210.46  4988.7   208.4
    4994  208.02  4996.6  204.88  4999.3  204.38  5002.6  204.88  5020.1  209.62
  5025.3  208.43  5031.3  209.54  5055.3  210.44    5088  210.35    5114  211.66
  5119.3  212.59  5145.3  221.15  5158.1  223.59  5176.6  226.07  5207.9  228.36
  5222.4  228.76    5308  233.29  5334.3  236.35  5371.2  238.65  5375.9  239.46
#Mann= 6 ,-1 , 0
    4666     .05       0  4823.4     .12       0  4996.6     .07       0
  5002.6     .12       0  5055.3     .16       0  5222.4      .1       0
Bank Sta=4996.6,5002.6
XS Rating Curve= 0 ,0
Exp/Cntr=0.3,0.1

Type RM Length L Ch R = 1 ,1668    ,530,530,530
BEGIN DESCRIPTION:
UNT091 IN ROCK 3.0
END DESCRIPTION:
XS GIS Cut Line= 3
      3645121.67       10143407.      3645992.11     10144141.64
      3646288.68      10144350.4
#Sta/Elev= 30
  3834.4   262.6  3909.2  262.37  3972.9  244.52  4149.8  230.21  4172.2  222.67
  4178.3  225.16  4186.1  219.76  4192.6   220.9  4200.4  216.93  4270.7  216.14
    4285  218.18  4306.1  226.48    4355  228.19  4469.6  233.02  4552.4  241.79
  4604.8  245.23  4697.1  242.71  4760.8  225.35  4806.5   220.9  4923.4  208.22
  4980.8  209.08  4998.7   203.6  5001.5   203.1  5004.7   203.6  5022.7  209.48
    5049   208.6  5081.9  208.52  5174.2   218.9  5203.5  226.21  5336.1  232.67
#Mann= 9 ,-1 , 0
  3834.4     .05       0  4172.2     .16       0    4355     .05       0
  4552.4      .1       0  4806.5     .12       0  4998.7     .07       0
  5004.7     .12       0    5049     .16       0  5203.5     .05       0
Bank Sta=4998.7,5004.7
XS Rating Curve= 0 ,0
Exp/Cntr=0.3,0.1

Type RM Length L Ch R = 1 ,1138    ,515,515,515
BEGIN DESCRIPTION:
UNT091 IN ROCK 2.0
END DESCRIPTION:
XS GIS Cut Line= 3
      3644589.96     10144144.83      3645742.11     10144491.64
      3646142.09     10144641.64
#Sta/Elev= 30
  3781.3  261.72  3925.4   253.3  4029.7  248.44  4380.7  236.58  4446.7  230.09
  4622.2  219.03  4655.2  216.29  4665.9  214.47  4688.3  211.83  4693.5  212.11
  4721.3  207.34  4744.3  206.42  4797.7  205.75  4848.8   207.1    4935  206.33
  4962.8  207.39  4974.1  206.31  4994.3  202.68  5005.6  198.37  5016.6  200.18
  5024.6   205.4  5029.9  207.99  5170.5  206.64  5213.5  211.11  5237.3  212.99
    5256  213.78  5311.1  219.59  5371.7  223.93  5396.6  227.56  5411.7   227.9
#Mann= 6 ,-1 , 0
  3781.3     .05       0  4665.9     .05       0  4974.1    .035       0
  5024.6     .05       0  5213.5      .1       0  5237.3     .05       0
Bank Sta=4974.1,5024.6
XS Rating Curve= 0 ,0
Exp/Cntr=0.3,0.1

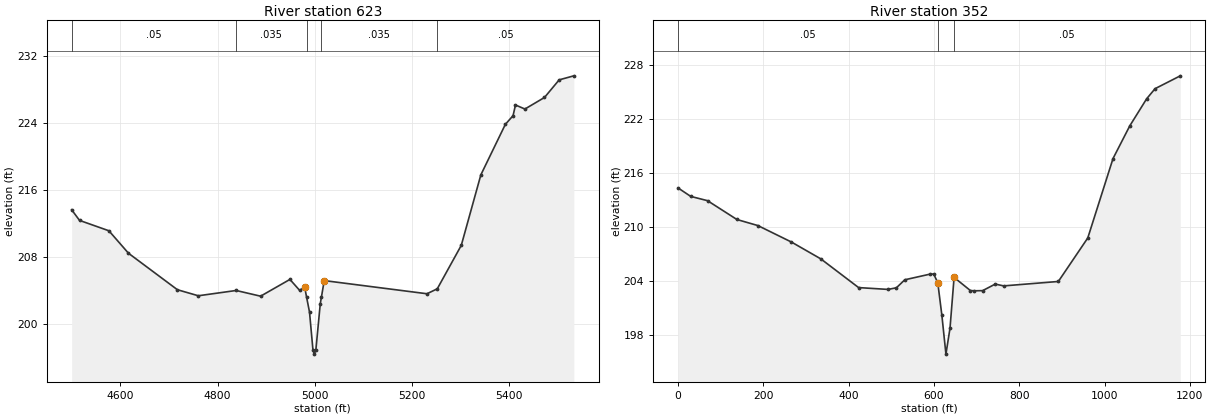
Type RM Length L Ch R = 1 ,623     ,271,271,271
BEGIN DESCRIPTION:
UNT091 IN ROCK 1.0
END DESCRIPTION:
XS GIS Cut Line= 3
      3645225.99      10144905.7      3645852.06     10144981.22
      3646252.04     10144931.23
#Sta/Elev= 30
  4499.7  213.65  4515.9  212.38  4576.4  211.14  4616.7  208.46  4717.4  204.11
  4760.4  203.39  4838.3  204.02  4888.6  203.34    4949  205.34  4969.2  204.02
  4979.3  204.44 4983.23  203.24  4989.3  201.45  4996.4  196.93  4999.2  196.43
  5002.4  196.93  5011.5  202.46 5013.87  203.24  5019.6   205.2  5231.1  203.63
  5252.3  204.22  5301.7   209.4    5342  217.81  5392.4  223.83  5408.3  224.87
  5413.3  226.14  5432.7  225.66    5473  227.04  5503.2  229.14  5533.4  229.62
#Mann= 5 ,-1 , 0
  4499.7     .05       0  4838.3    .035       0 4983.23    .035       0
 5013.87    .035       0  5252.3     .05       0
Bank Sta=4979.3,5019.6
XS Rating Curve= 0 ,0
Exp/Cntr=0.3,0.1

Type RM Length L Ch R = 1 ,352     ,0,0,0
XS GIS Cut Line= 4
     3645159.778    10145046.937     3645697.539    10145207.094
     3645849.882    10145192.771     3646262.643    10144981.833
#Sta/Elev= 30
       0214.354629.53172 213.41968.90736212.9433137.8147210.8492187.0342210.1746
265.7855208.3402334.6929206.4666 423.288203.2736492.1954203.0718511.8832203.2518
 531.571204.1418589.7932204.7612599.3566204.7835608.9201203.8122618.4836200.2032
628.0471195.8719637.6105198.7613 647.174204.4061685.4279202.9424694.9914202.9167
714.1183202.9355743.7057203.6641763.4307203.4624891.6428203.9538960.6801208.7957
1019.855 217.6291059.305221.27681098.755224.2797 1118.48225.40271177.655226.8318
#Mann= 3 , 0 , 0
       0     .05       0608.9201    .035       0 647.174     .05       0
Bank Sta=608.9201,647.174
XS Rating Curve= 0 ,0
Exp/Cntr=0.3,0.1

Chan Stop Cuts=-1
Use User Specified Reach Order=0
Composite Channel Slope=5