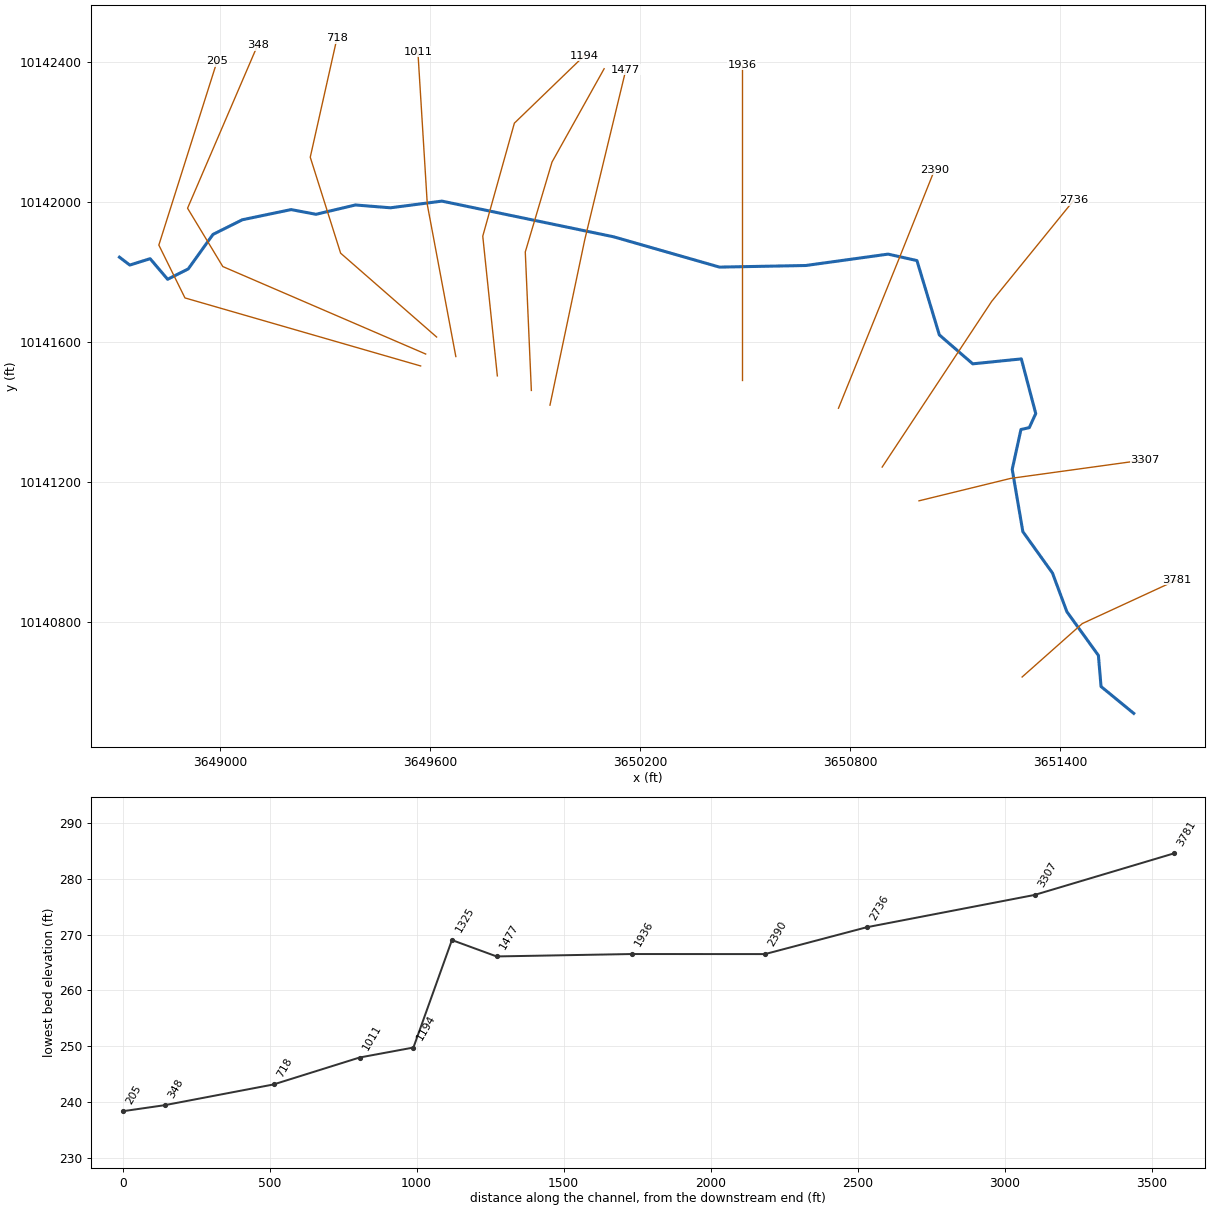
--- UNT092 IN ROCK.prj (project) ---

Proj Title=UNT092 IN ROCK Base Level Engineering
Current Plan=p01
Default Exp/Contr=0.3,0.1
English Units
Geom File=g01
Flow File=f01
Plan File=p01
Y Axis Title=Elevation
X Axis Title(PF)=Main Channel Distance
X Axis Title(XS)=Station
BEGIN DESCRIPTION:
UNT092 IN ROCK
END DESCRIPTION:
DSS Export Rating Curves= 0
DSS Export Rating Curve Sorted= 0
DSS Export Volume Flow Curves= 0
DXF OffsetX= 0
DXF OffsetY= 0
DXF ScaleX= 1
DXF ScaleY= 10

--- UNT092 IN ROCK.p01 (plan) ---

Plan Title=Multiple Run
Short Identifier=Multiple
Geom File=g01
Flow File=f01
Subcritical Flow
K Sum by GR= 0
Std Step Tol= 0.01
Critical Tol= 0.01
Num of Std Step Trials= 20
Max Error Tol= 0.3
Flow Tol Ratio= 0.001
Split Flow NTrial= 30
Split Flow Tol= 0.02
Split Flow Ratio= 0.02
Log Output Level= 0
Friction Slope Method= 1
Unsteady Friction Slope Method= 2
Unsteady Bridges Friction Slope Method= 1
Parabolic Critical Depth
Global Vel Dist=  1 , 1 , 1
Global Log Level= 0
CheckData=True
Encroach Param= -1, 0, 0, 0
BEGIN DESCRIPTION:
Multiple Run
END DESCRIPTION:

--- UNT092 IN ROCK.f01 (steady flow) ---

Flow Title=Multiple
Program Version=4.10
Number of Profiles= 7
Profile Names=10-year,25-year,50-year,1pct_min,100-year,1pct_plu,500-year
River Rch & RM=UNT092 IN ROCK,Reach-1         ,3781
     293     378     445     386     522     705     716
Boundary for River Rch & Prof#=UNT092 IN ROCK,Reach-1         , 1
Up Type= 0
Dn Type= 3
Dn Slope=0.017
Boundary for River Rch & Prof#=UNT092 IN ROCK,Reach-1         , 2
Up Type= 0
Dn Type= 3
Dn Slope=0.017
Boundary for River Rch & Prof#=UNT092 IN ROCK,Reach-1         , 3
Up Type= 0
Dn Type= 3
Dn Slope=0.017
Boundary for River Rch & Prof#=UNT092 IN ROCK,Reach-1         , 4
Up Type= 0
Dn Type= 3
Dn Slope=0.017
Boundary for River Rch & Prof#=UNT092 IN ROCK,Reach-1         , 5
Up Type= 0
Dn Type= 3
Dn Slope=0.017
Boundary for River Rch & Prof#=UNT092 IN ROCK,Reach-1         , 6
Up Type= 0
Dn Type= 3
Dn Slope=0.017
Boundary for River Rch & Prof#=UNT092 IN ROCK,Reach-1         , 7
Up Type= 0
Dn Type= 3
Dn Slope=0.017
DSS Import GetInterval= 0
DSS Import GetPeak= 0
DSS Import FillOption= 0

--- UNT092 IN ROCK.g01 (geometry) ---

Geom Title=Existing Conditions
Program Version=4.10

River Reach=UNT092 IN ROCK  ,Reach-1
Reach XY= 30
      3651611.23      10140537.7      3651517.75     10140614.43
      3651510.15      10140703.4      3651420.09     10140828.19
      3651378.86     10140938.86      3651294.22     10141057.14
      3651263.84     10141235.09       3651288.8     10141349.02
      3651312.67     10141354.44      3651331.11     10141394.59
      3651289.88     10141550.84      3651150.99     10141536.74
      3651055.52     10141619.44      3650991.49     10141831.88
      3650909.02     10141850.32      3650673.56     10141817.77
      3650427.21     10141813.22      3650124.76      10141899.8
      3649633.74     10142001.83      3649486.82     10141982.74
      3649386.66     10141990.78      3649273.85     10141964.14
      3649202.72     10141977.61      3649063.41     10141948.54
      3648979.53     10141906.69      3648908.79       10141808.
      3648849.84     10141778.41      3648799.83     10141837.27
      3648741.74     10141819.06      3648712.11     10141841.64

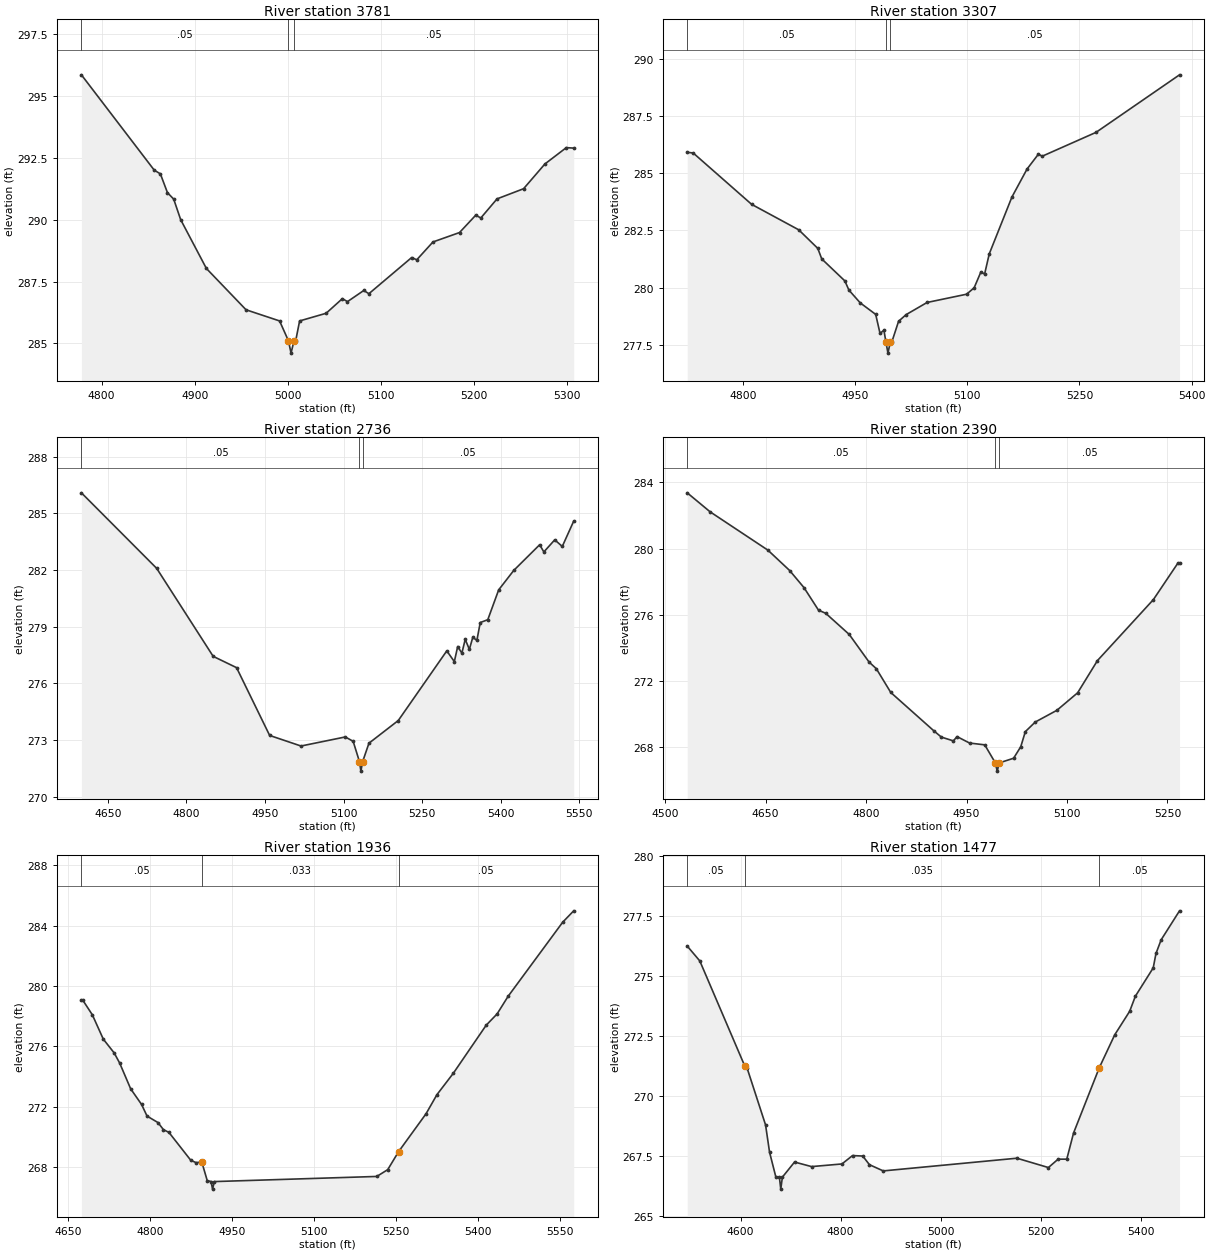
Type RM Length L Ch R = 1 ,3781    ,474,474,474
BEGIN DESCRIPTION:
UNT092 IN ROCK 8.0
END DESCRIPTION:
XS GIS Cut Line= 3
      3651292.14     10140641.67       3651464.2     10140794.39
      3651735.25     10140919.53
#Sta/Elev= 30
  4778.3  295.85  4856.5     292  4863.1  291.85  4870.7  291.09  4877.4  290.83
  4884.9     290  4912.5  288.03  4955.1  286.36  4991.1  285.91  5000.6  285.11
  5003.4  284.61  5006.6  285.11  5008.4  285.11  5012.6  285.91  5041.1  286.22
  5058.5  286.81    5064  286.69  5081.5  287.14    5087  287.01  5132.9  288.47
  5138.4  288.38  5155.8   289.1  5184.3  289.48  5201.7  290.18  5207.2  290.07
  5224.6  290.84  5253.1  291.25    5276  292.25    5299  292.91  5306.9  292.89
#Mann= 3 ,-1 , 0
  4778.3     .05       0  5000.6     .03       0  5006.6     .05       0
Bank Sta=5000.6,5006.6
XS Rating Curve= 0 ,0
Exp/Cntr=0.3,0.1

Type RM Length L Ch R = 1 ,3307    ,571,571,571
BEGIN DESCRIPTION:
UNT092 IN ROCK 7.0
END DESCRIPTION:
XS GIS Cut Line= 3
      3650997.41     10141145.22      3651259.34     10141209.32
      3651644.04     10141262.39
#Sta/Elev= 30
  4725.8  285.91  4733.8  285.88  4811.9  283.64  4874.8  282.53  4900.3  281.72
  4905.6  281.26  4936.5   280.3  4941.9   279.9  4957.1  279.34  4977.7  278.84
  4983.5  278.01  4988.7  278.15  4991.3  277.65  4994.1  277.15  4997.3  277.65
  4999.4  277.65  5008.3  278.54  5018.4  278.83  5046.4  279.36  5099.2  279.72
  5109.3     280  5118.3  280.69  5123.3   280.6  5129.5  281.48  5159.8  283.96
    5180  285.18  5195.2  285.83  5200.3  285.74  5272.2  286.78  5383.8  289.29
#Mann= 3 ,-1 , 0
  4725.8     .05       0  4991.3     .03       0  4997.3     .05       0
Bank Sta=4991.3,4997.3
XS Rating Curve= 0 ,0
Exp/Cntr=0.3,0.1

Type RM Length L Ch R = 1 ,2736    ,346,346,346
BEGIN DESCRIPTION:
UNT092 IN ROCK 6.0
END DESCRIPTION:
XS GIS Cut Line= 3
      3650892.11     10141241.66      3651205.13     10141715.25
      3651440.07     10142004.59
#Sta/Elev= 30
  4599.3  286.09  4743.1  282.09    4851  277.43  4895.7  276.83  4958.9  273.24
  5018.8  272.68  5103.4  273.16  5118.4  272.93  5130.5  271.85  5133.2  271.35
  5136.5  271.85  5148.6  272.83  5204.6  274.03  5297.3  277.72  5311.7  277.15
  5318.1  277.95  5326.1   277.6  5332.5  278.33  5340.4   277.8  5346.9  278.43
  5354.8  278.28  5361.2  279.22  5375.6  279.37  5396.4  280.95  5425.2  281.98
  5474.7  283.34  5482.7  282.96  5503.5   283.6  5517.9  283.25  5539.7  284.59
#Mann= 3 ,-1 , 0
  4599.3     .05       0  5130.5     .03       0  5136.5     .05       0
Bank Sta=5130.5,5136.5
XS Rating Curve= 0 ,0
Exp/Cntr=0.3,0.1

Type RM Length L Ch R = 1 ,2390    ,454,454,454
BEGIN DESCRIPTION:
UNT092 IN ROCK 5.0
END DESCRIPTION:
XS GIS Cut Line= 3
      3650767.32     10141409.95      3650942.11     10141841.64
      3651042.11     10142091.65
#Sta/Elev= 30
    4533  283.37  4567.2  282.22  4653.5   279.9  4685.9  278.67  4707.4  277.63
    4729  276.27  4739.8  276.08  4774.9   274.8  4804.5  273.13  4815.3  272.73
  4836.9  271.29  4900.9  268.98  4912.4  268.59  4930.4  268.36  4935.8  268.62
  4954.5  268.23  4977.2  268.12    4993  267.03  4995.8  266.53    4999  267.03
  5020.3  267.31    5031  268.01  5037.8  268.92  5052.6   269.5  5084.9  270.21
  5115.9  271.27  5145.5  273.22    5229  276.91  5265.3   279.1    5268   279.1
#Mann= 3 ,-1 , 0
    4533     .05       0    4993     .03       0    4999     .05       0
Bank Sta=4993,4999
XS Rating Curve= 0 ,0
Exp/Cntr=0.3,0.1

Type RM Length L Ch R = 1 ,1936    ,459,459,459
BEGIN DESCRIPTION:
UNT092 IN ROCK 4.0
END DESCRIPTION:
XS GIS Cut Line= 3
      3650492.11     10141491.63      3650492.11     10141791.64
      3650492.11     10142391.63
#Sta/Elev= 30
  4674.7  279.06  4677.2  279.06  4694.7  278.09  4714.7  276.48  4734.7  275.56
  4744.7  274.89  4764.7  273.19  4784.7  272.15  4794.7  271.38  4814.7  270.95
  4824.7  270.48  4834.7   270.3  4874.7  268.45  4884.7  268.29  4894.7  268.35
  4904.7  267.11  4911.7  267.04  4914.5  266.54  4917.7  267.04  5214.7  267.38
  5234.7  267.83  5254.7  269.03  5304.7  271.53  5324.7   272.8  5354.7  274.22
  5414.7   277.4  5434.7  278.15  5454.7  279.31  5554.7  284.23  5574.7  284.98
#Mann= 3 , 0 , 0
  4674.7     .05       0  4894.7    .033       0  5254.7     .05       0
Bank Sta=4894.7,5254.7
XS Rating Curve= 0 ,0
Exp/Cntr=0.3,0.1

Type RM Length L Ch R = 1 ,1477    ,152,152,152
BEGIN DESCRIPTION:
UNT092 IN ROCK 3.0
END DESCRIPTION:
XS GIS Cut Line= 3
      3649942.67     10141418.62      3650042.11     10141891.64
      3650159.56     10142377.28
#Sta/Elev= 30
  4493.6  276.25  4518.7  275.63  4608.2  271.26  4613.3  271.15    4650  268.79
    4658  267.65  4670.4  266.63  4677.6  266.61  4680.4  266.11  4683.6  266.61
  4707.9  267.24  4741.9  267.05  4802.5  267.16  4823.7  267.51  4844.1  267.49
  4857.4  267.13    4885  266.87  5151.9   267.4  5214.8  267.01  5234.2  267.36
  5251.5  267.36    5265  268.45  5316.5  271.18  5347.3  272.55  5377.1  273.53
  5388.5  274.16  5424.1  275.34  5429.6  275.94  5439.9  276.51  5476.6  277.72
#Mann= 3 , 0 , 0
  4493.6     .05       0  4608.2    .035       0  5316.5     .05       0
Bank Sta=4608.2,5316.5
XS Rating Curve= 0 ,0
Exp/Cntr=0.3,0.1

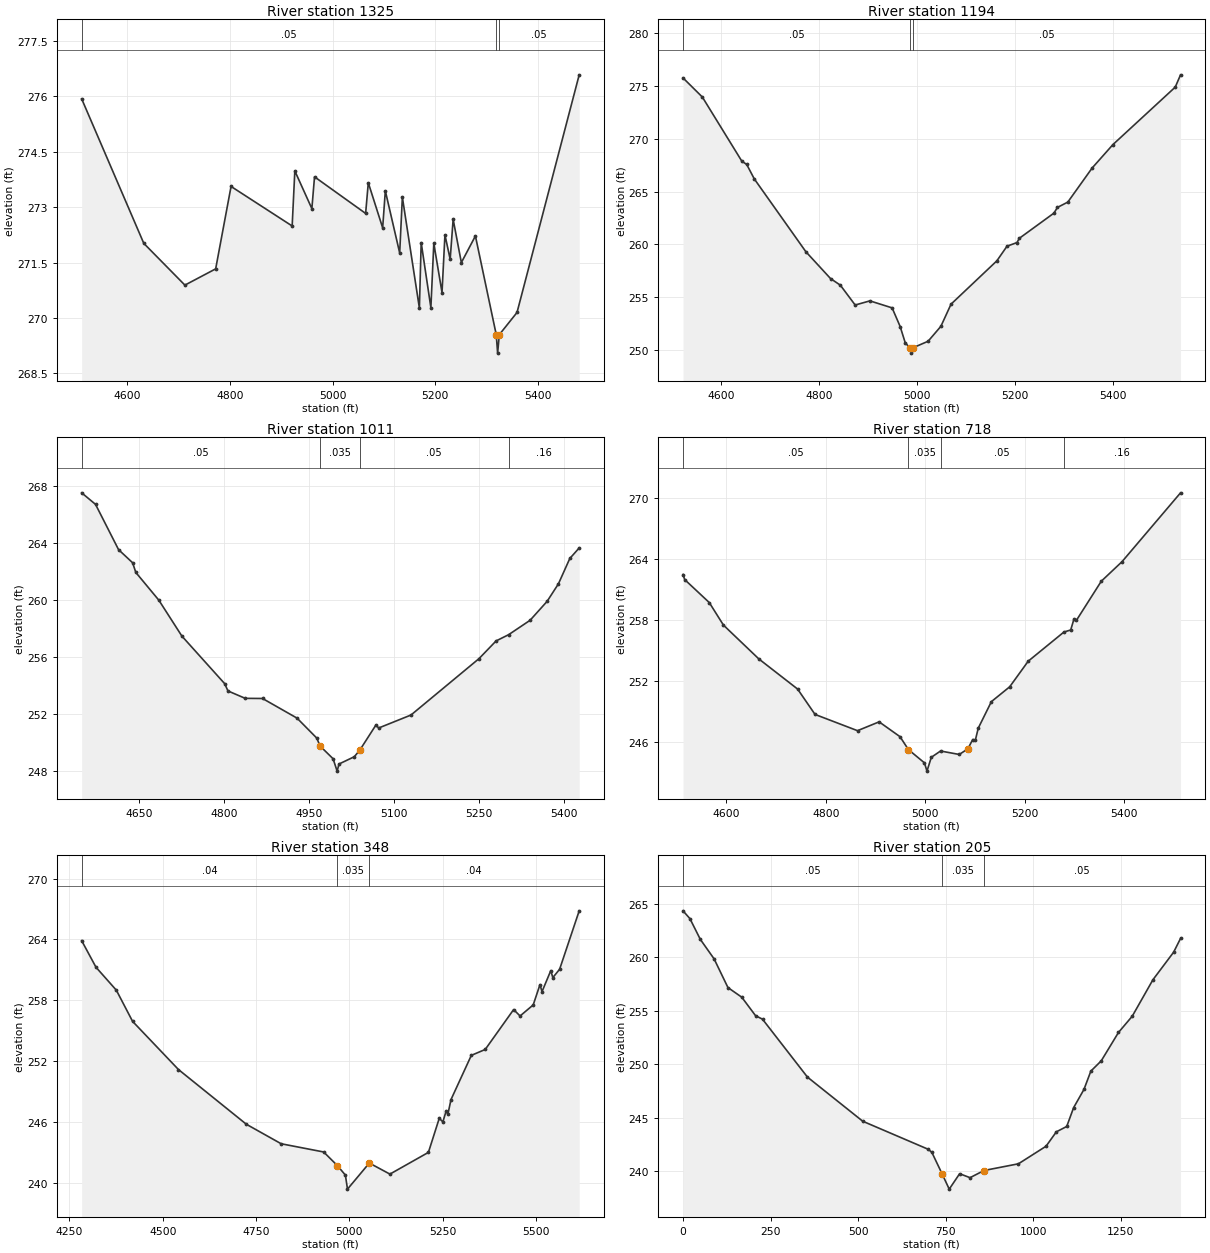
Type RM Length L Ch R = 1 ,1325    ,131,131,131
BEGIN DESCRIPTION:
Mapping XS 017f44d0
END DESCRIPTION:
XS GIS Cut Line= 4
      3649889.46     10141460.68       3649872.1     10141856.49
      3649948.49     10142113.43      3650097.46      10142380.2
#Sta/Elev= 30
  4510.9  275.93    4632  272.02  4712.1  270.89  4772.1  271.33  4802.1  273.56
  4921.2  272.49  4926.4  273.98  4959.6  272.96  4964.8  273.82  5064.4  272.83
  5069.6  273.66  5097.6  272.44  5102.8  273.44  5130.8  271.76    5136  273.27
  5169.2  270.27  5172.7  272.04  5191.6  270.28  5197.3  272.02  5213.3  270.69
    5219  272.25  5229.2  271.59    5235  272.67    5251   271.5  5278.4  272.22
    5319  269.55  5321.7  269.05    5325  269.55  5359.5  270.15  5480.7  276.58
#Mann= 3 ,-1 , 0
  4510.9     .05       0    5319     .03       0    5325     .05       0
Bank Sta=5319,5325
XS Rating Curve= 0 ,0
Exp/Cntr=0.3,0.1

Type RM Length L Ch R = 1 ,1194    ,183,183,183
BEGIN DESCRIPTION:
Mapping XS fd6e2e6f
END DESCRIPTION:
XS GIS Cut Line= 4
      3649792.23     10141502.36      3649750.57     10141901.63
      3649840.85     10142224.55      3650041.03     10142417.83
#Sta/Elev= 30
  4522.1  275.72  4561.6  273.91    4642  267.87  4652.1  267.55  4667.5  266.19
  4772.7  259.32    4823  256.79  4843.1  256.16  4873.3  254.29  4903.4  254.68
  4948.7  254.02  4965.1  252.26  4975.5  250.72    4985  250.25  4987.7  249.75
    4991  250.25  5022.1  250.87  5048.2  252.28  5068.9  254.37  5162.4  258.46
  5183.1  259.84  5203.3  260.18  5208.4  260.59  5278.8  262.96    5286   263.5
  5307.1     264  5356.8  267.22  5399.2  269.43  5526.3  274.85  5537.1  276.01
#Mann= 3 ,-1 , 0
  4522.1     .05       0    4985     .03       0    4991     .05       0
Bank Sta=4985,4991
XS Rating Curve= 0 ,0
Exp/Cntr=0.3,0.1

Type RM Length L Ch R = 1 ,1011    ,293,293,293
BEGIN DESCRIPTION:
UNT092 IN ROCK 2.0
END DESCRIPTION:
XS GIS Cut Line= 3
      3649673.58     10141557.57      3649592.11     10141991.64
      3649565.18     10142428.26
#Sta/Elev= 30
  4548.1   267.5  4572.6  266.69  4613.3  263.51  4638.1  262.59  4643.8  261.91
  4684.5  259.96  4725.2  257.44  4800.8   254.1  4806.6  253.59  4837.1  253.07
  4867.7  253.06  4928.7  251.68  4963.5  250.28  4969.4  249.72  4992.3  248.83
  4999.5  247.96  5002.8  248.46  5029.8  248.97  5039.8  249.45  5067.9  251.19
    5073  250.99    5130   251.9  5250.2  255.86  5280.3   257.1  5302.5  257.54
  5340.4  258.55  5370.5  259.88  5390.5  261.11  5410.6  262.89  5427.2  263.63
#Mann= 4 ,-1 , 0
  4548.1     .05       0  4969.4    .035       0  5039.8     .05       0
  5302.5     .16       0
Bank Sta=4969.4,5039.8
XS Rating Curve= 0 ,0
Exp/Cntr=0.3,0.1

Type RM Length L Ch R = 1 ,718     ,370,370,370
BEGIN DESCRIPTION:
Mapping XS 2b384cbe
END DESCRIPTION:
XS GIS Cut Line= 4
      3649618.61     10141613.45      3649344.32     10141853.02
      3649257.51     10142127.32      3649333.79     10142467.08
#Sta/Elev= 30
  4512.7  262.47  4516.1  261.97  4565.5  259.71    4594  257.49  4665.2  254.16
    4743   251.2  4778.1   248.7  4863.5   247.1  4906.9  247.97  4948.9  246.51
  4965.8  245.24  4998.1  243.93  5003.1  243.12  5011.8  244.48  5030.4   245.1
    5068  244.76  5085.2  245.31  5095.1  246.23  5100.3  246.16  5106.2  247.35
  5132.6  249.96  5169.4  251.42  5206.6  253.94  5278.4  256.81    5292  257.01
  5298.4  258.06  5303.5  257.96  5353.5  261.81  5395.3  263.74  5512.8  270.51
#Mann= 4 ,-1 , 0
  4512.7     .05       0  4965.8    .035       0  5030.4     .05       0
  5278.4     .16       0
Bank Sta=4965.8,5085.2
XS Rating Curve= 0 ,0
Exp/Cntr=0.3,0.1

Type RM Length L Ch R = 1 ,348     ,143,143,143
BEGIN DESCRIPTION:
UNT092 IN ROCK 1.0
END DESCRIPTION:
XS GIS Cut Line= 4
      3649587.37     10141564.83      3649007.51     10141814.82
      3648906.82     10141981.49      3649106.88     10142447.16
#Sta/Elev= 30
  4282.9  263.88  4321.3  261.26  4375.8     259  4419.3  255.93  4542.3  251.18
  4724.2  245.79  4817.4  243.87  4931.3  243.06  4968.2  241.71  4989.5  240.78
  4995.1   239.4  5053.6  241.97  5108.8  240.88  5211.9  243.02  5240.9  246.37
  5250.7  246.03    5259  247.05  5264.4  246.84  5272.5  248.23  5326.9  252.58
  5364.1  253.16  5440.2  257.09  5457.5  256.46  5492.7  257.55  5510.8  259.55
  5516.3  258.86  5539.8  260.93  5545.2  260.24  5563.4  261.06  5615.9  266.82
#Mann= 3 , 0 , 0
  4282.9     .04       0  4968.2    .035       0  5053.6     .04       0
Bank Sta=4968.2,5053.6
XS Rating Curve= 0 ,0
Exp/Cntr=0.3,0.1

Type RM Length L Ch R = 1 ,205     ,0,0,0
XS GIS Cut Line= 4
     3649573.008    10141530.684     3648899.396    10141725.128
     3648824.744     10141876.173648991.4099631310142402.2118836
#Sta/Elev= 30
       0 264.34819.74969263.618349.37421261.682288.87358259.8505 128.373 257.169
167.8723256.2667207.3717 254.534227.1214254.2112355.4943248.7933513.4918244.6632
701.1138242.0318711.0246241.7461 740.757239.7028760.5785238.3119790.3109239.7535
820.0432 239.383859.6863240.0523958.2814240.68131037.112242.32441066.673243.6742
1096.235244.17231115.942245.93341145.504247.64021165.211249.35371194.773250.3084
1244.042 252.9661283.457254.4904 1342.58257.90291401.703260.4801 1421.41 261.765
#Mann= 3 , 0 , 0
       0     .05       0 740.757    .035       0859.6863     .05       0
Bank Sta=740.757,859.6863
XS Rating Curve= 0 ,0
Exp/Cntr=0.3,0.1

Chan Stop Cuts=-1
Use User Specified Reach Order=0
Composite Channel Slope=5