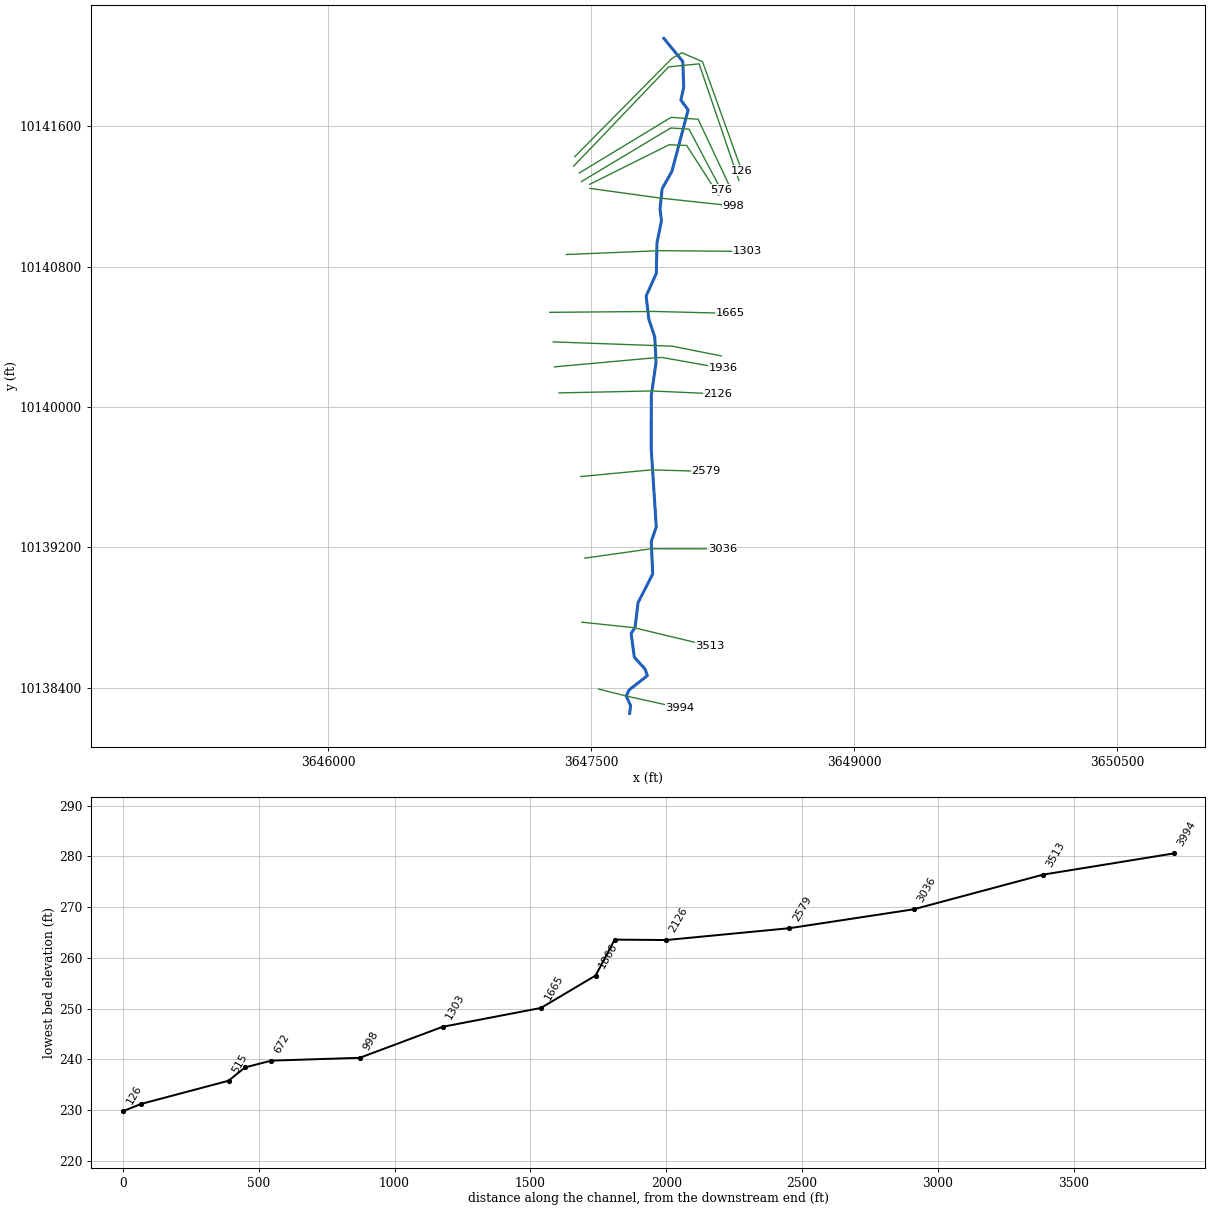
--- UNT093 IN ROCK.prj (project) ---

Proj Title=UNT093 IN ROCK Base Level Engineering
Current Plan=p01
Default Exp/Contr=0.3,0.1
English Units
Geom File=g01
Flow File=f01
Plan File=p01
Y Axis Title=Elevation
X Axis Title(PF)=Main Channel Distance
X Axis Title(XS)=Station
BEGIN DESCRIPTION:
UNT093 IN ROCK
END DESCRIPTION:
DSS Export Rating Curves= 0
DSS Export Rating Curve Sorted= 0
DSS Export Volume Flow Curves= 0
DXF OffsetX= 0
DXF OffsetY= 0
DXF ScaleX= 1
DXF ScaleY= 10

--- UNT093 IN ROCK.p01 (plan) ---

Plan Title=Multiple Run
Short Identifier=Multiple
Geom File=g01
Flow File=f01
Subcritical Flow
K Sum by GR= 0
Std Step Tol= 0.01
Critical Tol= 0.01
Num of Std Step Trials= 20
Max Error Tol= 0.3
Flow Tol Ratio= 0.001
Split Flow NTrial= 30
Split Flow Tol= 0.02
Split Flow Ratio= 0.02
Log Output Level= 0
Friction Slope Method= 1
Unsteady Friction Slope Method= 2
Unsteady Bridges Friction Slope Method= 1
Parabolic Critical Depth
Global Vel Dist=  1 , 1 , 1
Global Log Level= 0
CheckData=True
Encroach Param= -1, 0, 0, 0
BEGIN DESCRIPTION:
Multiple Run
END DESCRIPTION:

--- UNT093 IN ROCK.f01 (steady flow) ---

Flow Title=Multiple
Program Version=4.10
Number of Profiles= 7
Profile Names=10-year,25-year,50-year,1pct_min,100-year,1pct_plu,500-year
River Rch & RM=UNT093 IN ROCK,Reach-1         ,3994
     312     405     478     416     562     761     777
Boundary for River Rch & Prof#=UNT093 IN ROCK,Reach-1         , 1
Up Type= 0
Dn Type= 3
Dn Slope=0.015
Boundary for River Rch & Prof#=UNT093 IN ROCK,Reach-1         , 2
Up Type= 0
Dn Type= 3
Dn Slope=0.015
Boundary for River Rch & Prof#=UNT093 IN ROCK,Reach-1         , 3
Up Type= 0
Dn Type= 3
Dn Slope=0.015
Boundary for River Rch & Prof#=UNT093 IN ROCK,Reach-1         , 4
Up Type= 0
Dn Type= 3
Dn Slope=0.015
Boundary for River Rch & Prof#=UNT093 IN ROCK,Reach-1         , 5
Up Type= 0
Dn Type= 3
Dn Slope=0.015
Boundary for River Rch & Prof#=UNT093 IN ROCK,Reach-1         , 6
Up Type= 0
Dn Type= 3
Dn Slope=0.015
Boundary for River Rch & Prof#=UNT093 IN ROCK,Reach-1         , 7
Up Type= 0
Dn Type= 3
Dn Slope=0.015
DSS Import GetInterval= 0
DSS Import GetPeak= 0
DSS Import FillOption= 0

--- UNT093 IN ROCK.g01 (geometry) ---

Geom Title=Existing Conditions
Program Version=4.10

River Reach=UNT093 IN ROCK  ,Reach-1
Reach XY= 30
      3647719.03     10138252.84      3647724.44     10138297.09
       3647699.5      10138351.8      3647716.43     10138386.95
      3647819.65     10138467.71      3647807.73     10138504.29
      3647745.74     10138573.14      3647727.25     10138707.93
      3647749.85     10138743.31      3647767.04     10138884.49
      3647850.35     10139047.38      3647842.29     10139232.66
      3647870.73     10139316.56      3647841.97     10139761.59
       3647842.6     10140066.85      3647869.39     10140254.29
      3647862.44     10140398.38      3647828.59     10140499.95
      3647812.96     10140632.76      3647871.04     10140762.08
      3647874.92     10140936.14      3647900.37     10141061.99
      3647892.12     10141131.55      3647904.45     10141245.67
      3647959.51     10141342.77      3648052.54     10141694.39
      3648010.88     10141750.81      3648027.37     10141821.13
      3648022.16     10141970.43      3647913.88     10142102.58

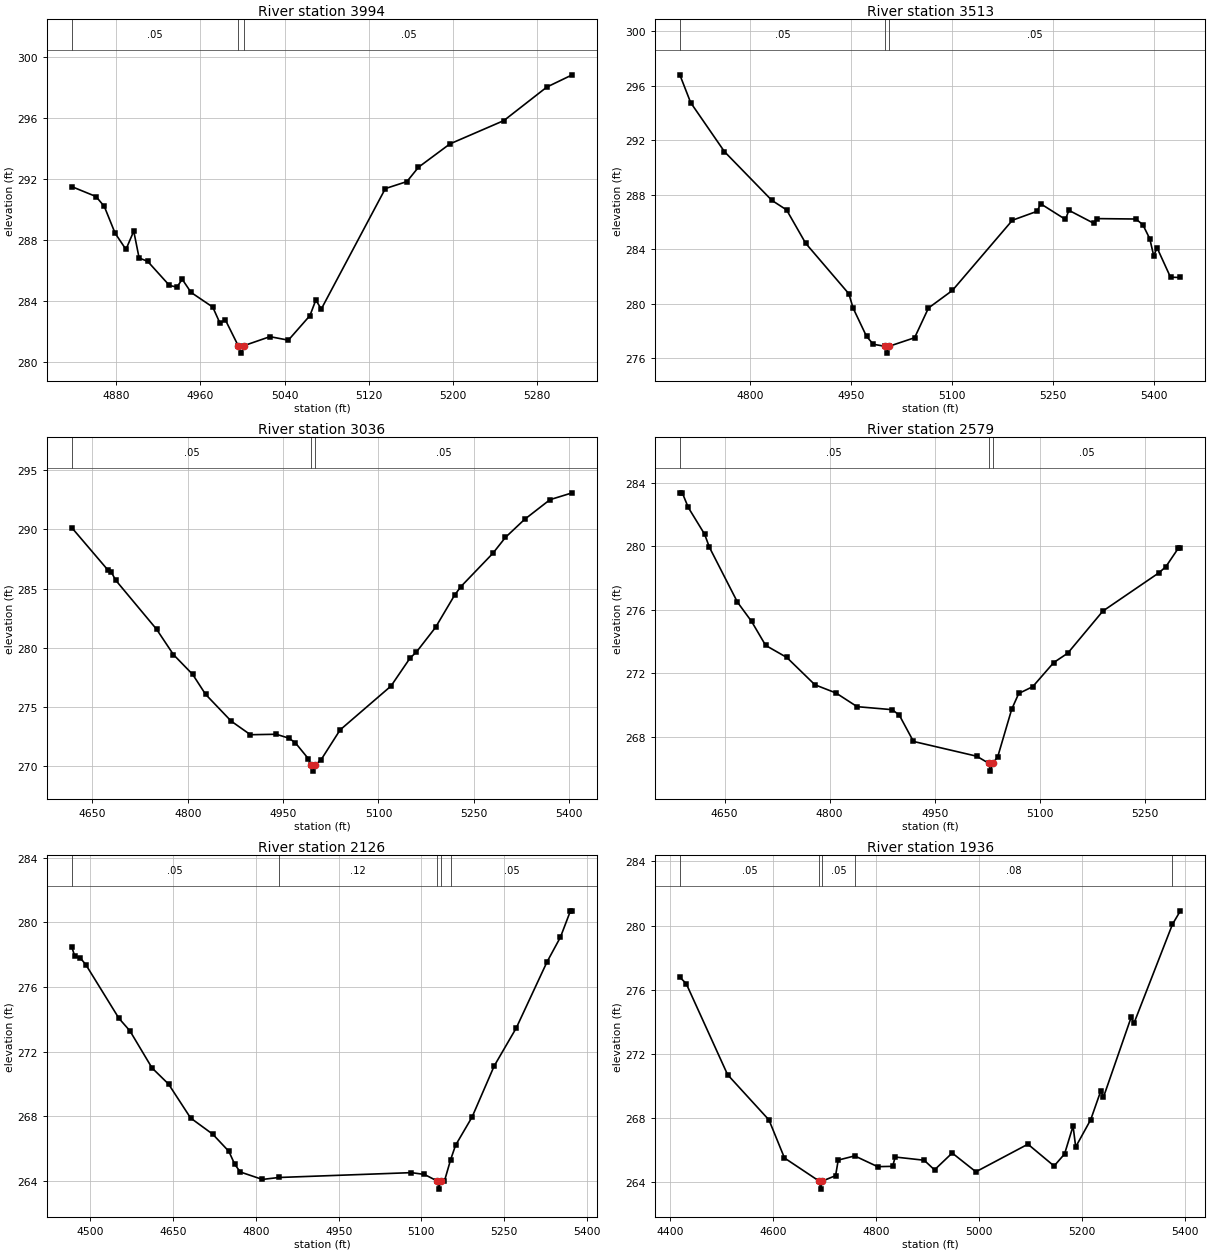
Type RM Length L Ch R = 1 ,3994    ,481,481,481
BEGIN DESCRIPTION:
UNT093 IN ROCK 9.0
END DESCRIPTION:
XS GIS Cut Line= 3
      3647542.07     10138391.65       3647699.5      10138351.8
      3648005.62     10138284.16
#Sta/Elev= 30
  4837.6  291.49  4860.7  290.84  4868.6  290.19  4878.9  288.43  4889.2  287.37
  4896.6  288.57  4901.7  286.81  4909.8  286.59  4930.5  285.01  4937.6   284.9
  4942.7  285.41  4951.1  284.55  4971.7  283.59  4978.6  282.53  4983.7  282.75
  4995.8  281.07  4998.5  280.57  5001.8  281.07  5026.1  281.65  5043.6  281.42
  5064.1  283.03  5069.7  284.05  5074.9  283.46  5135.8  291.36  5156.3  291.82
  5167.3  292.76  5197.2  294.29  5248.5  295.82  5289.4  298.02  5313.5  298.82
#Mann= 3 ,-1 , 0
  4837.6     .05       0  4995.8     .03       0  5001.8     .05       0
Bank Sta=4995.8,5001.8
XS Rating Curve= 0 ,0
Exp/Cntr=0.3,0.1

Type RM Length L Ch R = 1 ,3513    ,477,477,477
BEGIN DESCRIPTION:
UNT093 IN ROCK 8.0
END DESCRIPTION:
XS GIS Cut Line= 3
      3647446.05     10138773.01      3647742.11     10138741.64
      3648176.39     10138637.55
#Sta/Elev= 30
  4695.4  296.81  4711.5  294.77  4761.8  291.17  4832.2   287.6  4854.1   286.9
  4882.5  284.45  4946.8  280.74  4952.9  279.71    4973  277.62  4983.1  277.04
  5000.4  276.89  5003.1  276.39  5006.4  276.89  5044.5  277.52  5065.1   279.7
  5100.7  280.99  5189.9  286.14  5226.8   286.8  5231.9  287.35  5268.8   286.2
  5273.9  286.87  5310.8  285.92    5316  286.26  5373.6  286.23  5383.9  285.81
  5394.2  284.78    5400  283.54  5405.1  284.11    5425  281.96  5439.7  281.94
#Mann= 3 ,-1 , 0
  4695.4     .05       0  5000.4     .03       0  5006.4     .05       0
Bank Sta=5000.4,5006.4
XS Rating Curve= 0 ,0
Exp/Cntr=0.3,0.1

Type RM Length L Ch R = 1 ,3036    ,457,457,457
BEGIN DESCRIPTION:
UNT093 IN ROCK 7.0
END DESCRIPTION:
XS GIS Cut Line= 3
      3647463.73     10139138.17      3647842.11     10139191.64
      3648247.07     10139191.18
#Sta/Elev= 30
  4617.6  290.16  4674.8  286.55  4679.9  286.39  4686.7  285.71    4751  281.56
  4777.6  279.41  4807.9  277.73  4828.1  276.05  4868.4  273.78  4898.7  272.63
  4939.1  272.67  4959.2  272.34  4969.4  271.94  4989.6  270.61  4994.2  270.05
    4997  269.55  5000.2  270.05  5009.7  270.51  5039.7  273.04  5119.7  276.75
  5149.7  279.12  5159.7  279.63  5189.7  281.71  5219.7  284.44  5229.7  285.17
  5279.7  287.97  5299.7  289.33  5329.7  290.85  5369.7  292.52  5404.7   293.1
#Mann= 3 ,-1 , 0
  4617.6     .05       0  4994.2     .03       0  5000.2     .05       0
Bank Sta=4994.2,5000.2
XS Rating Curve= 0 ,0
Exp/Cntr=0.3,0.1

Type RM Length L Ch R = 1 ,2579    ,453,453,453
BEGIN DESCRIPTION:
UNT093 IN ROCK 6.0
END DESCRIPTION:
XS GIS Cut Line= 3
      3647440.14     10139603.46      3647842.11     10139641.64
       3648152.8     10139632.91
#Sta/Elev= 30
  4586.1  283.36  4589.6  283.36  4598.1  282.44  4621.5  280.75  4628.3  279.93
  4668.4  276.47  4688.5  275.26  4708.6  273.75  4738.8  272.99  4778.9  271.27
  4809.1  270.75  4839.2  269.89  4889.4   269.7  4899.5  269.35  4919.6   267.7
  5009.9  266.77  5026.9  266.33  5029.6  265.83  5032.9  266.33  5039.9  266.73
  5059.9  269.73  5069.9  270.72  5089.9  271.15  5119.9  272.67  5139.9  273.26
    5190  275.91    5270  278.32    5280  278.71  5297.9  279.88  5300.7  279.88
#Mann= 3 ,-1 , 0
  4586.1     .05       0  5026.9     .03       0  5032.9     .05       0
Bank Sta=5026.9,5032.9
XS Rating Curve= 0 ,0
Exp/Cntr=0.3,0.1

Type RM Length L Ch R = 1 ,2126    ,190,190,190
BEGIN DESCRIPTION:
UNT093 IN ROCK 5.0
END DESCRIPTION:
XS GIS Cut Line= 3
      3647316.51     10140080.53      3647842.11     10140091.64
      3648223.51     10140074.64
#Sta/Elev= 30
    4466   278.5  4471.6  277.91  4481.6   277.8  4491.6  277.39  4551.6  274.07
  4571.6  273.29  4611.6     271  4641.6     270  4681.6   267.9  4721.7   266.9
  4750.9  265.84  4761.7  265.03  4771.7  264.56  4811.7   264.1  4841.5  264.22
  5081.8  264.52  5105.4  264.41  5128.9     264  5131.6   263.5  5134.9     264
  5141.9  264.01  5152.9  265.31  5161.9  266.21  5191.9  267.96    5232  271.12
    5272  273.47  5327.8  277.56  5352.1  279.09  5370.3  280.72  5373.5  280.72
#Mann= 5 ,-1 , 0
    4466     .05       0  4841.5     .12       0  5128.9     .07       0
  5134.9     .12       0  5152.9     .05       0
Bank Sta=5128.9,5134.9
XS Rating Curve= 0 ,0
Exp/Cntr=0.3,0.1

Type RM Length L Ch R = 1 ,1936    ,70,70,70
BEGIN DESCRIPTION:
Mapping XS 511b8a74
END DESCRIPTION:
XS GIS Cut Line= 4
      3647289.82     10140229.01      3647826.31     10140277.63
       3647902.7     10140282.83      3648253.42     10140220.33
#Sta/Elev= 30
  4419.4  276.78  4431.7  276.39  4512.1  270.71  4592.4  267.89  4622.5  265.52
  4689.8  264.08  4692.6  263.58  4695.8  264.08  4721.7  264.42  4726.8  265.39
  4758.8  265.65  4803.3  264.98  4832.4     265  4837.4  265.58  4893.6  265.38
  4913.7  264.78    4948  265.83    4994  264.66    5095  266.38  5145.8  265.02
  5166.1  265.77  5182.6  267.51  5187.7  266.21  5216.9  267.91  5236.5  269.71
  5241.6  269.31  5295.5   274.3  5300.6   273.9  5375.5  280.08  5390.9  280.92
#Mann= 5 ,-1 , 0
  4419.4     .05       0  4689.8     .07       0  4695.8     .05       0
  4758.8     .08       0  5375.5     .05       0
Bank Sta=4689.8,4695.8
XS Rating Curve= 0 ,0
Exp/Cntr=0.3,0.1

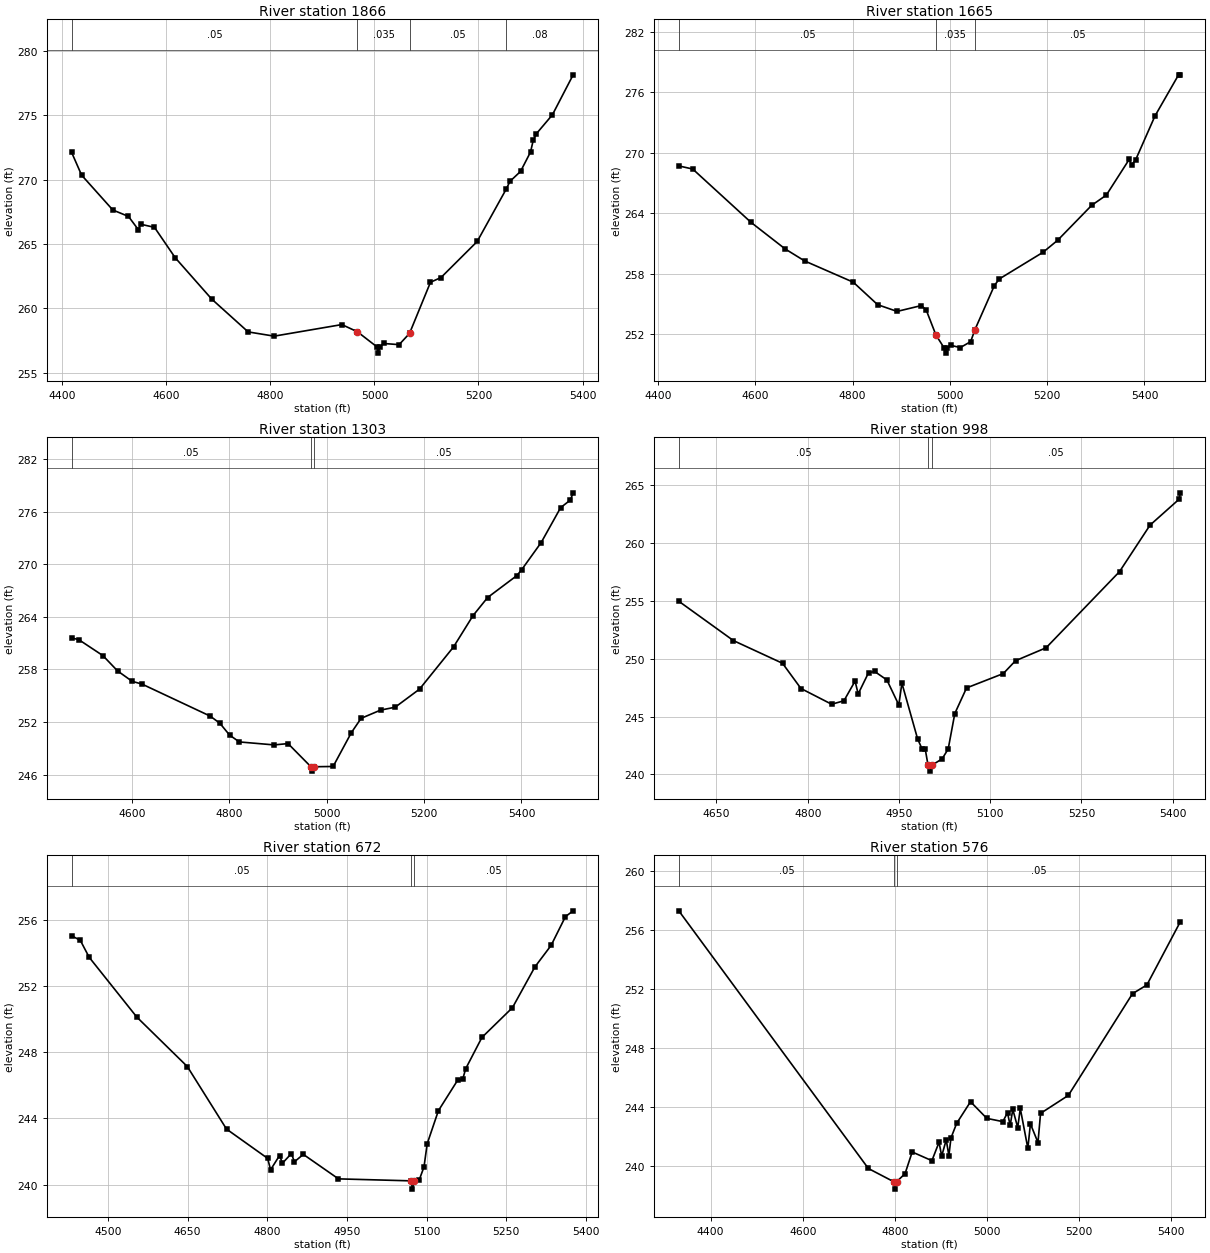
Type RM Length L Ch R = 1 ,1866    ,201,201,201
BEGIN DESCRIPTION:
Mapping XS 52f38d2a
END DESCRIPTION:
XS GIS Cut Line= 3
      3647282.92     10140371.38      3647959.99     10140347.07
      3648241.25     10140291.51
#Sta/Elev= 30
  4417.8  272.12    4437  270.35    4497  267.64  4527.1  267.14  4545.9  266.12
  4550.9  266.53  4577.1  266.29  4617.1  263.92  4687.2  260.71  4757.2  258.16
  4807.2  257.83  4937.3  258.73  4967.3  258.17  5004.4  257.01  5007.1  256.51
  5010.4  257.01  5017.4  257.26  5047.4  257.17  5067.4  258.04  5107.7  262.02
    5128  262.39  5197.5  265.19    5253  269.24  5260.6  269.87  5280.9  270.64
  5300.1  272.15  5305.2  273.05  5311.5  273.58  5342.1  275.04    5382  278.15
#Mann= 4 ,-1 , 0
  4417.8     .05       0  4967.3    .035       0  5067.4     .05       0
    5253     .08       0
#XS Ineff= 2 , 0
          4937.5  258.72
Permanent Ineff=
       F       F
Bank Sta=4967.3,5067.4
XS Rating Curve= 0 ,0
Exp/Cntr=0.3,0.1

Type RM Length L Ch R = 1 ,1665    ,362,362,362
BEGIN DESCRIPTION:
UNT093 IN ROCK 4.0
END DESCRIPTION:
XS GIS Cut Line= 3
      3647263.48     10140539.93      3647859.67     10140544.99
      3648294.22     10140534.04
#Sta/Elev= 30
  4442.8   268.7  4471.4  268.39  4591.4  263.09  4661.4  260.46  4701.4  259.27
  4801.4  257.16  4851.4  254.93  4891.4  254.26  4941.4  254.84  4951.4  254.39
  4971.4  251.91  4988.4  250.62  4991.2  250.12  4994.4  250.62  5001.4   250.9
  5021.4  250.67  5042.7  251.26  5051.4  252.44  5091.5  256.83  5101.5  257.48
  5191.5  260.13  5221.5  261.32  5291.5  264.79  5321.5   265.8  5368.5  269.34
  5373.5   268.8  5381.6  269.28  5421.6  273.66  5470.1  277.74  5473.7  277.74
#Mann= 3 , 0 , 0
  4442.8     .05       0  4971.4    .035       0  5051.4     .05       0
Bank Sta=4971.4,5051.4
XS Rating Curve= 0 ,0
Exp/Cntr=0.3,0.1

Type RM Length L Ch R = 1 ,1303    ,305,305,305
BEGIN DESCRIPTION:
UNT093 IN ROCK 3.0
END DESCRIPTION:
XS GIS Cut Line= 3
      3647357.77     10140869.76      3647892.11     10140891.64
      3648387.81     10140887.43
#Sta/Elev= 30
  4475.7  261.58    4490  261.41  4540.1  259.57  4570.1  257.83  4600.1  256.64
  4620.2  256.33  4760.3  252.68  4780.3  251.86  4800.3  250.51  4820.3  249.73
  4891.8  249.39  4920.4  249.54  4967.4   246.9  4970.2   246.4  4973.4   246.9
    5013  246.93  5050.5  250.79  5070.5  252.42  5110.5  253.36  5140.5  253.69
  5190.5  255.75  5260.5  260.57  5300.5  264.14  5330.5   266.2  5390.5   268.7
  5400.5  269.38  5440.5  272.47  5480.5  276.45  5500.5  277.32  5506.2  278.14
#Mann= 3 ,-1 , 0
  4475.7     .05       0  4967.4     .03       0  4973.4     .05       0
Bank Sta=4967.4,4973.4
XS Rating Curve= 0 ,0
Exp/Cntr=0.3,0.1

Type RM Length L Ch R = 1 ,998     ,326,326,326
BEGIN DESCRIPTION:
UNT093 IN ROCK 2.0
END DESCRIPTION:
XS GIS Cut Line= 3
      3647493.17      10141246.7      3647892.11     10141191.64
      3648311.58      10141146.6
#Sta/Elev= 30
  4588.1  254.97  4677.9  251.57  4758.6  249.61  4788.9  247.43  4839.4  246.07
  4859.6  246.37  4877.9  248.07    4883  246.96    4900  248.79  4910.1   248.9
  4930.2  248.17  4949.8  246.01  4954.9  247.89  4980.7  243.08  4988.3  242.18
  4993.3  242.18  4997.9  240.79  5000.6  240.29  5003.9  240.79    5021  241.35
    5031   242.2  5041.9  245.27  5061.2  247.48  5121.6  248.72  5141.7  249.83
    5192  250.95  5312.7  257.53  5362.9  261.55  5410.3  263.77  5412.7  264.34
#Mann= 3 ,-1 , 0
  4588.1     .05       0  4997.9     .03       0  5003.9     .05       0
Bank Sta=4997.9,5003.9
XS Rating Curve= 0 ,0
Exp/Cntr=0.3,0.1

Type RM Length L Ch R = 1 ,672     ,96,96,96
BEGIN DESCRIPTION:
Mapping XS 60496998
END DESCRIPTION:
XS GIS Cut Line= 4
      3647491.03     10141270.12      3647944.58     10141495.81
      3648044.41     10141491.47      3648226.68     10141207.22
#Sta/Elev= 30
  4431.8  255.04  4448.1  254.77  4464.9  253.74  4554.5  250.13  4649.6  247.14
  4723.4  243.36  4800.8  241.59  4806.4   240.9  4823.2  241.76  4828.8   241.3
  4845.6  241.88  4851.2  241.38    4868  241.83  4934.2  240.35  5070.8  240.23
  5073.5  239.73  5076.8  240.23    5086  240.27  5095.2  241.07  5101.2  242.47
  5122.3  244.47  5158.7  246.32  5167.9  246.36  5173.9  247.02  5204.3   248.9
  5261.8   250.7    5304  253.16  5334.5  254.46  5361.5   256.2    5376  256.55
#Mann= 3 ,-1 , 0
  4431.8     .05       0  5070.8     .04       0  5076.8     .05       0
Bank Sta=5070.8,5076.8
XS Rating Curve= 0 ,0
Exp/Cntr=0.3,0.1

Type RM Length L Ch R = 1 ,576     ,61,61,61
BEGIN DESCRIPTION:
Mapping XS 64baf155
END DESCRIPTION:
XS GIS Cut Line= 4
       3647443.3     10141285.32      3647953.26      10141591.3
      3648057.43     10141584.79      3648239.71     10141239.76
#Sta/Elev= 30
  4330.8  257.28  4742.5   239.8  4797.8   238.9  4800.5   238.4  4803.8   238.9
  4822.2  239.45  4837.7  240.92  4880.5  240.33    4896  241.58  4901.8  240.64
  4911.6  241.75  4917.4  240.67  4921.9  241.87  4934.4  242.87  4964.4  244.33
  4999.8   243.2  5034.5  242.98  5044.7  243.58  5050.5  242.72  5056.2  243.81
  5066.9  242.58  5072.5  243.87  5088.9  241.17  5094.5  242.83  5110.9  241.56
  5116.5  243.54  5176.9  244.76  5316.2  251.66  5347.4  252.25  5420.1  256.54
#Mann= 3 ,-1 , 0
  4330.8     .05       0  4797.8     .03       0  4803.8     .05       0
Bank Sta=4797.8,4803.8
XS Rating Curve= 0 ,0
Exp/Cntr=0.3,0.1

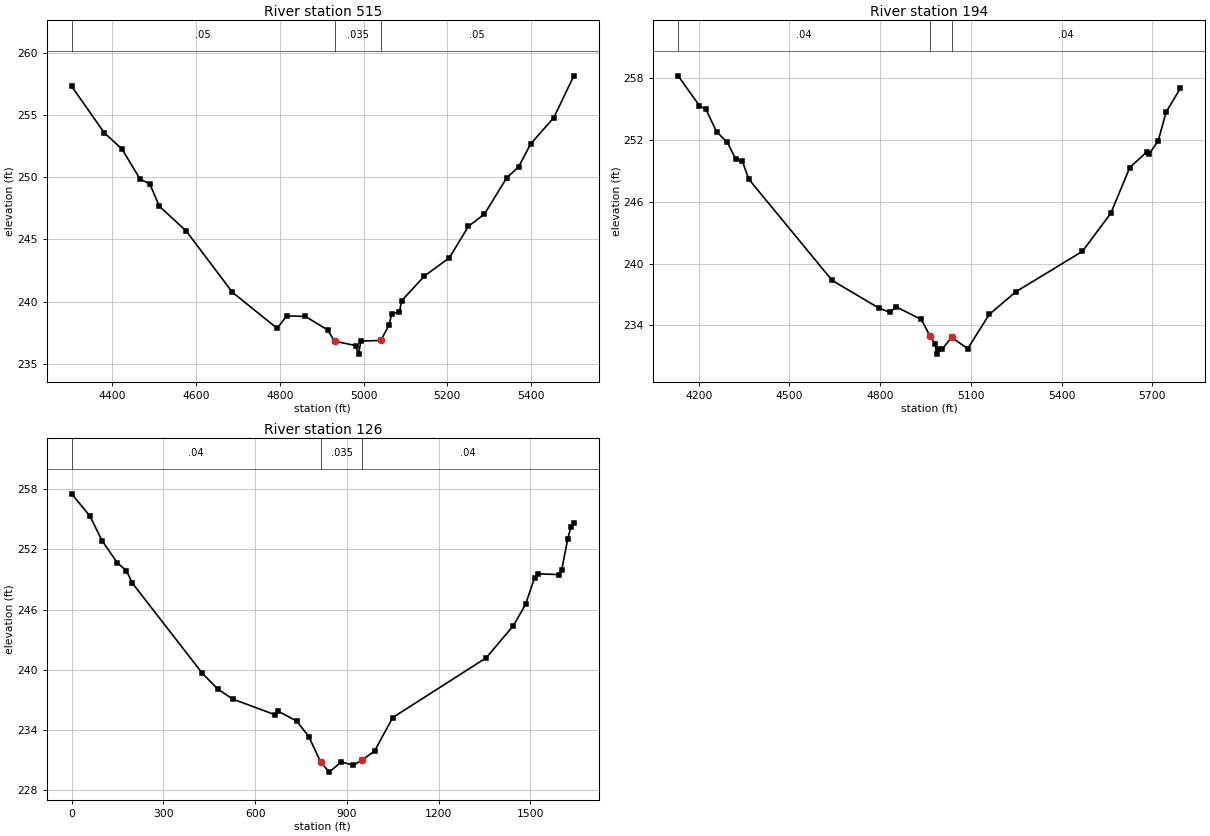
Type RM Length L Ch R = 1 ,515     ,321,321,321
BEGIN DESCRIPTION:
Mapping XS 9449670b
END DESCRIPTION:
XS GIS Cut Line= 4
      3647432.45     10141335.23      3647955.43     10141652.06
      3648109.51     10141641.21      3648293.98      10141248.4
#Sta/Elev= 30
  4302.6  257.32  4380.4  253.58    4423  252.27  4465.9  249.86  4489.3  249.46
  4512.2  247.66  4576.2  245.68  4686.8  240.74  4793.5  237.85  4816.6  238.85
  4861.3   238.8  4914.1  237.72  4930.8  236.81  4980.9  236.46  4988.3  235.77
  4993.6  236.82  5041.1  236.87  5061.1  238.11  5067.3  239.02  5085.5  239.15
    5091  240.06  5145.4  242.05  5205.1  243.52  5250.7  246.05    5289  247.04
    5342  249.95  5370.3  250.83  5399.5  252.69  5454.7   254.8  5502.5  258.16
#Mann= 3 , 0 , 0
  4302.6     .05       0  4930.8    .035       0  5041.1     .05       0
Bank Sta=4930.8,5041.1
XS Rating Curve= 0 ,0
Exp/Cntr=0.3,0.1

Type RM Length L Ch R = 1 ,194     ,68,68,68
BEGIN DESCRIPTION:
UNT093 IN ROCK 1.0
END DESCRIPTION:
XS GIS Cut Line= 4
      3647399.86     10141373.84      3647941.54     10141939.82
      3648115.15     10141957.18      3648342.11     10141291.62
#Sta/Elev= 30
  4131.6  258.24  4202.3  255.33  4223.7  254.99  4258.9   252.8  4294.5  251.77
  4322.4  250.14  4343.8  249.98  4364.9  248.22  4640.7  238.38  4796.4  235.67
  4831.9  235.28    4853   235.8  4935.7  234.58  4965.8  232.93  4982.2   232.2
    4987  231.21  4990.3  231.71    5006  231.73  5036.2  232.84  5089.5  231.74
  5160.8  235.07  5249.5  237.28  5468.9  241.19  5562.9   244.9  5625.6  249.33
    5683  250.89  5688.3   250.6  5719.6  251.93  5745.7  254.72  5792.7  257.01
#Mann= 3 ,-1 , 0
  4131.6     .04       0  4965.8    .035       0  5036.2     .04       0
Bank Sta=4965.8,5036.2
XS Rating Curve= 0 ,0
Exp/Cntr=0.3,0.1

Type RM Length L Ch R = 1 ,126     ,0,0,0
XS GIS Cut Line= 6
     3647406.394    10141428.046      3647957.61    10141985.772
     3648016.203    10142020.494     3648134.476    10141969.496
        3648358.    10141347.7513648358.0001238910141347.7506554
#Sta/Elev= 30
       0257.550159.64917255.335599.41529 252.869149.1229 250.672178.9475249.8759
198.8306248.6214427.4857239.6288477.1934238.0701526.9011237.0574666.0825235.4802
 676.024235.8322735.6732 234.865775.4393233.3184813.9008 230.792842.4207229.7617
881.6765230.7785921.3419230.4486 951.091230.9948990.7127231.87081049.948235.2094
1355.999241.18051444.852244.39891484.342246.5064 1513.96249.17161523.833 249.559
1592.941249.49061602.813249.97081622.558253.08951632.431254.22681642.304254.6445
#Mann= 3 , 0 , 0
       0     .04       0813.9008    .035       0 951.091     .04       0
Bank Sta=813.9008,951.091
XS Rating Curve= 0 ,0
Exp/Cntr=0.3,0.1

Chan Stop Cuts=-1
Use User Specified Reach Order=0
Composite Channel Slope=5