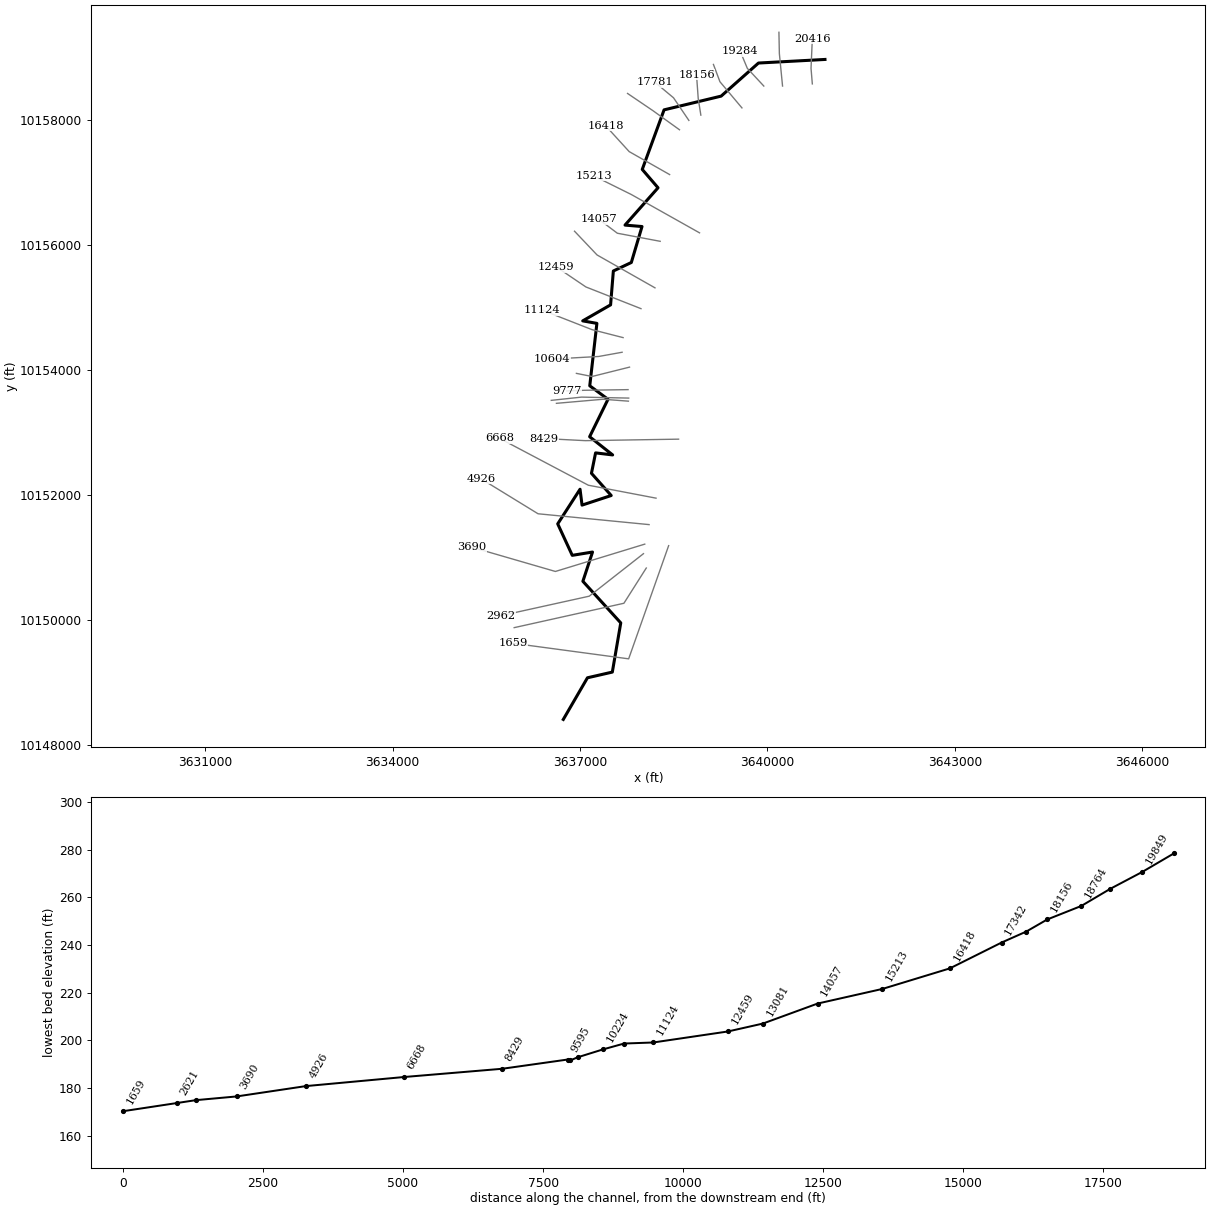
--- UNT094 IN ROCK.prj (project) ---

Proj Title=UNT094 IN ROCK Base Level Engineering
Current Plan=p01
Default Exp/Contr=0.3,0.1
English Units
Geom File=g01
Flow File=f01
Plan File=p01
Y Axis Title=Elevation
X Axis Title(PF)=Main Channel Distance
X Axis Title(XS)=Station
BEGIN DESCRIPTION:
UNT094 IN ROCK
END DESCRIPTION:
DSS Export Rating Curves= 0
DSS Export Rating Curve Sorted= 0
DSS Export Volume Flow Curves= 0
DXF OffsetX= 0
DXF OffsetY= 0
DXF ScaleX= 1
DXF ScaleY= 10

--- UNT094 IN ROCK.p01 (plan) ---

Plan Title=Multiple Run
Short Identifier=Multiple
Geom File=g01
Flow File=f01
Subcritical Flow
K Sum by GR= 0
Std Step Tol= 0.01
Critical Tol= 0.01
Num of Std Step Trials= 20
Max Error Tol= 0.3
Flow Tol Ratio= 0.001
Split Flow NTrial= 30
Split Flow Tol= 0.02
Split Flow Ratio= 0.02
Log Output Level= 0
Friction Slope Method= 1
Unsteady Friction Slope Method= 2
Unsteady Bridges Friction Slope Method= 1
Parabolic Critical Depth
Global Vel Dist=  1 , 1 , 1
Global Log Level= 0
CheckData=True
Encroach Param= -1, 0, 0, 0
BEGIN DESCRIPTION:
Multiple Run
END DESCRIPTION:

--- UNT094 IN ROCK.f01 (steady flow) ---

Flow Title=Multiple
Program Version=4.10
Number of Profiles= 7
Profile Names=10-year,25-year,50-year,1pct_min,100-year,1pct_plu,500-year
River Rch & RM=UNT094 IN ROCK,Reach-1         ,20416
     340     444     526     459     621     839     863
River Rch & RM=UNT094 IN ROCK,Reach-1         ,15213
     535     718     868     770    1041    1408    1500
River Rch & RM=UNT094 IN ROCK,Reach-1         ,14057
     535     718     868     770    1041    1408    1500
River Rch & RM=UNT094 IN ROCK,Reach-1         ,12459
     677     920    1121    1001    1354    1831    1977
River Rch & RM=UNT094 IN ROCK,Reach-1         ,8429
     823    1127    1380    1238    1674    2264    2467
River Rch & RM=UNT094 IN ROCK,Reach-1         ,4926
     942    1296    1592    1431    1935    2617    2864
Boundary for River Rch & Prof#=UNT094 IN ROCK,Reach-1         , 1
Up Type= 0
Dn Type= 3
Dn Slope=0.005
Boundary for River Rch & Prof#=UNT094 IN ROCK,Reach-1         , 2
Up Type= 0
Dn Type= 3
Dn Slope=0.005
Boundary for River Rch & Prof#=UNT094 IN ROCK,Reach-1         , 3
Up Type= 0
Dn Type= 3
Dn Slope=0.005
Boundary for River Rch & Prof#=UNT094 IN ROCK,Reach-1         , 4
Up Type= 0
Dn Type= 3
Dn Slope=0.005
Boundary for River Rch & Prof#=UNT094 IN ROCK,Reach-1         , 5
Up Type= 0
Dn Type= 3
Dn Slope=0.005
Boundary for River Rch & Prof#=UNT094 IN ROCK,Reach-1         , 6
Up Type= 0
Dn Type= 3
Dn Slope=0.005
Boundary for River Rch & Prof#=UNT094 IN ROCK,Reach-1         , 7
Up Type= 0
Dn Type= 3
Dn Slope=0.005
DSS Import GetInterval= 0
DSS Import GetPeak= 0
DSS Import FillOption= 0

--- UNT094 IN ROCK.g01 (geometry) ---

Geom Title=Existing Conditions
Program Version=4.10

River Reach=UNT094 IN ROCK  ,Reach-1
Reach XY= 30
      3640921.32     10158967.41      3639856.77     10158909.99
       3639259.2     10158380.32      3638345.37      10158160.3
      3637996.02     10157206.74      3638248.69     10156912.85
      3637719.98     10156315.27      3637992.23      10156292.6
      3637821.05     10155716.67      3637533.43     10155580.69
      3637489.19      10155038.5      3637043.26     10154782.17
      3637269.94     10154742.16      3637155.73     10153742.75
      3637447.71     10153526.97      3637153.54     10152927.41
      3637522.14       10152636.      3637248.98     10152668.81
      3637182.88     10152341.97      3637499.33     10151986.25
      3637032.16     10151832.55      3637000.15     10152086.73
      3636642.72     10151532.43      3636875.59     10151028.57
      3637200.02     10151081.34      3637045.64     10150613.09
      3637651.95     10149947.15      3637517.03     10149159.51
      3637118.81     10149068.27      3636732.11     10148401.64

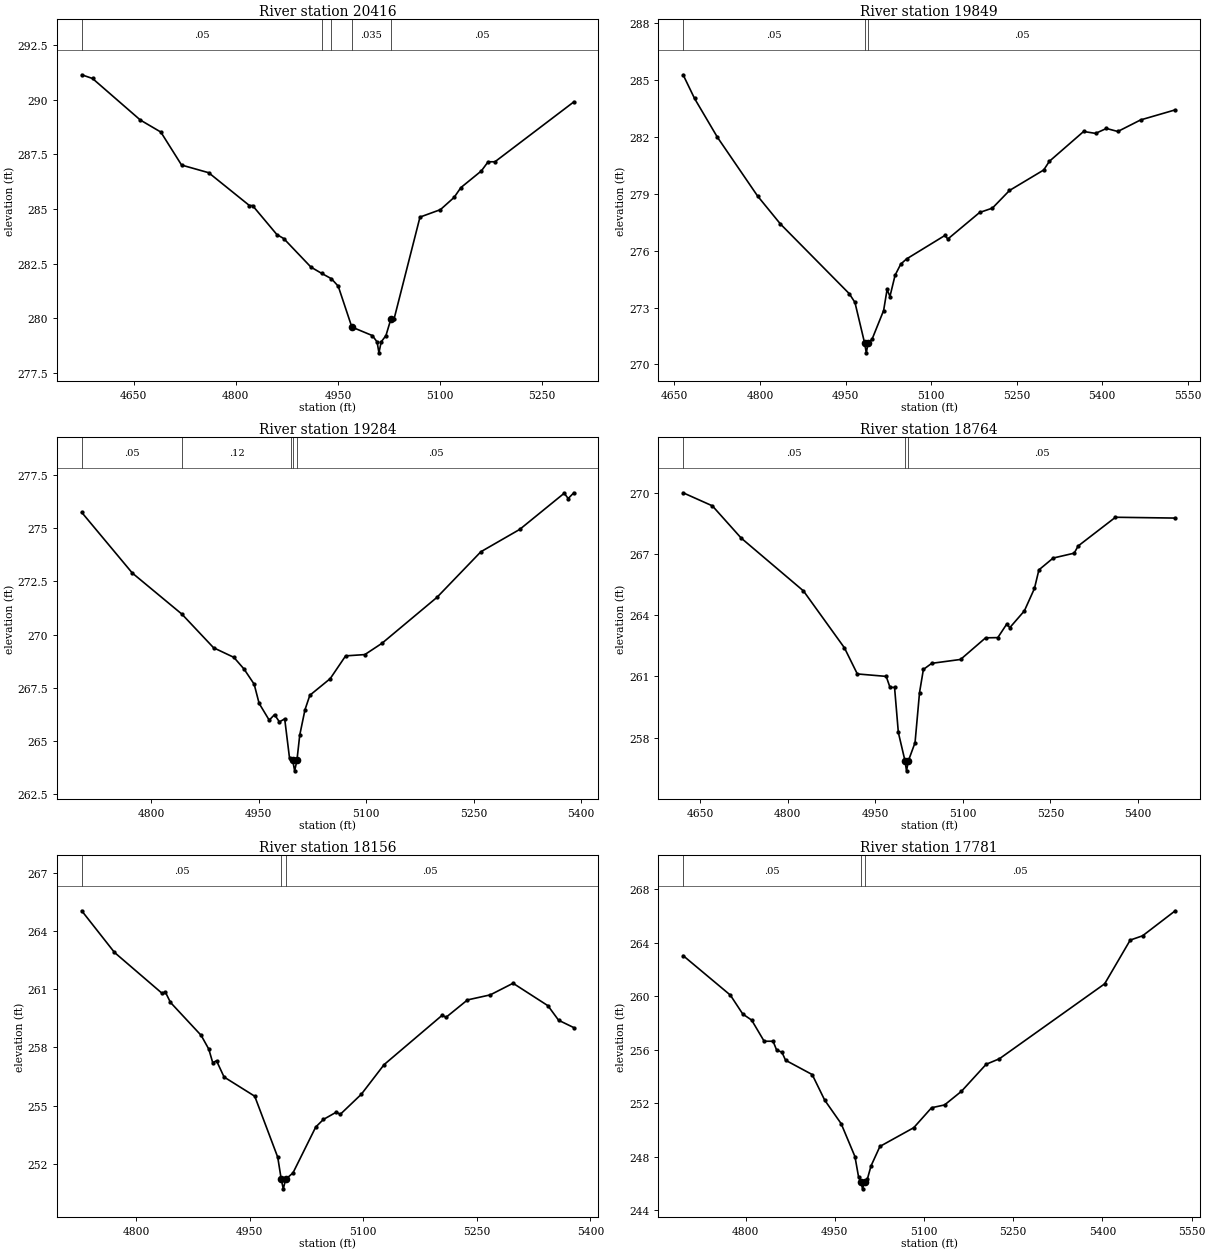
Type RM Length L Ch R = 1 ,20416   ,567,567,567
BEGIN DESCRIPTION:
UNT094 IN ROCK 33.0
END DESCRIPTION:
XS GIS Cut Line= 3
       3640718.9     10158575.83      3640698.06     10158825.86
      3640718.87      10159297.4
#Sta/Elev= 30
  4573.6  291.14  4589.5  290.97  4659.7  289.07  4689.8  288.52  4720.3  287.01
  4760.1  286.66  4819.9  285.16  4824.5  285.16  4860.3  283.83  4870.3  283.65
  4910.4  282.34  4926.4  282.05  4940.4  281.81  4950.4  281.47  4970.4   279.6
  5000.5  279.21  5007.5  278.92  5010.2  278.42  5013.5  278.92  5020.5  279.21
  5027.6  279.95  5032.6  279.99  5070.5  284.63  5100.5  284.97  5120.6  285.53
  5130.6  285.98  5160.6  286.74  5170.6  287.16  5180.6  287.16  5296.5   289.9
#Mann= 5 ,-1 , 0
  4573.6     .05       0  4926.4     .12       0  4940.4     .05       0
  4970.4    .035       0  5027.6     .05       0
Bank Sta=4970.4,5027.6
XS Rating Curve= 0 ,0
Exp/Cntr=0.3,0.1

Type RM Length L Ch R = 1 ,19849   ,565,565,565
BEGIN DESCRIPTION:
UNT094 IN ROCK 31.0
END DESCRIPTION:
XS GIS Cut Line= 3
      3640242.11     10158541.64      3640191.12     10159061.97
      3640184.17     10159402.28
#Sta/Elev= 30
  4665.1  285.27  4685.2  284.02  4725.4  281.97  4795.7  278.88  4835.9   277.4
  4956.5  273.73  4966.5  273.27  4983.6  271.11  4986.4  270.61  4989.6  271.11
  4996.7  271.34  5016.8  272.84  5022.9  273.95  5027.9  273.58  5036.9   274.7
  5046.9  275.29    5057  275.56  5124.4   276.8  5129.4  276.61  5185.2  278.01
  5207.6  278.24  5237.6  279.17  5297.6  280.25  5307.6  280.71  5367.6  282.28
  5388.6  282.18  5407.6  282.44  5427.6  282.28  5467.6  282.89  5528.3  283.42
#Mann= 3 ,-1 , 0
  4665.1     .05       0  4983.6    .035       0  4989.6     .05       0
Bank Sta=4983.6,4989.6
XS Rating Curve= 0 ,0
Exp/Cntr=0.3,0.1

Type RM Length L Ch R = 1 ,19284   ,520,520,520
BEGIN DESCRIPTION:
UNT094 IN ROCK 30.0
END DESCRIPTION:
XS GIS Cut Line= 3
      3639942.12     10158541.63       3639678.3      10158825.1
      3639562.95     10159101.34
#Sta/Elev= 30
  4703.1  275.74  4773.7  272.89  4842.9  270.96  4887.1  269.38  4915.4  268.93
  4929.6  268.38  4943.7  267.67  4950.6  266.77  4964.7  265.98  4972.1  266.24
  4978.9   265.9  4986.3  266.04  4993.1  264.18  4995.5  264.14  4997.4   264.1
  5000.2   263.6  5003.4   264.1  5007.3  265.28  5014.6  266.47  5021.4  267.15
  5049.8  267.93  5071.3     269  5098.1  269.06    5122  269.59  5198.8  271.75
    5260  273.89  5314.2  274.94  5376.3  276.64  5381.8  276.39  5389.7  276.66
#Mann= 5 ,-1 , 0
  4703.1     .05       0  4842.9     .12       0  4995.5     .05       0
  4997.4     .03       0  5003.4     .05       0
Bank Sta=4997.4,5003.4
XS Rating Curve= 0 ,0
Exp/Cntr=0.3,0.1

Type RM Length L Ch R = 1 ,18764   ,608,608,608
BEGIN DESCRIPTION:
UNT094 IN ROCK 29.0
END DESCRIPTION:
XS GIS Cut Line= 3
      3639592.13     10158191.61      3639239.73     10158610.58
      3639135.89     10158887.48
#Sta/Elev= 30
  4620.7     270  4670.8  269.36  4720.2  267.78  4826.9  265.19  4897.1   262.4
  4919.2  261.12  4968.7     261  4975.2  260.46    4983  260.46  4989.5  258.25
  5000.8  256.87  5003.5  256.37  5006.8  256.87  5018.1  257.75  5025.8  260.21
  5032.4  261.34  5046.7  261.64  5096.1  261.83    5139  262.89  5159.9   262.9
  5175.1  263.56  5180.5  263.39  5205.4  264.21  5222.7  265.31  5230.3  266.22
  5254.7   266.8  5290.8  267.04  5297.5  267.39  5361.5   268.8  5463.9  268.76
#Mann= 3 ,-1 , 0
  4620.7     .05       0  5000.8     .03       0  5006.8     .05       0
Bank Sta=5000.8,5006.8
XS Rating Curve= 0 ,0
Exp/Cntr=0.3,0.1

Type RM Length L Ch R = 1 ,18156   ,375,375,375
BEGIN DESCRIPTION:
UNT094 IN ROCK 28.0
END DESCRIPTION:
XS GIS Cut Line= 3
      3638934.18     10158075.83      3638892.11     10158341.64
      3638864.73     10158721.74
#Sta/Elev= 30
  4727.9  265.05  4771.2   262.9  4833.5  260.81  4838.6  260.84  4845.2  260.32
  4885.7  258.62  4895.8  257.91    4901  257.21    4906  257.31    4916  256.47
  4956.5  255.48  4986.9  252.33  4991.5   251.2  4994.2   250.7  4997.5   251.2
    5007  251.52  5037.1  253.89  5047.2  254.28  5064.4  254.66  5069.4  254.54
  5097.3  255.58  5127.4  257.11  5204.2  259.66  5209.2  259.55  5237.6  260.45
  5267.7  260.71  5297.8  261.31  5343.9  260.15    5358   259.4  5378.1  259.02
#Mann= 3 ,-1 , 0
  4727.9     .05       0  4991.5    .035       0  4997.5     .05       0
Bank Sta=4991.5,4997.5
XS Rating Curve= 0 ,0
Exp/Cntr=0.3,0.1

Type RM Length L Ch R = 1 ,17781   ,439,439,439
BEGIN DESCRIPTION:
UNT094 IN ROCK 27.0
END DESCRIPTION:
XS GIS Cut Line= 3
      3638742.12     10157991.62      3638496.67     10158353.64
       3638196.9     10158603.45
#Sta/Elev= 30
  4694.8  263.04  4774.2  260.09  4795.2  258.67  4810.1  258.22  4831.1  256.64
  4846.1  256.64  4852.1  255.98    4861  255.82  4867.1  255.22  4911.9  254.15
  4932.9  252.24  4960.6  250.48  4983.8  248.02  4989.8  246.52  4993.9  246.11
  4996.6  245.61  4999.9  246.11  5004.8  246.36  5010.8  247.32  5025.8  248.78
  5082.7  250.18  5112.6  251.67  5134.5  251.88  5162.9   252.9  5204.5  254.92
  5226.7  255.33  5403.7  260.93  5446.7   264.2  5467.5  264.52  5522.4  266.39
#Mann= 3 ,-1 , 0
  4694.8     .05       0  4993.9    .035       0  4999.9     .05       0
Bank Sta=4993.9,4999.9
XS Rating Curve= 0 ,0
Exp/Cntr=0.3,0.1

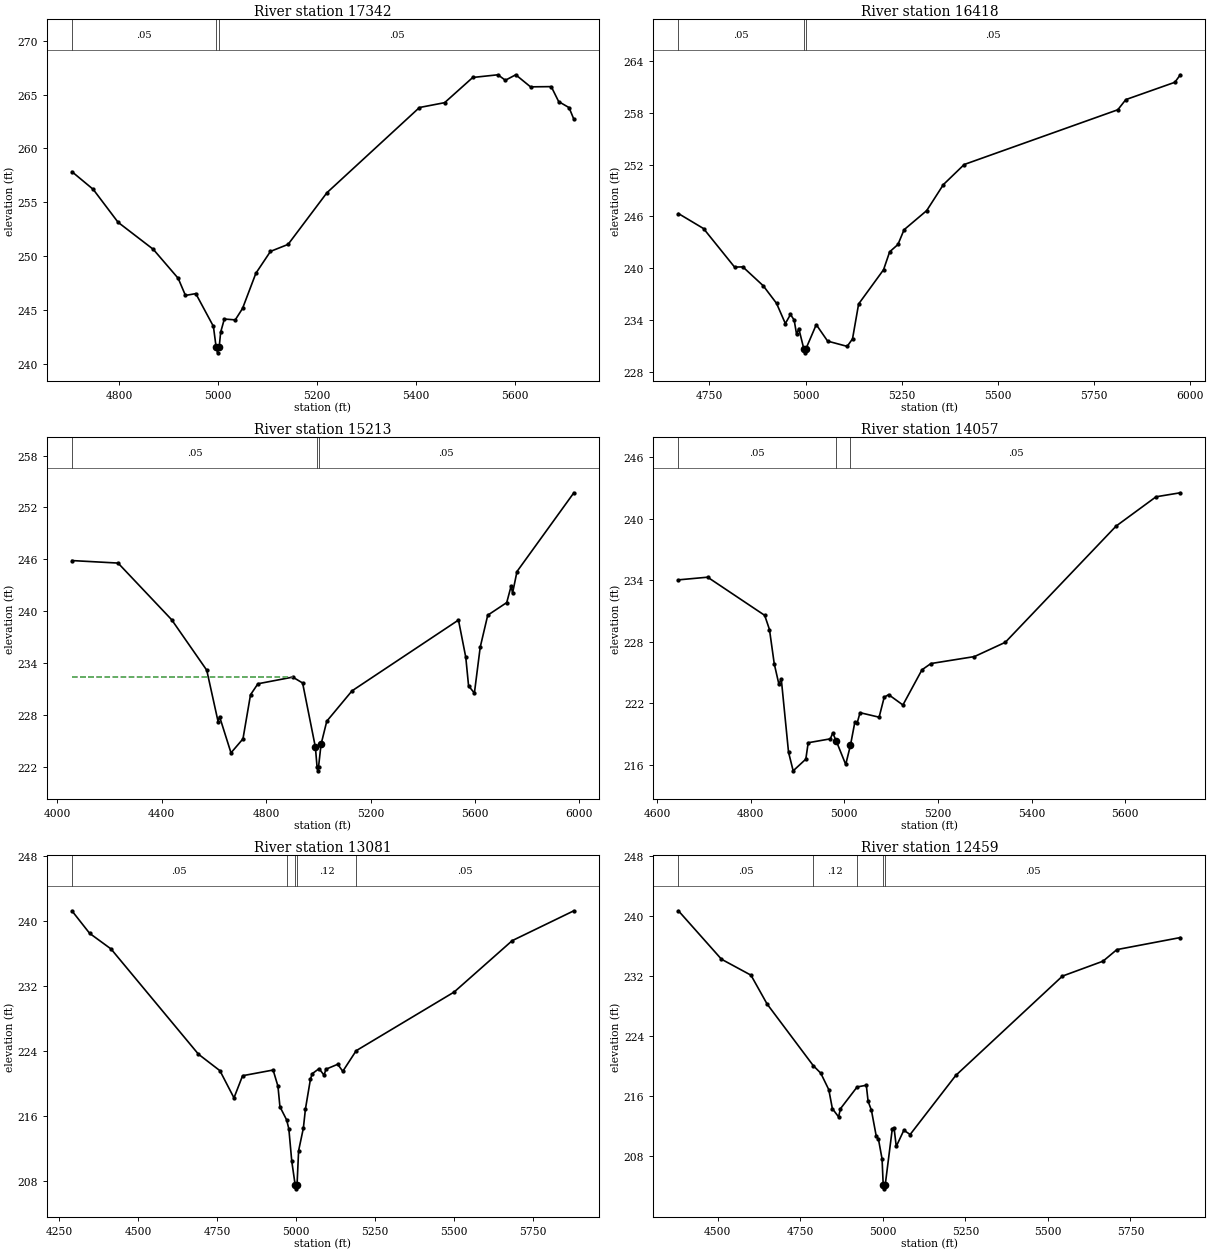
Type RM Length L Ch R = 1 ,17342   ,924,924,924
BEGIN DESCRIPTION:
UNT094 IN ROCK 26.0
END DESCRIPTION:
XS GIS Cut Line= 3
      3638592.12     10157841.63      3638170.29      10158145.3
      3637760.54      10158423.1
#Sta/Elev= 30
    4705  257.84    4748   256.2  4798.3  253.14  4869.5  250.63  4919.8  247.94
  4934.5  246.35  4955.4  246.52    4991  243.48  4996.6  241.52  4999.3  241.02
  5002.6  241.52  5005.7  242.94  5013.1  244.16  5035.2  244.08  5049.9  245.14
  5076.9  248.41  5106.4  250.44    5142  251.09  5220.6  255.89  5407.6   263.8
  5458.5  264.25  5515.4  266.59  5566.3  266.84  5581.3  266.33  5602.3  266.84
  5632.2  265.72  5674.1  265.74  5689.1  264.35  5710.1  263.79  5719.8  262.71
#Mann= 3 ,-1 , 0
    4705     .05       0  4996.6     .03       0  5002.6     .05       0
Bank Sta=4996.6,5002.6
XS Rating Curve= 0 ,0
Exp/Cntr=0.3,0.1

Type RM Length L Ch R = 1 ,16418   ,1205,1205,1205
BEGIN DESCRIPTION:
UNT094 IN ROCK 24.0
END DESCRIPTION:
XS GIS Cut Line= 3
      3638434.21     10157124.45      3637787.08     10157491.86
       3637407.9     10157907.55
#Sta/Elev= 30
  4669.1  246.33  4734.5  244.59  4815.3  240.12  4836.9  240.14    4890  237.95
  4924.5  235.92  4947.5  233.57  4960.9  234.62  4970.5  233.97  4976.8   232.3
  4982.5  232.99  4995.4  230.67  4998.2  230.17  5001.4  230.67    5028  233.44
  5057.6  231.53  5108.5  230.92  5122.4  231.79  5138.3  235.84  5203.2  239.81
  5219.1  241.89  5240.7  242.74  5256.6  244.45  5315.5  246.67    5359  249.69
  5413.2  252.02  5813.1  258.37    5834  259.55  5961.7  261.56  5975.9  262.43
#Mann= 3 ,-1 , 0
  4669.1     .05       0  4995.4     .03       0  5001.4     .05       0
Bank Sta=4995.4,5001.4
XS Rating Curve= 0 ,0
Exp/Cntr=0.3,0.1

Type RM Length L Ch R = 1 ,15213   ,1156,1156,1156
BEGIN DESCRIPTION:
UNT094 IN ROCK 22.0
END DESCRIPTION:
XS GIS Cut Line= 3
      3638913.36     10156191.36      3637819.59     10156805.95
      3637220.64     10157102.82
#Sta/Elev= 30
    4056  245.86  4232.7  245.57    4438  239.02  4572.5  233.18  4615.9  227.24
  4621.6  227.81  4665.4  223.62  4711.3  225.24  4740.2  230.34  4768.6  231.61
  4902.1  232.38  4939.8   231.7  4988.8  224.27    4995  222.04  4997.8  221.54
    5001  222.04  5010.5  224.61  5032.4  227.28  5129.1  230.79    5537  238.98
    5565  234.67  5575.7  231.37    5598  230.53  5620.3  235.84  5649.1  239.54
  5721.9     241  5738.8  242.92  5744.3   242.1  5761.2  244.59  5979.1   253.7
#Mann= 3 ,-1 , 0
    4056     .05       0    4995    .035       0    5001     .05       0
#XS Ineff= 2 , 0
         4903.41  232.44
Permanent Ineff=
       F       F
Bank Sta=4988.8,5010.5
XS Rating Curve= 0 ,0
Exp/Cntr=0.3,0.1

Type RM Length L Ch R = 1 ,14057   ,976,976,976
BEGIN DESCRIPTION:
UNT094 IN ROCK 21.0
END DESCRIPTION:
XS GIS Cut Line= 3
      3638283.13     10156055.95      3637597.31     10156185.39
      3637298.76     10156410.11
#Sta/Elev= 30
  4645.8  234.02  4708.2  234.28    4830  230.56  4840.2  229.18  4850.4  225.84
  4860.3  223.85  4865.4  224.36  4880.9  217.22  4890.8   215.4  4917.8  216.54
  4922.9  218.14  4970.2  218.52  4975.3  219.09  4982.7  218.32    5003  216.02
  5013.2  217.91  5022.6  220.17  5027.7  220.11  5033.6  221.07  5074.3  220.63
  5085.2  222.58  5094.6  222.83  5125.1  221.82  5165.8  225.25  5184.9  225.86
  5277.8  226.54  5343.7  227.93  5580.2  239.26  5665.6  242.12  5717.4  242.51
#Mann= 3 , 0 , 0
  4645.8     .05       0  4982.7    .035       0  5013.2     .05       0
Bank Sta=4982.7,5013.2
XS Rating Curve= 0 ,0
Exp/Cntr=0.3,0.1

Type RM Length L Ch R = 1 ,13081   ,622,622,622
BEGIN DESCRIPTION:
UNT094 IN ROCK 19.0
END DESCRIPTION:
XS GIS Cut Line= 3
      3638199.82     10155311.15      3637272.72      10155837.2
      3636911.88     10156217.65
#Sta/Elev= 30
  4290.7  241.24  4346.8  238.47  4414.5  236.55  4691.5  223.59  4759.5  221.56
  4804.1  218.21  4831.4  220.94  4928.1  221.64  4943.4  219.65  4949.7  217.12
  4970.9   215.5  4977.9  214.41  4987.2  210.41  4997.9  207.51  5000.7  207.01
  5003.9  207.51  5008.9  211.71  5023.9  214.47  5030.5  216.84  5046.4  220.52
  5052.1  221.19  5073.7  221.81  5089.6     221  5095.4  221.74  5132.9  222.35
  5148.8  221.48  5191.3  224.02  5501.5  231.24  5685.6  237.57    5881  241.25
#Mann= 5 ,-1 , 0
  4290.7     .05       0  4970.9     .12       0  4997.9     .07       0
  5003.9     .12       0  5191.3     .05       0
Bank Sta=4997.9,5003.9
XS Rating Curve= 0 ,0
Exp/Cntr=0.3,0.1

Type RM Length L Ch R = 1 ,12459   ,1335,1335,1335
BEGIN DESCRIPTION:
UNT094 IN ROCK 18.0
END DESCRIPTION:
XS GIS Cut Line= 3
      3637975.88     10154977.81      3637093.53     10155325.42
      3636620.23     10155645.81
#Sta/Elev= 30
    4381  240.66  4511.4  234.22  4600.7   232.1  4649.5  228.27  4789.3  220.08
    4812  219.08  4836.4  216.88  4847.2  214.36  4866.1  213.26  4871.5  214.34
  4922.1  217.24    4950  217.47  4955.4  215.34  4965.5  214.14  4979.8  210.77
  4986.9  210.27  4997.7  207.68  5001.2   204.2  5003.9   203.7  5007.2   204.2
  5028.6  211.65    5034  211.81  5040.7  209.34  5063.7  211.49  5082.7  210.92
  5220.8  218.77    5544  231.98  5666.8  233.96  5708.8   235.5  5900.9   237.1
#Mann= 5 ,-1 , 0
    4381     .05       0  4789.3     .12       0  4922.1     .05       0
  5001.2     .03       0  5007.2     .05       0
Bank Sta=5001.2,5007.2
XS Rating Curve= 0 ,0
Exp/Cntr=0.3,0.1

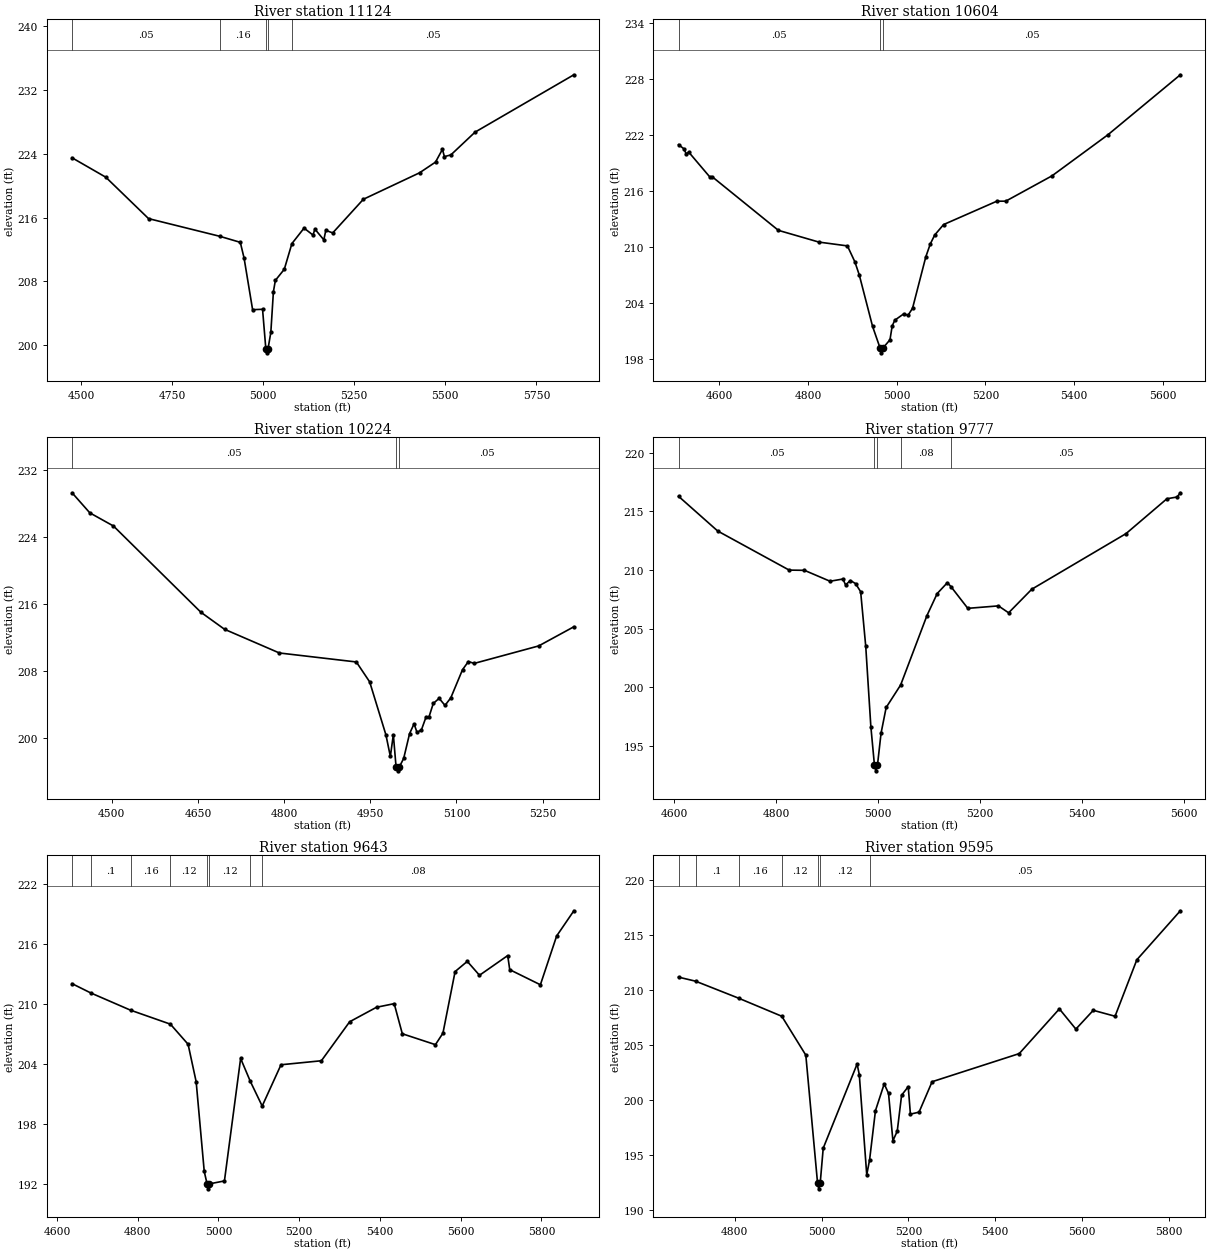
Type RM Length L Ch R = 1 ,11124   ,520,520,520
BEGIN DESCRIPTION:
UNT094 IN ROCK 16.0
END DESCRIPTION:
XS GIS Cut Line= 3
      3637689.35     10154514.29      3637192.11     10154641.64
      3636387.74     10154956.82
#Sta/Elev= 30
  4475.6  223.48  4568.2  221.05  4685.5  215.87  4880.6  213.66  4937.3   212.9
  4947.6  210.95  4971.1  204.47  4998.4  204.52  5007.4  199.57  5010.1  199.07
  5013.4  199.57  5021.1  201.62  5028.2  206.73  5033.6  208.14  5058.1  209.53
  5078.9  212.74  5112.3  214.68  5136.8  213.81  5142.1  214.55  5166.6  213.21
    5172   214.4    5191  214.08  5275.1  218.29  5429.2   221.6  5473.1  222.94
  5492.1  224.54  5497.5  223.63  5515.2  223.84  5581.6  226.69  5852.8  233.87
#Mann= 5 ,-1 , 0
  4475.6     .05       0  4880.6     .16       0  5007.4     .07       0
  5013.4     .16       0  5078.9     .05       0
Bank Sta=5007.4,5013.4
XS Rating Curve= 0 ,0
Exp/Cntr=0.3,0.1

Type RM Length L Ch R = 1 ,10604   ,380,380,380
BEGIN DESCRIPTION:
UNT094 IN ROCK 15.0
END DESCRIPTION:
XS GIS Cut Line= 3
      3637673.81     10154279.92      3637298.76      10154212.2
      3636548.73     10154170.53
#Sta/Elev= 30
  4507.6  220.98  4519.5  220.54  4525.3  219.96  4530.4  220.19  4578.9  217.47
  4583.9  217.52  4732.9  211.78  4824.3  210.52  4888.7  210.11  4905.4  208.41
  4915.4     207  4945.5  201.46  4962.5  199.13  4965.2  198.63  4968.5  199.13
  4984.7  200.03  4989.7  201.51  4995.5  202.13  5015.6  202.81  5025.6  202.67
  5035.6  203.41  5065.6  208.94  5075.7  210.32  5085.7  211.28  5105.7   212.4
  5225.9  214.91  5245.9  214.91  5350.3  217.63  5476.3  222.03  5639.9  228.48
#Mann= 3 ,-1 , 0
  4507.6     .05       0  4962.5     .03       0  4968.5     .05       0
Bank Sta=4962.5,4968.5
XS Rating Curve= 0 ,0
Exp/Cntr=0.3,0.1

Type RM Length L Ch R = 1 ,10224   ,447,447,447
BEGIN DESCRIPTION:
UNT094 IN ROCK 14.0
END DESCRIPTION:
XS GIS Cut Line= 3
       3637792.1     10154041.64      3637192.11     10153891.64
      3636942.11     10153941.64
#Sta/Elev= 30
    4431  229.24  4461.9  226.85  4503.1  225.28  4655.2  215.02  4696.4  212.99
  4791.8  210.17  4925.8   209.1    4949  206.73  4977.3  200.42    4985  197.85
  4990.2  200.45  4994.9  196.64  4997.7  196.14  5000.9  196.64  5008.2  197.62
  5018.5  200.58  5026.3  201.74  5031.4  200.71  5039.1  201.02  5046.9  202.51
    5052  202.51  5059.7  204.16  5069.9  204.77  5080.1  203.93  5090.2  204.83
  5110.6  208.18  5120.8  209.15    5131  208.93  5243.2  211.01  5304.4  213.29
#Mann= 3 ,-1 , 0
    4431     .05       0  4994.9    .035       0  5000.9     .05       0
Bank Sta=4994.9,5000.9
XS Rating Curve= 0 ,0
Exp/Cntr=0.3,0.1

Type RM Length L Ch R = 1 ,9777    ,134,134,134
BEGIN DESCRIPTION:
UNT094 IN ROCK 13.0
END DESCRIPTION:
XS GIS Cut Line= 3
      3637768.92     10153681.49      3637076.21     10153671.08
      3636785.79     10153660.71
#Sta/Elev= 30
  4608.7  216.27  4685.5  213.31  4825.5  209.98  4855.5  209.96  4905.6  209.03
    4931  209.22    4936  208.72  4945.6  209.09  4955.6  208.83  4965.6  208.14
  4975.6  203.47  4985.6  196.64  4992.6  193.37  4995.3  192.87  4998.6  193.37
  5005.6  196.08  5015.6  198.27    5044  200.19  5095.6  206.11  5115.6  207.98
  5135.6  208.91  5142.6  208.57  5175.6  206.72  5235.6  206.93  5255.6  206.34
    5301  208.35  5485.7  213.09  5565.8  216.06  5585.8  216.21  5592.1  216.57
#Mann= 5 ,-1 , 0
  4608.7     .05       0  4992.6    .035       0  4998.6     .05       0
    5044     .08       0  5142.6     .05       0
Bank Sta=4992.6,4998.6
XS Rating Curve= 0 ,0
Exp/Cntr=0.3,0.1

Type RM Length L Ch R = 1 ,9643    ,48,48,48
BEGIN DESCRIPTION:
UNT094 IN ROCK 12.0
END DESCRIPTION:
XS GIS Cut Line= 3
      3637779.37     10153546.08      3637024.13      10153561.7
      3636539.73     10153509.62
#Sta/Elev= 30
  4637.6  212.06  4683.5  211.14  4782.3  209.41  4881.1  208.01  4924.9     206
  4944.9  202.25  4964.9  193.28  4971.9  192.04  4974.7  191.54  4977.9  192.04
  5014.9  192.33    5055  204.58  5079.1  202.28  5108.4  199.82    5155  203.95
    5255  204.35    5325  208.25  5391.5   209.7  5435.3  210.06  5455.4  207.05
  5537.4  205.96    5556  207.11  5586.1  213.27  5616.3  214.29  5646.5   212.9
  5716.4  214.87  5721.4  213.46  5797.3  211.95  5837.6  216.83  5880.2  219.35
#Mann= 8 ,-1 , 0
  4637.6     .05       0  4683.5      .1       0  4782.3     .16       0
  4881.1     .12       0  4971.9     .07       0  4977.9     .12       0
  5079.1     .05       0  5108.4     .08       0
Bank Sta=4971.9,4977.9
XS Rating Curve= 0 ,0
Exp/Cntr=0.3,0.1

Type RM Length L Ch R = 1 ,9595    ,1166,1166,1166
BEGIN DESCRIPTION:
Mapping XS eb9dbf46
END DESCRIPTION:
XS GIS Cut Line= 3
      3637774.61      10153496.9      3637368.77     10153527.28
      3636622.28     10153462.18
#Sta/Elev= 30
  4670.5  211.18  4709.9  210.81  4809.2  209.26  4908.4  207.62  4963.8  204.08
  4990.9  192.41  4993.7  191.91  4996.9  192.41  5003.9  195.61    5082  203.27
    5087  202.31  5104.2  193.19  5110.8  194.56  5124.3  199.03  5144.4  201.46
  5154.4   200.6  5164.5  196.29  5174.5  197.16  5184.5  200.43  5199.8  201.21
  5204.8  198.71  5224.7  198.89  5254.8  201.66  5455.6  204.22  5548.1  208.29
  5586.1  206.45  5626.2  208.16  5676.4  207.62  5726.6  212.76  5826.8  217.22
#Mann= 7 ,-1 , 0
  4670.5     .05       0  4709.9      .1       0  4809.2     .16       0
  4908.4     .12       0  4990.9     .07       0  4996.9     .12       0
  5110.8     .05       0
Bank Sta=4990.9,4996.9
XS Rating Curve= 0 ,0
Exp/Cntr=0.3,0.1

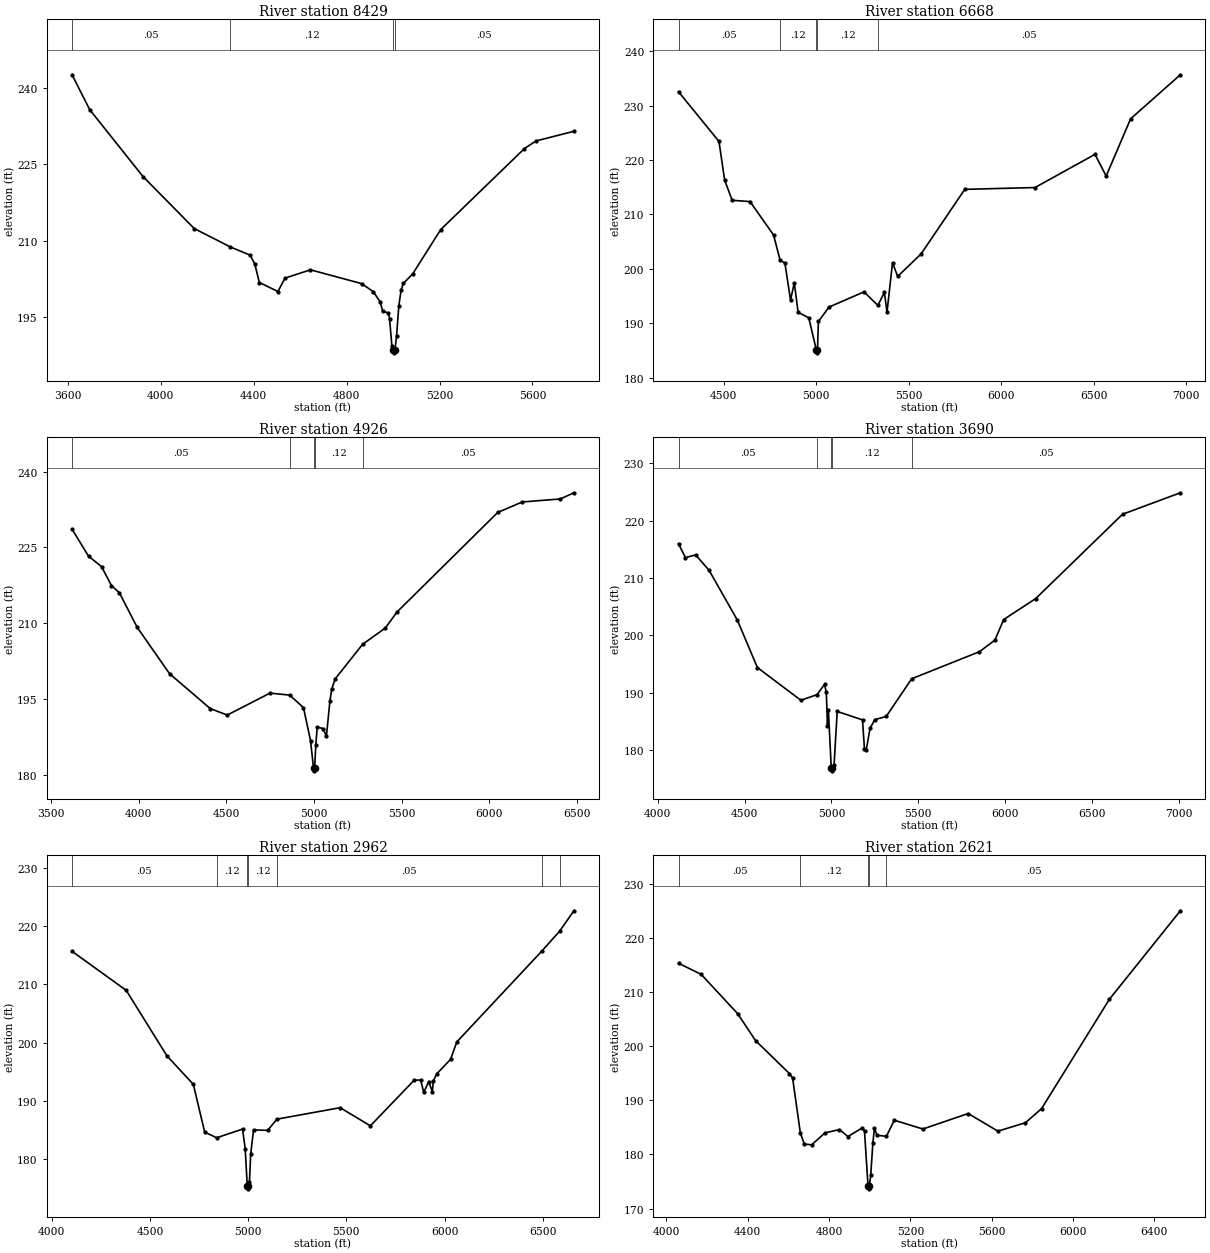
Type RM Length L Ch R = 1 ,8429    ,1761,1761,1761
BEGIN DESCRIPTION:
UNT094 IN ROCK 11.0
END DESCRIPTION:
XS GIS Cut Line= 3
       3638577.9     10152888.52      3637085.11     10152864.52
      3636419.87     10152898.59
#Sta/Elev= 30
  3618.9   242.6  3694.7  235.76  3924.7   222.6  4144.8  212.42  4300.3  208.81
  4384.8  207.21  4404.8  205.51  4424.8  201.84  4504.8  200.07  4534.8   202.7
  4644.8  204.33  4864.9  201.62  4914.9  200.05  4944.9  198.02  4954.9   196.3
    4980  195.82    4985  194.74  4994.9  189.45  5001.9  188.54  5004.6  188.04
  5007.9  188.54  5014.9  191.25  5024.9   197.3  5034.9  200.44  5044.9  201.67
  5084.9  203.56    5205  212.22  5565.5  228.13  5615.5  229.62    5778  231.51
#Mann= 4 ,-1 , 0
  3618.9     .05       0  4300.3     .12       0  5001.9     .07       0
  5007.9     .05       0
Bank Sta=5001.9,5007.9
XS Rating Curve= 0 ,0
Exp/Cntr=0.3,0.1

Type RM Length L Ch R = 1 ,6668    ,1742,1742,1742
BEGIN DESCRIPTION:
UNT094 IN ROCK 9.0
END DESCRIPTION:
XS GIS Cut Line= 3
      3638216.87     10151944.07      3637132.42     10152151.33
      3635709.91     10152902.41
#Sta/Elev= 30
  4255.2  232.53  4473.9   223.4  4504.4   216.3  4545.1  212.59  4641.8  212.35
  4769.1   206.2  4803.9  201.62  4830.2  201.05  4860.7  194.28  4881.1  197.42
  4901.5  192.01  4959.4  190.99  5000.3  185.06    5003  184.56  5006.3  185.06
  5011.5  190.33  5068.7  192.97  5257.8  195.76  5332.7  193.28    5368  195.66
  5382.3  192.05    5412  201.13  5439.7   198.6  5566.1  202.72  5802.7   214.6
    6182  214.93  6506.6  221.03    6567  217.04  6699.1  227.56  6967.9  235.65
#Mann= 5 ,-1 , 0
  4255.2     .05       0  4803.9     .12       0  5000.3     .07       0
  5006.3     .12       0  5332.7     .05       0
Bank Sta=5000.3,5006.3
XS Rating Curve= 0 ,0
Exp/Cntr=0.3,0.1

Type RM Length L Ch R = 1 ,4926    ,1236,1236,1236
BEGIN DESCRIPTION:
UNT094 IN ROCK 8.0
END DESCRIPTION:
XS GIS Cut Line= 3
      3638105.69     10151520.47      3636327.95     10151694.08
      3635411.28     10152256.58
#Sta/Elev= 30
  3620.2   228.6  3714.2  223.26  3788.1  221.21  3844.9  217.45  3889.8  216.04
  3991.4  209.19  4176.4  199.99  4408.2   193.1  4504.9  191.81  4749.1  196.16
  4861.4  195.76    4940  193.27  4980.2  186.74  4997.3  181.27  5000.1  180.77
  5003.3  181.27  5010.4  185.96  5018.3  189.44  5050.6  189.15  5070.7  187.64
  5090.8  194.62  5100.8   196.9    5120  198.95  5277.3  205.83  5406.4  209.03
  5473.2  212.21  6047.5  231.92  6187.6     234  6405.1   234.6  6481.9  235.82
#Mann= 5 ,-1 , 0
  3620.2     .05       0  4861.4     .12       0  4997.3     .07       0
  5003.3     .12       0  5277.3     .05       0
Bank Sta=4997.3,5003.3
XS Rating Curve= 0 ,0
Exp/Cntr=0.3,0.1

Type RM Length L Ch R = 1 ,3690    ,728,728,728
BEGIN DESCRIPTION:
UNT094 IN ROCK 7.0
END DESCRIPTION:
XS GIS Cut Line= 3
      3638036.29     10151207.97      3636605.72     10150770.47
      3635266.24     10151159.13
#Sta/Elev= 30
  4119.4  215.95  4159.3  213.54  4217.9  214.02  4295.6  211.32  4458.4  202.66
  4573.6  194.41  4824.4  188.71  4917.6   189.7  4960.3  191.48  4970.8  190.07
  4977.4  184.31  4982.6  187.02  4999.2  176.93  5001.9  176.43  5005.2  176.93
  5015.4  177.45  5033.5  186.77  5179.3   185.3  5190.4  180.27  5200.9  180.09
  5222.6  183.83  5250.1  185.34  5315.7   185.9  5462.7  192.46  5853.1  197.17
  5941.9  199.19  5992.6  202.77    6176  206.39  6677.1  221.09  7010.1  224.83
#Mann= 5 ,-1 , 0
  4119.4     .05       0  4917.6     .12       0  4999.2     .07       0
  5005.2     .12       0  5462.7     .05       0
Bank Sta=4999.2,5005.2
XS Rating Curve= 0 ,0
Exp/Cntr=0.3,0.1

Type RM Length L Ch R = 1 ,2962    ,341,341,341
BEGIN DESCRIPTION:
UNT094 IN ROCK 5.0
END DESCRIPTION:
XS GIS Cut Line= 3
      3638015.47     10151055.21      3637147.39     10150374.64
      3635730.71     10150062.13
#Sta/Elev= 30
    4104   215.7  4379.3     209  4586.4  197.75  4721.1  192.83  4778.9  184.62
  4839.8  183.65  4971.5  185.14  4985.1   181.8  4995.6  175.37  4998.4  174.87
  5001.6  175.37  5006.7  176.06  5013.1  180.84  5027.5     185  5099.4  184.92
  5146.7  186.85  5468.5  188.82  5622.1   185.7    5845  193.54  5878.1  193.59
  5893.8  191.44  5919.1  193.31  5937.5  191.58  5942.6  193.43    5960  194.64
    6030  197.12  6062.4  200.14  6494.5  215.73  6585.4  219.16  6657.8  222.67
#Mann= 7 ,-1 , 0
    4104     .05       0  4839.8     .12       0  4995.6     .07       0
  5001.6     .12       0  5146.7     .05       0  6494.5     .16       0
  6585.4     .05       0
Bank Sta=4995.6,5001.6
XS Rating Curve= 0 ,0
Exp/Cntr=0.3,0.1

Type RM Length L Ch R = 1 ,2621    ,962,962,962
BEGIN DESCRIPTION:
UNT094 IN ROCK 3.0
END DESCRIPTION:
XS GIS Cut Line= 3
       3638060.6     10150825.61      3637702.51     10150261.36
      3635945.85     10149870.99
#Sta/Elev= 30
  4059.9  215.31  4171.2  213.26  4350.6     206  4438.7  201.02  4605.6  194.93
  4620.8  194.13    4659  183.97  4678.4  181.92  4714.9  181.78  4779.8  183.98
  4851.5   184.6  4892.9  183.31  4964.2  184.92  4974.5   184.3  4991.9  174.15
  4994.7  173.65  4997.9  174.15  5005.2  176.17  5015.4  182.06  5023.5  184.85
  5035.9  183.53  5082.5  183.36  5120.9  186.32  5261.7   184.7  5484.5  187.56
  5630.5   184.3  5766.2  185.86  5845.2  188.46  6178.5  208.64  6527.7     225
#Mann= 5 ,-1 , 0
  4059.9     .05       0    4659     .12       0  4991.9     .07       0
  4997.9     .12       0  5082.5     .05       0
Bank Sta=4991.9,4997.9
XS Rating Curve= 0 ,0
Exp/Cntr=0.3,0.1

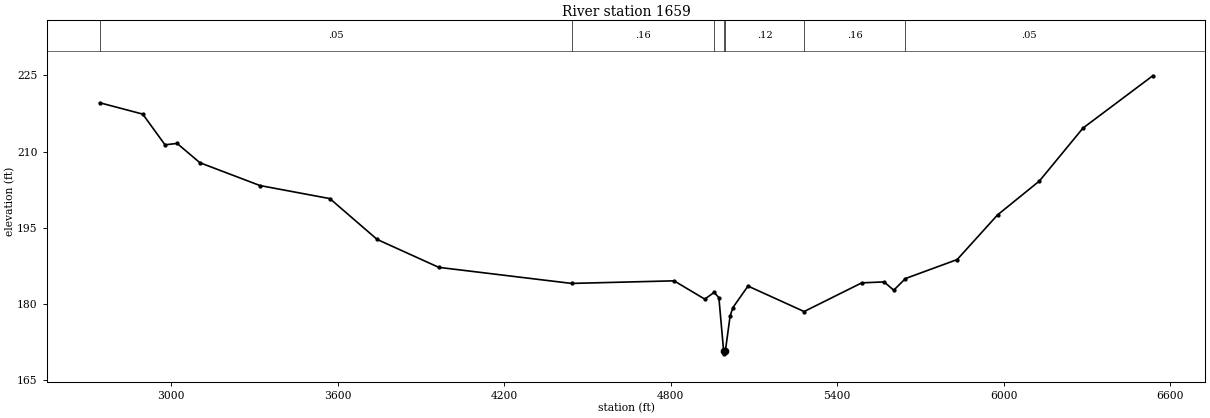
Type RM Length L Ch R = 1 ,1659    ,0,0,0
BEGIN DESCRIPTION:
UNT094 IN ROCK 1.0
END DESCRIPTION:
XS GIS Cut Line= 3
      3638418.65     10151183.66      3637778.47      10149371.6
        3635923.     10149621.16
#Sta/Elev= 30
  2742.8  219.61  2898.1  217.37  2978.3  211.33  3021.8  211.61    3104  207.81
  3320.4  203.32  3572.2  200.75  3742.6  192.72  3964.6  187.23  4442.8  184.07
  4812.3  184.58  4922.9  180.98  4956.4   182.3  4973.7  181.28  4990.9  170.72
  4993.7  170.22  4996.9  170.72  5014.1  177.64  5024.2  179.32  5078.6  183.55
  5280.8  178.54  5488.3  184.18  5569.1  184.37  5603.5  182.73  5645.8  185.03
  5832.1  188.76  5977.7  197.55  6128.4  204.21  6285.4  214.62  6536.8  224.91
#Mann= 7 ,-1 , 0
  2742.8     .05       0  4442.8     .16       0  4956.4     .12       0
  4990.9     .07       0  4996.9     .12       0  5280.8     .16       0
  5645.8     .05       0
Bank Sta=4990.9,4996.9
XS Rating Curve= 0 ,0
Exp/Cntr=0.3,0.1

Chan Stop Cuts=-1
Use User Specified Reach Order=0
Composite Channel Slope=5