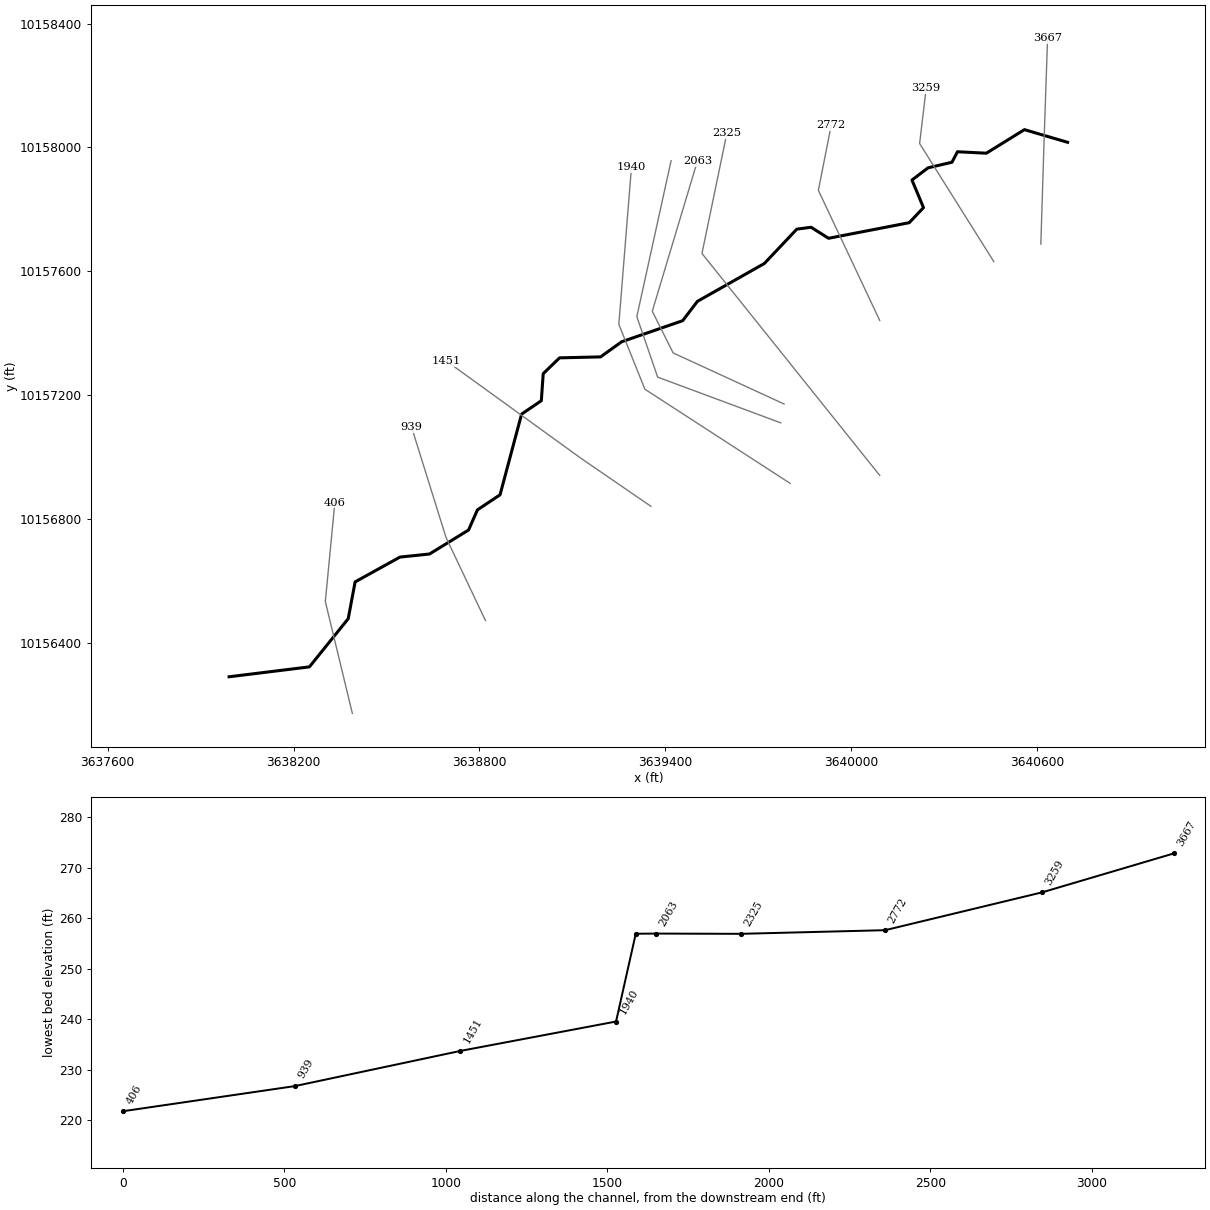
--- UNT095 IN ROCK.prj (project) ---

Proj Title=UNT095 IN ROCK Base Level Engineering
Current Plan=p01
Default Exp/Contr=0.3,0.1
English Units
Geom File=g01
Flow File=f01
Plan File=p01
Y Axis Title=Elevation
X Axis Title(PF)=Main Channel Distance
X Axis Title(XS)=Station
BEGIN DESCRIPTION:
UNT095 IN ROCK
END DESCRIPTION:
DSS Export Rating Curves= 0
DSS Export Rating Curve Sorted= 0
DSS Export Volume Flow Curves= 0
DXF OffsetX= 0
DXF OffsetY= 0
DXF ScaleX= 1
DXF ScaleY= 10

--- UNT095 IN ROCK.p01 (plan) ---

Plan Title=Multiple Run
Short Identifier=Multiple
Geom File=g01
Flow File=f01
Subcritical Flow
K Sum by GR= 0
Std Step Tol= 0.01
Critical Tol= 0.01
Num of Std Step Trials= 20
Max Error Tol= 0.3
Flow Tol Ratio= 0.001
Split Flow NTrial= 30
Split Flow Tol= 0.02
Split Flow Ratio= 0.02
Log Output Level= 0
Friction Slope Method= 1
Unsteady Friction Slope Method= 2
Unsteady Bridges Friction Slope Method= 1
Parabolic Critical Depth
Global Vel Dist=  1 , 1 , 1
Global Log Level= 0
CheckData=True
Encroach Param= -1, 0, 0, 0
BEGIN DESCRIPTION:
Multiple Run
END DESCRIPTION:

--- UNT095 IN ROCK.f01 (steady flow) ---

Flow Title=Multiple
Program Version=4.10
Number of Profiles= 7
Profile Names=10-year,25-year,50-year,1pct_min,100-year,1pct_plu,500-year
River Rch & RM=UNT095 IN ROCK,Reach-1         ,3667
     200     252     293     250     339     458     452
Boundary for River Rch & Prof#=UNT095 IN ROCK,Reach-1         , 1
Up Type= 0
Dn Type= 3
Dn Slope=0.005
Boundary for River Rch & Prof#=UNT095 IN ROCK,Reach-1         , 2
Up Type= 0
Dn Type= 3
Dn Slope=0.005
Boundary for River Rch & Prof#=UNT095 IN ROCK,Reach-1         , 3
Up Type= 0
Dn Type= 3
Dn Slope=0.005
Boundary for River Rch & Prof#=UNT095 IN ROCK,Reach-1         , 4
Up Type= 0
Dn Type= 3
Dn Slope=0.005
Boundary for River Rch & Prof#=UNT095 IN ROCK,Reach-1         , 5
Up Type= 0
Dn Type= 3
Dn Slope=0.005
Boundary for River Rch & Prof#=UNT095 IN ROCK,Reach-1         , 6
Up Type= 0
Dn Type= 3
Dn Slope=0.005
Boundary for River Rch & Prof#=UNT095 IN ROCK,Reach-1         , 7
Up Type= 0
Dn Type= 3
Dn Slope=0.005
DSS Import GetInterval= 0
DSS Import GetPeak= 0
DSS Import FillOption= 0

--- UNT095 IN ROCK.g01 (geometry) ---

Geom Title=Existing Conditions
Program Version=4.10

River Reach=UNT095 IN ROCK  ,Reach-1
Reach XY= 30
      3640698.46     10158016.73      3640559.13      10158057.6
      3640436.22     10157981.55      3640342.99     10157986.24
      3640325.28     10157952.39      3640248.11     10157934.37
      3640196.15     10157894.95      3640233.36      10157805.9
      3640187.35     10157757.29      3639926.93     10157706.94
      3639870.51     10157742.53       3639824.5     10157736.45
      3639719.61      10157625.5      3639503.71     10157503.42
      3639455.96     10157440.92      3639258.96     10157372.88
      3639191.09      10157324.1      3639058.69     10157321.03
      3639005.94     10157270.12      3638999.81     10157182.69
      3638936.15     10157139.48       3638866.6     10156878.99
      3638793.48     10156830.22      3638765.14     10156765.48
        3638639.     10156687.91      3638543.61     10156677.98
      3638398.79     10156597.85      3638376.57     10156479.15
      3638251.27      10156323.6      3637992.11     10156291.64

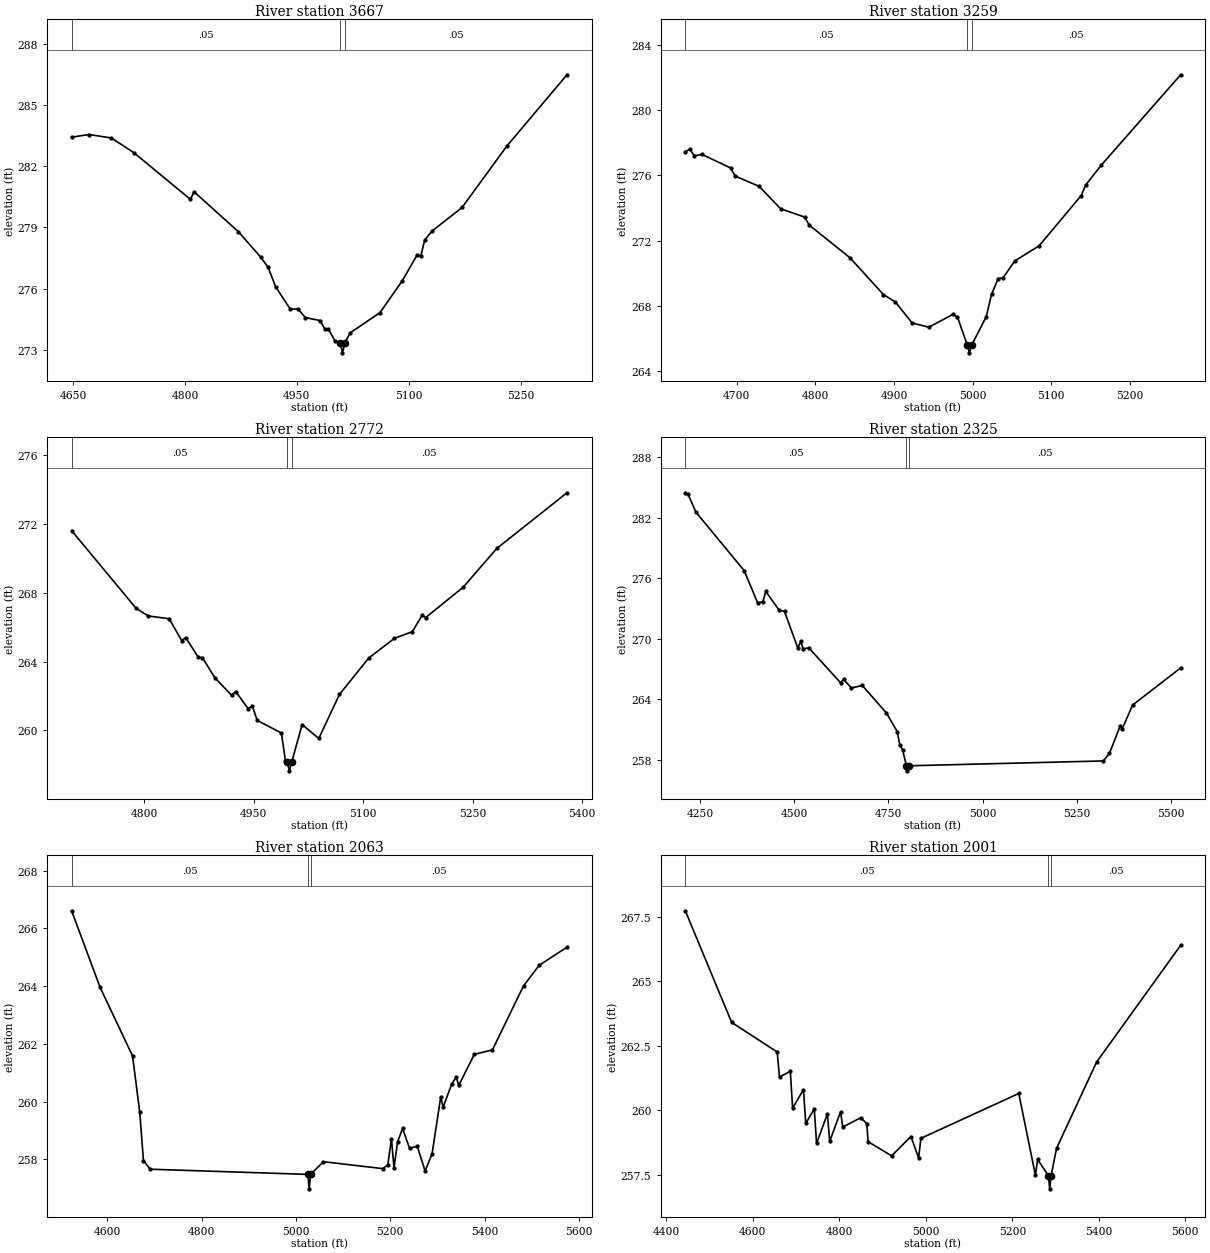
Type RM Length L Ch R = 1 ,3667    ,408,408,408
BEGIN DESCRIPTION:
UNT095 IN ROCK 8.0
END DESCRIPTION:
XS GIS Cut Line= 3
       3640612.1     10157688.27      3640622.75     10158028.48
       3640633.8     10158352.31
#Sta/Elev= 30
  4647.9  283.43  4671.3  283.56  4701.3  283.39  4731.3  282.67  4807.2  280.38
  4812.2  280.75  4871.4   278.8  4901.4  277.55  4911.4  277.05  4921.4   276.1
  4941.4  274.98  4951.4  275.01  4961.4  274.58  4981.4  274.43  4987.4  274.01
  4992.4  274.01  5001.5  273.41  5008.5  273.35  5011.2  272.85  5014.5  273.35
  5021.5  273.83  5061.5  274.82  5091.5  276.39  5111.3  277.65  5116.3   277.6
  5121.5  278.39  5131.5  278.83  5171.6  279.98  5231.6  282.99  5312.3  286.49
#Mann= 3 ,-1 , 0
  4647.9     .05       0  5008.5     .03       0  5014.5     .05       0
Bank Sta=5008.5,5014.5
XS Rating Curve= 0 ,0
Exp/Cntr=0.3,0.1

Type RM Length L Ch R = 1 ,3259    ,486,486,486
BEGIN DESCRIPTION:
UNT095 IN ROCK 7.0
END DESCRIPTION:
XS GIS Cut Line= 3
      3640460.17      10157631.9      3640220.85     10158012.85
       3640242.1     10158191.61
#Sta/Elev= 30
  4634.6  277.45  4640.3   277.6  4646.2   277.2  4655.6  277.29  4692.1  276.46
    4698  275.96  4728.6  275.33  4755.7  273.96  4786.3  273.45  4792.2  272.96
    4844  270.96  4886.5  268.71  4901.8  268.25    4923  266.97  4944.2  266.71
  4974.8  267.49  4980.7  267.33    4993  265.64  4995.8  265.14    4999  265.64
  5017.2  267.34    5024  268.72  5032.5  269.69  5038.4  269.72  5053.7  270.77
  5084.5  271.69  5138.1  274.77  5143.7  275.41  5163.8  276.64  5264.5  282.16
#Mann= 3 ,-1 , 0
  4634.6     .05       0    4993     .03       0    4999     .05       0
Bank Sta=4993,4999
XS Rating Curve= 0 ,0
Exp/Cntr=0.3,0.1

Type RM Length L Ch R = 1 ,2772    ,447,447,447
BEGIN DESCRIPTION:
UNT095 IN ROCK 6.0
END DESCRIPTION:
XS GIS Cut Line= 3
      3640092.09     10157441.67      3639894.01     10157861.73
      3639935.51     10158071.85
#Sta/Elev= 30
  4700.5  271.61  4788.9  267.09  4805.7  266.65  4834.1  266.49  4851.3  265.22
  4856.8  265.39  4874.1  264.25  4879.6  264.23  4896.9  263.05  4919.6  262.04
  4925.2  262.26  4942.4  261.26  4947.9  261.43  4954.8  260.58  4987.9  259.85
  4993.5  258.21    4996  258.15  4998.8  257.65    5002  258.15  5016.3  260.34
  5039.1  259.53  5067.4  262.09  5107.4   264.2  5142.7  265.35  5167.4  265.74
  5180.5  266.68  5185.6  266.56  5236.9  268.32  5283.1  270.58  5379.1  273.81
#Mann= 3 ,-1 , 0
  4700.5     .05       0    4996     .03       0    5002     .05       0
Bank Sta=4996,5002
XS Rating Curve= 0 ,0
Exp/Cntr=0.3,0.1

Type RM Length L Ch R = 1 ,2325    ,262,262,262
BEGIN DESCRIPTION:
UNT095 IN ROCK 5.0
END DESCRIPTION:
XS GIS Cut Line= 3
      3640092.11     10156941.64      3639518.35     10157657.91
      3639598.88     10158046.62
#Sta/Elev= 30
  4211.2  284.46  4218.4  284.33  4239.2  282.55  4367.3  276.76  4403.4  273.54
  4416.9  273.69  4424.9  274.69  4460.1  272.84  4474.5  272.71  4509.7   269.1
  4517.7  269.75  4524.1  268.98  4538.5  269.12  4623.3  265.65  4631.3  265.98
  4652.2  265.14    4681  265.38    4745  262.66  4773.8  260.81  4780.2  259.53
  4787.8  259.02    4798  257.43  4800.8  256.93    4804  257.43  5320.8  257.91
    5337  258.67  5365.9  261.41    5371   261.1  5398.3  263.44  5525.9  267.12
#Mann= 3 ,-1 , 0
  4211.2     .05       0    4798    .033       0    4804     .05       0
Bank Sta=4798,4804
XS Rating Curve= 0 ,0
Exp/Cntr=0.3,0.1

Type RM Length L Ch R = 1 ,2063    ,63,63,63
BEGIN DESCRIPTION:
Mapping XS ffb31b52
END DESCRIPTION:
XS GIS Cut Line= 4
       3639783.3     10157172.04      3639425.26     10157336.95
      3639357.99      10157471.5      3639503.38      10157955.4
#Sta/Elev= 30
  4524.6  266.61  4584.9  263.96  4653.8  261.58    4669  259.63  4676.8  257.96
  4691.1  257.66  5025.4  257.48  5028.1  256.98  5031.4  257.48  5058.2  257.92
  5184.2  257.68  5194.7  257.81  5202.5  258.71  5207.8  257.71  5215.6  258.61
    5226  259.07  5240.8  258.39  5257.3  258.45  5273.8   257.6  5288.6  258.19
  5306.9  260.16  5312.1  259.81  5330.4  260.62  5339.9  260.85  5345.1  260.56
  5378.2  261.64  5416.4  261.79  5482.5  264.01  5515.5  264.72  5574.5  265.35
#Mann= 3 ,-1 , 0
  4524.6     .05       0  5025.4    .033       0  5031.4     .05       0
Bank Sta=5025.4,5031.4
XS Rating Curve= 0 ,0
Exp/Cntr=0.3,0.1

Type RM Length L Ch R = 1 ,2001    ,61,61,61
BEGIN DESCRIPTION:
Mapping XS 89a90cd5
END DESCRIPTION:
XS GIS Cut Line= 4
       3639772.5     10157111.25      3639375.35     10157258.83
      3639308.08     10157454.14      3639418.66     10157957.17
#Sta/Elev= 30
  4443.9  267.74    4551  263.41  4656.3  262.26  4661.7  261.29  4686.7  261.51
    4692  260.08  4717.1   260.8  4722.4  259.49  4742.1  260.05  4747.4  258.71
  4772.4  259.86  4777.8  258.79  4802.8  259.94  4808.1  259.35  4849.7  259.71
  4863.5  259.48  4866.6  258.78  4920.9  258.23  4965.7  258.98  4983.3  258.15
  4988.6  258.91  5214.9  260.65  5253.4  257.48  5258.5  258.09  5283.6  257.45
  5286.4  256.95  5289.6  257.45  5302.2  258.52  5394.9  261.87  5589.2   266.4
#Mann= 3 ,-1 , 0
  4443.9     .05       0  5283.6     .03       0  5289.6     .05       0
Bank Sta=5283.6,5289.6
XS Rating Curve= 0 ,0
Exp/Cntr=0.3,0.1

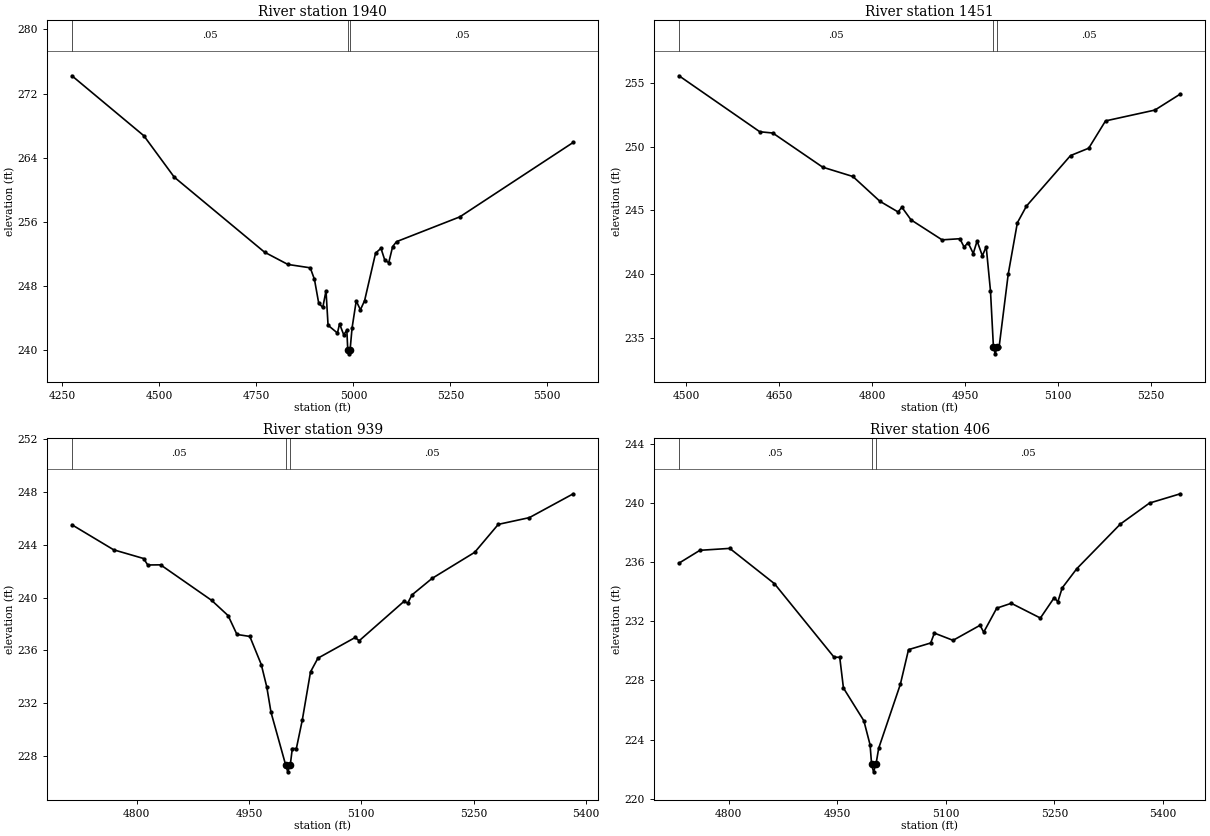
Type RM Length L Ch R = 1 ,1940    ,482,482,482
BEGIN DESCRIPTION:
UNT095 IN ROCK 4.0
END DESCRIPTION:
XS GIS Cut Line= 4
      3639802.86     10156915.95      3639334.12     10157219.76
      3639249.99     10157429.26      3639290.71     10157935.88
#Sta/Elev= 30
  4274.3  274.22  4459.7  266.75  4538.1  261.59  4770.9  252.24  4831.1  250.71
  4888.8  250.29  4899.6  248.85  4910.6  245.88  4921.1  245.35  4929.4  247.43
  4934.7  243.13  4958.9  242.16  4964.3  243.32    4975  241.95  4983.1  242.51
  4985.5  240.07  4988.3  239.57  4991.5  240.07  4996.6   242.8  5007.3  246.16
  5018.1  245.06  5028.9   246.2  5057.2  252.12  5071.1  252.72  5081.1  251.23
  5091.1  250.93  5101.2  252.93  5111.2  253.55  5274.5  256.64  5566.9  265.92
#Mann= 3 ,-1 , 0
  4274.3     .05       0  4985.5     .03       0  4991.5     .05       0
Bank Sta=4985.5,4991.5
XS Rating Curve= 0 ,0
Exp/Cntr=0.3,0.1

Type RM Length L Ch R = 1 ,1451    ,512,512,512
BEGIN DESCRIPTION:
UNT095 IN ROCK 3.0
END DESCRIPTION:
XS GIS Cut Line= 3
      3639353.38     10156841.96      3639128.74     10156996.16
       3638693.7     10157310.68
#Sta/Elev= 30
  4488.3  255.56  4618.7  251.17  4639.7  251.07  4720.3  248.39    4769  247.66
  4812.5  245.72  4841.9  244.88  4848.1  245.25  4862.8  244.26    4913  242.69
  4941.7  242.78  4948.6  242.12  4954.8  242.48  4963.3  241.62  4969.5   242.6
    4978  241.44  4984.2  242.15  4991.1  238.69  4995.9  234.25  4998.7  233.75
  5001.9  234.25  5005.1  234.31  5019.8  240.02  5034.5  244.03  5049.2  245.34
  5120.3   249.3  5149.7  249.88  5176.8  252.02  5256.5  252.87  5297.6  254.13
#Mann= 3 ,-1 , 0
  4488.3     .05       0  4995.9    .035       0  5001.9     .05       0
Bank Sta=4995.9,5001.9
XS Rating Curve= 0 ,0
Exp/Cntr=0.3,0.1

Type RM Length L Ch R = 1 ,939     ,533,533,533
BEGIN DESCRIPTION:
UNT095 IN ROCK 2.0
END DESCRIPTION:
XS GIS Cut Line= 3
      3638819.55     10156473.05      3638692.11     10156741.64
      3638581.06     10157097.32
#Sta/Elev= 30
  4713.3  245.53  4769.1  243.63  4809.1  242.97  4814.6  242.48  4831.8  242.49
  4899.9   239.8    4922  238.64  4933.8  237.21    4951  237.06  4966.3  234.93
  4973.7  233.22  4979.3  231.31    4999  227.29  5001.7  226.79    5005  227.29
  5007.8  228.56  5013.2  228.56  5021.1  230.71  5032.1  234.37    5042  235.41
  5091.8  236.98  5097.1  236.73  5156.8  239.71    5162  239.59  5167.7  240.21
  5194.5  241.46  5251.5  243.44    5283  245.56  5324.5  246.07  5383.2  247.88
#Mann= 3 ,-1 , 0
  4713.3     .05       0    4999    .035       0    5005     .05       0
Bank Sta=4999,5005
XS Rating Curve= 0 ,0
Exp/Cntr=0.3,0.1

Type RM Length L Ch R = 1 ,406     ,0,0,0
BEGIN DESCRIPTION:
UNT095 IN ROCK 1.0
END DESCRIPTION:
XS GIS Cut Line= 3
      3638389.88     10156173.51      3638302.66     10156534.51
       3638333.4     10156854.05
#Sta/Elev= 30
  4731.5  235.95  4760.4  236.82  4801.6  236.95  4863.3  234.56  4945.6  229.58
  4953.5  229.57  4958.6  227.49  4986.8  225.27  4995.4  223.64  4997.5  222.31
  5000.2  221.81  5003.5  222.31  5007.3  223.41  5037.2  227.74  5048.5  230.09
  5079.1  230.54  5084.2  231.21    5110  230.72  5147.3  231.74  5152.3  231.27
  5170.3   232.9  5190.4  233.23  5230.6  232.23  5249.7  233.61  5254.7  233.33
  5260.7  234.27  5280.8  235.57  5341.1   238.6  5381.3  240.02  5423.9  240.65
#Mann= 3 ,-1 , 0
  4731.5     .05       0  4997.5     .03       0  5003.5     .05       0
Bank Sta=4997.5,5003.5
XS Rating Curve= 0 ,0
Exp/Cntr=0.3,0.1
Stream Node=UNT095 IN ROCK  ,Reach-1         , 0 , 0 ,Upstream end
Stream Node=UNT095 IN ROCK  ,Reach-1         , 0 , 1 ,Downstream end

Chan Stop Cuts=-1
Use User Specified Reach Order=0
Composite Channel Slope=5