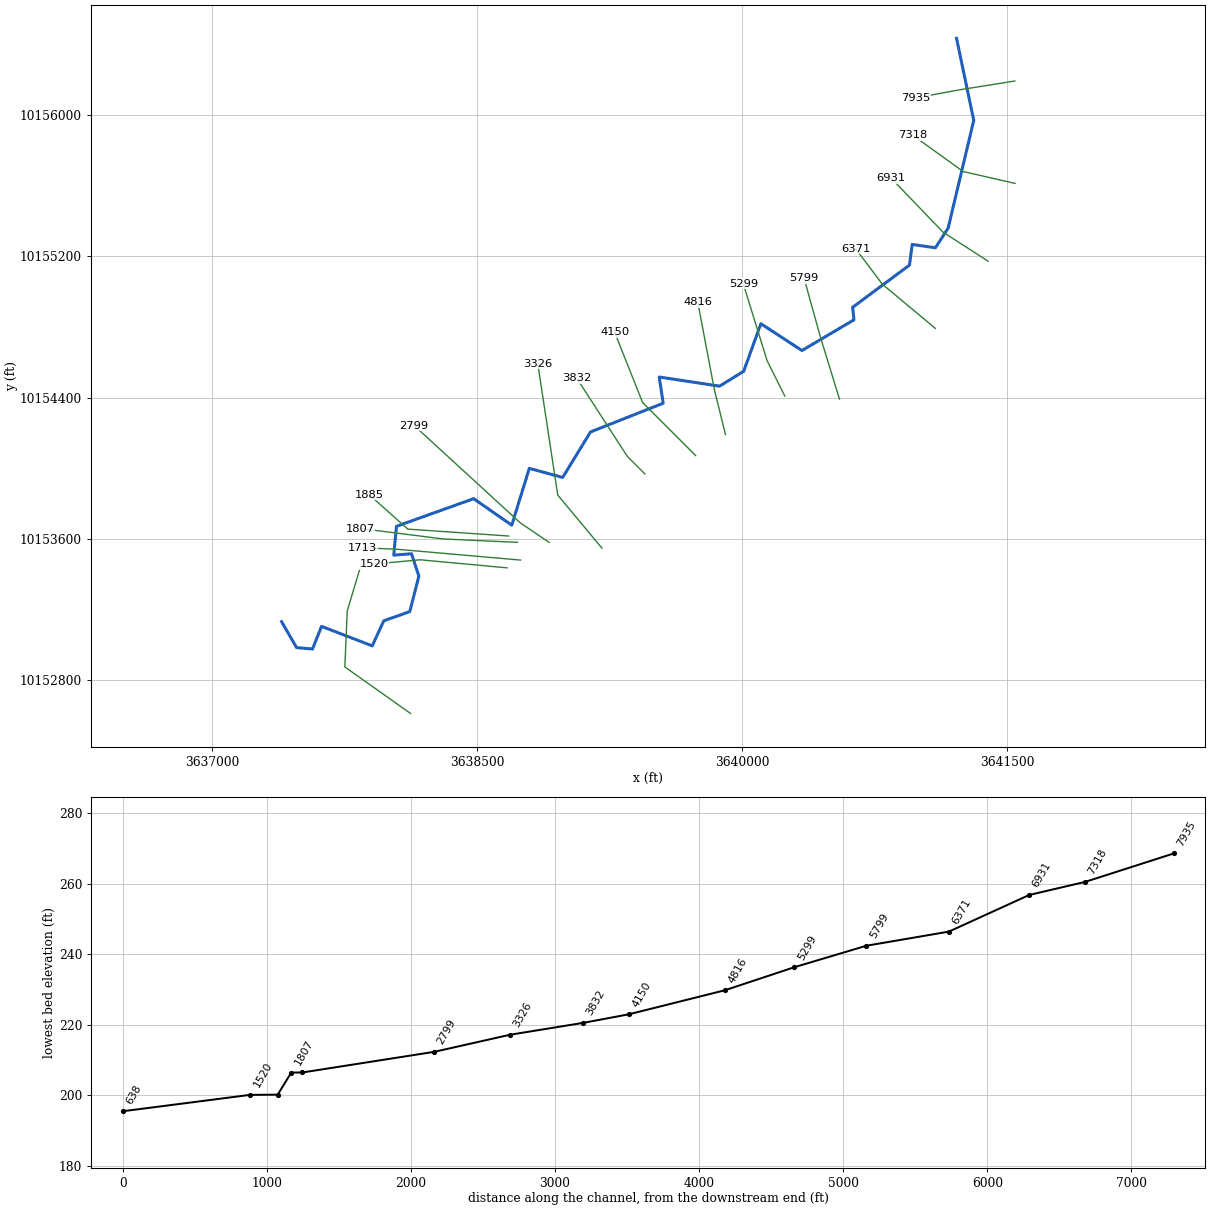
--- UNT096 IN ROCK.prj (project) ---

Proj Title=UNT096 IN ROCK Base Level Engineering
Current Plan=p01
Default Exp/Contr=0.3,0.1
English Units
Geom File=g01
Flow File=f01
Plan File=p01
Y Axis Title=Elevation
X Axis Title(PF)=Main Channel Distance
X Axis Title(XS)=Station
BEGIN DESCRIPTION:
UNT096 IN ROCK
END DESCRIPTION:
DSS Export Rating Curves= 0
DSS Export Rating Curve Sorted= 0
DSS Export Volume Flow Curves= 0
DXF OffsetX= 0
DXF OffsetY= 0
DXF ScaleX= 1
DXF ScaleY= 10

--- UNT096 IN ROCK.p01 (plan) ---

Plan Title=Multiple Run
Short Identifier=Multiple
Geom File=g01
Flow File=f01
Subcritical Flow
K Sum by GR= 0
Std Step Tol= 0.01
Critical Tol= 0.01
Num of Std Step Trials= 20
Max Error Tol= 0.3
Flow Tol Ratio= 0.001
Split Flow NTrial= 30
Split Flow Tol= 0.02
Split Flow Ratio= 0.02
Log Output Level= 0
Friction Slope Method= 1
Unsteady Friction Slope Method= 2
Unsteady Bridges Friction Slope Method= 1
Parabolic Critical Depth
Global Vel Dist=  1 , 1 , 1
Global Log Level= 0
CheckData=True
Encroach Param= -1, 0, 0, 0
BEGIN DESCRIPTION:
Multiple Run
END DESCRIPTION:

--- UNT096 IN ROCK.f01 (steady flow) ---

Flow Title=Multiple
Program Version=4.10
Number of Profiles= 7
Profile Names=10-year,25-year,50-year,1pct_min,100-year,1pct_plu,500-year
River Rch & RM=UNT096 IN ROCK,Reach-1         ,7935
     280     360     422     365     494     668     674
Boundary for River Rch & Prof#=UNT096 IN ROCK,Reach-1         , 1
Up Type= 0
Dn Type= 3
Dn Slope=0.009
Boundary for River Rch & Prof#=UNT096 IN ROCK,Reach-1         , 2
Up Type= 0
Dn Type= 3
Dn Slope=0.009
Boundary for River Rch & Prof#=UNT096 IN ROCK,Reach-1         , 3
Up Type= 0
Dn Type= 3
Dn Slope=0.009
Boundary for River Rch & Prof#=UNT096 IN ROCK,Reach-1         , 4
Up Type= 0
Dn Type= 3
Dn Slope=0.009
Boundary for River Rch & Prof#=UNT096 IN ROCK,Reach-1         , 5
Up Type= 0
Dn Type= 3
Dn Slope=0.009
Boundary for River Rch & Prof#=UNT096 IN ROCK,Reach-1         , 6
Up Type= 0
Dn Type= 3
Dn Slope=0.009
Boundary for River Rch & Prof#=UNT096 IN ROCK,Reach-1         , 7
Up Type= 0
Dn Type= 3
Dn Slope=0.009
DSS Import GetInterval= 0
DSS Import GetPeak= 0
DSS Import FillOption= 0

--- UNT096 IN ROCK.g01 (geometry) ---

Geom Title=Existing Conditions
Program Version=4.10

River Reach=UNT096 IN ROCK  ,Reach-1
Reach XY= 30
      3641212.22      10156433.1      3641309.64     10155969.02
      3641164.67     10155358.78      3641092.62     10155247.66
      3640961.33     10155266.59      3640945.92     10155149.57
      3640624.13     10154910.82      3640631.66     10154839.87
      3640337.16     10154666.12       3640104.8       10154818.
      3640007.46     10154548.71      3639870.86      10154464.5
      3639529.38     10154516.22      3639551.95     10154367.78
      3639140.63     10154205.35      3638982.95     10153947.63
      3638794.28     10153999.33      3638694.96     10153677.83
      3638479.08     10153827.56      3638042.45     10153671.31
      3638026.83     10153508.12      3638127.52     10153515.93
      3638169.19     10153390.06      3638117.61      10153188.4
       3637970.4     10153136.36      3637905.09      10152994.5
      3637618.18     10153105.07      3637567.01     10152976.71
      3637477.05     10152984.61      3637392.11     10153131.64

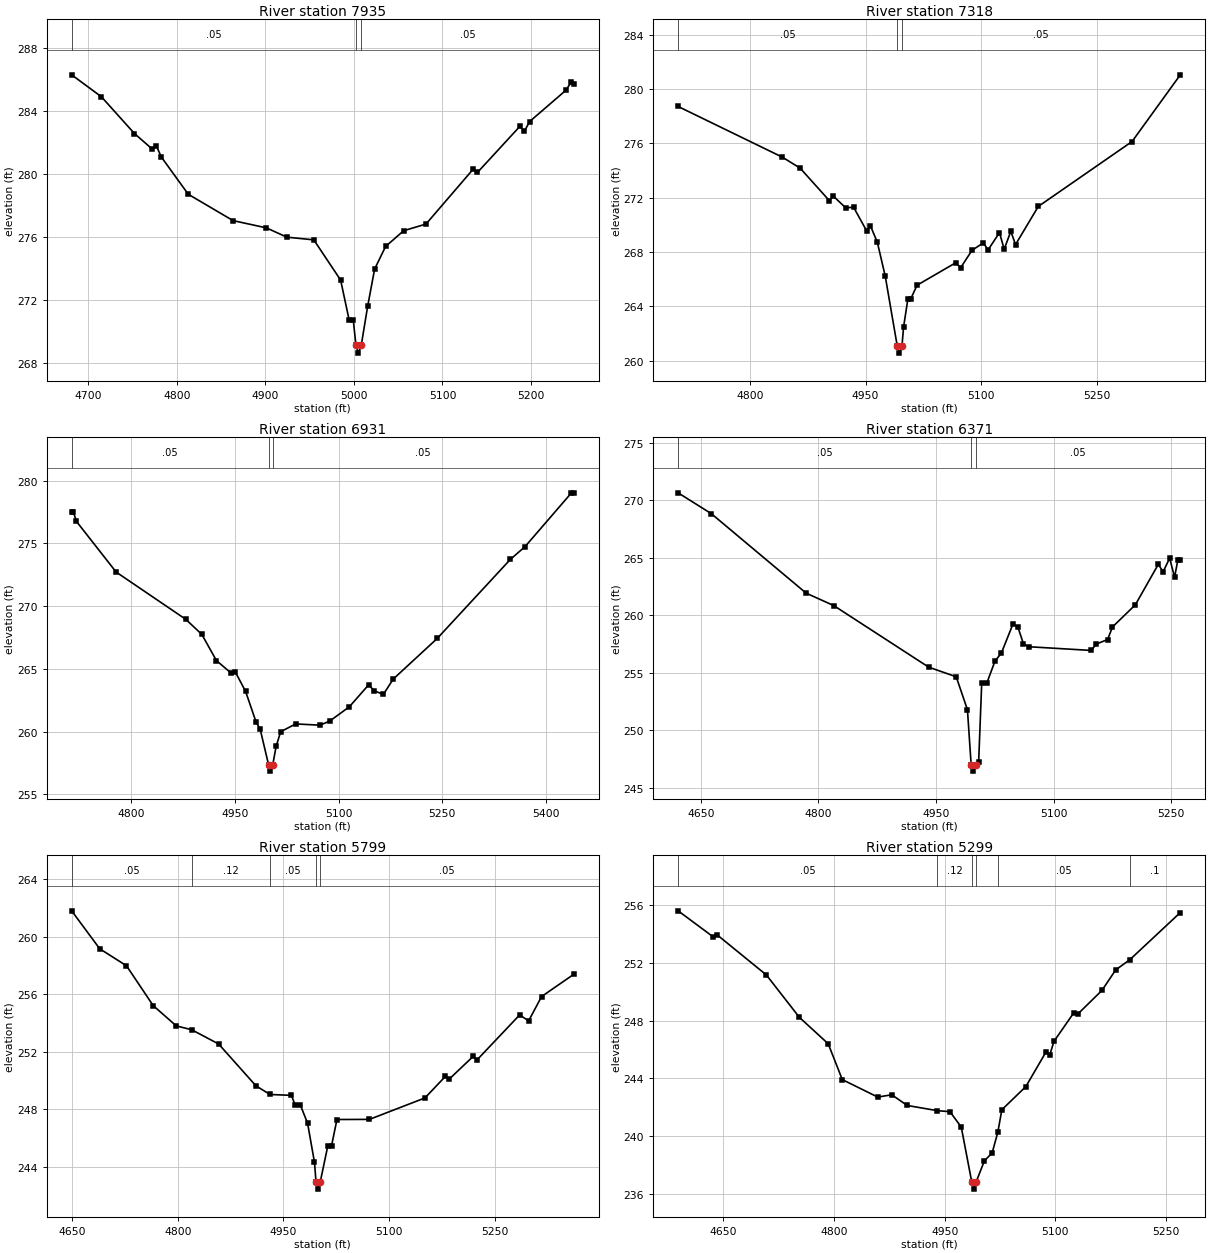
Type RM Length L Ch R = 1 ,7935    ,617,617,617
BEGIN DESCRIPTION:
UNT096 IN ROCK 14.0
END DESCRIPTION:
XS GIS Cut Line= 3
      3641542.15     10156191.65        3641228.     10156141.51
      3640983.06     10156096.32
#Sta/Elev= 30
  4681.2  286.29  4714.8   284.9  4752.1  282.57  4771.9   281.6  4776.9  281.78
  4782.5  281.08  4812.9  278.72  4863.5  277.05  4901.1  276.59  4924.3     276
  4954.7  275.83    4985  273.28  4994.7  270.73  4999.3  270.73  5002.3  269.15
  5005.1  268.65  5008.3  269.15  5015.5  271.61  5023.4  273.98  5035.8  275.41
  5056.2  276.41  5081.4  276.83  5134.4  280.29  5139.5   280.1  5187.4  283.02
  5192.5  282.71  5198.5  283.33  5239.2   285.3  5245.4  285.82  5248.4  285.69
#Mann= 3 ,-1 , 0
  4681.2     .05       0  5002.3     .03       0  5008.3     .05       0
Bank Sta=5002.3,5008.3
XS Rating Curve= 0 ,0
Exp/Cntr=0.3,0.1

Type RM Length L Ch R = 1 ,7318    ,387,387,387
BEGIN DESCRIPTION:
UNT096 IN ROCK 13.0
END DESCRIPTION:
XS GIS Cut Line= 3
      3641543.77     10155612.06        3641250.     10155679.09
      3640966.49     10155883.27
#Sta/Elev= 30
  4707.2  278.71  4842.2  274.98  4865.3  274.17  4903.1  271.78  4908.3  272.11
  4924.3  271.25  4934.6  271.29  4951.3  269.57  4956.4  269.92  4965.3  268.72
  4975.6  266.21  4991.2  261.05    4994  260.55  4997.2  261.05  4999.4   262.5
  5004.9  264.53  5008.5  264.53  5016.8  265.55  5067.1  267.21  5073.2  266.83
    5088  268.12  5102.7  268.67  5108.8  268.15  5123.6  269.42  5129.7   268.2
  5138.3  269.52  5144.4  268.54  5173.9  271.35  5295.4  276.13  5357.9  281.04
#Mann= 3 ,-1 , 0
  4707.2     .05       0  4991.2     .03       0  4997.2     .05       0
Bank Sta=4991.2,4997.2
XS Rating Curve= 0 ,0
Exp/Cntr=0.3,0.1

Type RM Length L Ch R = 1 ,6931    ,558,558,558
BEGIN DESCRIPTION:
UNT096 IN ROCK 12.0
END DESCRIPTION:
XS GIS Cut Line= 3
      3641391.19     10155171.71      3641135.98     10155335.96
      3640842.13     10155641.62
#Sta/Elev= 30
  4713.3   277.5  4715.7   277.5  4720.3  276.74  4777.7  272.71  4878.7  268.94
  4901.9  267.74    4923  265.66  4944.1  264.67  4950.1  264.78  4965.3   263.2
  4980.4  260.77  4986.4  260.19  4998.6  257.35  5001.3  256.85  5004.6  257.35
  5009.5  258.82  5016.1  259.99  5037.8  260.61  5073.1  260.51  5087.2  260.84
  5115.5  261.97  5143.8  263.74  5150.8  263.27  5164.9  262.96  5179.1  264.18
  5242.9  267.42  5348.9  273.72  5370.2  274.74  5437.4  279.02  5440.8  279.02
#Mann= 3 ,-1 , 0
  4713.3     .05       0  4998.6     .03       0  5004.6     .05       0
Bank Sta=4998.6,5004.6
XS Rating Curve= 0 ,0
Exp/Cntr=0.3,0.1

Type RM Length L Ch R = 1 ,6371    ,572,572,572
BEGIN DESCRIPTION:
UNT096 IN ROCK 11.0
END DESCRIPTION:
XS GIS Cut Line= 3
      3641092.08     10154791.66      3640792.11     10155041.64
       3640642.1     10155241.66
#Sta/Elev= 30
  4621.2  270.63  4663.5  268.82  4784.5  261.91  4819.7  260.83  4940.7  255.48
  4975.9  254.64  4990.2  251.78    4995  246.94  4997.8  246.44    5001  246.94
  5004.5  247.22  5008.4  254.07  5014.8  254.07  5025.2  255.98  5033.6  256.72
  5048.1   259.2  5054.4     259  5061.7  257.49    5069  257.25  5148.1  256.93
  5154.4  257.48    5169  257.88  5175.2  258.97  5204.4   260.9  5233.6  264.41
  5239.8  263.77  5248.1  264.95  5254.4  263.29  5258.6  264.82  5261.7  264.82
#Mann= 3 ,-1 , 0
  4621.2     .05       0    4995    .035       0    5001     .05       0
Bank Sta=4995,5001
XS Rating Curve= 0 ,0
Exp/Cntr=0.3,0.1

Type RM Length L Ch R = 1 ,5799    ,500,500,500
BEGIN DESCRIPTION:
UNT096 IN ROCK 10.0
END DESCRIPTION:
XS GIS Cut Line= 3
      3640549.72     10154391.34      3640442.11     10154741.64
      3640349.18      10155075.8
#Sta/Elev= 30
  4649.3  261.79  4689.2  259.15  4727.2  257.97  4765.1   255.2  4797.9  253.79
  4819.9  253.52  4858.1  252.53  4911.1  249.62  4931.1  249.02  4961.5  248.96
  4966.7  248.29  4973.9  248.32  4984.4  247.02  4994.2  244.31  4996.4  242.94
  4999.1  242.44  5002.4  242.94  5013.1  245.44  5018.4  245.44  5026.1  247.28
  5072.3  247.29  5151.1  248.78  5180.2  250.28  5185.4  250.08  5219.6  251.67
  5224.8  251.41  5285.6  254.55  5298.4  254.14  5316.8  255.83  5362.6  257.38
#Mann= 5 ,-1 , 0
  4649.3     .05       0  4819.9     .12       0  4931.1     .05       0
  4996.4     .03       0  5002.4     .05       0
Bank Sta=4996.4,5002.4
XS Rating Curve= 0 ,0
Exp/Cntr=0.3,0.1

Type RM Length L Ch R = 1 ,5299    ,483,483,483
BEGIN DESCRIPTION:
UNT096 IN ROCK 9.0
END DESCRIPTION:
XS GIS Cut Line= 3
      3640240.07     10154408.51      3640140.06     10154608.53
      3640004.74     10155045.32
#Sta/Elev= 30
  4588.5   255.6  4635.5  253.82  4641.1  253.95  4708.2  251.16  4752.9  248.23
    4792   246.4  4811.1  243.92  4859.2  242.71  4878.2  242.87  4899.1  242.13
    4940  241.77    4957   241.7  4972.4  240.64  4986.6  236.84  4989.3  236.34
  4992.6  236.84  5003.8   238.3  5014.3  238.85    5022  240.28  5027.4  241.83
    5060  243.44  5087.4  245.84  5092.6  245.65    5098  246.56  5125.2  248.56
  5130.5  248.46  5163.1  250.09  5181.8  251.51    5201  252.22  5269.4  255.48
#Mann= 6 ,-1 , 0
  4588.5     .05       0    4940     .12       0  4986.6     .07       0
  4992.6     .12       0    5022     .05       0    5201      .1       0
Bank Sta=4986.6,4992.6
XS Rating Curve= 0 ,0
Exp/Cntr=0.3,0.1

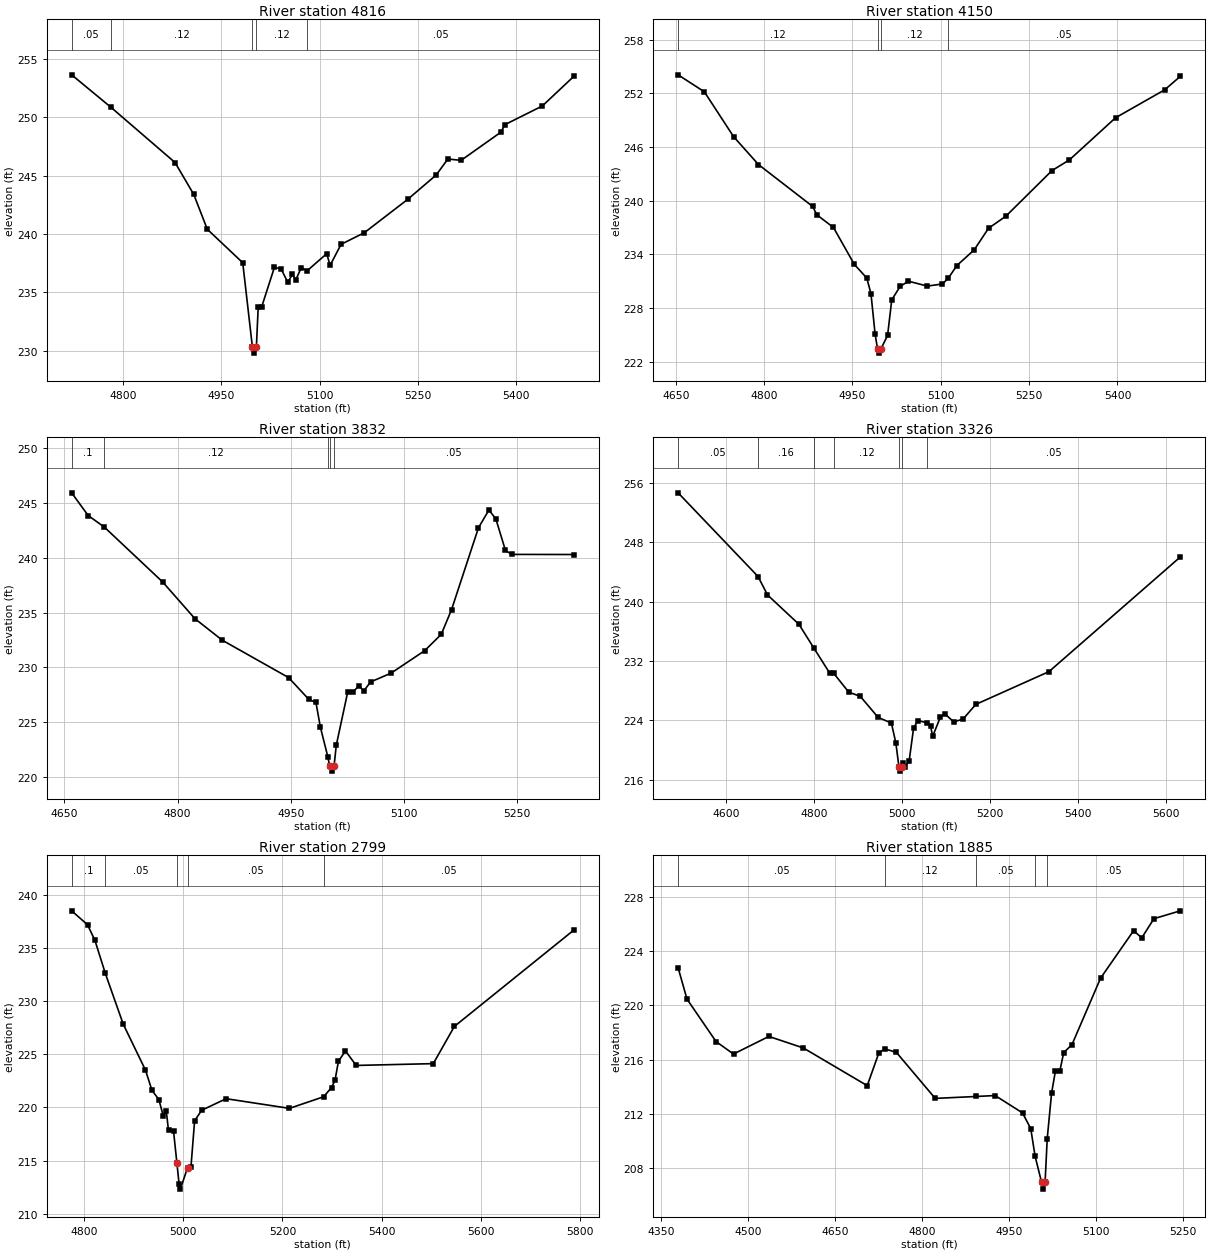
Type RM Length L Ch R = 1 ,4816    ,666,666,666
BEGIN DESCRIPTION:
UNT096 IN ROCK 8.0
END DESCRIPTION:
XS GIS Cut Line= 3
      3639904.47     10154190.74      3639842.11     10154441.64
      3639747.52     10154940.62
#Sta/Elev= 30
  4721.6  253.65  4781.5  250.87  4879.4  246.13    4908  243.39  4928.6  240.41
  4982.7  237.54  4997.5  230.29  5000.2  229.79  5003.5  230.29  5006.3  233.73
  5011.4  233.72    5031  237.14  5041.2  237.02  5051.4  235.86  5058.6  236.54
  5063.7  236.07  5071.7  237.08  5081.4  236.87  5110.9  238.32    5116  237.31
  5132.8  239.12  5168.2  240.11  5234.6  242.98  5277.9  245.06  5295.7  246.43
    5316  246.32  5377.1  248.75  5382.5  249.37  5439.9  250.98    5488  253.52
#Mann= 5 ,-1 , 0
  4721.6     .05       0  4781.5     .12       0  4997.5     .07       0
  5003.5     .12       0  5081.4     .05       0
Bank Sta=4997.5,5003.5
XS Rating Curve= 0 ,0
Exp/Cntr=0.3,0.1

Type RM Length L Ch R = 1 ,4150    ,318,318,318
BEGIN DESCRIPTION:
UNT096 IN ROCK 7.0
END DESCRIPTION:
XS GIS Cut Line= 3
      3639735.44     10154071.88      3639435.43     10154371.88
      3639276.89       10154770.
#Sta/Elev= 30
  4653.9  254.07  4698.5  252.17    4748  247.17  4790.4  244.04  4882.4  239.36
  4889.4  238.43  4917.7  237.01  4953.1  232.89  4974.3  231.36  4981.4  229.61
  4988.4   225.1  4992.5  223.47  4995.3  222.97  4998.5  223.47  5009.6  224.95
  5016.7  228.93  5030.9  230.42    5045  231.01    5077  230.46  5102.7   230.7
  5112.7  231.34    5127  232.74  5156.7  234.51    5181  236.92  5210.6  238.28
  5288.8  243.37  5318.5  244.57  5396.7  249.27  5480.3   252.4  5506.7   253.9
#Mann= 4 ,-1 , 0
  4653.9     .12       0  4992.5     .07       0  4998.5     .12       0
  5112.7     .05       0
Bank Sta=4992.5,4998.5
XS Rating Curve= 0 ,0
Exp/Cntr=0.3,0.1

Type RM Length L Ch R = 1 ,3832    ,506,506,506
BEGIN DESCRIPTION:
UNT096 IN ROCK 6.0
END DESCRIPTION:
XS GIS Cut Line= 3
      3639448.76     10153967.27      3639348.78     10154067.25
      3639063.79     10154507.82
#Sta/Elev= 30
  4659.5  245.93  4681.4  243.86  4702.9   242.8  4780.4  237.78  4823.2  234.43
  4859.5  232.47  4947.2  229.07  4974.2  227.07  4983.5   226.8  4989.4  224.55
  4999.4   221.8  5001.6  221.03  5004.3  220.53  5007.6  221.03  5010.5  222.89
  5025.7  227.76  5032.4  227.75  5040.8  228.32  5046.8  227.83    5056  228.67
  5083.1  229.47  5127.7  231.52  5149.7  233.01  5163.4  235.27  5199.1  242.74
    5213  244.37  5222.2  243.54  5234.9  240.67  5243.3  240.31  5325.6   240.3
#Mann= 5 ,-1 , 0
  4659.5      .1       0  4702.9     .12       0  4999.4     .05       0
  5001.6     .03       0  5007.6     .05       0
Bank Sta=5001.6,5007.6
XS Rating Curve= 0 ,0
Exp/Cntr=0.3,0.1

Type RM Length L Ch R = 1 ,3326    ,527,527,527
BEGIN DESCRIPTION:
UNT096 IN ROCK 5.0
END DESCRIPTION:
XS GIS Cut Line= 3
      3639205.17     10153547.79      3638955.19     10153847.77
      3638842.11     10154591.64
#Sta/Elev= 30
  4490.5  254.65  4672.4  243.38  4693.9   240.9  4765.5  236.94  4799.9   233.7
  4835.8  230.34  4844.9  230.32  4878.8  227.81  4905.1  227.24  4945.6  224.41
  4975.9  223.64  4986.1  220.94  4993.2  217.67  4995.9  217.17  4999.2  217.67
  5001.3  218.33  5006.3  217.67  5016.4   218.6  5026.5  223.01  5036.6  223.98
  5057.9  223.66  5064.9  223.27  5069.9  221.87  5087.2  224.42  5097.3   224.9
  5117.5  223.81  5138.6  224.16  5168.1  226.16  5334.5  230.57  5633.4  246.01
#Mann= 7 ,-1 , 0
  4490.5     .05       0  4672.4     .16       0  4799.9      .1       0
  4844.9     .12       0  4993.2     .07       0  4999.2     .12       0
  5057.9     .05       0
Bank Sta=4993.2,4999.2
XS Rating Curve= 0 ,0
Exp/Cntr=0.3,0.1

Type RM Length L Ch R = 1 ,2799    ,914,914,914
BEGIN DESCRIPTION:
UNT096 IN ROCK 4.0
END DESCRIPTION:
XS GIS Cut Line= 3
      3638906.09     10153580.34      3638742.11     10153691.64
      3638142.13     10154241.62
#Sta/Elev= 30
  4775.1   238.5  4807.1  237.19  4822.1  235.71  4842.9  232.62    4879  227.84
  4923.8  223.52    4937   221.6  4950.9  220.74  4959.8  219.19  4965.8  219.66
  4970.3  217.83  4980.4  217.78  4987.2  214.77  4991.6  212.81  4994.3  212.31
  5008.7  214.34  5015.5  214.36  5022.9  218.74  5037.1  219.73  5086.4  220.82
  5214.1  219.91  5282.8     221  5298.9  221.87    5306  222.58  5312.7  224.33
  5326.9  225.32  5348.5  223.95  5503.9  224.12  5546.4  227.62  5787.2  236.69
#Mann= 5 ,-1 , 0
  4775.1      .1       0  4842.9     .05       0  4987.2    .035       0
  5008.7     .05       0  5282.8     .05       0
Bank Sta=4987.2,5008.7
XS Rating Curve= 0 ,0
Exp/Cntr=0.3,0.1

Type RM Length L Ch R = 1 ,1885    ,78,78,78
BEGIN DESCRIPTION:
Mapping XS 4e0a73cb
END DESCRIPTION:
XS GIS Cut Line= 3
      3638677.36     10153616.26      3638106.61     10153655.32
       3637887.4     10153850.65
#Sta/Elev= 30
  4379.2  222.78  4394.5  220.47  4444.6  217.34  4474.7  216.42  4535.6  217.72
    4595  216.87  4705.2  214.09  4725.3  216.51  4735.4   216.8  4755.3  216.55
  4822.4  213.15  4892.3  213.29  4925.7  213.36  4972.9  212.08  4987.1  210.92
  4994.6  208.88  5005.8  206.96  5008.6  206.46  5011.8  206.96  5015.5  210.19
    5023  213.54  5029.7  215.19  5037.2  215.17  5043.9  216.53  5058.1  217.11
  5107.5  222.02  5164.3  225.51  5178.5  224.99  5199.4   226.4  5244.9  226.98
#Mann= 5 ,-1 , 0
  4379.2     .05       0  4735.4     .12       0  4892.3     .05       0
  4994.6    .035       0  5015.5     .05       0
Bank Sta=5005.8,5011.8
XS Rating Curve= 0 ,0
Exp/Cntr=0.3,0.1

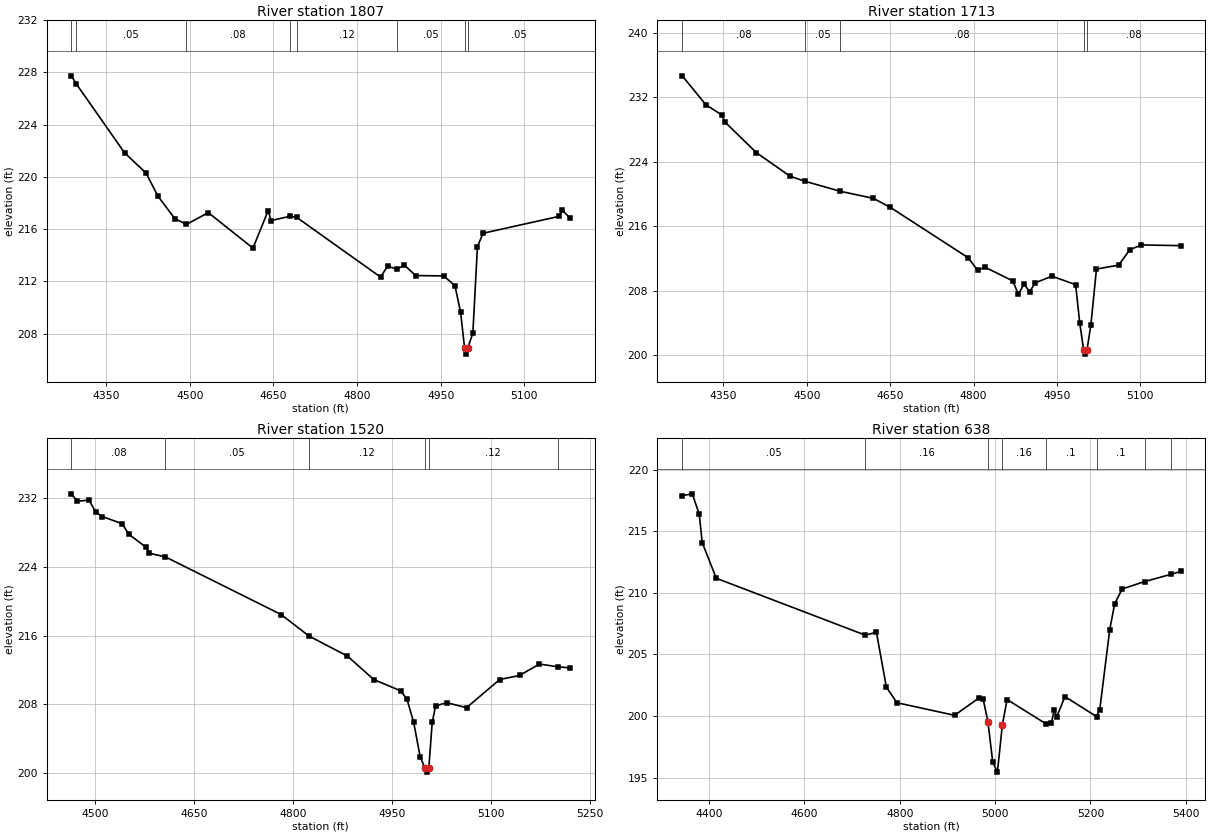
Type RM Length L Ch R = 1 ,1807    ,94,94,94
BEGIN DESCRIPTION:
UNT096 IN ROCK 3.0
END DESCRIPTION:
XS GIS Cut Line= 3
      3638727.28     10153580.36      3638305.52     10153599.72
      3637837.94     10153658.83
#Sta/Elev= 30
  4287.8  227.74    4296  227.15  4383.1  221.84  4421.4   220.3  4443.1  218.51
  4473.2   216.8    4494  216.36  4533.2  217.26  4613.3  214.54  4640.6  217.42
  4645.6  216.65  4679.7  216.98  4691.9  216.89  4842.2  212.32  4854.6  213.16
  4871.3  212.93  4884.8  213.24    4905  212.44  4955.4  212.41  4975.5  211.66
  4985.6  209.63  4992.7  206.92  4995.4  206.42  4998.7  206.92  5007.6  208.03
  5015.8  214.65  5025.9  215.68  5162.9  216.98    5168  217.45  5181.3  216.86
#Mann= 8 ,-1 , 0
  4287.8      .1       0    4296     .05       0    4494     .08       0
  4679.7     .05       0  4691.9     .12       0  4871.3     .05       0
  4992.7     .03       0  4998.7     .05       0
Bank Sta=4992.7,4998.7
XS Rating Curve= 0 ,0
Exp/Cntr=0.3,0.1

Type RM Length L Ch R = 1 ,1713    ,193,193,193
BEGIN DESCRIPTION:
UNT096 IN ROCK 2.0
END DESCRIPTION:
XS GIS Cut Line= 3
      3638744.74     10153480.08      3638042.11     10153541.64
      3637851.01     10153549.84
#Sta/Elev= 30
  4275.8  234.64  4318.6  231.04  4347.3  229.78  4352.3  228.94  4408.9  225.14
  4469.9   222.2  4496.5  221.58  4560.5  220.33  4619.7  219.46  4649.9  218.36
  4790.4   212.1  4807.4  210.54  4820.5  210.93  4870.7  209.23  4880.7  207.56
  4890.8  208.86  4900.8  207.88  4910.9  208.99    4941  209.82  4983.6  208.77
  4991.1  204.03  4998.1  200.66  5000.9  200.16  5004.1  200.66  5011.2  203.83
  5021.2   210.7  5061.2  211.19  5081.2   213.1    5102  213.69  5172.4   213.6
#Mann= 5 ,-1 , 0
  4275.8     .08       0  4496.5     .05       0  4560.5     .08       0
  4998.1     .07       0  5004.1     .08       0
Bank Sta=4998.1,5004.1
XS Rating Curve= 0 ,0
Exp/Cntr=0.3,0.1

Type RM Length L Ch R = 1 ,1520    ,882,882,882
BEGIN DESCRIPTION:
Mapping XS bbb20376
END DESCRIPTION:
XS GIS Cut Line= 3
      3638668.68     10153436.13      3638176.06     10153481.71
      3637916.37      10153457.9
#Sta/Elev= 30
  4464.4  232.51    4473  231.65  4491.1  231.77  4501.1  230.39  4511.2  229.86
  4541.3  229.03  4551.3   227.8  4577.5  226.29  4582.5  225.59  4606.9  225.16
  4782.3  218.45  4824.6  215.94  4882.8  213.61  4922.9  210.87  4963.6  209.56
  4973.1  208.59  4983.2  205.92  4993.2  201.85  5000.3  200.59    5003  200.09
  5006.3  200.59  5011.4  205.89  5016.5   207.8  5033.4  208.18  5063.5   207.6
  5113.7  210.88  5143.8  211.35    5174  212.68  5201.9  212.36  5219.9  212.23
#Mann= 6 ,-1 , 0
  4464.4     .08       0  4606.9     .05       0  4824.6     .12       0
  5000.3     .07       0  5006.3     .12       0  5201.9      .1       0
Bank Sta=5000.3,5006.3
XS Rating Curve= 0 ,0
Exp/Cntr=0.3,0.1

Type RM Length L Ch R = 1 ,638     ,0,0,0
BEGIN DESCRIPTION:
UNT096 IN ROCK 1.0
END DESCRIPTION:
XS GIS Cut Line= 4
       3638121.3     10152612.46      3637750.05     10152875.22
      3637763.78     10153192.33      3637842.24     10153453.88
#Sta/Elev= 30
  4343.6  217.88  4364.6  218.03  4379.3  216.38  4385.5  214.08    4415  211.18
  4727.2  206.57    4751  206.79  4771.9  202.34  4794.1  201.08    4915  200.06
  4965.8  201.46    4975  201.35    4985  199.52    4995  196.26  5004.8  195.45
  5015.1  199.26  5025.1  201.34  5106.3  199.38  5118.1   199.4  5123.9  200.51
  5129.1  199.92  5146.4  201.58  5212.7  199.96  5219.5  200.52  5240.4     207
  5250.8  209.11  5266.6  210.31  5313.4  210.91  5369.1   211.5  5388.9  211.73
#Mann= 8 ,-1 , 0
  4343.6     .05       0  4727.2     .16       0    4985     .07       0
  5015.1     .16       0  5106.3      .1       0  5212.7      .1       0
  5313.4     .16       0  5369.1      .1       0
Bank Sta=4985,5015.1
XS Rating Curve= 0 ,0
Exp/Cntr=0.3,0.1
Stream Node=UNT096 IN ROCK  ,Reach-1         , 0 , 0 ,Upstream end
Stream Node=UNT096 IN ROCK  ,Reach-1         , 0 , 1 ,Downstream end

Chan Stop Cuts=-1
Use User Specified Reach Order=0
Composite Channel Slope=5