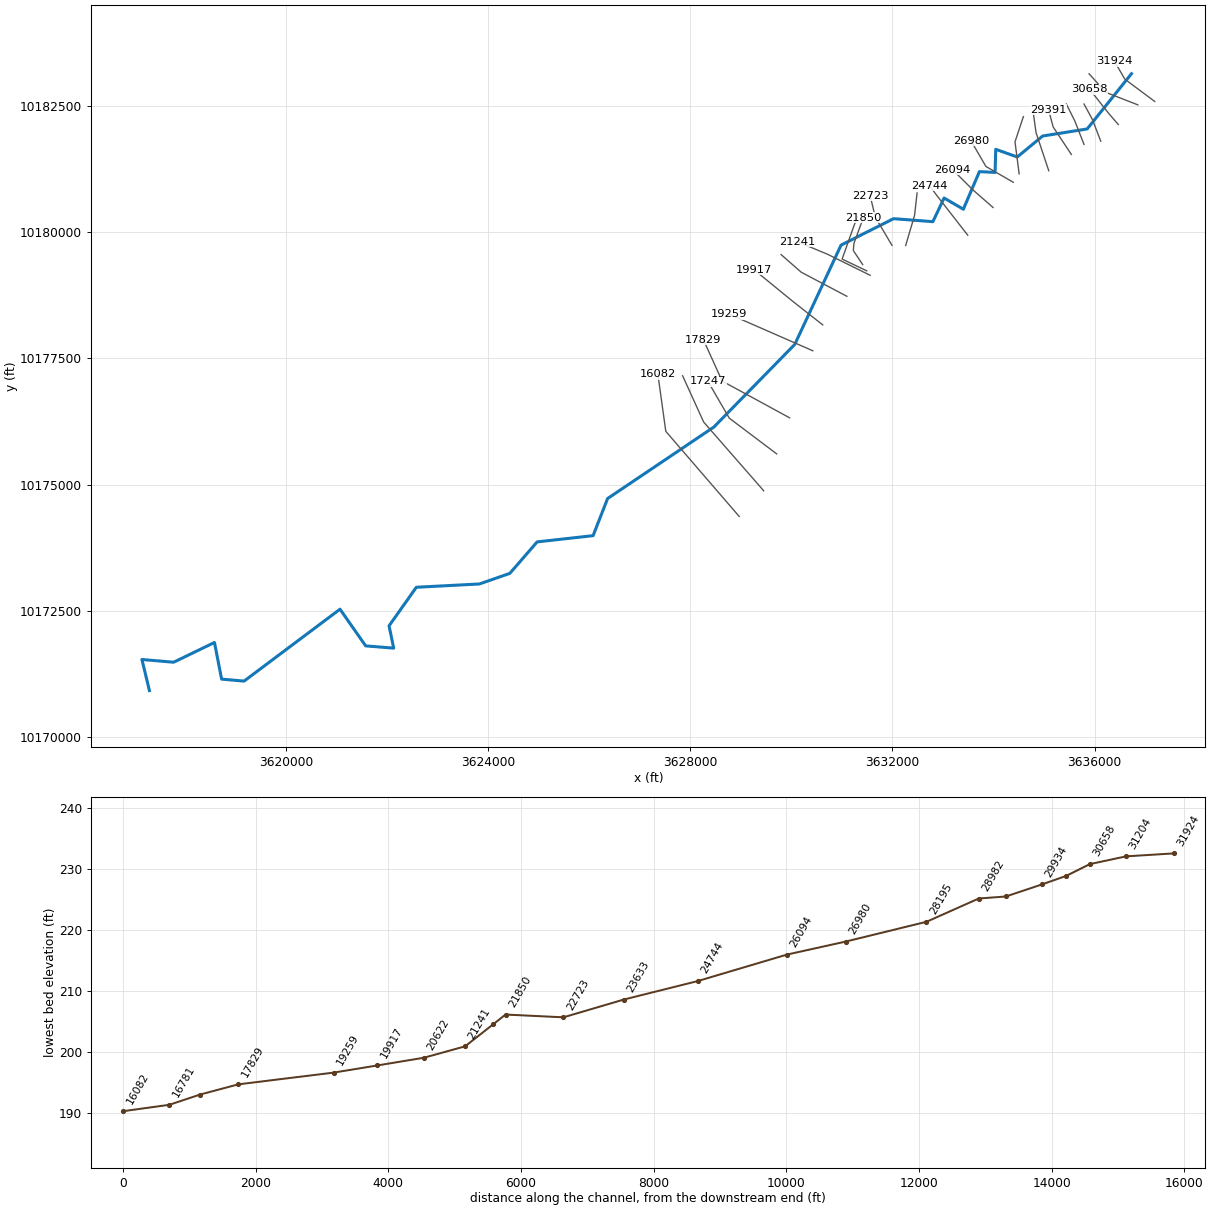
--- UNT097 IN ROCK.prj (project) ---

Proj Title=UNT097 IN ROCK Base Level Engineering
Current Plan=p01
Default Exp/Contr=0.3,0.1
English Units
Geom File=g01
Flow File=f01
Plan File=p01
Y Axis Title=Elevation
X Axis Title(PF)=Main Channel Distance
X Axis Title(XS)=Station
BEGIN DESCRIPTION:
UNT097 IN ROCK
END DESCRIPTION:
DSS Export Rating Curves= 0
DSS Export Rating Curve Sorted= 0
DSS Export Volume Flow Curves= 0
DXF OffsetX= 0
DXF OffsetY= 0
DXF ScaleX= 1
DXF ScaleY= 10

--- UNT097 IN ROCK.p01 (plan) ---

Plan Title=Multiple Run
Short Identifier=Multiple
Geom File=g01
Flow File=f01
Subcritical Flow
K Sum by GR= 0
Std Step Tol= 0.01
Critical Tol= 0.01
Num of Std Step Trials= 20
Max Error Tol= 0.3
Flow Tol Ratio= 0.001
Split Flow NTrial= 30
Split Flow Tol= 0.02
Split Flow Ratio= 0.02
Log Output Level= 0
Friction Slope Method= 1
Unsteady Friction Slope Method= 2
Unsteady Bridges Friction Slope Method= 1
Parabolic Critical Depth
Global Vel Dist=  1 , 1 , 1
Global Log Level= 0
CheckData=True
Encroach Param= -1, 0, 0, 0
BEGIN DESCRIPTION:
Multiple Run
END DESCRIPTION:

--- UNT097 IN ROCK.f01 (steady flow) ---

Flow Title=Multiple
Program Version=4.10
Number of Profiles= 7
Profile Names=10-year,25-year,50-year,1pct_min,100-year,1pct_plu,500-year
River Rch & RM=UNT097 IN ROCK,Reach-1         ,31924
     640     857    1032     912    1233    1667    1760
River Rch & RM=UNT097 IN ROCK,Reach-1         ,26980
    1083    1485    1818    1627    2200    2976    3228
Boundary for River Rch & Prof#=UNT097 IN ROCK,Reach-1         , 1
Up Type= 0
Dn Type= 3
Dn Slope=0.005
Boundary for River Rch & Prof#=UNT097 IN ROCK,Reach-1         , 2
Up Type= 0
Dn Type= 3
Dn Slope=0.005
Boundary for River Rch & Prof#=UNT097 IN ROCK,Reach-1         , 3
Up Type= 0
Dn Type= 3
Dn Slope=0.005
Boundary for River Rch & Prof#=UNT097 IN ROCK,Reach-1         , 4
Up Type= 0
Dn Type= 3
Dn Slope=0.005
Boundary for River Rch & Prof#=UNT097 IN ROCK,Reach-1         , 5
Up Type= 0
Dn Type= 3
Dn Slope=0.005
Boundary for River Rch & Prof#=UNT097 IN ROCK,Reach-1         , 6
Up Type= 0
Dn Type= 3
Dn Slope=0.005
Boundary for River Rch & Prof#=UNT097 IN ROCK,Reach-1         , 7
Up Type= 0
Dn Type= 3
Dn Slope=0.005
DSS Import GetInterval= 0
DSS Import GetPeak= 0
DSS Import FillOption= 0

--- UNT097 IN ROCK.g01 (geometry) ---

Geom Title=Existing Conditions
Program Version=4.10

River Reach=UNT097 IN ROCK  ,Reach-1
Reach XY= 30
       3636730.9     10183141.82      3635854.38     10182047.62
      3634973.57     10181907.98      3634471.86     10181492.02
      3634045.75     10181643.91      3634032.32     10181186.12
       3633722.1     10181202.35      3633404.24     10180456.55
       3633023.4     10180679.08      3632801.84     10180210.76
      3632022.32     10180269.79      3630984.69     10179745.87
      3630068.64     10177778.26      3628467.22     10176140.67
      3626365.43     10174724.92       3626078.6     10173989.39
      3624971.28     10173865.63      3624430.53     10173241.68
      3623828.68      10173031.9      3622581.28      10172966.8
      3622041.56     10172203.28       3622132.7     10171760.57
      3621578.14     10171805.47      3621071.19     10172532.03
      3619172.41     10171107.38      3618727.97     10171146.96
      3618586.99     10171872.65      3617779.35     10171481.68
      3617151.58     10171535.15      3617299.73     10170919.51

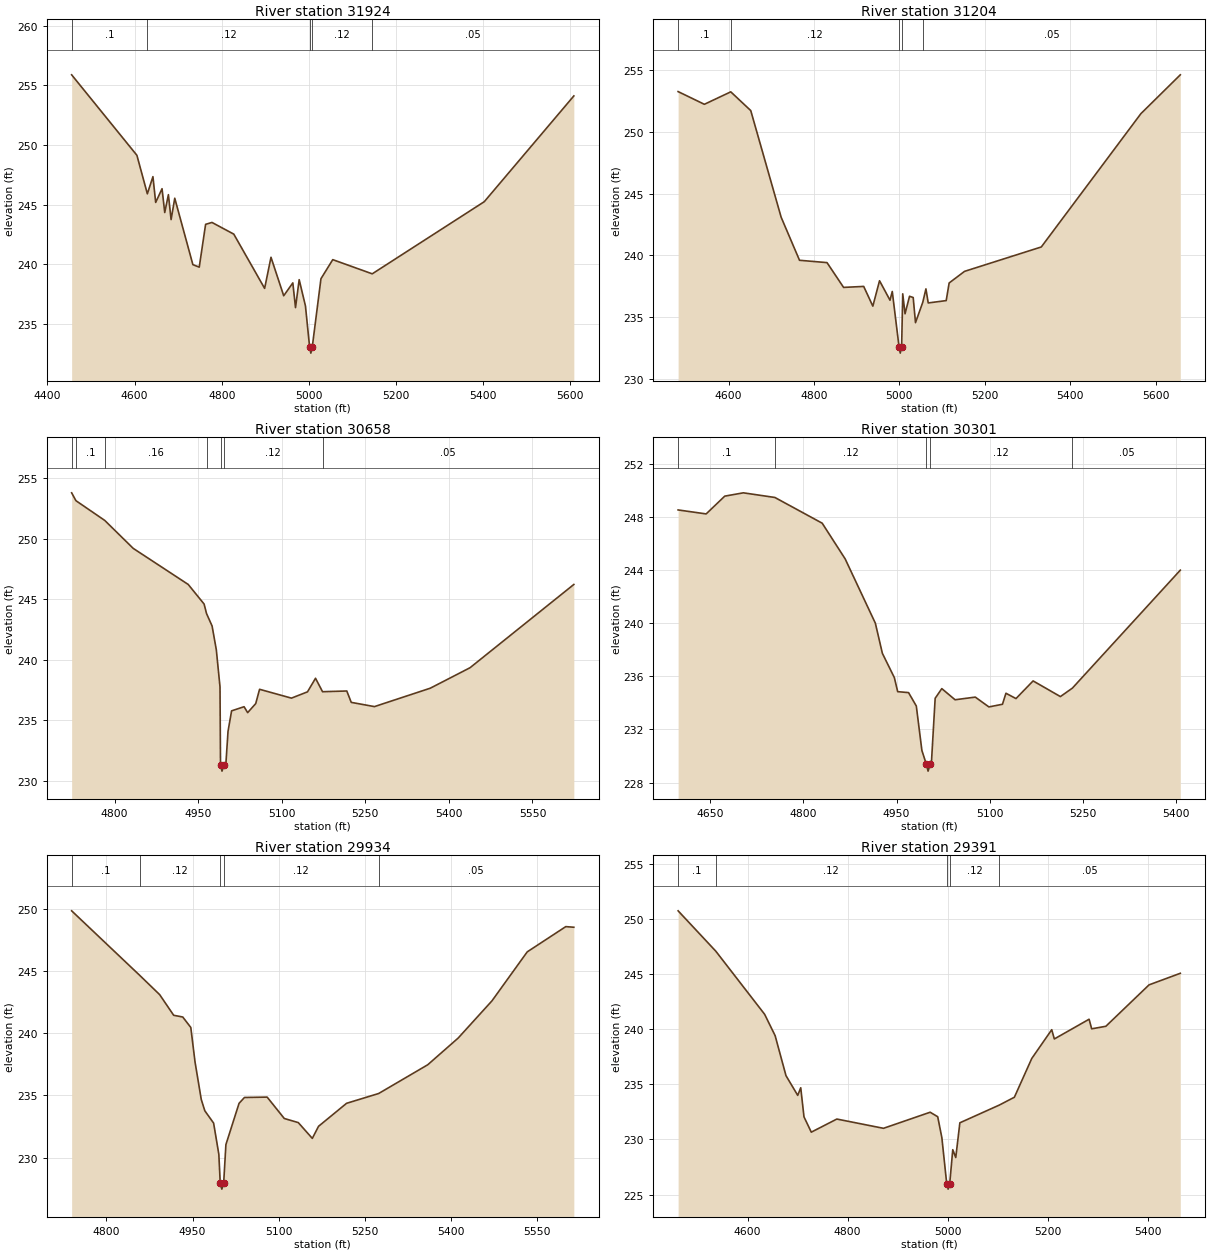
Type RM Length L Ch R = 1 ,31924   ,719,719,719
BEGIN DESCRIPTION:
UNT097 IN ROCK 55.0
END DESCRIPTION:
XS GIS Cut Line= 3
      3637192.15     10182591.61      3636600.82     10183033.09
      3636392.12     10183391.62
#Sta/Elev= 30
  4455.5  255.88  4605.3  249.13  4629.3   245.9  4642.1  247.34  4648.4  245.18
    4663  246.33  4669.2  244.33  4677.6  245.83  4683.8  243.74  4692.2  245.53
  4733.8  239.96  4748.4  239.75    4763  243.34  4777.6   243.5  4827.7  242.52
  4898.5  237.97  4913.1  240.58  4942.3  237.35  4963.2  238.43  4969.4  236.36
  4977.8   238.7  4992.2   236.5  5001.8  233.04  5004.6  232.54  5007.8  233.04
  5027.8  238.78  5054.9  240.38  5145.5  239.19  5402.7  245.24  5608.3  254.11
#Mann= 5 ,-1 , 0
  4455.5      .1       0  4629.3     .12       0  5001.8     .07       0
  5007.8     .12       0  5145.5     .05       0
Bank Sta=5001.8,5007.8
XS Rating Curve= 0 ,0
Exp/Cntr=0.3,0.1

Type RM Length L Ch R = 1 ,31204   ,547,547,547
BEGIN DESCRIPTION:
UNT097 IN ROCK 53.0
END DESCRIPTION:
XS GIS Cut Line= 3
      3636856.91     10182525.27      3636223.22     10182772.67
      3635892.12     10183141.62
#Sta/Elev= 30
    4482  253.27  4543.5  252.24  4605.3  253.25  4652.1  251.73  4723.3  243.08
  4766.3  239.59  4830.7   239.4  4869.5  237.39  4916.6  237.47    4938  235.87
  4953.7  237.93  4978.2  236.35  4983.5  237.06  4999.4  232.56  5002.2  232.06
  5005.4  232.56    5008  236.87  5013.4  235.25  5023.9  236.67  5032.5  236.57
  5037.9  234.53    5055  236.19  5062.3  237.27  5067.7  236.13  5109.8  236.32
  5116.7  237.75  5152.7  238.69  5332.5  240.67  5565.7  251.48    5658  254.63
#Mann= 5 ,-1 , 0
    4482      .1       0  4605.3     .12       0  4999.4     .07       0
  5005.4     .12       0    5055     .05       0
Bank Sta=4999.4,5005.4
XS Rating Curve= 0 ,0
Exp/Cntr=0.3,0.1

Type RM Length L Ch R = 1 ,30658   ,357,357,357
BEGIN DESCRIPTION:
UNT097 IN ROCK 52.0
END DESCRIPTION:
XS GIS Cut Line= 3
      3636470.64     10182134.62      3636292.11     10182341.64
      3635902.03     10182833.45
#Sta/Elev= 30
  4723.1  253.78  4730.8  253.13  4782.5   251.5  4833.6  249.19  4932.3  246.21
  4960.8  244.59  4965.1  243.81  4975.1  242.78  4982.7  240.81  4989.3  237.75
  4990.2  231.29  4992.9  230.79  4996.2  231.29  4999.7  231.29  5003.7  234.08
  5010.1  235.77  5032.5  236.11  5038.9  235.62  5053.4  236.37  5060.3  237.55
  5117.5  236.82  5146.3  237.34  5160.7  238.46  5173.3  237.35  5216.8  237.41
  5224.8  236.47  5266.4  236.12  5366.6  237.64  5437.9  239.33  5624.2  246.21
#Mann= 7 ,-1 , 0
  4723.1     .16       0  4730.8      .1       0  4782.5     .16       0
  4965.1     .12       0  4990.2     .07       0  4996.2     .12       0
  5173.3     .05       0
Bank Sta=4990.2,4996.2
XS Rating Curve= 0 ,0
Exp/Cntr=0.3,0.1

Type RM Length L Ch R = 1 ,30301   ,367,367,367
BEGIN DESCRIPTION:
UNT097 IN ROCK 51.0
END DESCRIPTION:
XS GIS Cut Line= 3
       3636123.4     10181804.77      3635958.46     10182234.48
       3635792.1     10182541.65
#Sta/Elev= 30
  4597.9  248.55  4643.1  248.25  4673.1  249.59  4703.1  249.84  4753.9  249.49
  4830.2  247.55  4867.2  244.86  4915.9  240.01  4927.2  237.74  4946.5  235.91
  4951.9  234.85  4969.4  234.78  4981.9  233.77  4990.9  230.42  4998.2  229.36
  5000.9  228.86  5004.2  229.36  5006.5  229.68  5012.3  234.35    5023  235.08
  5044.4  234.24    5077  234.44  5098.9   233.7  5120.8   233.9  5126.4  234.73
  5142.6  234.33  5170.2  235.66  5214.2  234.48  5233.6  235.12  5407.5  244.01
#Mann= 5 ,-1 , 0
  4597.9      .1       0  4753.9     .12       0  4998.2     .07       0
  5004.2     .12       0  5233.6     .05       0
Bank Sta=4998.2,5004.2
XS Rating Curve= 0 ,0
Exp/Cntr=0.3,0.1

Type RM Length L Ch R = 1 ,29934   ,543,543,543
BEGIN DESCRIPTION:
UNT097 IN ROCK 50.0
END DESCRIPTION:
XS GIS Cut Line= 3
       3635792.1     10181741.65      3635609.18      10182207.8
      3635442.09     10182541.67
#Sta/Elev= 30
  4739.5  249.84    4858  244.65  4892.7   243.1  4917.1  241.44  4932.9   241.3
  4946.9  240.46  4954.3  237.67  4965.1  234.67  4971.3  233.76  4986.6  232.77
  4995.7  230.26  4998.1  227.96  5000.9  227.46  5004.1  227.96    5008  231.04
  5030.9  234.36  5040.3  234.83  5079.8  234.86  5109.6  233.14    5134  232.81
  5158.4  231.54  5169.2  232.51    5218  234.36  5273.9  235.15  5359.3  237.46
  5412.3  239.61  5471.1   242.6  5532.5  246.54  5599.6  248.57  5613.6  248.52
#Mann= 5 ,-1 , 0
  4739.5      .1       0    4858     .12       0  4998.1     .07       0
  5004.1     .12       0  5273.9     .05       0
Bank Sta=4998.1,5004.1
XS Rating Curve= 0 ,0
Exp/Cntr=0.3,0.1

Type RM Length L Ch R = 1 ,29391   ,408,408,408
BEGIN DESCRIPTION:
UNT097 IN ROCK 49.0
END DESCRIPTION:
XS GIS Cut Line= 3
      3635542.08     10181541.68      3635181.55     10182086.91
      3635090.42     10182425.41
#Sta/Elev= 30
    4461  250.75  4536.3  247.09    4634  241.36    4655  239.42  4676.7  235.79
  4700.2     234  4706.2  234.69  4712.7  232.05  4727.3  230.66  4778.4  231.85
  4871.7  231.01    4965  232.47  4980.1  232.06  4988.4  230.16  4998.1  225.99
  5000.9  225.49  5004.1  225.99  5010.2  229.07  5016.2  228.36  5024.4  231.51
  5103.3  233.12  5133.4  233.83  5168.2  237.35  5208.1  239.96  5213.3  239.12
  5282.8  240.91    5288  240.04  5316.3  240.27  5402.7  244.03  5465.2  245.08
#Mann= 5 ,-1 , 0
    4461      .1       0  4536.3     .12       0  4998.1     .07       0
  5004.1     .12       0  5103.3     .05       0
Bank Sta=4998.1,5004.1
XS Rating Curve= 0 ,0
Exp/Cntr=0.3,0.1

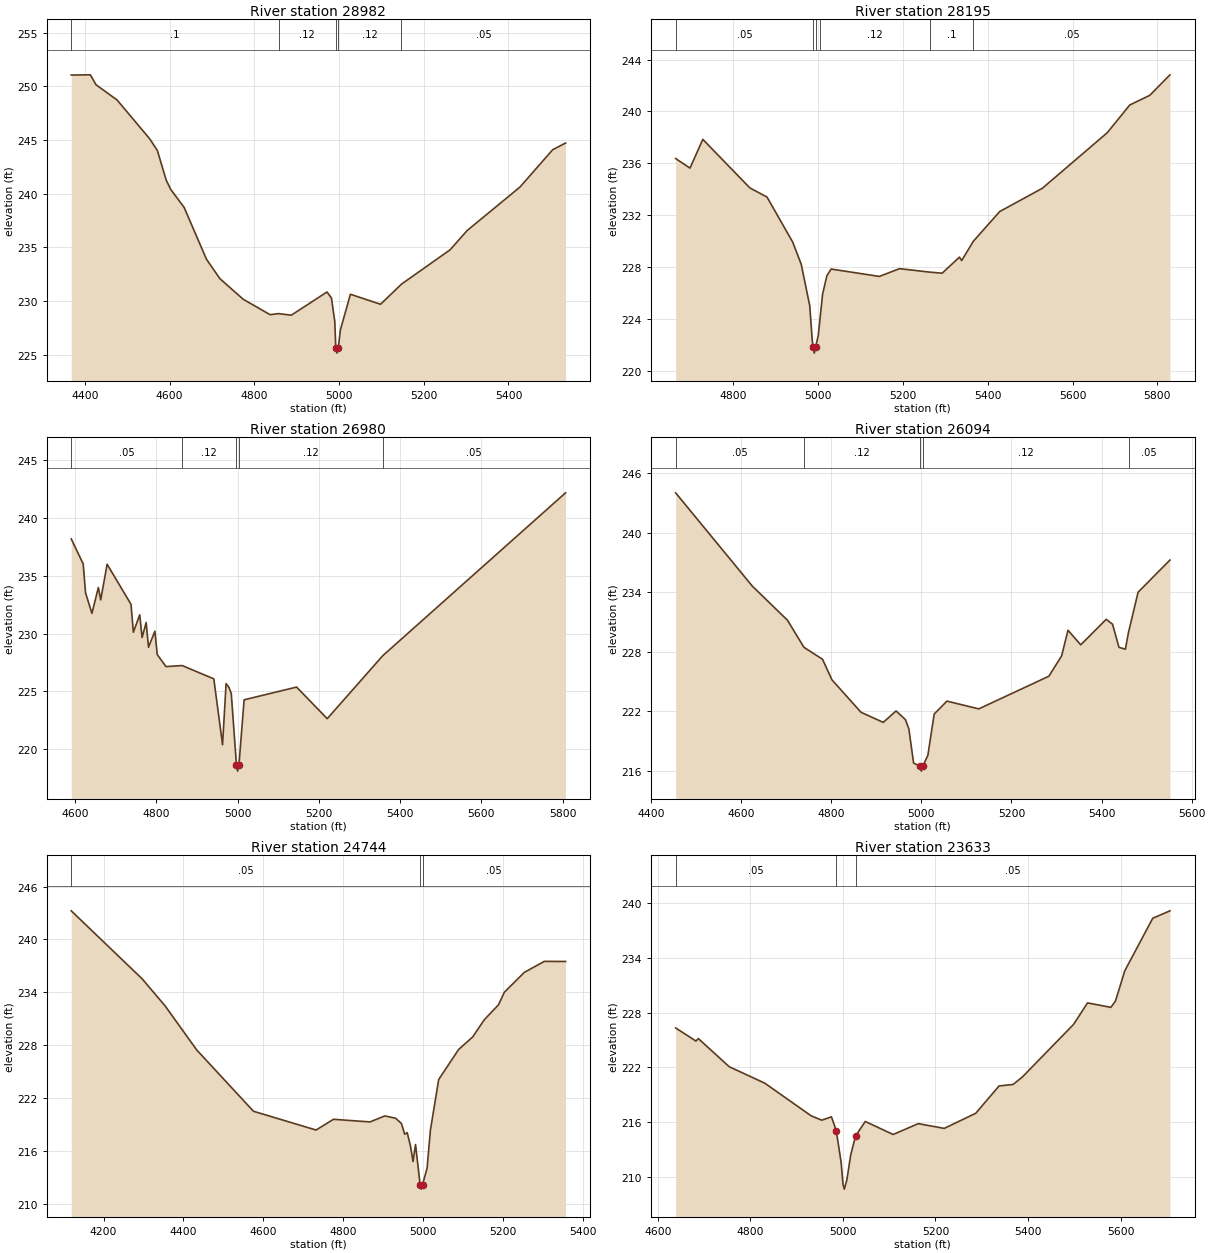
Type RM Length L Ch R = 1 ,28982   ,788,788,788
BEGIN DESCRIPTION:
UNT097 IN ROCK 48.0
END DESCRIPTION:
XS GIS Cut Line= 3
      3635094.76     10181218.81      3634843.01     10181974.06
       3634792.1     10182341.65
#Sta/Elev= 30
  4367.6  251.05  4412.8  251.07    4426  250.15    4476  248.72  4552.5  245.13
  4570.9  244.03  4591.9  241.26  4602.5   240.4  4634.1  238.73  4686.8  233.91
  4718.4   232.1  4773.8  230.17  4837.1  228.74  4857.3  228.84  4887.1  228.69
  4971.4  230.85    4982  230.29  4989.9  228.11  4992.2  225.66    4995  225.16
  4998.2  225.66    5003  227.31  5026.8  230.64  5097.9  229.71  5147.3  231.58
  5262.2  234.78  5302.6  236.58  5427.1  240.62  5504.5   244.1  5534.8  244.72
#Mann= 5 ,-1 , 0
  4367.6      .1       0  4857.3     .12       0  4992.2     .07       0
  4998.2     .12       0  5147.3     .05       0
Bank Sta=4992.2,4998.2
XS Rating Curve= 0 ,0
Exp/Cntr=0.3,0.1

Type RM Length L Ch R = 1 ,28195   ,1215,1215,1215
BEGIN DESCRIPTION:
UNT097 IN ROCK 46.0
END DESCRIPTION:
XS GIS Cut Line= 3
      3634508.82     10181158.05      3634426.35     10181791.77
       3634592.1     10182291.64
#Sta/Elev= 30
    4664  236.37  4697.9  235.63  4728.1  237.85  4839.1   234.1  4879.4   233.4
  4939.9  229.93  4960.1  228.22  4980.2  225.02  4986.2  222.32  4988.3  221.85
    4991  221.35  4994.3  221.85  5000.4  222.72  5005.5  224.32  5010.5  225.89
  5020.6  227.32  5030.7  227.84  5144.4  227.27    5192  227.87  5263.8   227.6
  5292.5  227.52  5333.3  228.76  5338.5  228.49  5366.2  229.99  5428.3  232.28
  5528.7  234.07  5681.8  238.36  5734.9   240.5  5782.2  241.25  5829.7  242.83
#Mann= 6 ,-1 , 0
    4664     .05       0  4988.3     .03       0  4994.3     .05       0
  5005.5     .12       0  5263.8      .1       0  5366.2     .05       0
Bank Sta=4988.3,4994.3
XS Rating Curve= 0 ,0
Exp/Cntr=0.3,0.1

Type RM Length L Ch R = 1 ,26980   ,886,886,886
BEGIN DESCRIPTION:
UNT097 IN ROCK 45.0
END DESCRIPTION:
XS GIS Cut Line= 3
      3634392.09     10180991.65      3633851.11      10181304.4
      3633553.89     10181816.52
#Sta/Elev= 30
  4590.3  238.18  4619.7  236.02  4625.5  233.52  4641.2  231.75    4657  233.98
  4662.8  232.91  4678.6  235.99  4737.4  232.53  4743.2  230.12  4758.9  231.62
  4764.7  229.66  4774.7  230.96  4780.5  228.82  4796.2  230.21    4802  228.19
  4823.6  227.15  4863.3  227.24  4941.3  226.09  4962.8   220.4  4971.5  225.68
  4978.6  225.35  4984.3  224.82  4997.1  218.62  4999.9  218.12  5003.1  218.62
  5015.9  224.28  5145.1  225.38  5220.5  222.65  5357.2  228.09  5807.3  242.16
#Mann= 5 ,-1 , 0
  4590.3     .05       0  4863.3     .12       0  4997.1     .07       0
  5003.1     .12       0  5357.2     .05       0
Bank Sta=4997.1,5003.1
XS Rating Curve= 0 ,0
Exp/Cntr=0.3,0.1

Type RM Length L Ch R = 1 ,26094   ,1350,1350,1350
BEGIN DESCRIPTION:
UNT097 IN ROCK 43.0
END DESCRIPTION:
XS GIS Cut Line= 3
      3633992.09     10180491.66      3633592.11     10180841.64
      3633192.09     10181241.66
#Sta/Elev= 30
  4454.6  244.02  4624.9  234.62  4702.8  231.19  4739.4  228.46  4780.6  227.26
  4801.5  225.19    4866  221.92  4915.4   220.9  4943.9  222.05  4964.7  221.18
  4972.3  220.24  4982.8   216.8  4997.2  216.49    5000  215.99  5003.2  216.49
  5014.4  217.57  5028.5  221.74  5056.8  223.04  5127.5  222.26  5283.1  225.55
  5311.4   227.6  5325.5  230.18  5353.8  228.71  5410.4  231.28  5424.5  230.78
  5438.6  228.46  5452.8  228.27    5460  230.01  5481.1  234.01  5551.8  237.25
#Mann= 5 ,-1 , 0
  4454.6     .05       0  4739.4     .12       0  4997.2     .07       0
  5003.2     .12       0    5460     .05       0
Bank Sta=4997.2,5003.2
XS Rating Curve= 0 ,0
Exp/Cntr=0.3,0.1

Type RM Length L Ch R = 1 ,24744   ,1110,1110,1110
BEGIN DESCRIPTION:
UNT097 IN ROCK 40.0
END DESCRIPTION:
XS GIS Cut Line= 3
      3633492.11     10179941.64      3632885.51     10180721.85
      3632736.33     10180920.75
#Sta/Elev= 30
  4119.2  243.24  4296.6  235.52  4354.5  232.42  4433.2  227.44  4575.2  220.48
  4731.8  218.35  4775.3  219.57  4866.7  219.27  4903.8  219.95  4930.9  219.69
  4945.4  219.09  4953.6  217.88  4959.9  218.05  4967.9  216.57  4974.4  214.78
  4980.7   216.7  4992.2  212.14  4994.9  211.64  4998.2  212.14  5009.7  214.04
  5017.8   218.3  5038.6  224.08  5088.4  227.49  5123.7  228.92  5152.9  230.88
  5188.3  232.57  5202.9  233.99  5252.9  236.25  5302.9   237.5  5356.1  237.49
#Mann= 3 ,-1 , 0
  4119.2     .05       0  4992.2     .03       0  4998.2     .05       0
Bank Sta=4992.2,4998.2
XS Rating Curve= 0 ,0
Exp/Cntr=0.3,0.1

Type RM Length L Ch R = 1 ,23633   ,911,911,911
BEGIN DESCRIPTION:
UNT097 IN ROCK 38.0
END DESCRIPTION:
XS GIS Cut Line= 3
      3632263.43      10179738.8      3632439.12     10180334.93
      3632488.92     10180778.56
#Sta/Elev= 30
  4638.7  226.33  4682.6  224.89  4687.8  225.16  4754.5  222.07  4831.5  220.26
  4931.5  216.68  4954.4   216.2  4975.3  216.57  4985.7  215.06  4996.1  211.61
  5000.4  209.13  5003.1  208.63  5008.6  209.64    5017   212.4  5027.4  214.46
  5048.3  216.06  5108.6  214.63  5162.9  215.82    5219   215.3  5287.1  216.96
  5337.4  219.96  5367.6  220.12  5387.7  220.94  5498.4  226.72  5528.6  229.08
  5578.9  228.59  5588.9  229.28  5609.1  232.61  5669.4  238.37  5706.6  239.19
#Mann= 3 , 0 , 0
  4638.7     .05       0  4985.7    .035       0  5027.4     .05       0
Bank Sta=4985.7,5027.4
XS Rating Curve= 0 ,0
Exp/Cntr=0.3,0.1

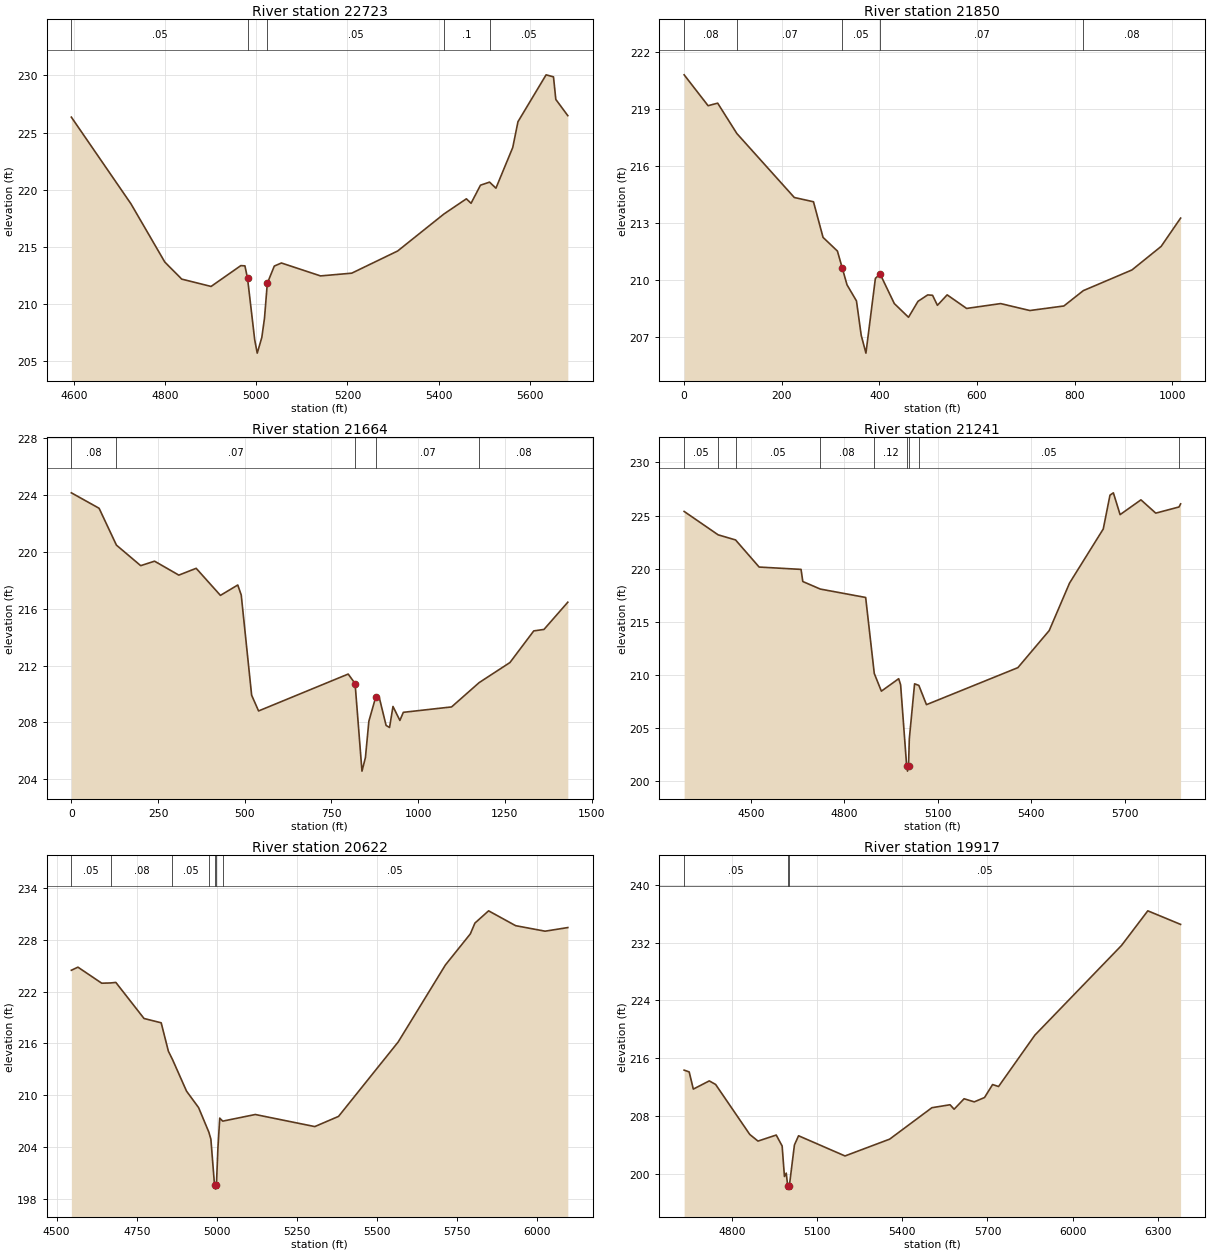
Type RM Length L Ch R = 1 ,22723   ,873,873,873
BEGIN DESCRIPTION:
UNT097 IN ROCK 37.0
END DESCRIPTION:
XS GIS Cut Line= 3
      3631992.09     10179741.67      3631662.13     10180300.89
      3631559.98     10180727.93
#Sta/Elev= 30
  4594.8  226.35  4725.5  218.77  4799.7  213.68  4836.8  212.19  4901.1  211.55
  4966.3  213.37  4975.3  213.35  4981.1  212.25  4996.8  206.87  5002.3  205.72
  5012.4   207.1  5018.2  208.77  5024.4  211.82  5039.7  213.33  5055.3   213.6
  5141.1  212.47  5209.5  212.71  5310.2  214.65  5411.5  217.88  5460.8  219.21
  5471.1  218.82  5491.7   220.4  5511.6  220.67  5525.6  220.14  5562.5   223.7
  5573.9  225.95  5635.6  230.05  5651.8  229.87  5656.9   227.9  5683.2  226.48
#Mann= 5 ,-1 , 0
  4594.8     .05       0  4981.1    .035       0  5024.4     .05       0
  5411.5      .1       0  5511.6     .05       0
Bank Sta=4981.1,5024.4
XS Rating Curve= 0 ,0
Exp/Cntr=0.3,0.1

Type RM Length L Ch R = 1 ,21850   ,186,186,186
BEGIN DESCRIPTION:
Mapping XS aa0d3a14
END DESCRIPTION:
XS GIS Cut Line= 4
     3631412.525    10179359.971     3631227.435    10179639.004
     3631239.588    10179781.018      3631426.22    10180290.045
#Sta/Elev= 30
       0220.801749.07161219.178468.70025219.3131107.9575 217.717225.7294214.3525
264.9867 214.128284.6153212.2556314.0583211.5355323.8726 210.654333.6869209.7628
353.0741 208.915362.7677207.1134372.4613206.1705391.8484210.1008401.5421210.3297
430.6228 208.776459.7036208.0553479.0908208.8924499.0191 209.231508.9833209.2114
518.9475 208.684538.8759 209.234578.7327208.5203 648.482208.7748708.2672  208.41
778.0165208.6491817.8733209.4562917.5152210.5433977.3003211.78091017.157213.2691
#Mann= 5 ,-1 , 0
       0     .08       0107.9575     .07       0323.8726     .05       0
401.5421     .07       0817.8733     .08       0
Bank Sta=323.8726,401.5421
XS Rating Curve= 0 ,0
Exp/Cntr=0.3,0.1

Type RM Length L Ch R = 1 ,21664   ,423,423,423
BEGIN DESCRIPTION:
Mapping XS 04705b3b
END DESCRIPTION:
XS GIS Cut Line= 4
     3631493.254    10179236.273     3631006.001    10179469.212
     3631237.418    10180122.077     3631310.396    10180312.272
#Sta/Elev= 30
       0224.1506 79.9824223.0643129.9714220.4711 199.956219.0267239.9472219.3417
309.9318218.3612359.9208218.8402429.9054216.9352479.8944217.6663489.8922216.9585
519.8856 209.914539.8812208.8054798.3018211.4004818.1803210.7365838.0588204.5719
 847.998205.5207857.9373208.0828877.8158209.7857887.7551209.7682907.6336207.7874
917.5728207.6411927.5121209.1213947.3906208.1393957.3298208.70851096.479209.0889
1175.993210.79881264.731212.2099 1333.47214.4365 1362.93214.54051431.669216.4565
#Mann= 5 ,-1 , 0
       0     .08       0129.9714     .07       0818.1803     .05       0
877.8158     .07       01175.993     .08       0
Bank Sta=818.1803,877.8158
XS Rating Curve= 0 ,0
Exp/Cntr=0.3,0.1

Type RM Length L Ch R = 1 ,21241   ,619,619,619
BEGIN DESCRIPTION:
UNT097 IN ROCK 33.0
END DESCRIPTION:
XS GIS Cut Line= 3
      3631560.33     10179148.53       3630711.9     10179567.34
       3630112.7       10179817.
#Sta/Elev= 30
  4284.9  225.39  4394.2  223.19  4450.1  222.71  4525.9  220.16  4660.6  219.94
  4666.2   218.8  4722.5  218.09  4868.2   217.3  4895.9  210.15  4918.7  208.49
  4974.3  209.66  4980.5   209.1  4999.9  201.47  5002.7  200.97  5005.9  201.47
  5008.5  204.01  5025.4  209.18  5039.1  209.03  5063.6  207.22  5357.3   210.7
  5458.1  214.19  5523.3  218.65  5631.7  223.74  5653.3  226.92  5664.2  227.14
  5685.8  225.09  5752.8  226.48  5800.4  225.23  5875.2  225.81  5880.2   226.1
#Mann= 9 ,-1 , 0
  4284.9     .05       0  4394.2     .08       0  4450.1     .05       0
  4722.5     .08       0  4895.9     .12       0  4999.9     .07       0
  5005.9     .12       0  5039.1     .05       0  5875.2     .08       0
Bank Sta=4999.9,5005.9
XS Rating Curve= 0 ,0
Exp/Cntr=0.3,0.1

Type RM Length L Ch R = 1 ,20622   ,705,705,705
BEGIN DESCRIPTION:
UNT097 IN ROCK 32.0
END DESCRIPTION:
XS GIS Cut Line= 3
      3631100.23     10178731.88      3630197.31     10179208.66
       3629798.5     10179557.62
#Sta/Elev= 30
  4545.9  224.48  4566.4  224.84  4640.8  222.98  4668.3  223.01  4684.9  223.07
  4772.9  218.89  4826.5  218.39  4849.1  215.09  4861.7  214.15  4905.7  210.47
  4943.4  208.56  4975.6   205.7  4981.8   204.9  4993.1  199.61  4995.9  199.11
  4999.1  199.61  5003.8  203.89  5009.5  207.34  5018.7  206.99  5120.5  207.76
  5306.4  206.36  5380.6  207.54    5567  216.17  5714.6   225.1  5792.4   228.7
  5806.7  229.95  5849.4  231.37  5933.8  229.65  6025.9  229.01  6096.9  229.43
#Mann= 7 ,-1 , 0
  4545.9     .05       0  4668.3     .08       0  4861.7     .05       0
  4975.6     .12       0  4993.1     .07       0  4999.1     .12       0
  5018.7     .05       0
Bank Sta=4993.1,4999.1
XS Rating Curve= 0 ,0
Exp/Cntr=0.3,0.1

Type RM Length L Ch R = 1 ,19917   ,658,658,658
BEGIN DESCRIPTION:
UNT097 IN ROCK 31.0
END DESCRIPTION:
XS GIS Cut Line= 3
      3630621.75     10178166.13      3630023.86     10178636.39
      3629259.94     10179261.41
#Sta/Elev= 30
  4632.1  214.34  4649.9  214.09  4664.4  211.71  4720.7  212.85    4743  212.35
  4863.2  205.42  4892.1   204.5  4956.3  205.34  4977.1  203.82  4985.2  199.59
  4991.5  200.06  4996.6  198.34  4999.4  197.84  5002.6  198.34  5020.4  203.97
  5034.9  205.24  5198.4  202.44  5355.6  204.77  5504.3  209.13  5568.2  209.54
  5582.5  208.92  5617.7  210.37  5653.4  209.94  5689.5  210.54    5718  212.34
    5739  212.07  5866.8  219.19  6171.9  231.63  6264.4  236.43  6379.8  234.55
#Mann= 3 ,-1 , 0
  4632.1     .05       0  4996.6     .03       0  5002.6     .05       0
Bank Sta=4996.6,5002.6
XS Rating Curve= 0 ,0
Exp/Cntr=0.3,0.1

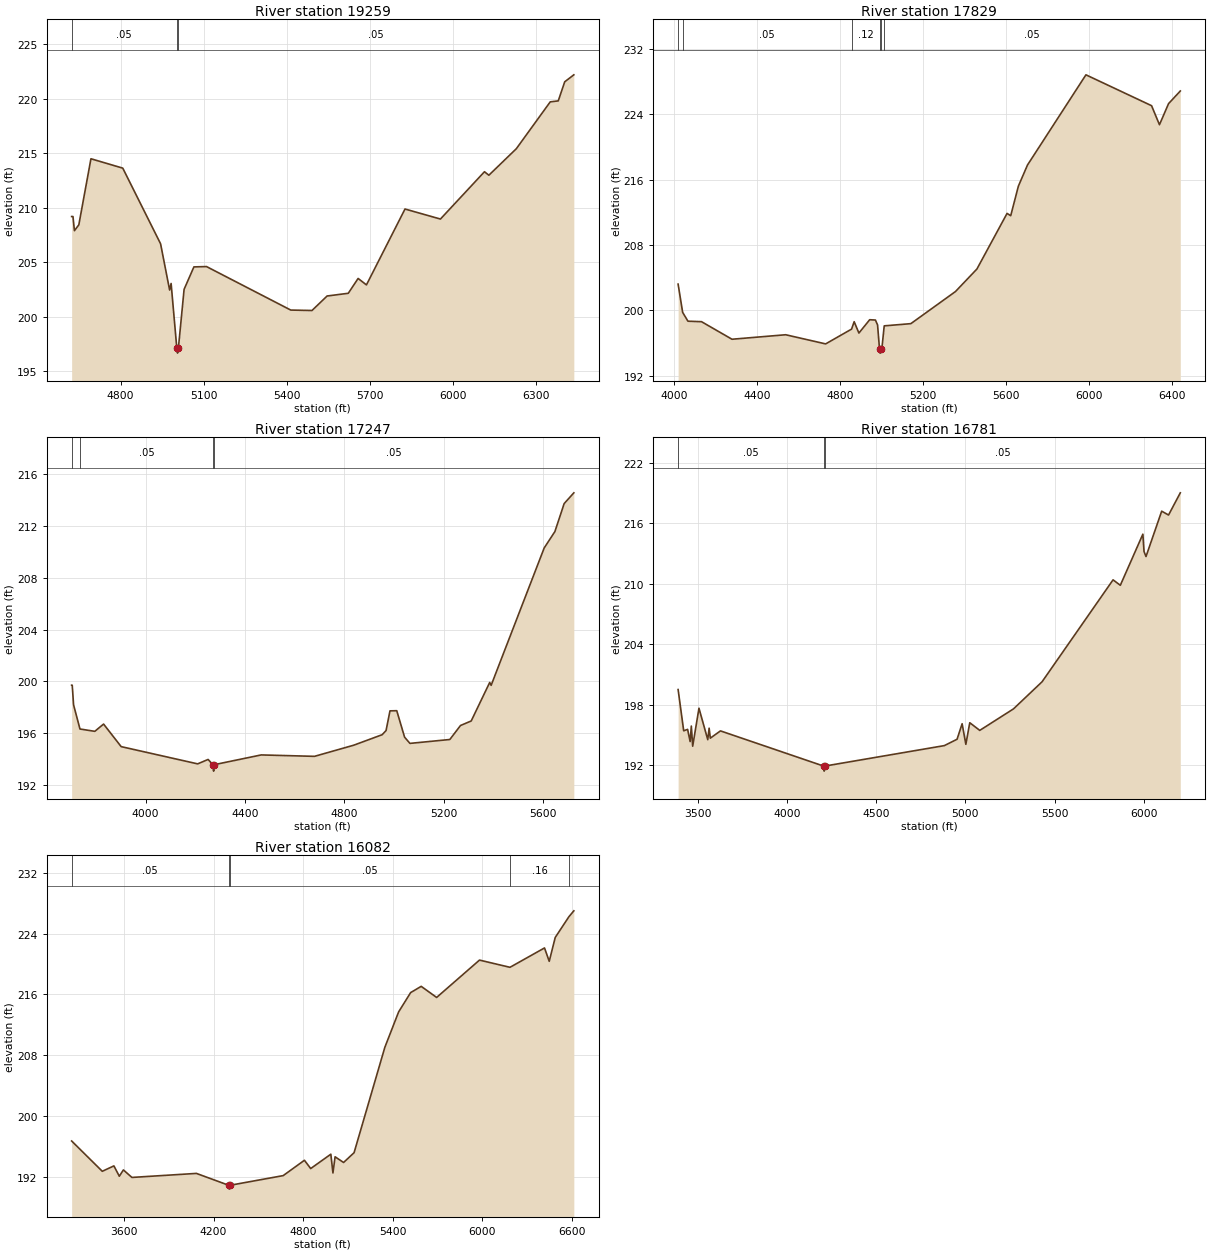
Type RM Length L Ch R = 1 ,19259   ,1437,1437,1437
BEGIN DESCRIPTION:
UNT097 IN ROCK 28.0
END DESCRIPTION:
XS GIS Cut Line= 3
      3630425.86     10177652.46      3629566.41     10178029.84
      3628766.74     10178379.69
#Sta/Elev= 30
  4623.5   209.2  4628.3   209.2  4633.5   207.9  4649.4  208.44  4693.1   214.5
  4807.9  213.64  4944.3   206.7  4976.9  202.46  4982.3  203.06  5002.7  197.17
  5005.4  196.67  5008.7  197.17  5029.1  202.52  5064.5  204.58    5110  204.61
  5413.9  200.62  5490.4  200.58    5545  201.91  5621.4  202.16  5656.8  203.52
  5686.9  202.93    5826  209.89  5953.8  208.97  6112.6  213.31  6128.5  212.99
  6227.5  215.42  6349.9  219.72  6378.8  219.81  6402.1  221.56    6435   222.2
#Mann= 3 ,-1 , 0
  4623.5     .05       0  5002.7     .03       0  5008.7     .05       0
Bank Sta=5002.7,5008.7
XS Rating Curve= 0 ,0
Exp/Cntr=0.3,0.1

Type RM Length L Ch R = 1 ,17829   ,575,575,575
BEGIN DESCRIPTION:
UNT097 IN ROCK 24.0
END DESCRIPTION:
XS GIS Cut Line= 3
      3629967.67     10176323.34      3628631.95     10177052.49
       3628260.1     10177873.31
#Sta/Elev= 30
  4017.5   203.2  4039.4  199.74  4064.9  198.66  4130.4   198.6  4277.5  196.45
  4536.5     197  4729.3  195.88  4854.4  197.69  4866.9   198.6  4889.7  197.21
  4941.8  198.84  4969.5   198.8  4979.8   198.2  4989.2  195.25    4992  194.75
  4995.2  195.25  5001.6  195.56  5011.9  198.09  5140.4  198.36  5355.6  202.29
  5459.1  205.05  5604.6  211.86  5622.2  211.58  5659.1  215.19    5703  217.78
  5985.1  228.83  6301.8  225.05  6339.8  222.72  6383.7   225.3  6440.4  226.85
#Mann= 6 ,-1 , 0
  4017.5     .08       0  4039.4     .05       0  4854.4     .12       0
  4989.2     .07       0  4995.2     .12       0  5011.9     .05       0
Bank Sta=4989.2,4995.2
XS Rating Curve= 0 ,0
Exp/Cntr=0.3,0.1

Type RM Length L Ch R = 1 ,17247   ,466,466,466
BEGIN DESCRIPTION:
Mapping XS 09f6bb4a
END DESCRIPTION:
XS GIS Cut Line= 3
       3629710.7     10175609.92       3628773.2     10176317.39
      3628347.85     10177050.89
#Sta/Elev= 30
  3702.5  199.71  3704.8  199.71  3710.3  198.19    3736  196.33  3795.7  196.15
  3831.1  196.71  3901.9  194.97  4209.9  193.64    4252  193.98  4271.4  193.58
  4274.2  193.08  4277.4  193.58    4466  194.33  4680.4  194.22  4838.5  195.08
    4953  195.89  4968.7  196.21  4984.5  197.73  5011.8  197.74  5043.3   195.7
  5064.8  195.22  5225.5  195.52  5268.5   196.6  5311.6  196.95  5386.1  199.92
  5391.9   199.7  5605.6   210.3  5648.6  211.56  5685.9  213.72  5724.9  214.55
#Mann= 4 ,-1 , 0
  3702.5     .08       0    3736     .05       0  4271.4     .03       0
  4277.4     .05       0
Bank Sta=4271.4,4277.4
XS Rating Curve= 0 ,0
Exp/Cntr=0.3,0.1

Type RM Length L Ch R = 1 ,16781   ,699,699,699
BEGIN DESCRIPTION:
Mapping XS a22436e3
END DESCRIPTION:
XS GIS Cut Line= 3
      3629454.06     10174878.88      3628266.54     10176240.01
       3627849.9     10177156.62
#Sta/Elev= 30
  3390.6  199.49  3421.9   195.4  3443.8  195.54    3458  194.33  3464.6  195.87
  3472.2  193.87  3507.4  197.64  3556.7  194.52  3564.3  195.66    3571  194.67
  3627.9  195.39  4205.9   191.9  4208.6   191.4  4211.9   191.9  4881.9  193.93
  4953.2  194.56  4981.6   196.1  5002.5  194.06  5024.4   196.2  5080.4  195.44
  5269.1  197.57  5429.4  200.26  5827.1  210.37  5867.8  209.83  5994.1   214.9
  6000.6  213.18  6011.6  212.68  6099.5  217.18    6138   216.8  6203.8     219
#Mann= 3 ,-1 , 0
  3390.6     .05       0  4205.9     .03       0  4211.9     .05       0
Bank Sta=4205.9,4211.9
XS Rating Curve= 0 ,0
Exp/Cntr=0.3,0.1

Type RM Length L Ch R = 1 ,16082   ,0,0,0
BEGIN DESCRIPTION:
UNT097 IN ROCK 20.0
END DESCRIPTION:
XS GIS Cut Line= 3
      3628969.68     10174369.45      3627516.91     10176056.53
      3627360.66     10177184.99
#Sta/Elev= 30
  3248.9  196.69  3454.2   192.7  3532.1  193.41  3568.3  192.05  3595.7  192.88
  3652.8  191.89  4085.1  192.42  4302.6  190.85  4305.3  190.35  4308.6  190.85
  4666.6  192.13    4809  194.15  4850.9  193.06  4985.9  194.95  5000.1  192.48
  5014.4  194.61  5071.4  193.86  5141.7  195.15  5347.9  209.03  5440.1  213.69
  5520.8  216.24  5591.5  217.06    5695   215.6  5982.2  220.52  6186.5  219.57
    6418  222.12  6449.6  220.36  6489.8   223.5  6581.3  226.23  6614.5  227.01
#Mann= 5 ,-1 , 0
  3248.9     .05       0  4302.6     .03       0  4308.6     .05       0
  6186.5     .16       0  6581.3     .05       0
Bank Sta=4302.6,4308.6
XS Rating Curve= 0 ,0
Exp/Cntr=0.3,0.1
Stream Node=UNT097 IN ROCK  ,Reach-1         , 0 , 0 ,Upstream end
Stream Node=UNT097 IN ROCK  ,Reach-1         , 0 , 1 ,Downstream end

Chan Stop Cuts=-1
Use User Specified Reach Order=0
Composite Channel Slope=5