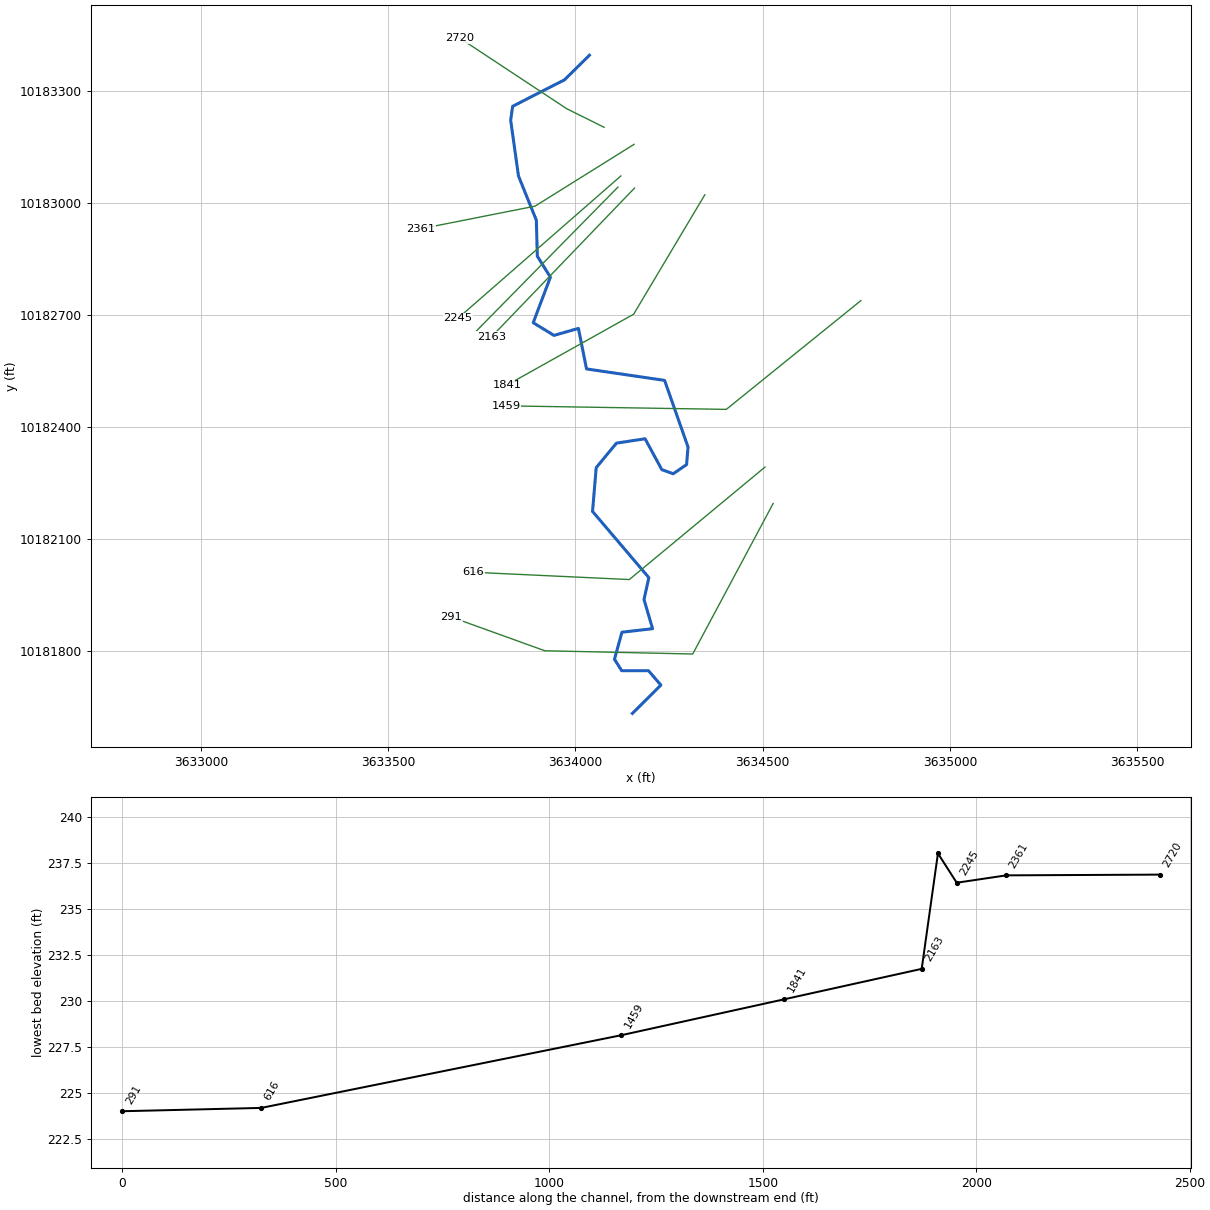
--- UNT098 IN ROCK.prj (project) ---

Proj Title=UNT098 IN ROCK Base Level Engineering
Current Plan=p01
Default Exp/Contr=0.3,0.1
English Units
Geom File=g01
Flow File=f01
Plan File=p01
Y Axis Title=Elevation
X Axis Title(PF)=Main Channel Distance
X Axis Title(XS)=Station
BEGIN DESCRIPTION:
UNT098 IN ROCK
END DESCRIPTION:
DSS Export Rating Curves= 0
DSS Export Rating Curve Sorted= 0
DSS Export Volume Flow Curves= 0
DXF OffsetX= 0
DXF OffsetY= 0
DXF ScaleX= 1
DXF ScaleY= 10

--- UNT098 IN ROCK.p01 (plan) ---

Plan Title=Multiple Run
Short Identifier=Multiple
Geom File=g01
Flow File=f01
Subcritical Flow
K Sum by GR= 0
Std Step Tol= 0.01
Critical Tol= 0.01
Num of Std Step Trials= 20
Max Error Tol= 0.3
Flow Tol Ratio= 0.001
Split Flow NTrial= 30
Split Flow Tol= 0.02
Split Flow Ratio= 0.02
Log Output Level= 0
Friction Slope Method= 1
Unsteady Friction Slope Method= 2
Unsteady Bridges Friction Slope Method= 1
Parabolic Critical Depth
Global Vel Dist=  1 , 1 , 1
Global Log Level= 0
CheckData=True
Encroach Param= -1, 0, 0, 0
BEGIN DESCRIPTION:
Multiple Run
END DESCRIPTION:

--- UNT098 IN ROCK.f01 (steady flow) ---

Flow Title=Multiple
Number of Profiles=7
Profile Names=10-year,25-year,50-year,1pct_min,100-year,1pct_plu,500-year
River Rch & RM= UNT098 IN ROCK,Reach-1,2720
     363     473     560     487     659     891     911
Boundary for River Rch & Prof#=UNT098 IN ROCK,Reach-1,1
Up Type=0
Dn Type=3
Dn Slope=0.005
Boundary for River Rch & Prof#=UNT098 IN ROCK,Reach-1,2
Up Type=0
Dn Type=3
Dn Slope=0.005
Boundary for River Rch & Prof#=UNT098 IN ROCK,Reach-1,3
Up Type=0
Dn Type=3
Dn Slope=0.005
Boundary for River Rch & Prof#=UNT098 IN ROCK,Reach-1,4
Up Type=0
Dn Type=3
Dn Slope=0.005
Boundary for River Rch & Prof#=UNT098 IN ROCK,Reach-1,5
Up Type=0
Dn Type=3
Dn Slope=0.005
Boundary for River Rch & Prof#=UNT098 IN ROCK,Reach-1,6
Up Type=0
Dn Type=3
Dn Slope=0.005
Boundary for River Rch & Prof#=UNT098 IN ROCK,Reach-1,7
Up Type=0
Dn Type=3
Dn Slope=0.005

--- UNT098 IN ROCK.g01 (geometry) ---

Geom Title=Existing Conditions
Program Version=4.10

River Reach=UNT098 IN ROCK  ,Reach-1
Reach XY= 30
       3634037.3     10183396.37      3633971.06      10183330.6
      3633832.22     10183259.37      3633827.01     10183222.05
      3633847.84     10183072.74      3633895.59     10182953.82
      3633898.19     10182857.46      3633933.14     10182801.24
      3633887.21     10182679.18      3633942.64     10182645.12
      3634008.01     10182663.86      3634029.62     10182555.21
      3634238.08      10182524.5      3634300.63     10182345.88
      3634296.78     10182298.77      3634261.03     10182274.11
      3634230.59     10182285.28      3634185.99     10182367.94
      3634109.54     10182356.27      3634055.44      10182290.6
      3634045.63     10182173.14      3634195.97     10181995.67
      3634183.11     10181936.83      3634205.96     10181858.69
      3634124.11     10181849.27      3634104.22     10181776.68
      3634123.55     10181746.06      3634195.11      10181746.1
      3634228.17     10181707.42      3634152.11     10181631.64

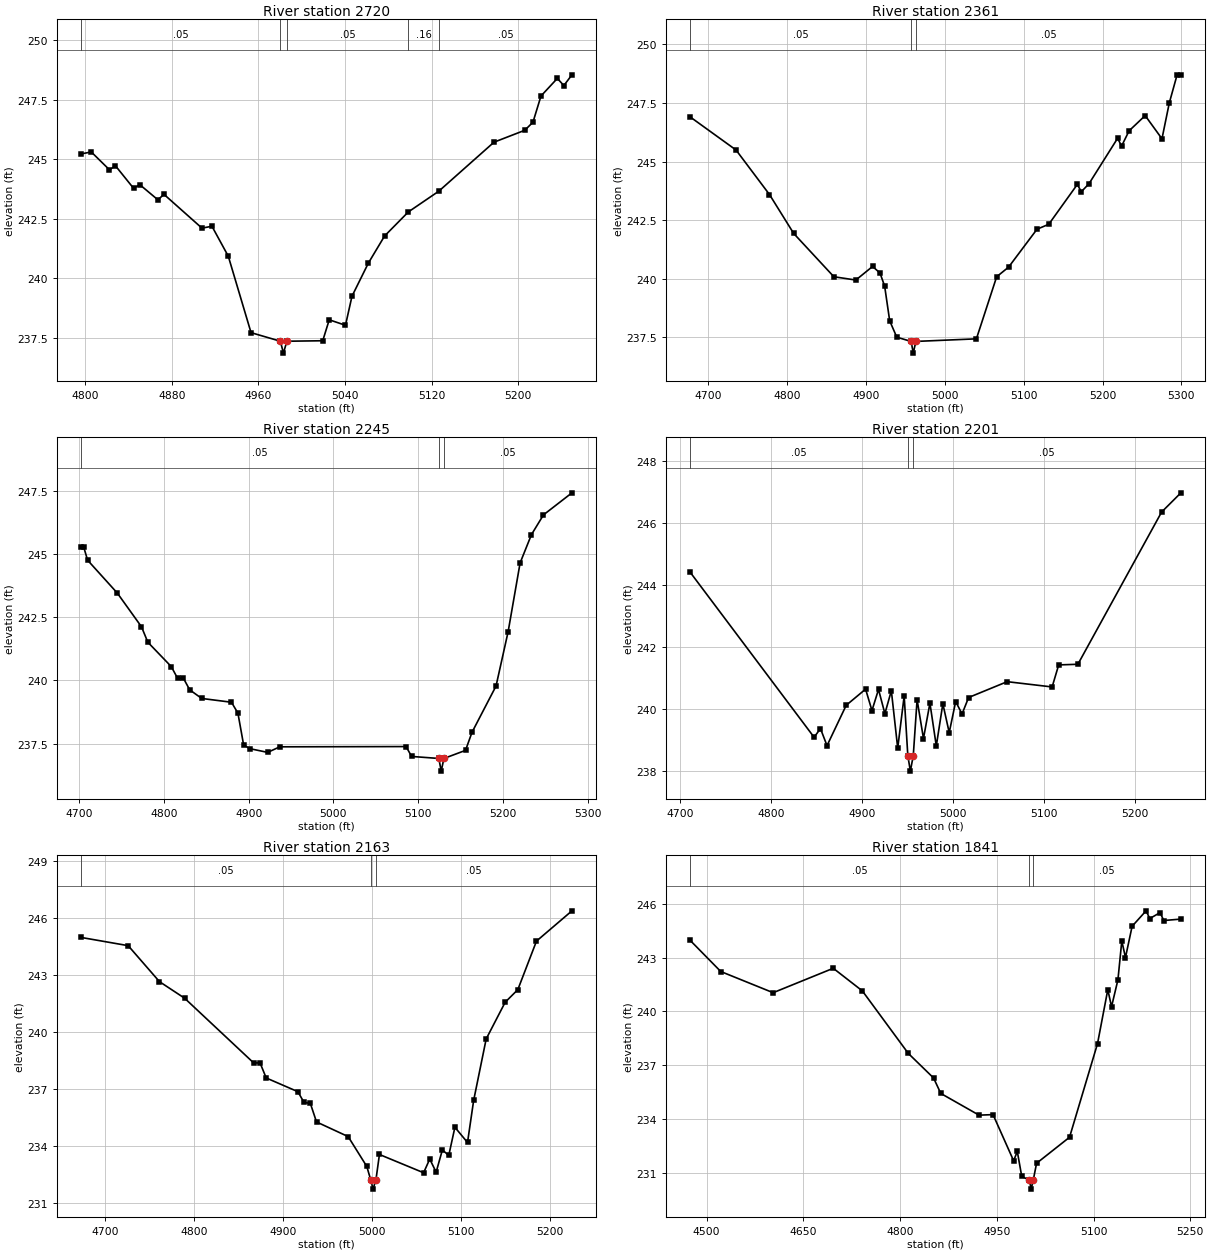
Type RM Length L Ch R = 1 ,2720    ,359,359,359
BEGIN DESCRIPTION:
UNT098 IN ROCK 5.0
END DESCRIPTION:
XS GIS Cut Line= 3
      3634076.46     10183203.11      3633976.48      10183253.1
      3633692.09     10183441.65
#Sta/Elev= 30
  4796.5  245.23  4805.7  245.31  4822.5  244.56    4828  244.73  4844.8  243.78
  4850.4  243.94  4867.2   243.3  4872.8  243.53  4907.9  242.11  4917.1  242.19
  4932.2  240.93  4953.2  237.72  4980.3  237.36  4983.1  236.86  4986.3  237.36
  5019.4  237.38  5025.4  238.26  5040.4  238.03  5046.4  239.25  5061.5  240.64
  5076.5  241.78  5098.4  242.79  5126.5  243.66  5177.5  245.72  5205.9  246.22
  5213.5  246.56  5220.9  247.66    5236   248.4    5242   248.1  5249.5  248.55
#Mann= 5 ,-1 , 0
  4796.5     .05       0  4980.3     .03       0  4986.3     .05       0
  5098.4     .16       0  5126.5     .05       0
Bank Sta=4980.3,4986.3
XS Rating Curve= 0 ,0
Exp/Cntr=0.3,0.1

Type RM Length L Ch R = 1 ,2361    ,116,116,116
BEGIN DESCRIPTION:
UNT098 IN ROCK 4.0
END DESCRIPTION:
XS GIS Cut Line= 3
      3634156.49      10183157.4      3633892.11     10182991.64
      3633587.71     10182931.13
#Sta/Elev= 30
  4676.9   246.9    4735  245.49  4777.4  243.59  4808.1  241.93  4859.1  240.08
    4887  239.94  4908.2  240.52  4917.6  240.24  4923.5  239.68  4929.9   238.2
  4938.9   237.5  4957.1  237.32  4959.8  236.82  4963.1  237.32  5039.9  237.43
  5065.6  240.08  5080.7  240.49  5116.8  242.11  5131.7  242.32  5167.9  244.02
    5173  243.71  5182.7  244.05    5219  245.99  5224.1  245.66  5233.6  246.31
    5254  246.96  5275.3  245.97  5284.6   247.5  5294.5   248.7  5299.3   248.7
#Mann= 3 ,-1 , 0
  4676.9     .05       0  4957.1     .03       0  4963.1     .05       0
Bank Sta=4957.1,4963.1
XS Rating Curve= 0 ,0
Exp/Cntr=0.3,0.1

Type RM Length L Ch R = 1 ,2245    ,44,44,44
BEGIN DESCRIPTION:
Mapping XS 2fe845bc
END DESCRIPTION:
XS GIS Cut Line= 2
      3634121.28     10183072.72       3633686.1      10182690.8
#Sta/Elev= 30
  4702.5  245.27  4705.3  245.27  4709.9  244.75    4745  243.45  4773.5  242.12
    4781  241.51  4808.6  240.55  4816.2  240.08  4822.8   240.1  4830.4  239.63
  4844.6  239.29  4879.7  239.14  4887.3  238.71    4894  237.46    4901  237.31
  4922.4  237.16  4936.7  237.38  5085.7  237.39  5092.3     237  5124.4  236.92
  5127.2  236.42  5130.4  236.92  5155.9  237.24  5163.5  237.95  5191.9  239.78
  5206.2  241.93  5220.3  244.64  5233.7  245.76  5247.9  246.54  5281.5  247.41
#Mann= 3 ,-1 , 0
  4702.5     .05       0  5124.4     .03       0  5130.4     .05       0
Bank Sta=5124.4,5130.4
XS Rating Curve= 0 ,0
Exp/Cntr=0.3,0.1

Type RM Length L Ch R = 1 ,2201    ,38,38,38
BEGIN DESCRIPTION:
Mapping XS 2580a8d1
END DESCRIPTION:
XS GIS Cut Line= 2
      3634113.46     10183042.77       3633736.1     10182657.63
#Sta/Elev= 30
  4711.1  244.41  4847.2   239.1  4854.2  239.38  4861.4  238.83  4882.5  240.13
  4903.8  240.65  4910.8  239.96    4918  240.64    4925  239.86  4932.1   240.6
  4939.1  238.75  4946.2  240.43  4950.2  238.51    4953  238.01  4956.2  238.51
  4960.4  240.31  4967.4  239.06  4974.5   240.2  4981.5  238.82  4988.7  240.18
  4995.7  239.25  5002.8  240.25  5009.8  239.85    5017  240.38  5059.4  240.89
  5108.8  240.72    5116  241.43  5137.1  241.45  5229.1  246.35  5250.3  246.97
#Mann= 3 ,-1 , 0
  4711.1     .05       0  4950.2     .03       0  4956.2     .05       0
Bank Sta=4950.2,4956.2
XS Rating Curve= 0 ,0
Exp/Cntr=0.3,0.1

Type RM Length L Ch R = 1 ,2163    ,322,322,322
BEGIN DESCRIPTION:
Mapping XS 1abec70a
END DESCRIPTION:
XS GIS Cut Line= 2
      3634157.79     10183040.22        3633776.     10182641.55
#Sta/Elev= 30
  4672.8  244.97  4725.5  244.54  4760.7  242.65    4789  241.78  4866.7  238.38
  4873.9  238.38  4880.8  237.59  4916.4  236.87  4923.3  236.31  4930.5  236.25
  4937.4  235.28    4973  234.51    4994  232.94  4998.3  232.25    5001  231.75
  5004.3  232.25  5008.2  233.57  5057.9  232.61  5064.8  233.33    5072  232.64
    5079  233.81  5086.2  233.52  5093.1     235  5107.3   234.2  5114.2  236.41
  5128.3  239.64  5149.7  241.57  5163.9  242.23  5184.9  244.78  5224.8  246.37
#Mann= 3 ,-1 , 0
  4672.8     .05       0  4998.3     .03       0  5004.3     .05       0
Bank Sta=4998.3,5004.3
XS Rating Curve= 0 ,0
Exp/Cntr=0.3,0.1

Type RM Length L Ch R = 1 ,1841    ,382,382,382
BEGIN DESCRIPTION:
UNT098 IN ROCK 3.0
END DESCRIPTION:
XS GIS Cut Line= 3
      3634345.53     10183022.28      3634155.43     10182701.97
      3633817.01     10182511.93
#Sta/Elev= 30
  4474.7  243.95    4522  242.22  4603.2  241.04  4696.4   242.4  4741.5  241.14
  4812.7  237.66  4851.9  236.29  4863.1  235.43  4922.4  234.22  4944.1  234.25
    4976  231.68  4981.7   232.2  4988.6  230.81  5000.4   230.6  5003.2   230.1
  5006.4   230.6  5011.6  231.54  5062.7  232.99  5106.1  238.21    5122  241.21
  5127.8  240.26  5137.7  241.76  5143.7  243.92  5149.4     243  5159.7  244.74
  5181.3   245.6  5187.1  245.17    5203   245.5  5208.8  245.06  5235.3  245.14
#Mann= 3 ,-1 , 0
  4474.7     .05       0  5000.4     .03       0  5006.4     .05       0
Bank Sta=5000.4,5006.4
XS Rating Curve= 0 ,0
Exp/Cntr=0.3,0.1

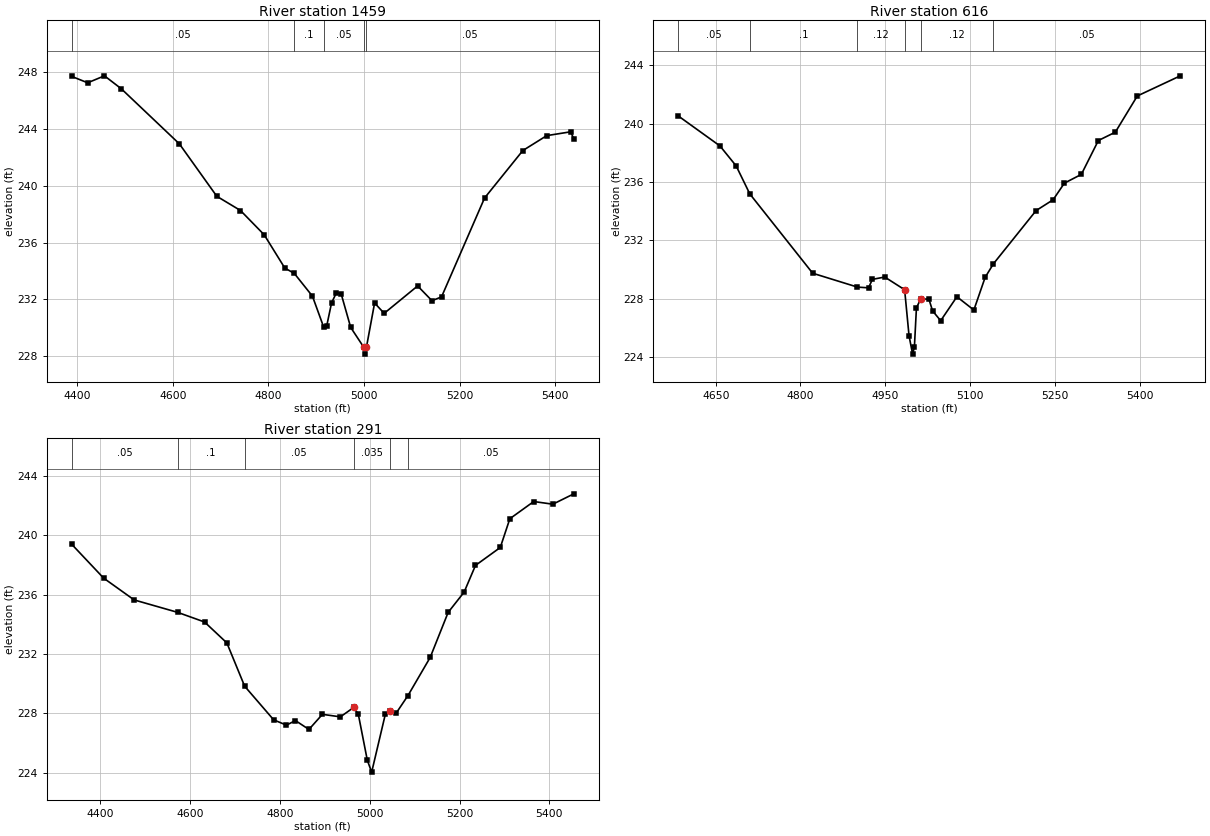
Type RM Length L Ch R = 1 ,1459    ,843,843,843
BEGIN DESCRIPTION:
UNT098 IN ROCK 2.0
END DESCRIPTION:
XS GIS Cut Line= 3
      3634762.22     10182738.43      3634402.83     10182446.76
      3633815.46     10182456.19
#Sta/Elev= 30
  4388.6   247.7  4422.1  247.25  4457.2  247.74  4492.4  246.83  4613.9  242.95
  4692.2  239.26  4741.7  238.26  4791.3  236.55  4834.4  234.21  4854.3  233.83
  4892.2  232.23  4915.5  230.07  4922.2  230.16  4932.2  231.76  4942.2  232.46
  4952.2   232.4  4972.2  230.03  4999.2  228.65  5001.9  228.15  5005.2  228.65
  5022.2  231.75  5042.2  231.02  5112.2  232.95  5142.2  231.91  5162.2  232.18
  5252.2  239.14  5332.2  242.48  5382.2  243.53  5432.3   243.8  5438.9  243.29
#Mann= 5 ,-1 , 0
  4388.6     .05       0  4854.3      .1       0  4915.5     .05       0
  4999.2     .03       0  5005.2     .05       0
Bank Sta=4999.2,5005.2
XS Rating Curve= 0 ,0
Exp/Cntr=0.3,0.1

Type RM Length L Ch R = 1 ,616     ,325,325,325
BEGIN DESCRIPTION:
Mapping XS d950d904
END DESCRIPTION:
XS GIS Cut Line= 3
      3634506.26     10182292.12      3634143.87     10181990.49
      3633727.22     10182010.02
#Sta/Elev= 30
  4583.5  240.53  4657.5  238.47  4686.2   237.1  4710.4  235.18  4821.6  229.75
  4900.9   228.8  4920.5  228.75  4927.2  229.33  4949.1  229.49  4984.3  228.62
  4992.1  225.47  4998.4  224.21  5001.6  224.71  5005.2  227.38  5012.9     228
  5027.3  227.97  5033.8  227.17  5048.1   226.5  5076.8  228.14  5106.8  227.23
  5126.8  229.47  5141.5   230.4  5216.9  234.04    5247  234.78    5267  235.92
    5297  236.52  5327.1  238.84  5357.1  239.41    5396  241.89  5472.1  243.27
#Mann= 6 ,-1 , 0
  4583.5     .05       0  4710.4      .1       0  4900.9     .12       0
  4984.3     .05       0  5012.9     .12       0  5141.5     .05       0
Bank Sta=4984.3,5012.9
XS Rating Curve= 0 ,0
Exp/Cntr=0.3,0.1

Type RM Length L Ch R = 1 ,291     ,0,0,0
BEGIN DESCRIPTION:
UNT098 IN ROCK 1.0
END DESCRIPTION:
XS GIS Cut Line= 4
        3634528.     10182194.52      3634313.14     10181790.84
      3633918.17     10181799.52      3633668.13     10181890.09
#Sta/Elev= 30
  4336.1  239.41  4407.4  237.12  4475.3  235.65  4572.3  234.81  4632.1  234.16
  4681.7  232.75  4721.3  229.83  4785.9  227.56  4814.4   227.2  4834.4  227.51
  4864.5  226.91  4894.5  227.93  4934.5  227.76  4964.5   228.4  4974.5  227.93
  4994.5  224.83  5004.2  224.03  5034.5  227.92  5044.5  228.18  5058.5     228
  5085.1   229.2  5134.5  231.77  5174.5  234.81  5210.1  236.18  5235.4  237.98
  5290.6  239.19  5311.9  241.13  5365.1  242.29  5407.6  242.11  5454.4  242.81
#Mann= 6 ,-1 , 0
  4336.1     .05       0  4572.3      .1       0  4721.3     .05       0
  4964.5    .035       0  5044.5     .05       0  5085.1     .05       0
Bank Sta=4964.5,5044.5
XS Rating Curve= 0 ,0
Exp/Cntr=0.3,0.1

Chan Stop Cuts=-1
Use User Specified Reach Order=0
Composite Channel Slope=5