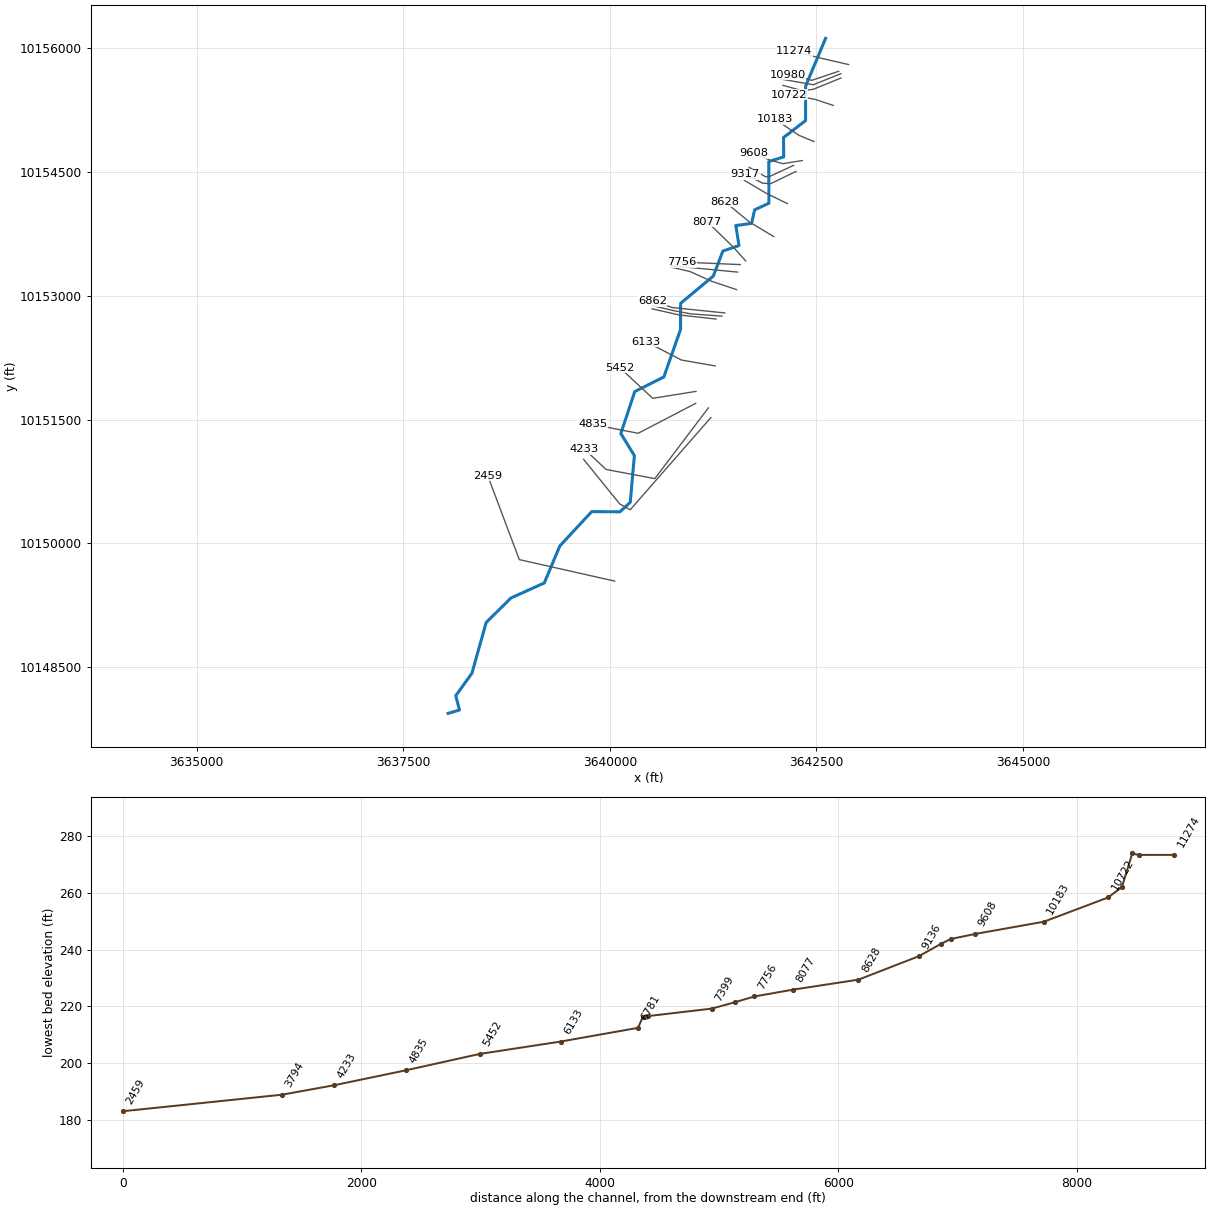
--- UNT101 IN ROCK.prj (project) ---

Proj Title=UNT101 IN ROCK Base Level Engineering
Current Plan=p01
Default Exp/Contr=0.3,0.1
English Units
Geom File=g01
Flow File=f01
Plan File=p01
Y Axis Title=Elevation
X Axis Title(PF)=Main Channel Distance
X Axis Title(XS)=Station
BEGIN DESCRIPTION:
UNT101 IN ROCK
END DESCRIPTION:
DSS Export Rating Curves= 0
DSS Export Rating Curve Sorted= 0
DSS Export Volume Flow Curves= 0
DXF OffsetX= 0
DXF OffsetY= 0
DXF ScaleX= 1
DXF ScaleY= 10

--- UNT101 IN ROCK.p01 (plan) ---

Plan Title=Multiple Run
Short Identifier=Multiple
Geom File=g01
Flow File=f01
Subcritical Flow
K Sum by GR= 0
Std Step Tol= 0.01
Critical Tol= 0.01
Num of Std Step Trials= 20
Max Error Tol= 0.3
Flow Tol Ratio= 0.001
Split Flow NTrial= 30
Split Flow Tol= 0.02
Split Flow Ratio= 0.02
Log Output Level= 0
Friction Slope Method= 1
Unsteady Friction Slope Method= 2
Unsteady Bridges Friction Slope Method= 1
Parabolic Critical Depth
Global Vel Dist=  1 , 1 , 1
Global Log Level= 0
CheckData=True
Encroach Param= -1, 0, 0, 0
BEGIN DESCRIPTION:
Multiple Run
END DESCRIPTION:

--- UNT101 IN ROCK.f01 (steady flow) ---

Flow Title=Multiple
Program Version=4.10
Number of Profiles= 7
Profile Names=10-year,25-year,50-year,1pct_min,100-year,1pct_plu,500-year
River Rch & RM=UNT101 IN ROCK,Reach-1         ,11274
     465     618     742     653     884    1195    1255
Boundary for River Rch & Prof#=UNT101 IN ROCK,Reach-1         , 1
Up Type= 0
Dn Type= 3
Dn Slope=0.005
Boundary for River Rch & Prof#=UNT101 IN ROCK,Reach-1         , 2
Up Type= 0
Dn Type= 3
Dn Slope=0.005
Boundary for River Rch & Prof#=UNT101 IN ROCK,Reach-1         , 3
Up Type= 0
Dn Type= 3
Dn Slope=0.005
Boundary for River Rch & Prof#=UNT101 IN ROCK,Reach-1         , 4
Up Type= 0
Dn Type= 3
Dn Slope=0.005
Boundary for River Rch & Prof#=UNT101 IN ROCK,Reach-1         , 5
Up Type= 0
Dn Type= 3
Dn Slope=0.005
Boundary for River Rch & Prof#=UNT101 IN ROCK,Reach-1         , 6
Up Type= 0
Dn Type= 3
Dn Slope=0.005
Boundary for River Rch & Prof#=UNT101 IN ROCK,Reach-1         , 7
Up Type= 0
Dn Type= 3
Dn Slope=0.005
DSS Import GetInterval= 0
DSS Import GetPeak= 0
DSS Import FillOption= 0

--- UNT101 IN ROCK.g01 (geometry) ---

Geom Title=Existing Conditions
Program Version=4.10

River Reach=UNT101 IN ROCK  ,Reach-1
Reach XY= 30
      3642611.39     10156117.78      3642369.74     10155539.55
       3642369.1      10155121.8      3642102.18      10154915.7
       3642104.2     10154681.64      3641924.22     10154625.55
      3641925.49     10154120.37      3641752.77     10154040.95
      3641714.95     10153876.33      3641524.77     10153850.21
       3641563.4     10153608.06      3641368.09     10153541.22
      3641251.84     10153237.31      3640856.55     10152908.48
      3640855.86     10152591.99      3640653.41     10152015.93
      3640301.24     10151838.67      3640133.17     10151331.07
      3640296.91     10151063.79      3640247.15     10150498.72
       3640122.4     10150382.89      3639781.07     10150385.52
       3639394.9      10149969.9       3639206.2     10149520.92
      3638802.99     10149339.35      3638502.93     10149041.93
      3638330.46     10148427.34      3638135.11     10148155.65
       3638180.2     10147982.38      3638042.11     10147941.64

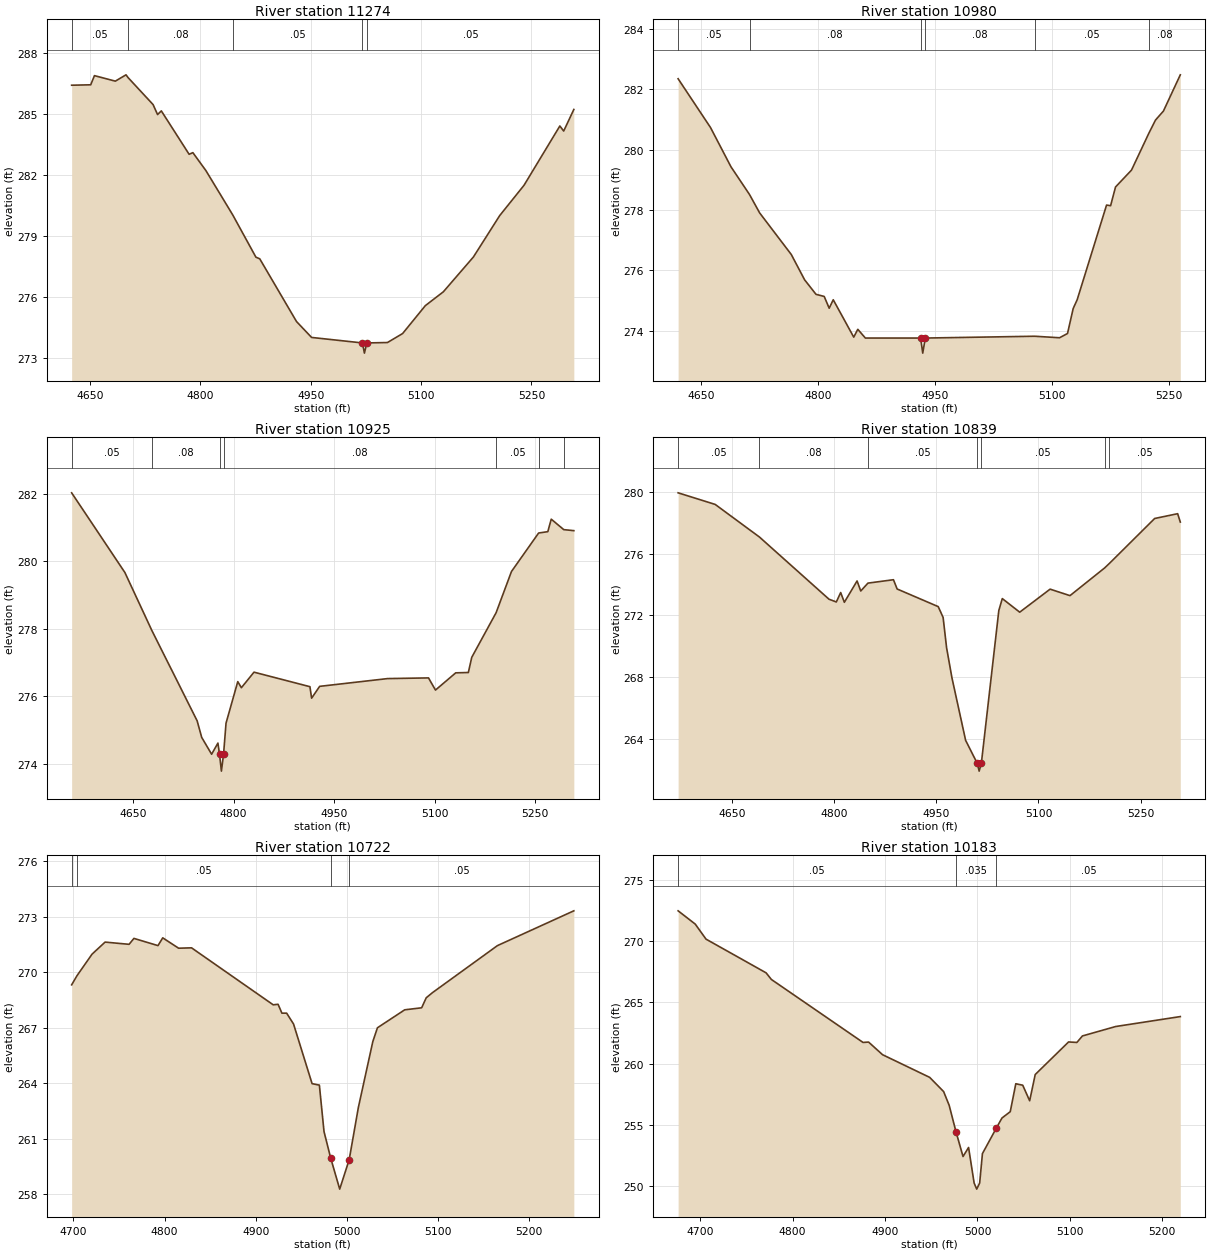
Type RM Length L Ch R = 1 ,11274   ,294,294,294
BEGIN DESCRIPTION:
UNT101 IN ROCK 18.0
END DESCRIPTION:
XS GIS Cut Line= 3
      3642890.03     10155800.31      3642550.62      10155878.2
       3642226.5     10155960.77
#Sta/Elev= 30
  4624.9  286.41  4650.8  286.43  4655.9  286.88  4684.3  286.61  4698.8  286.92
  4701.7  286.78  4735.6  285.46  4741.7  284.97  4746.8  285.15  4784.6  283.02
  4789.7   283.1  4807.4  282.22  4843.8  280.05  4875.4  277.97  4880.6  277.89
  4930.6  274.81  4951.1  274.03  5020.2  273.76  5022.9  273.26  5026.2  273.76
  5054.2  273.78  5074.8  274.22  5105.7  275.59  5130.2  276.27  5171.1  277.98
  5206.8  280.01  5239.9   281.5  5288.6  284.41  5293.8  284.16  5307.6  285.22
#Mann= 5 ,-1 , 0
  4624.9     .05       0  4701.7     .08       0  4843.8     .05       0
  5020.2     .03       0  5026.2     .05       0
Bank Sta=5020.2,5026.2
XS Rating Curve= 0 ,0
Exp/Cntr=0.3,0.1

Type RM Length L Ch R = 1 ,10980   ,55,55,55
BEGIN DESCRIPTION:
Mapping XS c2138d9d
END DESCRIPTION:
XS GIS Cut Line= 3
      3642769.73     10155718.85      3642445.05     10155609.46
      3642151.09      10155676.9
#Sta/Elev= 30
  4620.1  282.35  4661.7  280.73  4687.9  279.43  4711.7  278.51  4724.7   277.9
  4765.3  276.52  4782.4  275.68    4797   275.2  4807.5  275.13  4813.9  274.74
  4819.1  275.02  4845.4  273.78  4850.6  274.04  4860.3  273.75  4931.2  273.75
  4933.9  273.25  4937.2  273.75  5077.4  273.81  5109.4  273.76  5119.6   273.9
  5126.9  274.73    5132  275.02  5169.7  278.16  5174.9  278.14  5181.2  278.76
  5201.7  279.32  5224.1  280.55  5232.5  280.98  5242.7  281.28  5264.3  282.48
#Mann= 6 ,-1 , 0
  4620.1     .05       0  4711.7     .08       0  4931.2     .07       0
  4937.2     .08       0  5077.4     .05       0  5224.1     .08       0
Bank Sta=4931.2,4937.2
XS Rating Curve= 0 ,0
Exp/Cntr=0.3,0.1

Type RM Length L Ch R = 1 ,10925   ,87,87,87
BEGIN DESCRIPTION:
Mapping XS f44cc420
END DESCRIPTION:
XS GIS Cut Line= 3
      3642795.78     10155689.34      3642462.41     10155555.64
      3642078.72     10155623.35
#Sta/Elev= 30
  4558.6  282.02    4638  279.66  4678.3  277.94  4745.7  275.27  4752.5  274.78
  4767.3  274.28  4776.7  274.61  4779.1  274.28  4781.9  273.78  4785.1  274.28
  4788.8   275.2  4806.3  276.43  4811.7  276.25  4830.5  276.71  4913.9  276.28
  4916.4  275.94  4928.4  276.29  5029.8  276.52  5090.7  276.54  5101.1  276.18
  5131.3  276.69  5150.1   276.7  5155.2  277.15  5191.5  278.47  5214.4  279.69
  5254.9  280.83  5268.6  280.87  5273.7  281.24  5292.4  280.93  5307.4   280.9
#Mann= 7 ,-1 , 0
  4558.6     .05       0  4678.3     .08       0  4779.1     .07       0
  4785.1     .08       0  5191.5     .05       0  5254.9     .08       0
  5292.4     .05       0
Bank Sta=4779.1,4785.1
XS Rating Curve= 0 ,0
Exp/Cntr=0.3,0.1

Type RM Length L Ch R = 1 ,10839   ,116,116,116
BEGIN DESCRIPTION:
Mapping XS c171dccc
END DESCRIPTION:
XS GIS Cut Line= 4
      3642797.48     10155637.24      3642460.84     10155500.04
      3642328.95     10155484.08      3642095.72     10155548.32
#Sta/Elev= 30
  4570.2  279.93  4624.7  279.18  4689.8  277.07    4792  273.05  4802.8  272.87
  4809.2  273.48  4814.6  272.85  4833.3  274.23  4838.7  273.58  4849.3  274.09
  4886.8  274.31  4892.2  273.71  4952.6  272.57  4959.8  271.87  4964.9  269.91
  4972.7  267.98  4992.9  263.92    5010  262.43  5012.8  261.93    5016  262.43
  5041.7  272.32  5046.8  273.09  5072.4  272.21  5117.1   273.7  5146.3  273.28
  5197.2  275.07  5204.4  275.37  5270.8  278.27  5304.6  278.58  5308.5  278.04
#Mann= 7 ,-1 , 0
  4570.2     .05       0  4689.8     .08       0  4849.3     .05       0
    5010     .03       0    5016     .05       0  5197.2     .08       0
  5204.4     .05       0
Bank Sta=5010,5016
XS Rating Curve= 0 ,0
Exp/Cntr=0.3,0.1

Type RM Length L Ch R = 1 ,10722   ,539,539,539
BEGIN DESCRIPTION:
UNT101 IN ROCK 16.0
END DESCRIPTION:
XS GIS Cut Line= 3
      3642703.37     10155305.53      3642482.05      10155379.3
      3642169.59     10155435.72
#Sta/Elev= 30
  4698.1  269.33  4703.9  269.82  4720.5  270.99  4734.8  271.64  4761.1  271.52
  4766.4  271.84  4792.8  271.45    4798  271.87  4815.4  271.31  4829.6  271.33
  4919.2  268.25  4924.5  268.28  4928.7   267.8  4933.9   267.8  4941.5  267.21
  4961.8  263.99  4969.8  263.91  4974.9   261.4  4982.1  259.99  4992.1  258.29
  5002.5  259.88  5012.6  262.71  5028.4  266.26  5033.5  267.01  5063.4  267.98
    5082  268.09    5087  268.63  5093.9  268.91  5165.1  271.45  5248.9  273.33
#Mann= 4 ,-1 , 0
  4698.1     .08       0  4703.9     .05       0  4982.1    .035       0
  5002.5     .05       0
Bank Sta=4982.1,5002.5
XS Rating Curve= 0 ,0
Exp/Cntr=0.3,0.1

Type RM Length L Ch R = 1 ,10183   ,575,575,575
BEGIN DESCRIPTION:
UNT101 IN ROCK 15.0
END DESCRIPTION:
XS GIS Cut Line= 3
      3642470.04     10154867.86      3642292.11     10154941.64
      3642000.27     10155136.25
#Sta/Elev= 30
  4676.1  272.48  4694.6   271.4  4706.3  270.17  4771.3  267.42    4777  266.88
  4876.2  261.74  4882.2  261.77  4897.3  260.74  4948.3  258.89  4963.4  257.73
  4969.4  256.61  4976.9  254.42  4984.4  252.43  4990.4  253.17  4996.4  250.27
  4999.2  249.77  5002.4  250.27  5005.4  252.67  5020.5  254.76  5026.5  255.57
  5035.5  256.09  5041.5  258.37    5049  258.25  5056.5  256.98  5062.5  259.12
  5098.6  261.78  5107.6  261.74  5113.6  262.27  5149.6  263.04  5219.5  263.85
#Mann= 3 ,-1 , 0
  4676.1     .05       0  4976.9    .035       0  5020.5     .05       0
Bank Sta=4976.9,5020.5
XS Rating Curve= 0 ,0
Exp/Cntr=0.3,0.1

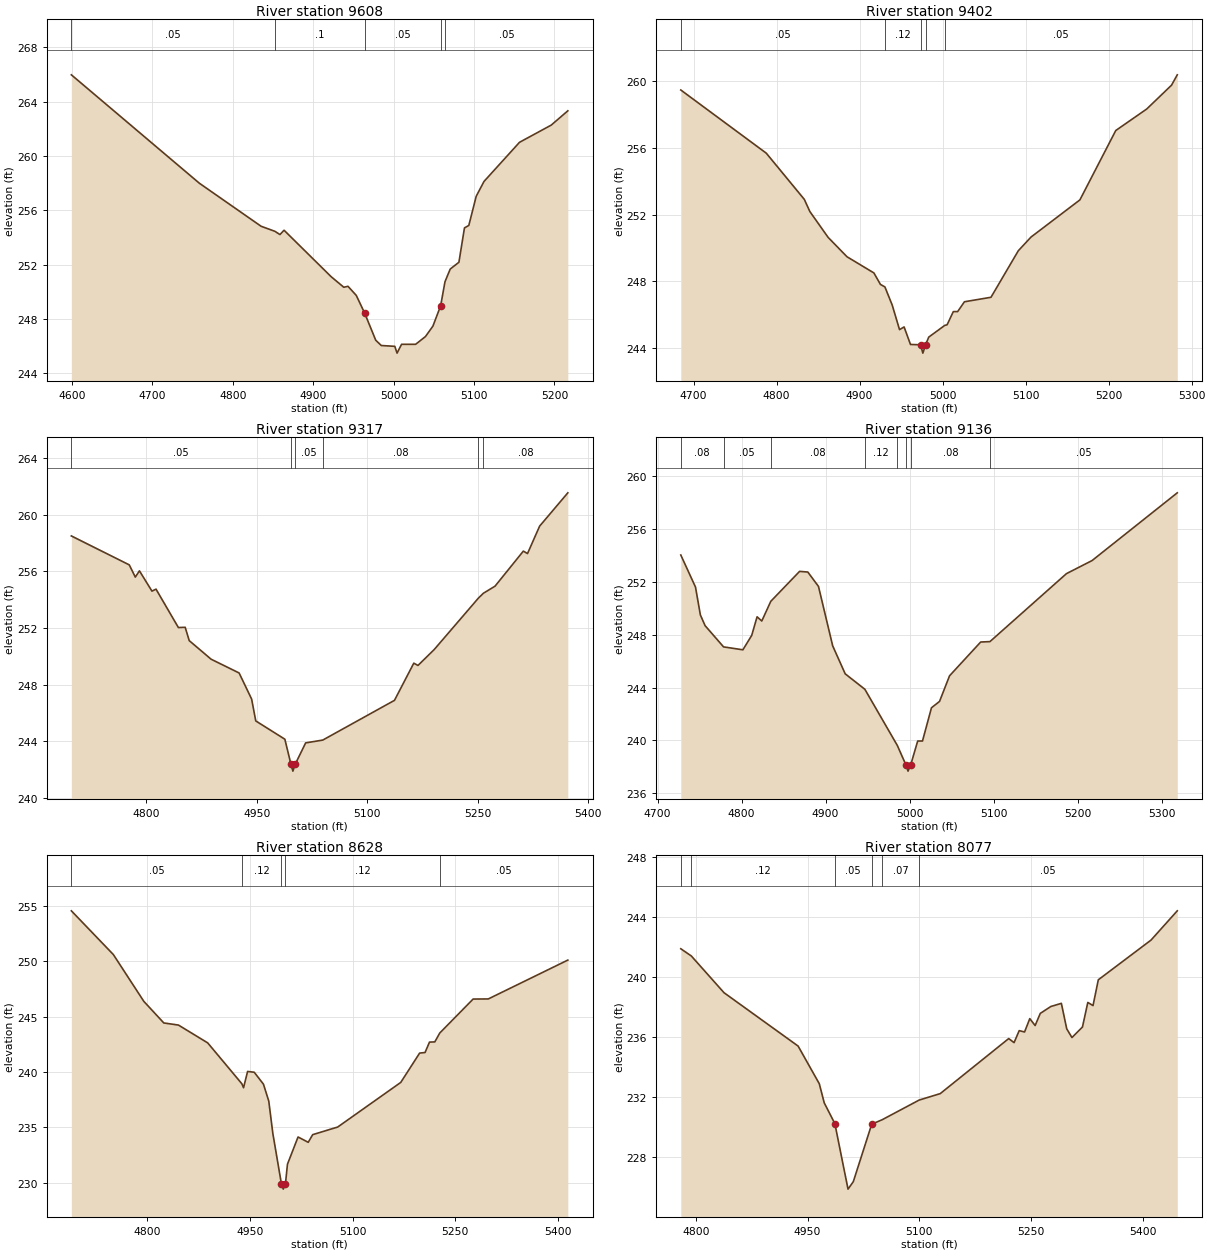
Type RM Length L Ch R = 1 ,9608    ,206,206,206
BEGIN DESCRIPTION:
UNT101 IN ROCK 14.0
END DESCRIPTION:
XS GIS Cut Line= 4
      3642329.12     10154637.67       3642095.5     10154599.77
      3641942.11     10154641.64      3641736.31     10154723.61
#Sta/Elev= 30
  4599.4  265.97  4758.5  257.99  4835.3  254.82  4852.4  254.45  4858.7  254.21
  4863.8  254.53  4922.5   251.1  4938.1  250.33  4943.3   250.4  4953.6  249.73
    4964  248.43  4977.8  246.43  4984.7  246.04  5001.5  245.98  5004.3  245.48
  5009.9  246.13  5027.4  246.13  5039.6   246.7  5048.9  247.47  5058.5  248.97
  5063.9  250.74  5070.4  251.67  5081.2  252.17  5088.1   254.7  5093.5  254.88
  5102.7  257.03  5112.4  258.12  5156.5     261    5196  262.27  5216.6  263.32
#Mann= 5 ,-1 , 0
  4599.4     .05       0  4852.4      .1       0    4964     .05       0
  5058.5      .1       0  5063.9     .05       0
Bank Sta=4964,5058.5
XS Rating Curve= 0 ,0
Exp/Cntr=0.3,0.1

Type RM Length L Ch R = 1 ,9402    ,85,85,85
BEGIN DESCRIPTION:
Mapping XS 5de5575e
END DESCRIPTION:
XS GIS Cut Line= 4
      3642223.24     10154578.64      3641923.44     10154439.93
       3641884.1     10154441.64      3641686.11     10154555.48
#Sta/Elev= 30
  4684.6  259.47  4787.6  255.68  4833.4  252.91  4840.1  252.18  4862.1  250.63
  4884.8  249.47  4917.2   248.5  4925.1  247.81  4930.5  247.66  4939.3  246.57
  4948.1   245.1  4953.6  245.26  4961.3  244.21  4973.5  244.19  4976.2  243.69
  4979.5  244.19  4983.3  244.65  5002.5  245.35  5005.4  245.39  5012.9  246.18
  5018.1  246.18  5026.3  246.77  5058.3  247.04  5091.2  249.83  5106.5  250.65
  5165.4  252.88  5208.6  257.04  5245.9  258.33  5275.8  259.76  5282.7  260.38
#Mann= 5 ,-1 , 0
  4684.6     .05       0  4930.5     .12       0  4973.5     .07       0
  4979.5     .12       0  5002.5     .05       0
Bank Sta=4973.5,4979.5
XS Rating Curve= 0 ,0
Exp/Cntr=0.3,0.1

Type RM Length L Ch R = 1 ,9317    ,181,181,181
BEGIN DESCRIPTION:
Mapping XS e59e95bd
END DESCRIPTION:
XS GIS Cut Line= 4
      3642252.77     10154505.73      3641948.96     10154358.16
      3641848.26     10154363.37      3641639.92     10154472.75
#Sta/Elev= 30
  4698.5  258.49  4777.1  256.45  4785.3  255.59  4790.9  256.03  4807.9   254.6
  4813.4  254.74  4843.8  252.03    4853  252.05  4858.5  251.11  4888.2   249.8
  4926.2  248.83  4943.2  246.99  4948.8  245.45  4988.3  244.16  4996.5  242.41
  4999.2  241.91  5002.5  242.41  5016.5   243.9  5039.8   244.1  5137.1   246.9
  5163.3  249.52    5169  249.36    5191  250.48  5250.9   254.1  5257.8  254.45
  5273.6  254.95    5312  257.42  5317.7  257.25  5334.1  259.18  5372.4  261.53
#Mann= 6 ,-1 , 0
  4698.5     .05       0  4996.5     .03       0  5002.5     .05       0
  5039.8     .08       0  5250.9     .05       0  5257.8     .08       0
Bank Sta=4996.5,5002.5
XS Rating Curve= 0 ,0
Exp/Cntr=0.3,0.1

Type RM Length L Ch R = 1 ,9136    ,508,508,508
BEGIN DESCRIPTION:
UNT101 IN ROCK 13.0
END DESCRIPTION:
XS GIS Cut Line= 3
      3642147.85     10154116.28      3641892.11     10154241.64
      3641628.55     10154397.49
#Sta/Elev= 30
  4727.7  254.04  4745.2  251.61    4751   249.5  4756.6  248.69  4778.6  247.08
  4801.6  246.86  4812.1  247.95  4818.5  249.36  4824.1  249.04  4834.8  250.53
  4869.1   252.8  4878.9  252.75  4891.6  251.66  4908.5  247.16  4923.4  245.04
  4946.8  243.87  4985.4  239.62  4995.5  238.17  4998.2  237.67  5001.5  238.17
  5009.7  239.95  5015.4  239.95  5026.1  242.47  5035.7  242.95  5047.6  244.89
  5084.7  247.45  5095.7  247.48  5186.8  252.63  5217.3  253.62  5318.7  258.75
#Mann= 8 ,-1 , 0
  4727.7     .08       0  4778.6     .05       0  4834.8     .08       0
  4946.8     .12       0  4985.4     .08       0  4995.5     .07       0
  5001.5     .08       0  5095.7     .05       0
Bank Sta=4995.5,5001.5
XS Rating Curve= 0 ,0
Exp/Cntr=0.3,0.1

Type RM Length L Ch R = 1 ,8628    ,552,552,552
BEGIN DESCRIPTION:
UNT101 IN ROCK 12.0
END DESCRIPTION:
XS GIS Cut Line= 3
      3641982.95     10153716.96      3641692.11     10153891.64
      3641393.44     10154137.32
#Sta/Elev= 30
  4688.7  254.55  4750.1   250.6  4794.7  246.37  4823.9  244.42  4845.3  244.23
  4888.1  242.62    4938  238.93  4940.5  238.57  4946.4  240.04  4956.1  239.97
  4969.6  238.89  4977.4  237.36  4983.3  234.45  4995.8  229.91  4998.6  229.41
  5001.8  229.91  5004.7  231.66  5020.2  234.12  5035.1  233.64  5041.6  234.33
  5078.2  235.02  5170.4  239.05    5198   241.7  5205.9  241.75  5212.4  242.69
  5220.2  242.71  5227.4  243.51  5276.2  246.58  5298.4  246.59  5414.7   250.1
#Mann= 5 ,-1 , 0
  4688.7     .05       0    4938     .12       0  4995.8     .07       0
  5001.8     .12       0  5227.4     .05       0
Bank Sta=4995.8,5001.8
XS Rating Curve= 0 ,0
Exp/Cntr=0.3,0.1

Type RM Length L Ch R = 1 ,8077    ,320,320,320
BEGIN DESCRIPTION:
UNT101 IN ROCK 11.0
END DESCRIPTION:
XS GIS Cut Line= 3
      3641644.38     10153421.83      3641492.11     10153591.64
      3641177.74     10153897.21
#Sta/Elev= 30
  4779.8  241.91  4793.9  241.43  4837.8  238.98  4937.3  235.42  4965.7  232.91
  4972.4  231.63  4986.6  230.25  5004.3  225.88  5011.4  226.38  5036.1  230.21
  5050.2  230.51  5099.8  231.82  5128.1  232.25    5220  235.92  5227.2  235.65
  5234.1  236.45  5241.3  236.36  5248.3  237.25  5255.5  236.79  5262.4   237.6
  5276.6  238.06  5290.7  238.27  5297.9  236.57  5304.9  235.99    5319  236.69
  5326.2  238.33  5333.2  238.12  5340.3  239.84  5411.1  242.49  5446.3  244.44
#Mann= 6 ,-1 , 0
  4779.8     .08       0  4793.9     .12       0  4986.6     .05       0
  5036.1     .12       0  5050.2     .07       0  5099.8     .05       0
Bank Sta=4986.6,5036.1
XS Rating Curve= 0 ,0
Exp/Cntr=0.3,0.1

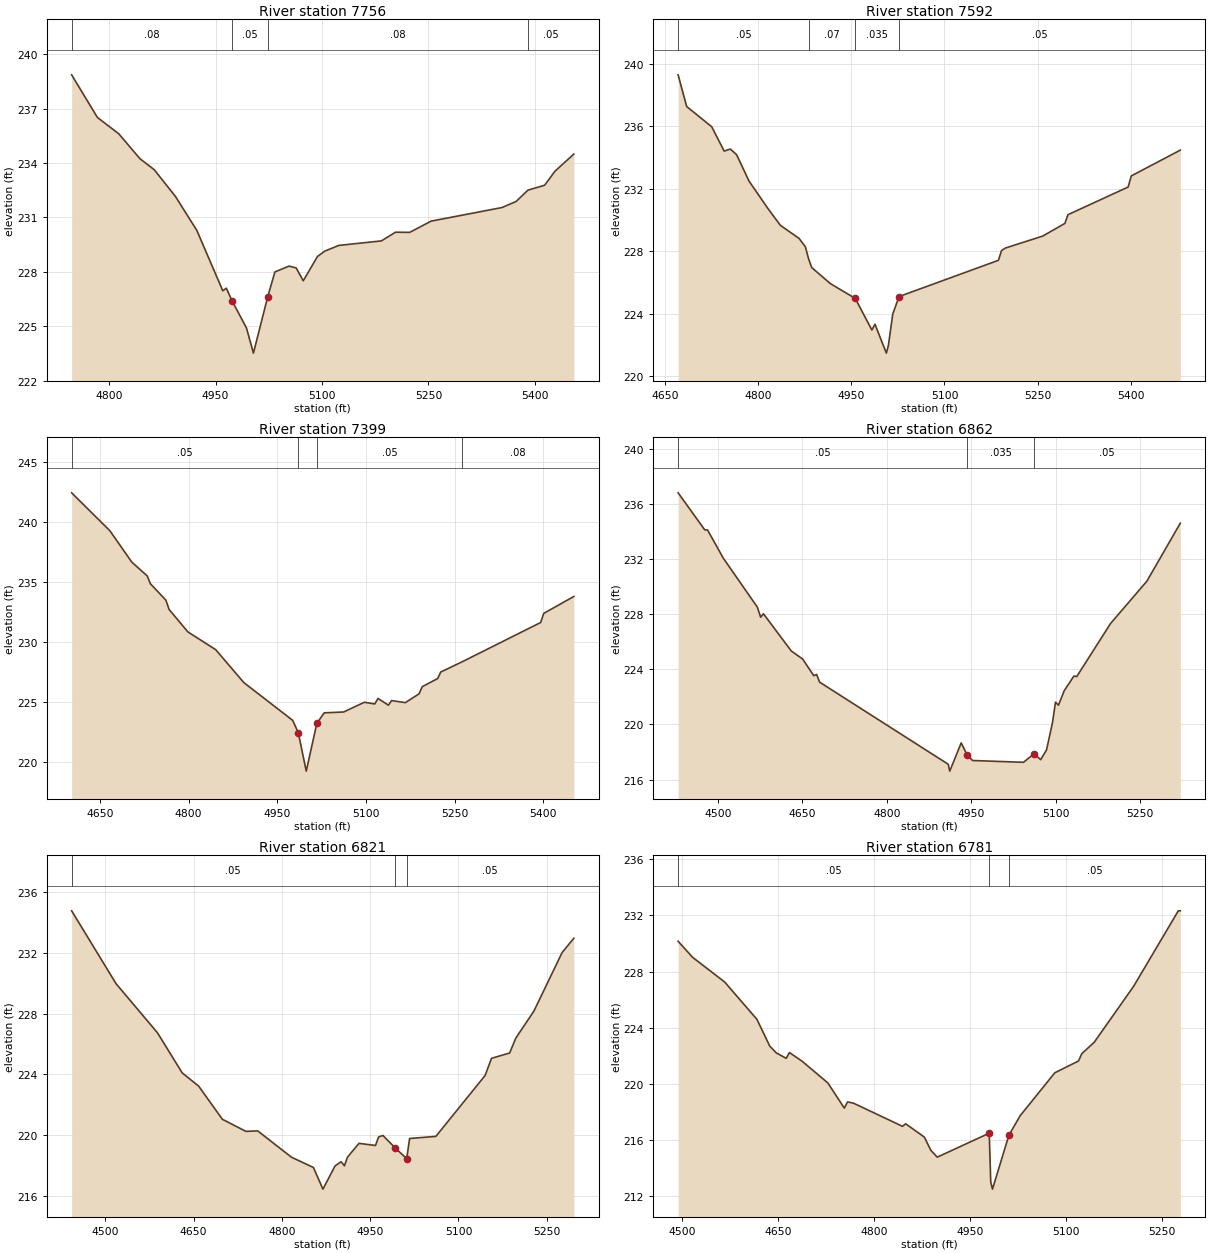
Type RM Length L Ch R = 1 ,7756    ,165,165,165
BEGIN DESCRIPTION:
Mapping XS 56a7976a
END DESCRIPTION:
XS GIS Cut Line= 2
      3641578.39     10153377.43      3640870.95     10153407.81
#Sta/Elev= 30
    4747  238.86  4783.3  236.51  4813.4  235.61  4843.4  234.23  4863.4  233.63
  4893.4  232.15  4923.5  230.28  4960.1  226.95  4965.1  227.09  4973.5  226.37
  4993.5   224.9  5003.3  223.51  5023.5  226.62  5033.6  227.99  5053.6  228.31
  5063.6  228.21  5073.6   227.5  5093.6  228.84  5103.6  229.13  5123.6  229.45
  5183.7   229.7  5203.7  230.18  5223.7  230.17  5253.8  230.79  5353.8  231.54
  5373.9  231.88  5390.4   232.5  5413.9  232.77  5428.4  233.54  5455.1  234.49
#Mann= 4 ,-1 , 0
    4747     .08       0  4973.5     .05       0  5023.5     .08       0
  5390.4     .05       0
Bank Sta=4973.5,5023.5
XS Rating Curve= 0 ,0
Exp/Cntr=0.3,0.1

Type RM Length L Ch R = 1 ,7592    ,193,193,193
BEGIN DESCRIPTION:
Mapping XS ed43769d
END DESCRIPTION:
XS GIS Cut Line= 2
      3641545.81     10153286.29      3640741.71     10153364.59
#Sta/Elev= 30
  4671.5  239.28  4685.3  237.25  4725.5  235.96  4745.6   234.4  4755.6  234.53
  4765.6  234.17  4785.7  232.47  4815.9  230.73    4836  229.65  4866.1  228.81
  4876.2  228.28  4881.3  227.52  4886.4  226.95  4916.4  225.92  4956.5  224.97
  4983.2  222.95  4988.2  223.32  5006.5  221.47  5009.8  221.97  5016.8  223.97
  5026.9  225.09  5186.8  227.41  5191.8  228.03  5197.7  228.19    5258  228.96
  5293.7  229.77  5298.7  230.33  5395.5   232.1  5400.5  232.81  5479.4  234.46
#Mann= 4 ,-1 , 0
  4671.5     .05       0  4881.3     .07       0  4956.5    .035       0
  5026.9     .05       0
Bank Sta=4956.5,5026.9
XS Rating Curve= 0 ,0
Exp/Cntr=0.3,0.1

Type RM Length L Ch R = 1 ,7399    ,536,536,536
BEGIN DESCRIPTION:
UNT101 IN ROCK 10.0
END DESCRIPTION:
XS GIS Cut Line= 4
      3641533.45     10153074.45      3641233.42     10153174.45
      3640970.65     10153292.98      3640731.95      10153349.4
#Sta/Elev= 30
  4602.1  242.44  4666.8  239.28  4703.8  236.67    4730  235.51  4735.4  234.86
  4761.6  233.49    4767  232.72  4798.7  230.85    4846  229.36  4893.5  226.62
  4976.2  223.47  4985.6  222.44  4999.1  219.24    5017  223.22  5029.5   224.1
  5062.4  224.17  5097.4  224.98    5115  224.84  5120.5   225.3  5138.1  224.74
  5143.6  225.12  5166.8  224.95  5189.9  225.68  5195.4  226.28  5221.5  226.96
  5226.7   227.5  5263.1  228.36  5395.8  231.63    5401  232.39  5451.9   233.8
#Mann= 4 ,-1 , 0
  4602.1     .05       0  4985.6    .035       0    5017     .05       0
  5263.1     .08       0
Bank Sta=4985.6,5017
XS Rating Curve= 0 ,0
Exp/Cntr=0.3,0.1

Type RM Length L Ch R = 1 ,6862    ,41,41,41
BEGIN DESCRIPTION:
UNT101 IN ROCK 8.0
END DESCRIPTION:
XS GIS Cut Line= 3
       3641392.1     10152791.64      3640759.64      10152856.4
      3640515.34     10152932.37
#Sta/Elev= 30
  4429.3  236.79  4476.5  234.11  4481.5   234.1  4509.7  232.04    4570   228.5
  4575.8  227.77  4580.8  228.02  4630.3  225.32  4650.4  224.74  4670.1  223.53
  4675.2  223.62  4680.6  223.06  4908.8  217.11  4911.6  216.61  4931.9  218.66
    4942  217.81    4952  217.38  5042.5  217.25  5061.3  217.87    5073  217.44
  5083.4  218.15  5093.9  220.11  5099.3  221.61  5104.6  221.39  5114.8  222.44
  5131.9   223.5  5137.1  223.47    5197  227.31  5261.5  230.38  5320.9  234.59
#Mann= 3 , 0 , 0
  4429.3     .05       0    4942    .035       0  5061.3     .05       0
Bank Sta=4942,5061.3
XS Rating Curve= 0 ,0
Exp/Cntr=0.3,0.1

Type RM Length L Ch R = 1 ,6821    ,41,41,41
BEGIN DESCRIPTION:
Mapping XS d9ac0093
END DESCRIPTION:
XS GIS Cut Line= 4
      3641357.43     10152753.21      3640982.39     10152780.56
      3640763.05     10152821.26      3640516.08     10152880.93
#Sta/Elev= 30
  4442.8  234.79  4518.3  229.98  4588.5  226.75  4630.6   224.1  4658.7  223.22
  4698.8  221.04  4738.9  220.24    4759  220.27  4816.5  218.53  4853.5  217.86
  4869.7  216.43  4890.3  217.96  4900.5  218.24  4906.3  217.97  4911.4  218.54
    4931  219.45  4959.1  219.31  4964.2  219.87  4971.7  219.97    4992  219.17
    5012  218.44    5017  219.77  5061.6  219.91  5145.3  223.93  5156.1  225.06
  5186.9  225.41  5197.5   226.4  5228.1  228.17  5276.1  232.04    5296  232.98
#Mann= 3 ,-1 , 0
  4442.8     .05       0    4992    .035       0    5012     .05       0
Bank Sta=4992,5012
XS Rating Curve= 0 ,0
Exp/Cntr=0.3,0.1

Type RM Length L Ch R = 1 ,6781    ,647,647,647
BEGIN DESCRIPTION:
Mapping XS 4072b064
END DESCRIPTION:
XS GIS Cut Line= 3
      3641284.47     10152718.06      3640836.56     10152767.54
      3640511.05     10152841.75
#Sta/Elev= 30
  4493.6  230.16  4516.1  229.02  4566.4  227.25  4616.7  224.59  4636.8  222.68
  4646.9   222.2  4662.4  221.81  4667.5  222.22  4687.1  221.61  4727.4  220.06
  4753.2  218.26  4758.3   218.7  4767.6  218.61  4844.1  216.96  4849.1  217.14
  4878.3  216.19  4888.4  215.25  4898.4  214.76  4979.6  216.47    4982  212.98
  4984.7  212.48  5010.3  216.32    5028  217.72  5082.1  220.78  5119.1  221.62
  5124.2  222.14  5143.7  222.96  5205.1  226.94    5275  232.33  5278.1  232.33
#Mann= 3 , 0 , 0
  4493.6     .05       0  4979.6    .035       0  5010.3     .05       0
Bank Sta=4979.6,5010.3
XS Rating Curve= 0 ,0
Exp/Cntr=0.3,0.1

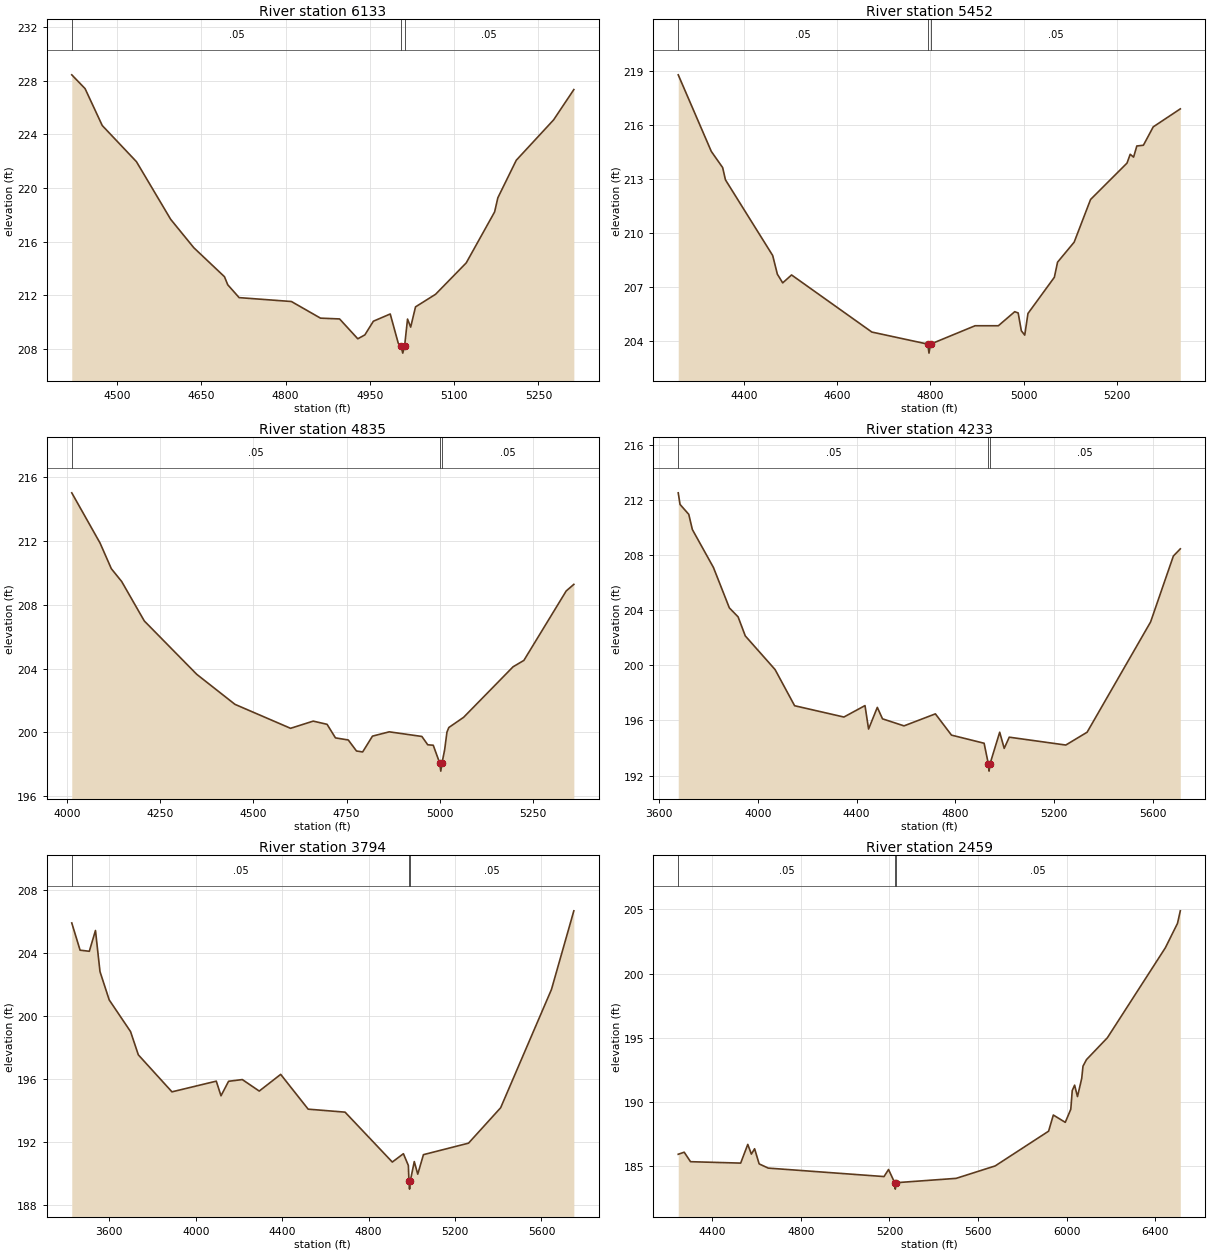
Type RM Length L Ch R = 1 ,6133    ,681,681,681
BEGIN DESCRIPTION:
UNT101 IN ROCK 7.0
END DESCRIPTION:
XS GIS Cut Line= 3
      3641275.48     10152150.13        3640867.     10152221.31
      3640442.07     10152441.66
#Sta/Elev= 30
  4419.7  228.44  4443.4  227.41  4473.9  224.66  4534.8  221.96  4595.7  217.66
  4636.9  215.54  4691.4  213.38  4697.2  212.78  4717.5  211.82  4810.5  211.53
  4862.2  210.29  4896.2  210.23  4928.6  208.75  4941.2  209.04  4956.3  210.06
  4986.3   210.6  5000.6  208.42  5005.8  208.18  5008.6  207.68  5011.8  208.18
  5017.1  210.22  5022.7  209.62  5031.3  211.13    5067  212.07  5121.5  214.41
    5172  218.21  5177.8  219.27  5210.6  222.07    5277  225.08    5313  227.34
#Mann= 3 ,-1 , 0
  4419.7     .05       0  5005.8     .03       0  5011.8     .05       0
Bank Sta=5005.8,5011.8
XS Rating Curve= 0 ,0
Exp/Cntr=0.3,0.1

Type RM Length L Ch R = 1 ,5452    ,617,617,617
BEGIN DESCRIPTION:
UNT101 IN ROCK 6.0
END DESCRIPTION:
XS GIS Cut Line= 3
      3641042.15     10151841.65       3640518.5     10151757.34
      3640119.19     10152130.61
#Sta/Elev= 30
  4259.1  218.76    4330  214.51  4354.4  213.61  4360.4  212.93  4461.7  208.73
  4471.8  207.69  4483.2  207.21  4502.2  207.65  4674.4  204.48  4794.3  203.81
    4797  203.31  4800.3  203.81  4895.9  204.83  4945.8  204.83  4980.9  205.61
  4988.3  205.54  4995.1  204.55  5002.4  204.31  5009.3  205.51  5065.9  207.52
  5072.8  208.36  5108.4  209.47  5143.6  211.84  5221.8  213.86  5228.6  214.35
  5235.9  214.19  5242.8  214.81  5256.9  214.85    5278  215.87  5336.1  216.87
#Mann= 3 ,-1 , 0
  4259.1     .05       0  4794.3     .04       0  4800.3     .05       0
Bank Sta=4794.3,4800.3
XS Rating Curve= 0 ,0
Exp/Cntr=0.3,0.1

Type RM Length L Ch R = 1 ,4835    ,602,602,602
BEGIN DESCRIPTION:
UNT101 IN ROCK 5.0
END DESCRIPTION:
XS GIS Cut Line= 3
      3641039.33     10151696.58      3640342.97      10151334.1
      3639792.13     10151441.64
#Sta/Elev= 30
  4013.2     215    4089  211.86  4119.3  210.25    4147  209.45  4207.7  206.98
  4348.3  203.64  4450.8  201.76  4599.9  200.26  4660.6  200.71  4697.8  200.51
  4720.3  199.66  4754.6  199.53  4776.7  198.84  4793.2  198.78  4819.5  199.77
  4864.5  200.04    4952  199.75  4967.7  199.23  4982.5   199.2  4999.9  198.08
  5002.7  197.58  5005.9  198.08  5013.1  198.92  5019.2  200.02  5024.3  200.31
    5064  200.95  5196.5  204.11  5225.5  204.51  5339.1  208.86  5359.5  209.27
#Mann= 3 ,-1 , 0
  4013.2     .05       0  4999.9     .03       0  5005.9     .05       0
Bank Sta=4999.9,5005.9
XS Rating Curve= 0 ,0
Exp/Cntr=0.3,0.1

Type RM Length L Ch R = 1 ,4233    ,439,439,439
BEGIN DESCRIPTION:
UNT101 IN ROCK 4.0
END DESCRIPTION:
XS GIS Cut Line= 4
      3641192.11     10151641.65      3640544.55     10150785.12
      3639954.26     10150895.87      3639692.11     10151141.64
#Sta/Elev= 30
  3677.3   212.5  3684.6  211.66    3720  210.94  3734.5  209.84  3819.9  207.09
  3884.4  204.16  3919.8  203.51  3948.9  202.13  4069.6  199.69  4148.7  197.07
  4348.4  196.25  4433.8  197.08  4448.3  195.38  4483.7  196.95  4504.7  196.12
  4591.9  195.61  4718.9  196.48  4784.1  194.94  4916.3  194.35  4933.7  192.83
  4936.4  192.33  4939.7  192.83  4979.4  195.15  4997.7  193.98  5018.1  194.79
  5247.2  194.22  5333.5  195.15  5590.6  203.14  5682.9  207.92    5711  208.44
#Mann= 3 ,-1 , 0
  3677.3     .05       0  4933.7     .03       0  4939.7     .05       0
Bank Sta=4933.7,4939.7
XS Rating Curve= 0 ,0
Exp/Cntr=0.3,0.1

Type RM Length L Ch R = 1 ,3794    ,1335,1335,1335
BEGIN DESCRIPTION:
Mapping XS a397ed3a
END DESCRIPTION:
XS GIS Cut Line= 4
      3641223.08     10151524.89      3640246.51      10150407.7
      3640118.91     10150479.31      3639682.63     10151018.16
#Sta/Elev= 30
  3426.4   205.9  3464.9  204.17  3507.6   204.1  3536.1  205.42    3557  202.81
  3599.7  201.01  3698.4     199  3734.5  197.52  3890.1  195.17  4095.2  195.85
    4117  194.92  4152.1  195.84  4215.7  195.95    4294  195.22  4393.2  196.28
  4520.4  194.07  4691.2  193.88  4909.8  190.71  4961.2  191.24  4984.1  190.49
  4986.8  189.49  4989.6  188.99  4992.8  189.49  5011.5  190.74  5027.5  189.94
  5053.9  191.18  5262.5  191.91  5411.2  194.16  5646.2  201.67  5749.9  206.67
#Mann= 3 ,-1 , 0
  3426.4     .05       0  4986.8     .03       0  4992.8     .05       0
Bank Sta=4986.8,4992.8
XS Rating Curve= 0 ,0
Exp/Cntr=0.3,0.1

Type RM Length L Ch R = 1 ,2459    ,0,0,0
BEGIN DESCRIPTION:
UNT101 IN ROCK 1.0
END DESCRIPTION:
XS GIS Cut Line= 3
      3640058.42      10149543.8      3638903.92     10149804.22
      3638522.57     10150818.28
#Sta/Elev= 30
  4246.3   185.9  4273.3  186.06  4301.8  185.32  4528.2  185.21  4560.3  186.67
  4576.5  185.91  4591.1  186.33  4611.6  185.15  4652.6  184.82  5175.4  184.16
  5195.9  184.71  5223.6  183.68  5226.4  183.18  5229.6  183.68  5501.2  184.02
  5677.3  184.99  5918.5   187.7  5939.9  188.96  5993.8  188.39  6018.7  189.41
  6025.3  190.87    6036  191.29  6048.9   190.4  6068.1  191.82  6073.8  192.77
  6089.4  193.28    6184  194.99  6445.4     202  6500.5  203.91  6513.2  204.89
#Mann= 3 ,-1 , 0
  4246.3     .05       0  5223.6     .03       0  5229.6     .05       0
Bank Sta=5223.6,5229.6
XS Rating Curve= 0 ,0
Exp/Cntr=0.3,0.1
Stream Node=UNT101 IN ROCK  ,Reach-1         , 0 , 0 ,Upstream end
Stream Node=UNT101 IN ROCK  ,Reach-1         , 0 , 1 ,Downstream end

Chan Stop Cuts=-1
Use User Specified Reach Order=0
Composite Channel Slope=5