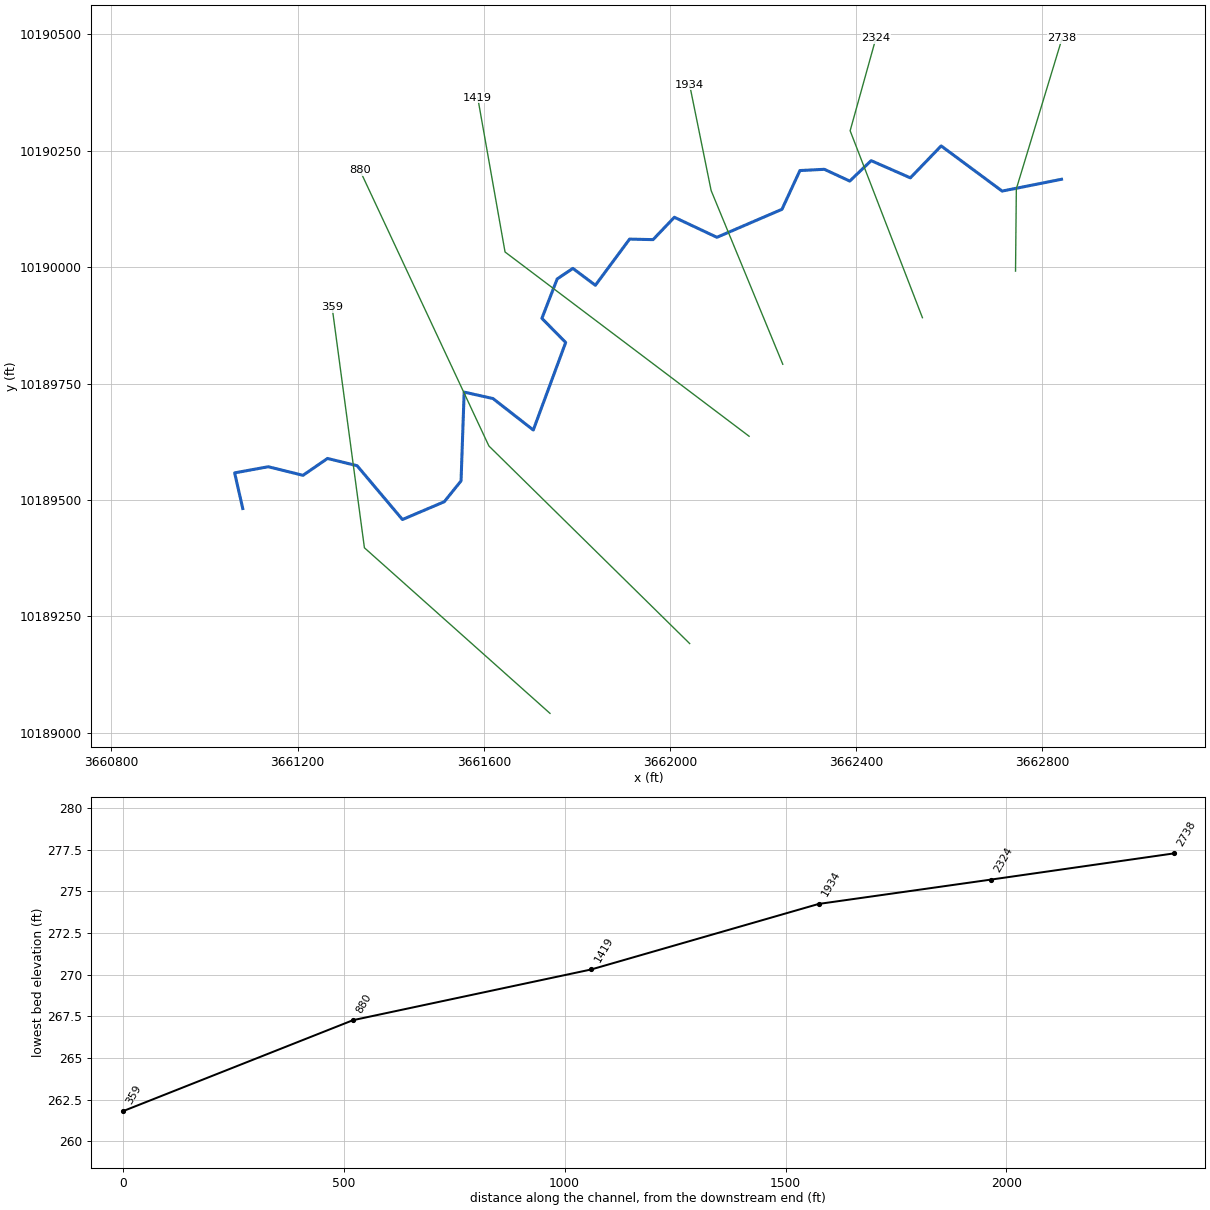
--- UNT102 IN ROCK.prj (project) ---

Proj Title=UNT102 IN ROCK Base Level Engineering
Current Plan=p01
Default Exp/Contr=0.3,0.1
English Units
Geom File=g01
Flow File=f01
Plan File=p01
BEGIN DESCRIPTION:
UNT102 IN ROCK
END DESCRIPTION:

--- UNT102 IN ROCK.p01 (plan) ---

Plan Title=Multiple Run
Short Identifier=Multiple
Geom File=g01
Flow File=f01
Subcritical Flow
K Sum by GR= 0
Std Step Tol= 0.01
Critical Tol= 0.01
Num of Std Step Trials= 20
Max Error Tol= 0.3
Flow Tol Ratio= 0.001
Split Flow NTrial= 30
Split Flow Tol= 0.02
Split Flow Ratio= 0.02
Log Output Level= 0
Friction Slope Method= 1
Unsteady Friction Slope Method= 2
Unsteady Bridges Friction Slope Method= 1
Parabolic Critical Depth
Global Vel Dist=  1 , 1 , 1
Global Log Level= 0
CheckData=True
Encroach Param= -1, 0, 0, 0
BEGIN DESCRIPTION:
Multiple Run
END DESCRIPTION:

--- UNT102 IN ROCK.f01 (steady flow) ---

Flow Title=Multiple
Number of Profiles=7
Profile Names=10-year,25-year,50-year,1pct_min,100-year,1pct_plu,500-year
River Rch & RM= UNT102 IN ROCK,Reach-1,2738
     316     404     473     407     550     744     742
Boundary for River Rch & Prof#=UNT102 IN ROCK,Reach-1,1
Up Type=0
Dn Type=3
Dn Slope=0.005
Boundary for River Rch & Prof#=UNT102 IN ROCK,Reach-1,2
Up Type=0
Dn Type=3
Dn Slope=0.005
Boundary for River Rch & Prof#=UNT102 IN ROCK,Reach-1,3
Up Type=0
Dn Type=3
Dn Slope=0.005
Boundary for River Rch & Prof#=UNT102 IN ROCK,Reach-1,4
Up Type=0
Dn Type=3
Dn Slope=0.005
Boundary for River Rch & Prof#=UNT102 IN ROCK,Reach-1,5
Up Type=0
Dn Type=3
Dn Slope=0.005
Boundary for River Rch & Prof#=UNT102 IN ROCK,Reach-1,6
Up Type=0
Dn Type=3
Dn Slope=0.005
Boundary for River Rch & Prof#=UNT102 IN ROCK,Reach-1,7
Up Type=0
Dn Type=3
Dn Slope=0.005

--- UNT102 IN ROCK.g01 (geometry) ---

Geom Title=Existing Conditions

River Reach=UNT102 IN ROCK,Reach-1
Reach XY= 30
      3662840.91     10190188.95      3662713.28     10190163.58
      3662582.34     10190260.59      3662516.21     10190192.00
      3662431.94     10190228.96      3662385.97     10190185.09
      3662331.40     10190210.34      3662278.93     10190207.66
      3662240.39     10190124.41      3662100.64     10190064.29
      3662009.25     10190107.32      3661963.45     10190059.27
      3661913.05     10190060.40      3661839.57     10189961.22
      3661791.25     10189997.50      3661757.54     10189974.88
      3661724.70     10189890.21      3661775.80     10189838.35
      3661706.20     10189650.33      3661619.63     10189717.90
      3661557.70     10189731.74      3661551.04     10189541.07
      3661515.08     10189496.33      3661425.14     10189458.02
      3661327.74     10189573.61      3661264.20     10189589.25
      3661211.58     10189553.03      3661136.95     10189571.41
      3661064.65     10189558.26      3661082.11     10189481.64

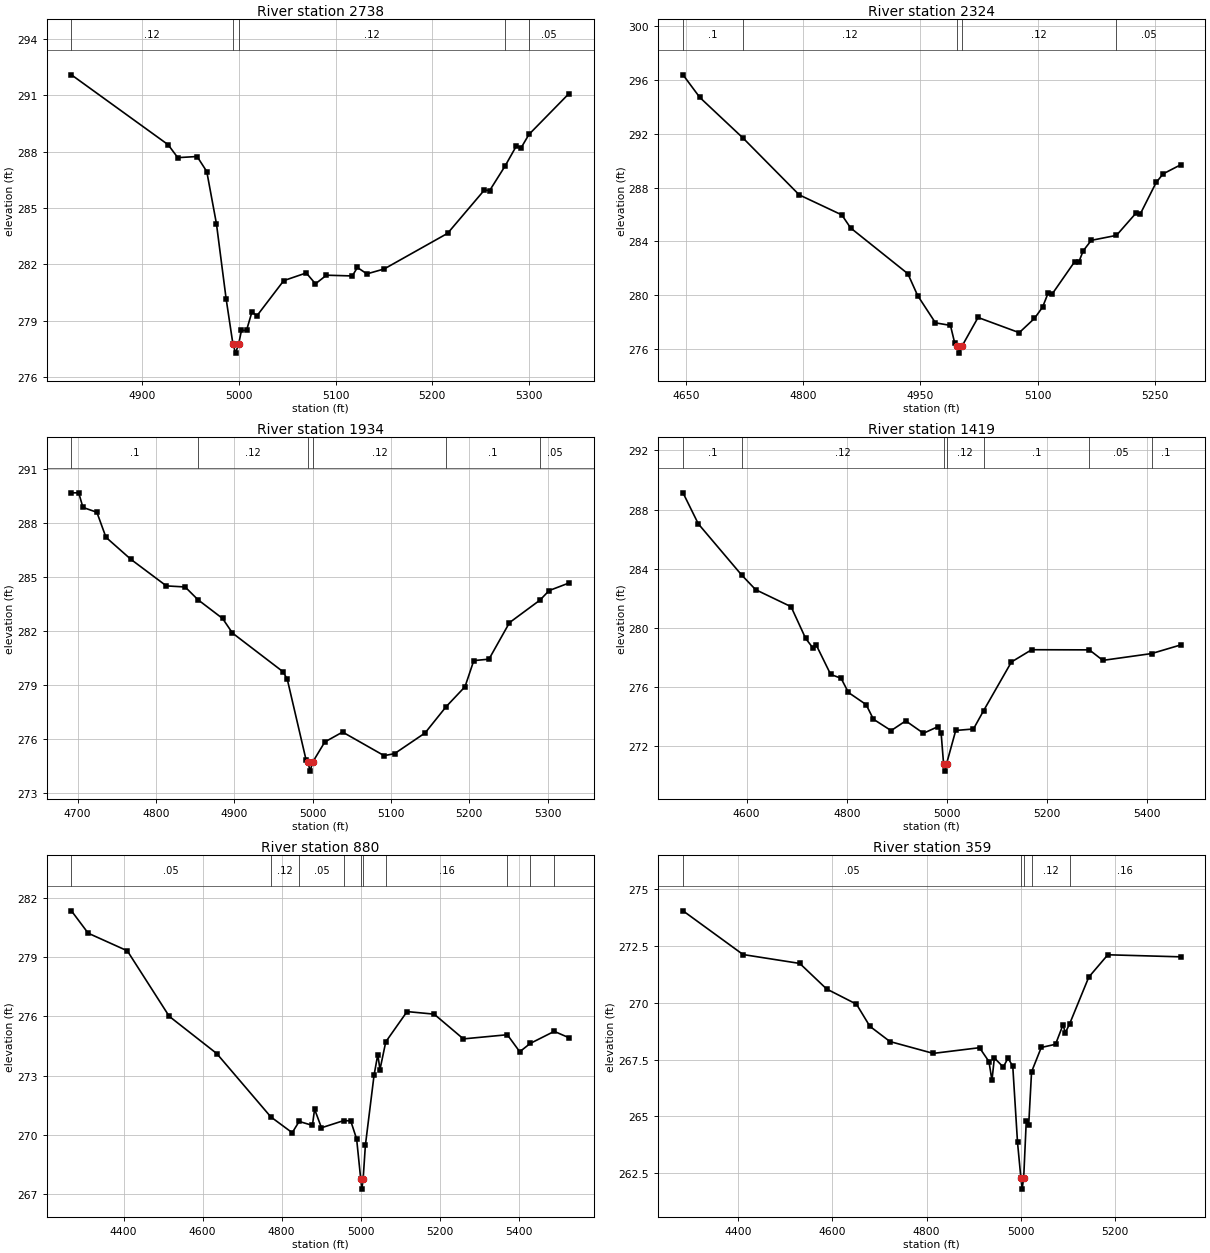
Type RM Length L Ch R = 1,2738,414,414,414
BEGIN DESCRIPTION:
UNT102 IN ROCK 6.0
END DESCRIPTION:
XS GIS Cut Line= 3
      3662742.11     10189991.63      3662743.83     10190168.38
      3662842.10     10190491.61
#Sta/Elev= 30
  4826.7  292.09  4926.7  288.37  4936.7  287.68  4956.7  287.74  4966.7  286.94
  4976.7  284.16  4986.7  280.17  4993.7  277.77  4996.5  277.27  4999.7  277.77
  5002.6  278.48  5007.8  278.48  5013.4  279.46  5018.6  279.26  5046.3  281.13
  5069.6  281.54  5079.1  280.96  5090.5  281.42  5117.2  281.38  5122.5  281.83
  5132.3  281.49  5150.1  281.75  5215.8  283.65  5253.9  285.96  5259.2  285.92
  5275.2  287.23  5286.8  288.29  5292.0  288.22  5300.0  288.92  5341.3  291.09
#Mann=5,-1,0
  4826.7    0.12       0  4993.7    0.07       0  4999.7    0.12       0
  5275.2     0.1       0  5300.0    0.05       0
Bank Sta=4993.7,4999.7
Exp/Cntr=0.3,0.1

Type RM Length L Ch R = 1,2324,390,390,390
BEGIN DESCRIPTION:
UNT102 IN ROCK 5.0
END DESCRIPTION:
XS GIS Cut Line= 3
      3662542.12     10189891.61      3662386.85     10190293.15
      3662442.12     10190491.68
#Sta/Elev= 30
  4646.4  296.38  4667.9  294.70  4723.4  291.67  4795.1  287.46  4849.6  285.97
  4860.9  285.00  4934.1  281.60  4946.6  279.98  4969.4  277.95  4988.6  277.76
  4994.0  276.46  4997.2  276.20  5000.0  275.70  5003.2  276.20  5023.9  278.35
  5076.6  277.22  5096.1  278.28  5106.5  279.12  5113.4  280.14  5118.6  280.08
  5147.6  282.50  5152.8  282.46  5158.4  283.30  5168.8  284.08  5201.0  284.45
  5226.4  286.13  5231.6  286.05  5251.8  288.38  5260.7  289.02  5283.0  289.69
#Mann=5,-1,0
  4646.4     0.1       0  4723.4    0.12       0  4997.2    0.07       0
  5003.2    0.12       0  5201.0    0.05       0
Bank Sta=4997.2,5003.2
Exp/Cntr=0.3,0.1

Type RM Length L Ch R = 1,1934,515,515,515
BEGIN DESCRIPTION:
UNT102 IN ROCK 4.0
END DESCRIPTION:
XS GIS Cut Line= 3
      3662242.12     10189791.60      3662088.24     10190164.68
      3662042.10     10190391.67
#Sta/Elev= 30
  4692.0  289.70  4701.3  289.70  4706.7  288.89  4724.5  288.62  4736.1  287.23
  4767.8  286.01  4813.2  284.53  4837.2  284.47  4853.6  283.76  4885.0  282.72
  4897.6  281.91  4962.2  279.76  4967.6  279.34  4991.6  274.86  4994.0  274.74
  4996.7  274.24  5000.0  274.74  5015.5  275.86  5038.2  276.41  5091.2  275.10
  5104.5  275.21  5143.5  276.36  5170.4  277.82  5194.5  278.93  5205.7  280.38
  5225.1  280.46  5251.3  282.49  5290.2  283.74  5301.9  284.27  5327.2  284.69
#Mann=6,-1,0
  4692.0     0.1       0  4853.6    0.12       0  4994.0    0.07       0
  5000.0    0.12       0  5170.4     0.1       0  5290.2    0.05       0
Bank Sta=4994,5000
Exp/Cntr=0.3,0.1

Type RM Length L Ch R = 1,1419,539,539,539
BEGIN DESCRIPTION:
UNT102 IN ROCK 3.0
END DESCRIPTION:
XS GIS Cut Line= 3
      3662169.81     10189636.93      3661645.53     10190032.74
      3661586.81     10190364.37
#Sta/Elev= 30
  4472.9  289.13  4503.5  287.03  4589.8  283.58  4618.0  282.58  4688.7  281.43
  4717.9  279.28  4732.4  278.64  4738.7  278.86  4767.8  276.85  4788.6  276.59
  4803.2  275.63  4838.6  274.81  4853.2  273.82  4888.6  273.05  4917.7  273.71
  4953.1  272.87  4982.2  273.32  4988.5  272.86  4993.3  270.81  4996.0  270.31
  4999.3  270.81  5017.6  273.06  5053.0  273.16  5073.1  274.39  5128.8  277.69
  5169.3  278.52  5284.4  278.51  5311.5  277.80  5408.8  278.26  5466.6  278.84
#Mann=7,-1,0
  4472.9     0.1       0  4589.8    0.12       0  4993.3    0.07       0
  4999.3    0.12       0  5073.1     0.1       0  5284.4    0.05       0
  5408.8     0.1       0
Bank Sta=4993.3,4999.3
Exp/Cntr=0.3,0.1

Type RM Length L Ch R = 1,880,521,521,521
BEGIN DESCRIPTION:
UNT102 IN ROCK 2.0
END DESCRIPTION:
XS GIS Cut Line= 3
      3662042.12     10189191.63      3661610.81     10189616.07
      3661333.77     10190208.24
#Sta/Elev= 30
  4268.1  281.33  4310.5  280.20  4409.5  279.31  4515.6  276.00  4635.8  274.12
  4772.6  270.92  4826.8  270.12  4844.3  270.69  4877.9  270.49  4883.4  271.31
  4900.8  270.37  4956.9  270.73  4974.8  270.72  4989.8  269.80  5000.2  267.77
  5002.9  267.27  5006.2  267.77  5011.9  269.48  5033.9  273.03  5043.3  274.07
  5048.8  273.31  5063.5  274.71  5117.4  276.24  5185.9  276.11  5259.9  274.86
  5371.1  275.07  5402.5  274.21  5429.0  274.63  5489.7  275.24  5527.0  274.92
#Mann=10,-1,0
  4268.1    0.05       0  4772.6    0.12       0  4844.3    0.05       0
  4956.9    0.12       0  5000.2    0.07       0  5006.2    0.12       0
  5063.5    0.16       0  5371.1     0.1       0  5429.0    0.16       0
  5489.7     0.1       0
Bank Sta=5000.2,5006.2
Exp/Cntr=0.3,0.1

Type RM Length L Ch R = 1,359,0,0,0
BEGIN DESCRIPTION:
UNT102 IN ROCK 1.0
END DESCRIPTION:
XS GIS Cut Line= 3
      3661742.12     10189041.63      3661343.45     10189397.32
      3661274.00     10189914.70
#Sta/Elev= 30
  4282.8  274.03  4410.3  272.11  4530.7  271.72  4587.6  270.60  4651.1  269.93
  4679.5  268.96  4722.2  268.29  4814.1  267.77  4912.3  268.02  4932.4  267.41
  4938.7  266.58  4943.8  267.57  4962.7  267.17  4972.8  267.56  4982.9  267.21
  4993.0  263.86  5000.1  262.31  5002.8  261.81  5006.1  262.31  5011.6  264.82
  5016.7  264.61  5022.8  266.96  5043.4  268.03  5073.7  268.17  5089.5  269.02
  5094.6  268.68  5103.7  269.07  5144.3  271.12  5184.7  272.10  5339.1  272.01
#Mann=5,-1,0
  4282.8    0.05       0  5000.1    0.03       0  5006.1    0.05       0
  5022.8    0.12       0  5103.7    0.16       0
Bank Sta=5000.1,5006.1
Exp/Cntr=0.3,0.1

Chan Stop Cuts=-1