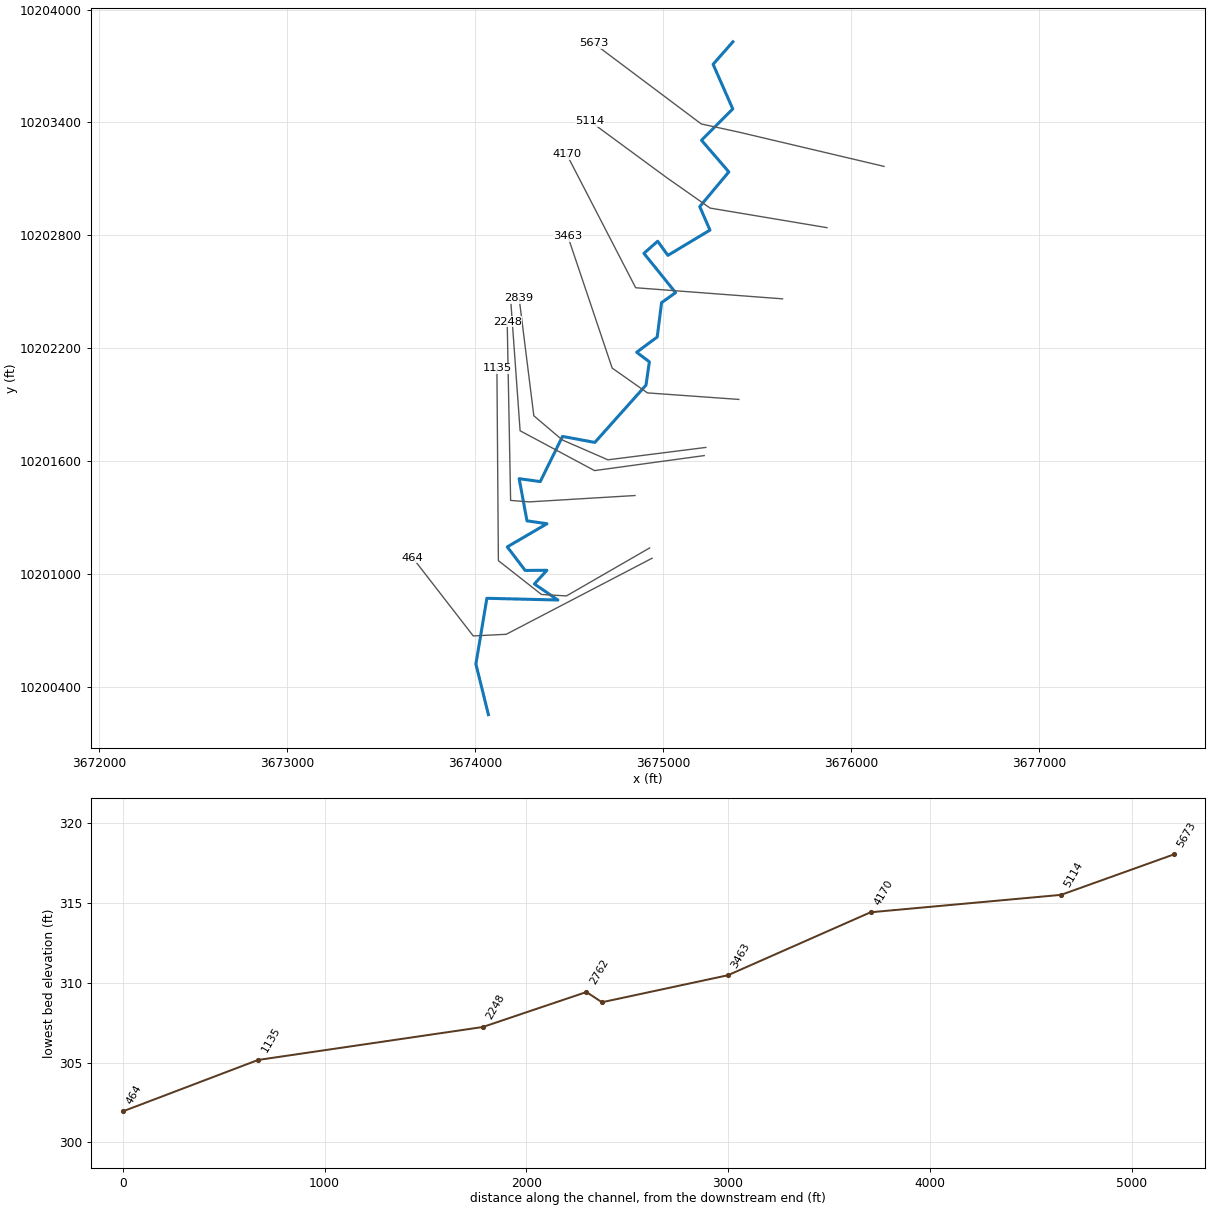
--- UNT103 IN ROCK.prj (project) ---

Proj Title=UNT103 IN ROCK Base Level Engineering
Current Plan=p01
Default Exp/Contr=0.3,0.1
English Units
Geom File=g01
Flow File=f01
Plan File=p01
Y Axis Title=Elevation
X Axis Title(PF)=Main Channel Distance
X Axis Title(XS)=Station
BEGIN DESCRIPTION:
UNT103 IN ROCK
END DESCRIPTION:
DSS Export Rating Curves= 0
DSS Export Rating Curve Sorted= 0
DSS Export Volume Flow Curves= 0
DXF OffsetX= 0
DXF OffsetY= 0
DXF ScaleX= 1
DXF ScaleY= 10

--- UNT103 IN ROCK.p01 (plan) ---

Plan Title=Multiple Run
Short Identifier=Multiple
Geom File=g01
Flow File=f01
Subcritical Flow
K Sum by GR= 0
Std Step Tol= 0.01
Critical Tol= 0.01
Num of Std Step Trials= 20
Max Error Tol= 0.3
Flow Tol Ratio= 0.001
Split Flow NTrial= 30
Split Flow Tol= 0.02
Split Flow Ratio= 0.02
Log Output Level= 0
Friction Slope Method= 1
Unsteady Friction Slope Method= 2
Unsteady Bridges Friction Slope Method= 1
Parabolic Critical Depth
Global Vel Dist=  1 , 1 , 1
Global Log Level= 0
CheckData=True
Encroach Param= -1, 0, 0, 0
BEGIN DESCRIPTION:
Multiple Run
END DESCRIPTION:

--- UNT103 IN ROCK.f01 (steady flow) ---

Flow Title=Multiple
Program Version=4.10
Number of Profiles= 7
Profile Names=10-year,25-year,50-year,1pct_min,100-year,1pct_plu,500-year
River Rch & RM=UNT103 IN ROCK,Reach-1         ,5673
    1066    1462    1791    1604    2169    2933    3181
Boundary for River Rch & Prof#=UNT103 IN ROCK,Reach-1         , 1
Up Type= 0
Dn Type= 3
Dn Slope=0.005
Boundary for River Rch & Prof#=UNT103 IN ROCK,Reach-1         , 2
Up Type= 0
Dn Type= 3
Dn Slope=0.005
Boundary for River Rch & Prof#=UNT103 IN ROCK,Reach-1         , 3
Up Type= 0
Dn Type= 3
Dn Slope=0.005
Boundary for River Rch & Prof#=UNT103 IN ROCK,Reach-1         , 4
Up Type= 0
Dn Type= 3
Dn Slope=0.005
Boundary for River Rch & Prof#=UNT103 IN ROCK,Reach-1         , 5
Up Type= 0
Dn Type= 3
Dn Slope=0.005
Boundary for River Rch & Prof#=UNT103 IN ROCK,Reach-1         , 6
Up Type= 0
Dn Type= 3
Dn Slope=0.005
Boundary for River Rch & Prof#=UNT103 IN ROCK,Reach-1         , 7
Up Type= 0
Dn Type= 3
Dn Slope=0.005
DSS Import GetInterval= 0
DSS Import GetPeak= 0
DSS Import FillOption= 0

--- UNT103 IN ROCK.g01 (geometry) ---

Geom Title=Existing Conditions
Program Version=4.10

River Reach=UNT103 IN ROCK  ,Reach-1
Reach XY= 30
       3675371.5     10203828.68      3675266.24      10203709.1
      3675370.71     10203471.86      3675204.48      10203305.2
      3675349.88     10203137.01      3675195.15     10202952.33
       3675249.4     10202827.55      3675025.88     10202693.22
      3674971.41     10202768.31      3674898.06     10202704.07
      3675066.68     10202495.09      3674992.11     10202441.64
       3674968.8     10202258.97      3674859.65     10202178.03
      3674927.14     10202127.25      3674909.34     10202003.33
      3674637.21     10201698.64      3674465.33     10201730.55
      3674346.84     10201490.31      3674234.65     10201505.94
      3674276.31     10201281.54      3674382.65     10201266.35
       3674171.5     10201143.09      3674266.73     10201017.98
      3674382.22     10201018.74      3674315.81     10200946.04
      3674440.59     10200860.75      3674063.03     10200869.82
      3674004.42     10200520.35      3674071.21     10200251.05

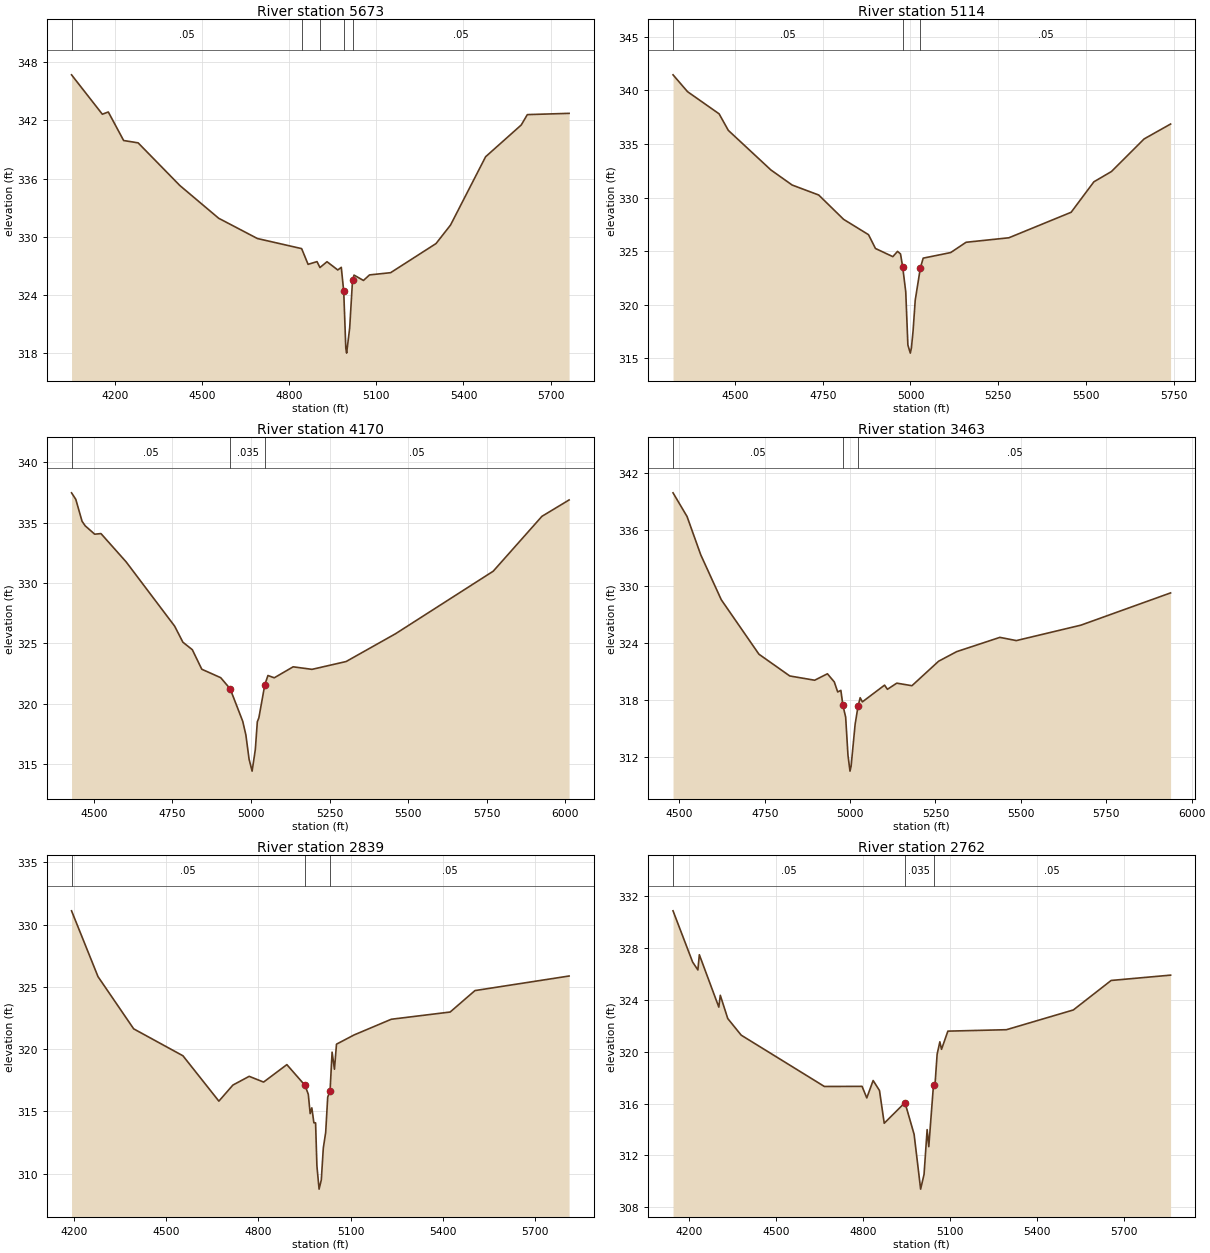
Type RM Length L Ch R = 1 ,5673    ,559,559,559
BEGIN DESCRIPTION:
UNT103 IN ROCK 9.0
END DESCRIPTION:
XS GIS Cut Line= 4
      3676175.42     10203166.26       3675402.8     10203348.56
      3675203.14     10203391.97      3674630.22     10203821.66
#Sta/Elev= 30
  4049.6   346.7  4155.7  342.64  4176.3  342.87  4229.1  339.93    4279  339.69
  4422.9  335.29  4556.5  331.92    4690  329.83  4842.4  328.79  4864.6  327.17
  4895.3  327.45  4905.5  326.84  4929.8  327.44  4966.9  326.59    4979  326.86
  4987.4  324.39  4994.6  318.52  4997.4  318.02  5007.9  320.61  5017.8  325.56
    5023  326.06  5055.4  325.51  5076.3  326.08    5149  326.31  5305.4  329.31
  5355.4  331.22  5476.3  338.26    5599  341.53    5620   342.6  5763.9  342.73
#Mann= 5 ,-1 , 0
  4049.6     .05       0  4842.4     .12       0  4905.5     .05       0
  4987.4    .035       0  5017.8     .05       0
Bank Sta=4987.4,5017.8
XS Rating Curve= 0 ,0
Exp/Cntr=0.3,0.1

Type RM Length L Ch R = 1 ,5114    ,944,944,944
BEGIN DESCRIPTION:
UNT103 IN ROCK 8.0
END DESCRIPTION:
XS GIS Cut Line= 4
      3675871.71     10202840.46      3675250.16     10202944.63
      3675017.53     10203107.82      3674611.25     10203406.45
#Sta/Elev= 30
  4323.1  341.45  4364.4  339.88  4454.5  337.81  4480.7  336.27    4602  332.58
  4662.7  331.17  4738.4  330.24  4809.4  327.97  4880.4  326.54  4900.3  325.25
  4949.8  324.49  4963.2  324.98  4971.7  324.74  4977.9  323.52  4986.6  321.21
  4992.7  316.25  4999.6  315.49  5002.8  315.99  5007.5  317.57  5013.6  320.42
  5028.4  323.46  5036.4  324.35  5114.7  324.87  5158.6  325.83  5280.7  326.25
  5458.2  328.63    5523  331.47  5573.1  332.43  5666.2  335.47  5741.7  336.86
#Mann= 3 , 0 , 0
  4323.1     .05       0  4977.9    .035       0  5028.4     .05       0
Bank Sta=4977.9,5028.4
XS Rating Curve= 0 ,0
Exp/Cntr=0.3,0.1

Type RM Length L Ch R = 1 ,4170    ,707,707,707
BEGIN DESCRIPTION:
UNT103 IN ROCK 7.0
END DESCRIPTION:
XS GIS Cut Line= 3
      3675635.55     10202461.99      3674854.33     10202521.02
      3674486.68     10203232.04
#Sta/Elev= 30
  4428.7  337.48  4442.2  336.94  4462.2  335.12  4472.3  334.74  4502.4  334.05
  4522.4   334.1  4602.6  331.75    4757  326.42  4783.2  325.09  4813.2  324.47
  4843.3  322.85  4903.5  322.15  4933.6  321.23  4973.7  318.53  4983.7   317.4
  4993.8   315.4  5003.5   314.4  5013.8   316.2  5020.1  318.49  5025.1  318.83
  5043.9  321.56  5053.9  322.33    5074  322.14  5134.2  323.05  5194.3  322.84
  5302.9  323.49  5460.5   325.8  5771.1  330.98  5926.1  335.53  6012.6  336.89
#Mann= 3 , 0 , 0
  4428.7     .05       0  4933.6    .035       0  5043.9     .05       0
Bank Sta=4933.6,5043.9
XS Rating Curve= 0 ,0
Exp/Cntr=0.3,0.1

Type RM Length L Ch R = 1 ,3463    ,624,624,624
BEGIN DESCRIPTION:
UNT103 IN ROCK 6.0
END DESCRIPTION:
XS GIS Cut Line= 4
      3675402.99     10201927.26      3674916.83     10201961.99
      3674729.33     10202093.93      3674493.23     10202795.29
#Sta/Elev= 30
  4481.6  339.88  4522.6  337.38  4562.7  333.33  4622.8  328.58  4733.1  322.82
  4823.4  320.52  4896.2  320.07  4933.6  320.75  4953.7  319.89  4963.7  318.83
    4973     319    4979   317.4    4987  316.17  4993.8  312.13  4999.7  310.46
  5002.9  310.96  5014.7  315.41  5023.4  317.34  5029.5  318.22  5035.9  317.78
  5100.9  319.55  5109.3  319.11  5136.7  319.76  5181.1  319.49  5259.2  322.08
  5311.9  323.09  5438.5   324.6  5486.7  324.26  5675.7  325.89  5938.3   329.3
#Mann= 3 , 0 , 0
  4481.6     .05       0    4979    .035       0  5023.4     .05       0
Bank Sta=4979,5023.4
XS Rating Curve= 0 ,0
Exp/Cntr=0.3,0.1

Type RM Length L Ch R = 1 ,2839    ,77,77,77
BEGIN DESCRIPTION:
UNT103 IN ROCK 5.0
END DESCRIPTION:
XS GIS Cut Line= 5
      3675227.55     10201672.05      3674706.76     10201606.09
      3674463.71     10201711.99      3674312.66     10201840.46
      3674234.54     10202465.43
#Sta/Elev= 30
  4192.7   331.1  4278.8  325.82  4394.8  321.63    4555  319.47  4671.9  315.83
  4717.5  317.12  4770.5  317.82  4817.3  317.36    4893  318.76  4951.8   317.1
  4962.7  316.38  4968.8  314.83  4974.2  315.29  4980.9  314.09  4986.4  314.09
  4990.7  310.64  4997.8  308.77    5005  309.51  5011.5  312.06  5019.3  313.33
  5025.8  316.15  5033.5  316.66  5040.1  319.76  5047.8  318.39  5054.4   320.4
  5111.5  321.14  5232.6   322.4  5424.1  322.98  5504.7   324.7  5810.9  325.87
#Mann= 3 , 0 , 0
  4192.7     .05       0  4951.8    .035       0  5033.5     .05       0
Bank Sta=4951.8,5033.5
XS Rating Curve= 0 ,0
Exp/Cntr=0.3,0.1

Type RM Length L Ch R = 1 ,2762    ,514,514,514
BEGIN DESCRIPTION:
UNT103 IN ROCK 4.0
END DESCRIPTION:
XS GIS Cut Line= 4
      3675218.96     10201628.66      3674635.58     10201548.79
      3674239.75      10201760.6      3674191.13     10202435.99
#Sta/Elev= 30
  4145.1  330.83  4212.6  326.89  4230.7  326.28  4235.8  327.45  4302.9  323.42
    4308  324.33  4333.7  322.54  4380.1  321.26  4666.8  317.31  4796.6  317.32
  4812.9  316.43  4834.8  317.77  4856.7     317    4873  314.48  4944.5  316.07
    4976  313.63  4998.5  309.41  5010.3  310.55  5020.9  313.99  5026.6  312.68
  5042.9  317.46  5048.5  317.61  5055.4   319.8  5064.8  320.75  5070.5  320.17
  5092.4  321.57  5294.2  321.68  5524.8   323.2  5655.1  325.47    5860  325.88
#Mann= 3 , 0 , 0
  4145.1     .05       0  4944.5    .035       0  5042.9     .05       0
Bank Sta=4944.5,5042.9
XS Rating Curve= 0 ,0
Exp/Cntr=0.3,0.1

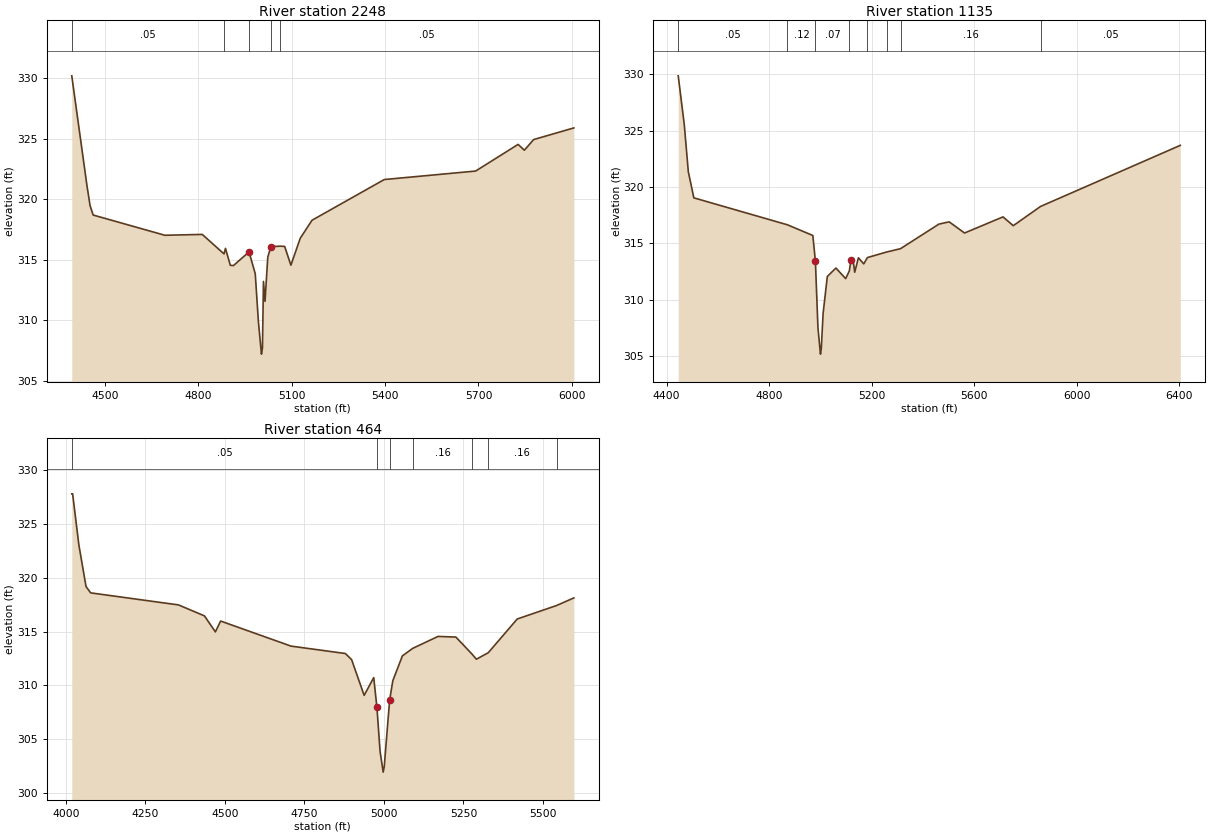
Type RM Length L Ch R = 1 ,2248    ,1113,1113,1113
BEGIN DESCRIPTION:
UNT103 IN ROCK 3.0
END DESCRIPTION:
XS GIS Cut Line= 4
      3674850.75     10201416.27      3674288.21     10201382.42
      3674189.26     10201390.23      3674171.03     10202340.73
#Sta/Elev= 30
    4393  330.19  4441.7  321.15  4451.8  319.48  4461.8   318.7  4692.2  317.03
  4812.4   317.1  4882.4  315.49  4886.9  315.95  4902.6  314.55  4912.6  314.53
  4962.7  315.66  4982.7  313.85  4992.8   309.9  5002.6  307.22  5005.8  307.72
    5009  313.22    5014  311.57  5022.9  315.22  5032.9  316.09  5062.8  316.13
  5077.2  316.11  5097.2  314.56  5127.2  316.78  5165.1  318.27  5397.3  321.63
  5690.9  322.33  5827.4  324.53  5847.4  324.05  5877.4  324.93  6006.5  325.89
#Mann= 5 ,-1 , 0
    4393     .05       0  4882.4     .12       0  4962.7     .07       0
  5032.9     .12       0  5062.8     .05       0
Bank Sta=4962.7,5032.9
XS Rating Curve= 0 ,0
Exp/Cntr=0.3,0.1

Type RM Length L Ch R = 1 ,1135    ,671,671,671
BEGIN DESCRIPTION:
UNT103 IN ROCK 2.0
END DESCRIPTION:
XS GIS Cut Line= 5
      3674928.86     10201137.64      3674486.13     10200882.42
      3674353.32     10200890.23      3674124.15     10201069.92
      3674116.34     10202093.31
#Sta/Elev= 30
  4445.7  329.86  4469.3  325.53    4485  321.35  4506.6  319.03  4871.5  316.64
  4970.8  315.69  4980.8  313.42  4990.8  307.48  5000.6  305.16  5003.8  305.66
  5010.8  308.75  5027.3  312.05  5060.9   312.8  5098.9  311.86  5113.4  312.56
  5119.7  313.53  5127.8  313.52  5134.2  312.43  5148.6  313.71  5169.4  313.17
  5183.7  313.73  5258.4  314.22    5313  314.52  5462.7   316.7  5502.7   316.9
  5562.7  315.91  5712.7  317.34  5752.7  316.56  5859.4  318.27  6404.4  323.69
#Mann= 8 ,-1 , 0
  4445.7     .05       0  4871.5     .12       0  4980.8     .07       0
  5113.4     .12       0  5183.7     .16       0  5258.4     .12       0
    5313     .16       0  5859.4     .05       0
Bank Sta=4980.8,5119.7
XS Rating Curve= 0 ,0
Exp/Cntr=0.3,0.1

Type RM Length L Ch R = 1 ,464     ,0,0,0
BEGIN DESCRIPTION:
UNT103 IN ROCK 1.0
END DESCRIPTION:
XS GIS Cut Line= 4
      3674941.87     10201082.95      3674165.82     10200678.42
      3673990.47     10200669.74      3673667.54     10201086.43
#Sta/Elev= 30
  4018.9  327.82  4021.6  327.82  4041.2  323.07  4063.7   319.2  4078.2  318.61
  4354.2  317.49  4435.9  316.47  4470.3  314.98  4486.7  315.99  4707.7  313.66
  4878.8  312.97  4898.4   312.4  4937.8  309.08  4967.9  310.73  4977.9  307.96
  4987.9  303.86  4997.6  301.94  5000.9  302.44  5017.9  308.65  5027.9  310.44
    5058  312.75  5090.5  313.45    5170  314.56  5226.1   314.5    5277  312.91
  5290.4  312.44  5327.7  313.04  5418.9  316.18  5542.3  317.43  5596.8  318.14
#Mann= 7 ,-1 , 0
  4018.9     .05       0  4977.9    .035       0  5017.9     .05       0
  5090.5     .16       0    5277     .12       0  5327.7     .16       0
  5542.3     .05       0
Bank Sta=4977.9,5017.9
XS Rating Curve= 0 ,0
Exp/Cntr=0.3,0.1

Chan Stop Cuts=-1
Use User Specified Reach Order=0
Composite Channel Slope=5