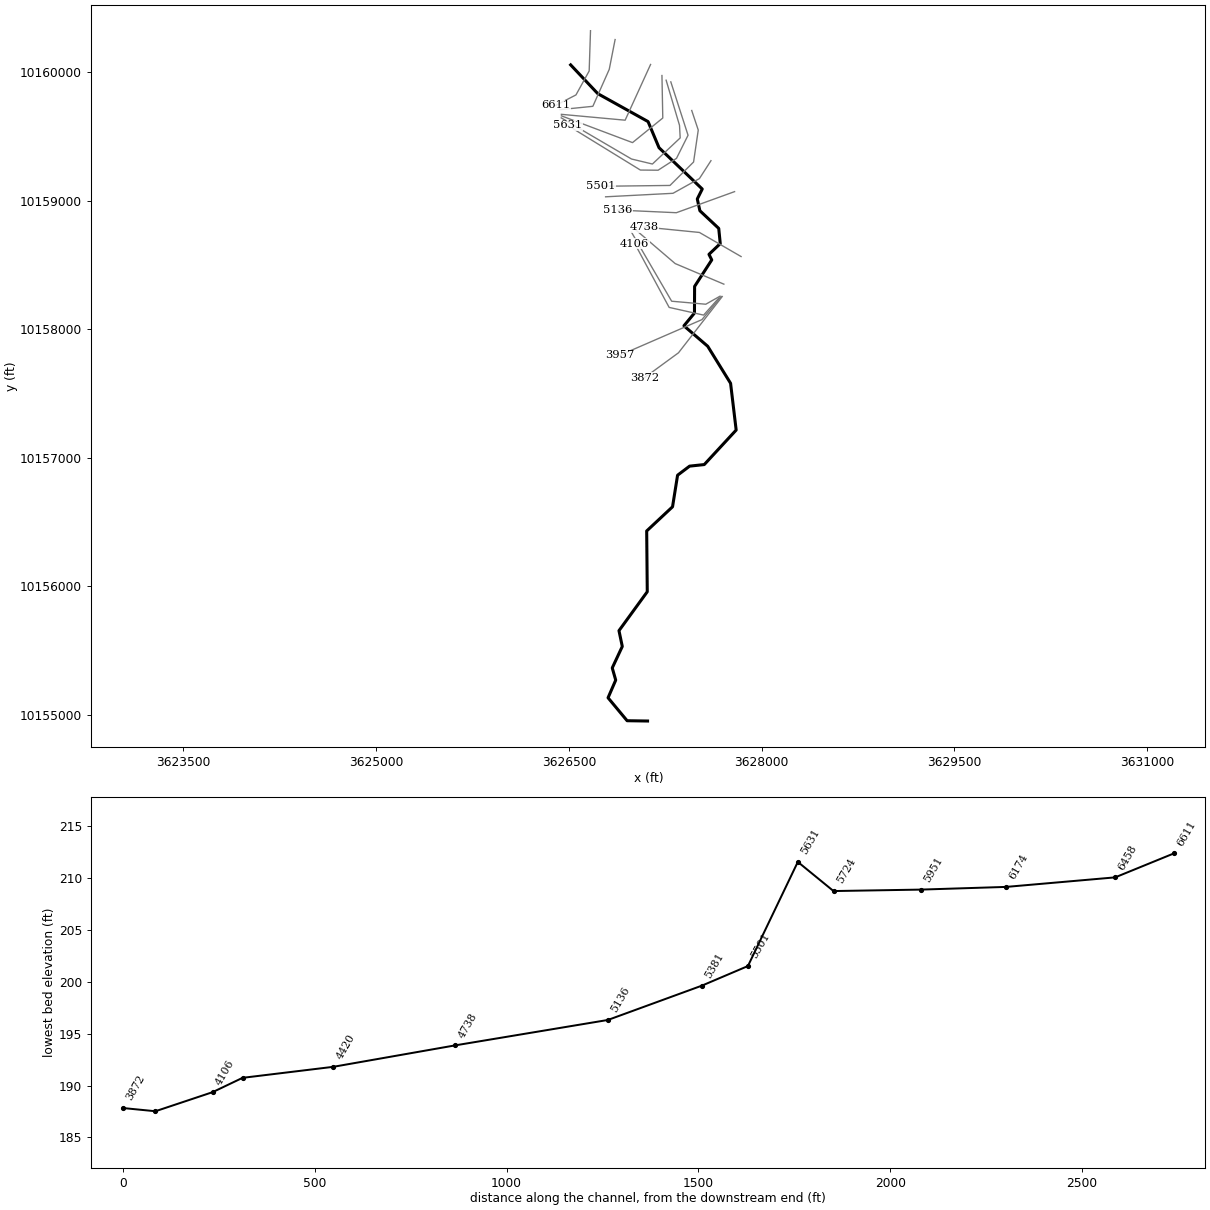
--- UNT104 IN ROCK.prj (project) ---

Proj Title=UNT104 IN ROCK Base Level Engineering
Current Plan=p01
Default Exp/Contr=0.3,0.1
English Units
Geom File=g01
Flow File=f01
Plan File=p01
Y Axis Title=Elevation
X Axis Title(PF)=Main Channel Distance
X Axis Title(XS)=Station
BEGIN DESCRIPTION:
UNT104 IN ROCK
END DESCRIPTION:
DSS Export Rating Curves= 0
DSS Export Rating Curve Sorted= 0
DSS Export Volume Flow Curves= 0
DXF OffsetX= 0
DXF OffsetY= 0
DXF ScaleX= 1
DXF ScaleY= 10

--- UNT104 IN ROCK.p01 (plan) ---

Plan Title=Multiple Run
Short Identifier=Multiple
Geom File=g01
Flow File=f01
Subcritical Flow
K Sum by GR= 0
Std Step Tol= 0.01
Critical Tol= 0.01
Num of Std Step Trials= 20
Max Error Tol= 0.3
Flow Tol Ratio= 0.001
Split Flow NTrial= 30
Split Flow Tol= 0.02
Split Flow Ratio= 0.02
Log Output Level= 0
Friction Slope Method= 1
Unsteady Friction Slope Method= 2
Unsteady Bridges Friction Slope Method= 1
Parabolic Critical Depth
Global Vel Dist=  1 , 1 , 1
Global Log Level= 0
CheckData=True
Encroach Param= -1, 0, 0, 0
BEGIN DESCRIPTION:
Multiple Run
END DESCRIPTION:

--- UNT104 IN ROCK.f01 (steady flow) ---

Flow Title=Multiple
Program Version=4.10
Number of Profiles= 7
Profile Names=10-year,25-year,50-year,1pct_min,100-year,1pct_plu,500-year
River Rch & RM=UNT104 IN ROCK,Reach-1         ,6611
     227     285     328     279     377     510     495
Boundary for River Rch & Prof#=UNT104 IN ROCK,Reach-1         , 1
Up Type= 0
Dn Type= 3
Dn Slope=0.01051
Boundary for River Rch & Prof#=UNT104 IN ROCK,Reach-1         , 2
Up Type= 0
Dn Type= 3
Dn Slope=0.01051
Boundary for River Rch & Prof#=UNT104 IN ROCK,Reach-1         , 3
Up Type= 0
Dn Type= 3
Dn Slope=0.01051
Boundary for River Rch & Prof#=UNT104 IN ROCK,Reach-1         , 4
Up Type= 0
Dn Type= 3
Dn Slope=0.01051
Boundary for River Rch & Prof#=UNT104 IN ROCK,Reach-1         , 5
Up Type= 0
Dn Type= 3
Dn Slope=0.01051
Boundary for River Rch & Prof#=UNT104 IN ROCK,Reach-1         , 6
Up Type= 0
Dn Type= 3
Dn Slope=0.01051
Boundary for River Rch & Prof#=UNT104 IN ROCK,Reach-1         , 7
Up Type= 0
Dn Type= 3
Dn Slope=0.01051
DSS Import GetInterval= 0
DSS Import GetPeak= 0
DSS Import FillOption= 0

--- UNT104 IN ROCK.g01 (geometry) ---

Geom Title=Existing Conditions
Program Version=4.10

River Reach=UNT104 IN ROCK  ,Reach-1
Reach XY= 30
      3626513.59     10160058.19      3626724.95     10159834.13
        3627116.      10159616.8      3627201.42      10159413.4
      3627537.76     10159091.91      3627499.08     10159014.56
      3627519.34     10158923.09      3627666.06     10158785.58
      3627677.87     10158667.13      3627589.98     10158583.58
      3627611.68     10158540.18      3627478.22     10158334.01
      3627477.14     10158126.76      3627395.12     10158027.43
      3627580.25     10157868.25      3627758.23     10157580.04
       3627801.7     10157216.11      3627553.43     10156947.53
      3627439.26     10156935.31      3627345.71     10156864.73
      3627306.53       10156619.      3627105.31     10156430.74
      3627109.81     10155957.67      3626889.63     10155654.82
      3626915.43     10155531.94      3626837.31     10155364.88
      3626864.29     10155270.03       3626804.6     10155132.46
      3626953.04     10154953.93      3627112.11     10154951.64

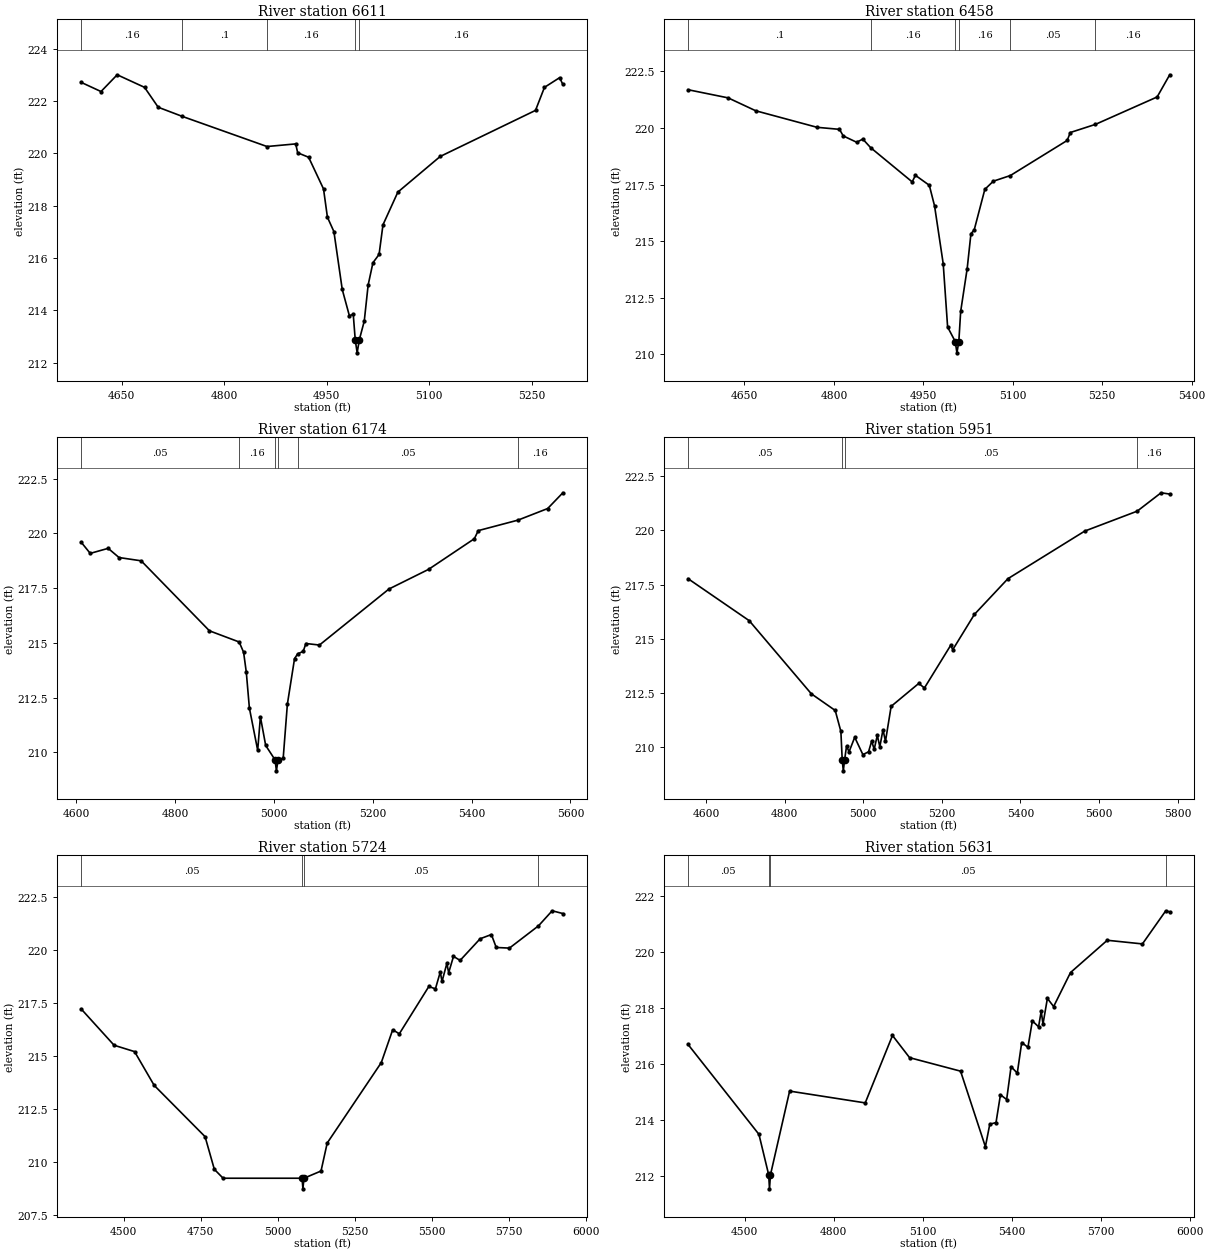
Type RM Length L Ch R = 1 ,6611    ,153,153,153
BEGIN DESCRIPTION:
UNT104 IN ROCK 19.0
END DESCRIPTION:
XS GIS Cut Line= 4
      3626668.11     10160324.28       3626657.7     10160010.52
      3626554.83     10159824.32      3626396.55     10159742.58
#Sta/Elev= 30
  4590.8  222.71  4619.8  222.36  4643.5     223  4683.5  222.52  4703.5  221.76
  4738.8  221.41  4862.7  220.26  4904.7  220.36  4907.6  220.02  4923.6  219.85
  4945.4  218.64  4951.1  217.56  4960.6  217.01  4972.8   214.8  4983.2   213.8
  4988.9  213.85  4991.8  212.88  4994.6  212.38  4997.8  212.88    5005  213.59
  5010.7  214.97  5017.7  215.82  5026.7  216.14  5032.4  217.27  5054.2  218.52
  5116.1  219.88  5255.6  221.64  5268.7  222.52  5290.9  222.89  5295.6  222.63
#Mann= 5 ,-1 , 0
  4590.8     .16       0  4738.8      .1       0  4862.7     .16       0
  4991.8     .07       0  4997.8     .16       0
Bank Sta=4991.8,4997.8
XS Rating Curve= 0 ,0
Exp/Cntr=0.3,0.1

Type RM Length L Ch R = 1 ,6458    ,284,284,284
BEGIN DESCRIPTION:
Mapping XS d6a766be
END DESCRIPTION:
XS GIS Cut Line= 4
      3626859.53     10160255.34      3626813.95     10160023.54
      3626686.34     10159735.78      3626431.09     10159709.73
#Sta/Elev= 30
  4555.5  221.69  4622.7  221.33    4669  220.76  4771.8  220.03  4809.4  219.94
  4815.7  219.65  4838.2  219.37  4848.5  219.51  4861.7  219.13  4931.3  217.62
  4936.7  217.91    4960  217.47  4968.8  216.56  4983.3  214.01  4990.7  211.21
  5003.5  210.57  5006.3  210.07  5009.5  210.57  5012.6   211.9  5023.5  213.79
  5029.8  215.33  5035.3   215.5  5053.1  217.29  5067.3  217.65  5095.9   217.9
  5191.2  219.45  5196.4   219.8  5238.6  220.16    5342  221.37  5363.1  222.35
#Mann= 6 ,-1 , 0
  4555.5      .1       0  4861.7     .16       0  5003.5     .07       0
  5009.5     .16       0  5095.9     .05       0  5238.6     .16       0
Bank Sta=5003.5,5009.5
XS Rating Curve= 0 ,0
Exp/Cntr=0.3,0.1

Type RM Length L Ch R = 1 ,6174    ,223,223,223
BEGIN DESCRIPTION:
Mapping XS 9cca0119
END DESCRIPTION:
XS GIS Cut Line= 3
      3627135.57     10160061.31      3626937.65      10159627.7
      3626441.57     10159673.28
#Sta/Elev= 30
  4609.9   219.6  4628.2  219.09  4664.5  219.32  4686.5   218.9  4731.3  218.75
  4869.5  215.55  4929.6  215.04  4938.6  214.57  4944.1  213.65  4950.3  212.02
  4967.1  210.09  4972.6  211.62  4983.3  210.31  5002.3  209.65    5005  209.15
  5008.3  209.65  5018.7  209.72  5027.2   212.2  5041.7  214.28  5048.1   214.5
  5059.2  214.61  5064.7  214.97  5092.1   214.9  5232.7  217.46    5313  218.36
  5405.6  219.76  5413.5  220.13  5493.9  220.61    5554  221.14  5584.7  221.86
#Mann= 6 ,-1 , 0
  4609.9     .05       0  4929.6     .16       0  5002.3     .07       0
  5008.3     .16       0  5048.1     .05       0  5493.9     .16       0
Bank Sta=5002.3,5008.3
XS Rating Curve= 0 ,0
Exp/Cntr=0.3,0.1

Type RM Length L Ch R = 1 ,5951    ,227,227,227
BEGIN DESCRIPTION:
Mapping XS ead9a1c7
END DESCRIPTION:
XS GIS Cut Line= 4
       3627224.1     10159975.32      3627230.61     10159644.63
      3626994.94     10159453.23      3626441.52     10159661.57
#Sta/Elev= 30
  4554.1  217.77  4709.7  215.83  4867.8  212.45  4928.6  211.68    4943  210.71
  4946.4  209.39  4949.2  208.89  4952.4  209.39  4957.4  210.03  4963.8  209.77
  4978.2  210.44    4999  209.64  5013.4  209.77  5021.3  210.26  5027.8  209.89
  5035.7  210.53  5042.1     210  5050.1  210.79  5056.5  210.26  5070.9  211.87
  5141.2  212.93  5155.6  212.72  5222.4  214.69  5227.7  214.49  5282.8  216.12
  5368.1  217.77  5563.6  219.97    5697  220.89  5757.8  221.74  5779.8  221.68
#Mann= 4 ,-1 , 0
  4554.1     .05       0  4946.4     .03       0  4952.4     .05       0
    5697     .16       0
Bank Sta=4946.4,4952.4
XS Rating Curve= 0 ,0
Exp/Cntr=0.3,0.1

Type RM Length L Ch R = 1 ,5724    ,93,93,93
BEGIN DESCRIPTION:
Mapping XS 39ba38f0
END DESCRIPTION:
XS GIS Cut Line= 6
      3627256.65     10159938.92      3627360.82     10159587.34
      3627366.03     10159489.68      3627149.89     10159286.56
      3626987.12     10159325.62      3626440.22     10159645.95
#Sta/Elev= 30
  4361.6  217.23  4468.5  215.52    4535  215.22  4598.6  213.63    4764  211.21
  4794.1  209.67  4822.6  209.25  5079.1  209.25  5081.8  208.75  5085.1  209.25
  5140.6  209.59  5160.7  210.91  5336.3   214.7  5373.4  216.25  5394.9  216.06
  5490.8  218.29  5512.2  218.18  5527.9  218.97  5533.7  218.53  5549.4  219.38
  5555.2  218.94  5570.9  219.71  5592.4  219.52  5657.4  220.54    5694  220.74
  5709.7  220.13  5752.6   220.1    5847  221.15  5891.4  221.86  5926.1  221.73
#Mann= 4 ,-1 , 0
  4361.6     .05       0  5079.1     .03       0  5085.1     .05       0
    5847     .16       0
Bank Sta=5079.1,5085.1
XS Rating Curve= 0 ,0
Exp/Cntr=0.3,0.1

Type RM Length L Ch R = 1 ,5631    ,130,130,130
BEGIN DESCRIPTION:
Mapping XS ea0d2a2b
END DESCRIPTION:
XS GIS Cut Line= 6
      3627293.12     10159925.86      3627427.23     10159510.52
      3627337.39     10159330.83      3627194.16     10159238.38
      3627056.14     10159239.68      3626488.43     10159588.64
#Sta/Elev= 30
  4309.6   216.7  4548.3   213.5  4581.1  212.06  4583.8  211.56  4587.1  212.06
  4651.6  215.04  4906.2  214.62    4998  217.02  5055.6  216.23  5227.2  215.75
  5310.8  213.06  5325.6  213.86  5346.6  213.92  5361.5  214.91  5382.4  214.74
  5397.3  215.91  5418.2  215.68  5433.1  216.77  5454.1   216.6  5468.9  217.54
  5489.9  217.33  5498.7  217.88  5504.8  217.43  5519.6  218.34  5540.6  218.05
  5597.4  219.26  5721.2  220.41  5839.6  220.28  5918.2  221.46  5931.5  221.42
#Mann= 4 ,-1 , 0
  4309.6     .05       0  4581.1     .03       0  4587.1     .05       0
  5918.2     .16       0
Bank Sta=4581.1,4587.1
XS Rating Curve= 0 ,0
Exp/Cntr=0.3,0.1

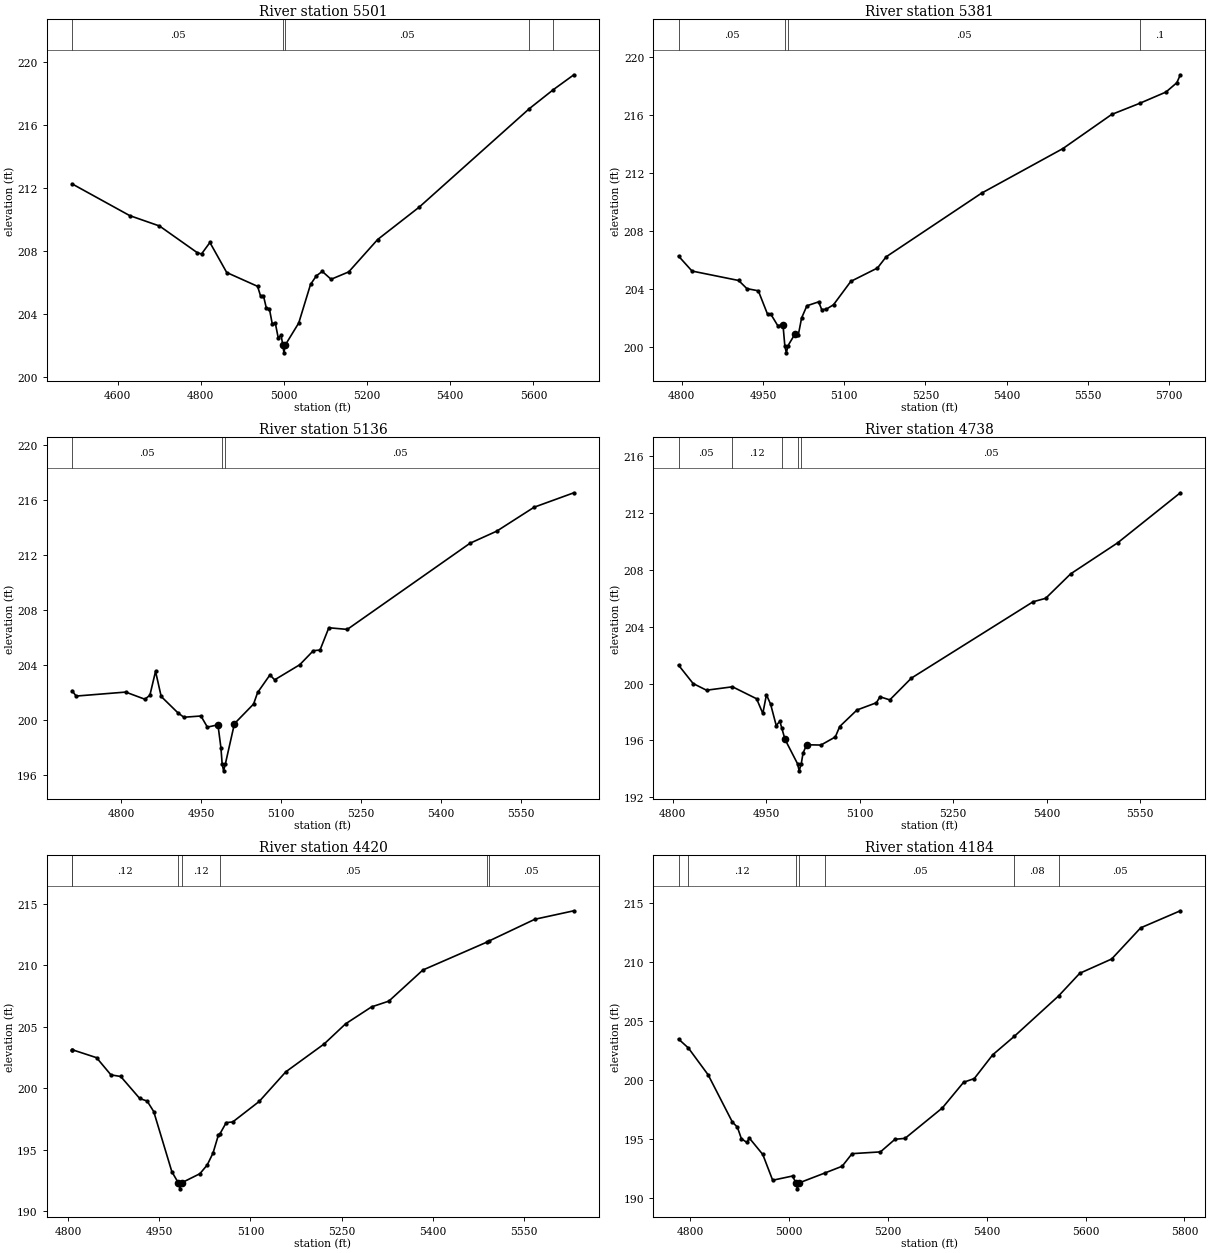
Type RM Length L Ch R = 1 ,5501    ,120,120,120
BEGIN DESCRIPTION:
Mapping XS d5484f20
END DESCRIPTION:
XS GIS Cut Line= 5
      3627455.88      10159703.2      3627506.66     10159550.88
       3627470.2     10159302.18       3627286.6     10159119.89
      3626750.18     10159113.38
#Sta/Elev= 30
  4490.2  212.27  4628.9  210.25  4700.5  209.59  4791.5  207.89  4801.6  207.81
  4821.8  208.54  4862.2  206.63  4936.5  205.75  4943.6  205.14  4950.7  205.14
  4957.7  204.35  4964.8  204.33  4971.8  203.36  4978.9  203.44    4986  202.49
  4993.1  202.63  4997.1  202.02  4999.9  201.52  5003.1  202.02  5035.5  203.42
  5063.8  205.87  5077.9  206.42  5092.1   206.7  5113.3   206.2  5155.7  206.67
  5225.3  208.73  5325.3  210.79  5590.4  217.06  5648.3  218.27  5697.3  219.21
#Mann= 5 ,-1 , 0
  4490.2     .05       0  4997.1     .03       0  5003.1     .05       0
  5590.4      .1       0  5648.3     .16       0
Bank Sta=4997.1,5003.1
XS Rating Curve= 0 ,0
Exp/Cntr=0.3,0.1

Type RM Length L Ch R = 1 ,5381    ,245,245,245
BEGIN DESCRIPTION:
Mapping XS 2b483e39
END DESCRIPTION:
XS GIS Cut Line= 4
      3627605.59     10159312.56      3627515.77     10159173.28
      3627310.04     10159058.69      3626785.57     10159031.43
#Sta/Elev= 30
  4794.2  206.29  4819.1  205.26  4905.2  204.61  4920.4  204.05  4941.5   203.9
  4958.7  202.27  4964.9  202.27  4977.4   201.5    4987  201.57  4990.4  200.13
  4993.2  199.63  4996.4  200.13  5009.4  200.94  5015.2  200.84  5021.4  202.03
  5031.2  202.87  5052.9  203.14  5058.6   202.6  5067.2  202.64  5080.3  202.94
  5112.3  204.55  5161.5  205.47  5177.5  206.24  5353.6  210.62  5503.8  213.69
  5593.9  216.04  5645.9  216.81    5694  217.58  5714.1  218.22  5720.6  218.77
#Mann= 4 ,-1 , 0
  4794.2     .05       0  4990.4     .03       0  4996.4     .05       0
  5645.9      .1       0
Bank Sta=4987,5009.4
XS Rating Curve= 0 ,0
Exp/Cntr=0.3,0.1

Type RM Length L Ch R = 1 ,5136    ,398,398,398
BEGIN DESCRIPTION:
Mapping XS 4fc5daa3
END DESCRIPTION:
XS GIS Cut Line= 3
      3627789.25     10159071.73      3627336.08     10158907.65
      3626877.71     10158928.49
#Sta/Elev= 30
  4707.9  202.15  4715.5  201.76  4808.4  202.05  4844.4  201.53  4853.8  201.82
  4864.4  203.56    4875  201.73  4906.9  200.52  4917.6  200.22  4949.5  200.31
  4961.6   199.5  4981.4  199.67    4987     198  4989.3  196.82    4992  196.32
  4995.3  196.82  5012.3  199.75  5048.2  201.18  5055.8  202.02  5078.9   203.3
  5087.7  202.94  5134.8  204.04  5160.2  205.06  5172.8  205.11  5189.3  206.73
  5223.9  206.61  5454.1  212.88  5504.2  213.76  5574.2   215.5  5648.7  216.55
#Mann= 3 ,-1 , 0
  4707.9     .05       0  4989.3     .03       0  4995.3     .05       0
Bank Sta=4981.4,5012.3
XS Rating Curve= 0 ,0
Exp/Cntr=0.3,0.1

Type RM Length L Ch R = 1 ,4738    ,318,318,318
BEGIN DESCRIPTION:
Mapping XS 0f46d806
END DESCRIPTION:
XS GIS Cut Line= 3
      3627840.02     10158566.49      3627515.77     10158754.01
      3627086.95     10158796.63
#Sta/Elev= 30
  4809.2  201.29  4832.6     200  4854.1  199.53  4895.8  199.77  4934.5  198.93
  4944.5   197.9  4950.3  199.21    4957  198.55    4966  197.05  4971.8  197.35
  4974.9  196.88  4980.1  196.08  5000.2  194.37  5002.9  193.87  5006.2  194.37
  5009.1  195.12  5014.9   195.7  5037.8  195.68  5060.9  196.25  5067.9  196.98
  5095.6  198.14  5126.8  198.65  5132.6  199.07  5148.3  198.85    5183  200.38
  5378.4  205.74  5398.5  205.98  5438.7   207.7  5513.9  209.87  5614.7  213.39
#Mann= 5 ,-1 , 0
  4809.2     .05       0  4895.8     .12       0  4974.9     .05       0
  5000.2     .03       0  5006.2     .05       0
Bank Sta=4980.1,5014.9
XS Rating Curve= 0 ,0
Exp/Cntr=0.3,0.1

Type RM Length L Ch R = 1 ,4420    ,236,236,236
BEGIN DESCRIPTION:
Mapping XS 236b9d19
END DESCRIPTION:
XS GIS Cut Line= 3
      3627705.92     10158351.64      3627326.97     10158511.82
      3627011.84     10158781.37
#Sta/Elev= 30
  4806.4  203.12  4806.5  203.12  4846.7  202.47  4870.4  201.07  4886.5  200.94
  4917.8  199.15    4930  198.94  4940.8  198.09  4970.7  193.19  4981.2   192.3
    4984   191.8  4987.2   192.3  5016.8  193.03  5028.9  193.74  5038.5  194.72
  5047.2  196.16  5049.9  196.28  5060.2  197.19  5070.9  197.24  5114.5  198.91
  5158.3  201.32  5221.5  203.59  5256.6  205.22  5299.4   206.6  5327.9  207.07
  5383.9   209.6  5488.8  211.86  5492.3  211.95  5568.3  213.73  5632.5  214.42
#Mann= 7 ,-1 , 0
  4806.4     .05       0  4806.5     .12       0  4981.2     .07       0
  4987.2     .12       0  5049.9     .05       0  5488.8     .08       0
  5492.3     .05       0
Bank Sta=4981.2,4987.2
XS Rating Curve= 0 ,0
Exp/Cntr=0.3,0.1

Type RM Length L Ch R = 1 ,4184    ,78,78,78
BEGIN DESCRIPTION:
Mapping XS ffddae0a
END DESCRIPTION:
XS GIS Cut Line= 4
      3627675.96     10158257.93      3627565.25     10158195.41
      3627299.62     10158218.85      3626986.85     10158756.15
#Sta/Elev= 30
  4776.3  203.47  4796.2  202.71  4836.2  200.43  4885.2  196.42  4895.4  195.98
  4903.4  195.01  4914.5  194.68  4919.5  195.06  4946.8  193.66  4966.8  191.47
    5007  191.83    5014  191.24  5016.8  190.74    5020  191.24  5072.7  192.09
  5107.4  192.66  5127.5  193.73  5184.9  193.88  5214.3  194.95  5234.7  195.03
  5310.3  197.62  5353.3   199.8  5374.8  200.11  5412.1  202.13  5455.8   203.7
  5545.6  207.14  5588.3  209.06  5652.8  210.27  5711.6  212.92  5791.8  214.37
#Mann= 7 ,-1 , 0
  4776.3     .05       0  4796.2     .12       0    5014     .07       0
    5020     .12       0  5072.7     .05       0  5455.8     .08       0
  5545.6     .05       0
Bank Sta=5014,5020
XS Rating Curve= 0 ,0
Exp/Cntr=0.3,0.1

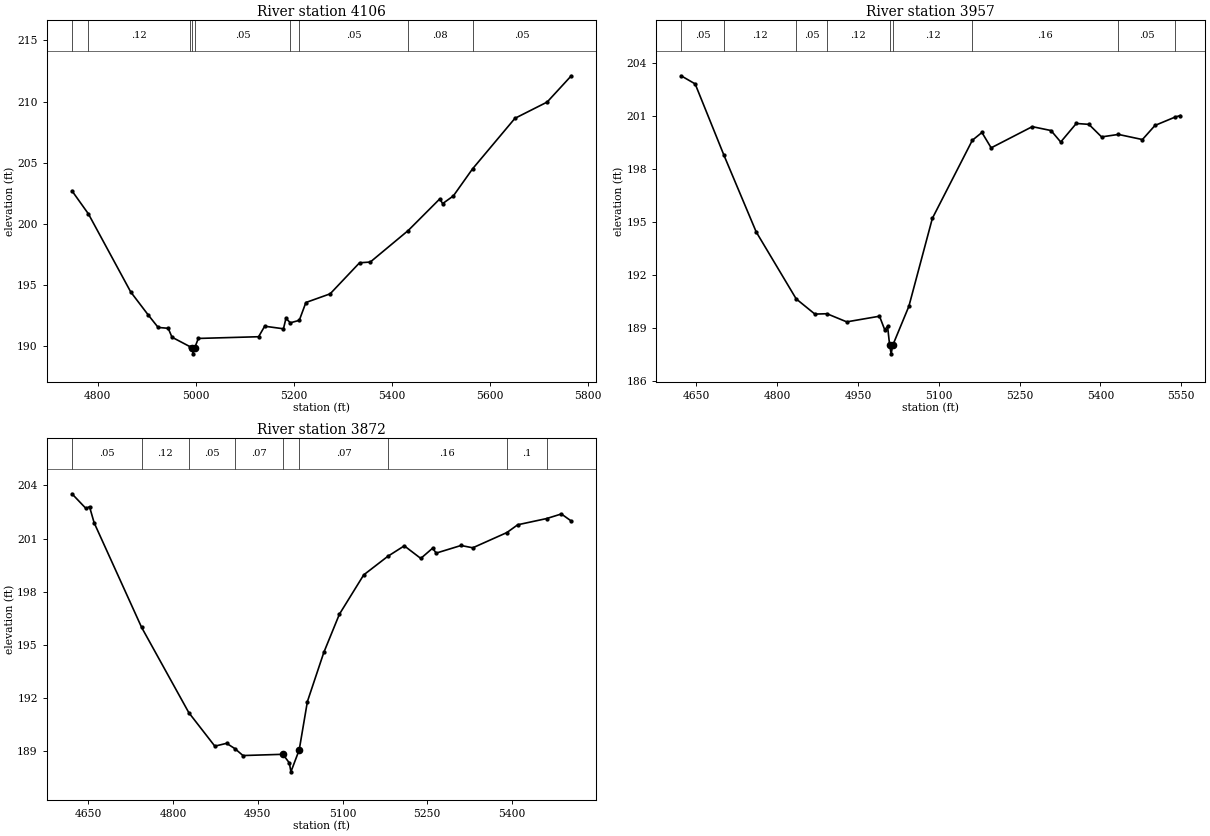
Type RM Length L Ch R = 1 ,4106    ,149,149,149
BEGIN DESCRIPTION:
Mapping XS eba47747
END DESCRIPTION:
XS GIS Cut Line= 4
      3627668.12     10158244.89      3627548.32     10158110.78
      3627280.09     10158170.67      3627012.23     10158667.39
#Sta/Elev= 30
  4747.2   202.7  4780.8  200.81  4867.2  194.42  4902.3  192.57  4923.1  191.52
  4943.6  191.45  4951.4  190.72  4988.9  189.93  4991.8  189.86  4994.5  189.36
  4997.8  189.86  5005.1  190.62  5128.1  190.76  5140.5  191.62  5178.8  191.41
  5183.9  192.26  5192.9   191.9  5211.1   192.1  5224.6  193.56  5274.1  194.27
  5334.1  196.81    5356  196.87  5433.4  199.45  5497.9  202.04  5503.6  201.65
  5525.5  202.28  5564.6  204.49  5651.2  208.63  5716.9  209.96  5766.2  212.11
#Mann= 9 ,-1 , 0
  4747.2     .05       0  4780.8     .12       0  4988.9     .05       0
  4991.8     .04       0  4997.8     .05       0  5192.9     .08       0
  5211.1     .05       0  5433.4     .08       0  5564.6     .05       0
Bank Sta=4991.8,4997.8
XS Rating Curve= 0 ,0
Exp/Cntr=0.3,0.1

Type RM Length L Ch R = 1 ,3957    ,85,85,85
BEGIN DESCRIPTION:
Mapping XS 453593af
END DESCRIPTION:
XS GIS Cut Line= 3
      3627685.03      10158255.3       3627535.3     10158075.62
      3626899.86     10157799.57
#Sta/Elev= 30
  4621.7  203.26  4647.8   202.8  4701.4  198.75  4761.1  194.42  4835.3  190.63
    4870  189.77  4892.4  189.79  4929.1  189.33  4989.9  189.65  4999.5  188.89
  5004.9  189.07  5008.7  188.02  5011.5  187.52  5014.7  188.02  5044.4  190.21
    5088  195.19  5162.2  199.61    5180  200.05  5197.1  199.18  5273.4  200.38
  5308.2  200.16  5326.2  199.51  5355.1  200.56  5378.5  200.51    5402   199.8
  5433.3  199.94  5477.8  199.65  5501.2  200.45  5539.1  200.93  5548.4  201.01
#Mann= 9 ,-1 , 0
  4621.7     .05       0  4701.4     .12       0  4835.3     .05       0
  4892.4     .12       0  5008.7     .07       0  5014.7     .12       0
  5162.2     .16       0  5433.3     .05       0  5539.1     .16       0
Bank Sta=5008.7,5014.7
XS Rating Curve= 0 ,0
Exp/Cntr=0.3,0.1

Type RM Length L Ch R = 1 ,3872    ,0,0,0
BEGIN DESCRIPTION:
UNT104 IN ROCK 1.0
END DESCRIPTION:
XS GIS Cut Line= 3
      3627693.17     10158255.12      3627352.87     10157817.59
      3627087.23     10157623.14
#Sta/Elev= 30
  4621.3  203.53  4646.1   202.7  4652.4   202.8  4660.6  201.89  4744.5  195.99
  4828.1  191.17  4874.1  189.28  4894.9  189.44  4909.6  189.14  4923.9  188.75
  4994.5  188.82    5006  188.33  5008.7  187.83  5023.4  189.07  5037.9   191.8
  5066.9  194.57  5094.5  196.73  5137.5  198.95  5180.2     200  5209.3  200.59
  5238.5  199.88  5259.5  200.46  5265.7  200.18  5309.7  200.61  5330.5  200.48
  5390.8  201.34    5410  201.78    5461  202.13  5487.2  202.39  5504.8  201.99
#Mann= 9 ,-1 , 0
  4621.3     .05       0  4744.5     .12       0  4828.1     .05       0
  4909.6     .07       0  4994.5     .03       0  5023.4     .07       0
  5180.2     .16       0  5390.8      .1       0    5461     .16       0
Bank Sta=4994.5,5023.4
XS Rating Curve= 0 ,0
Exp/Cntr=0.3,0.1

Chan Stop Cuts=-1
Use User Specified Reach Order=0
Composite Channel Slope=5