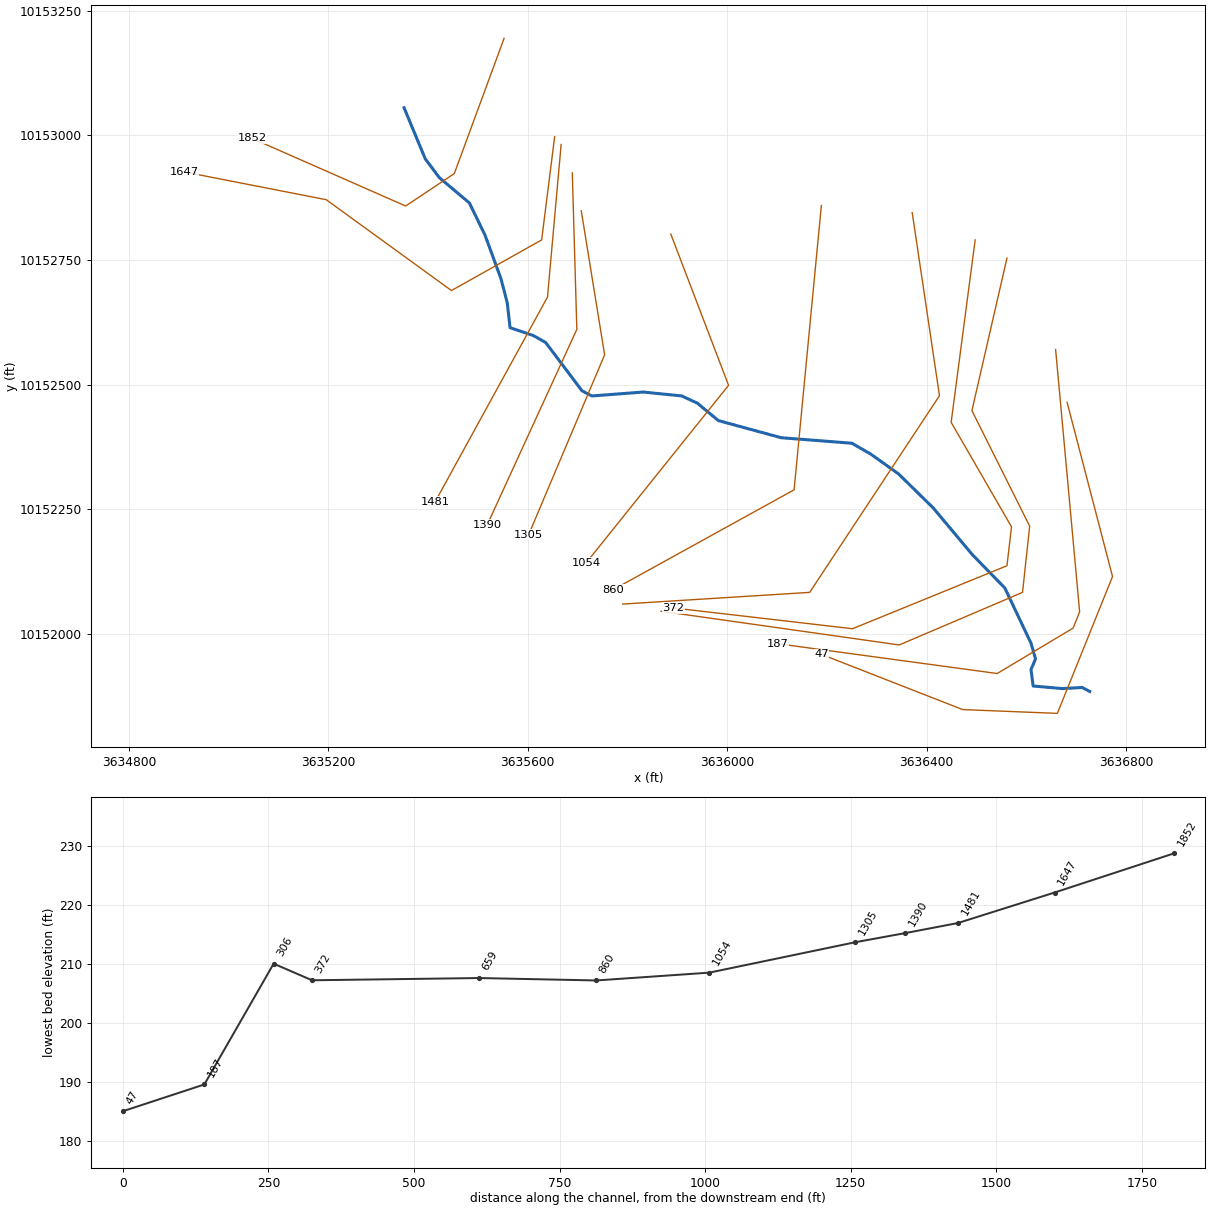
--- UNT105 IN ROCK.prj (project) ---

Proj Title=UNT105 IN ROCK Base Level Engineering
Current Plan=p01
Default Exp/Contr=0.3,0.1
English Units
Geom File=g01
Flow File=f01
Plan File=p01
Y Axis Title=Elevation
X Axis Title(PF)=Main Channel Distance
X Axis Title(XS)=Station
BEGIN DESCRIPTION:
UNT105 IN ROCK
END DESCRIPTION:
DSS Export Rating Curves= 0
DSS Export Rating Curve Sorted= 0
DSS Export Volume Flow Curves= 0
DXF OffsetX= 0
DXF OffsetY= 0
DXF ScaleX= 1
DXF ScaleY= 10

--- UNT105 IN ROCK.p01 (plan) ---

Plan Title=Multiple Run
Short Identifier=Multiple
Geom File=g01
Flow File=f01
Subcritical Flow
K Sum by GR= 0
Std Step Tol= 0.01
Critical Tol= 0.01
Num of Std Step Trials= 20
Max Error Tol= 0.3
Flow Tol Ratio= 0.001
Split Flow NTrial= 30
Split Flow Tol= 0.02
Split Flow Ratio= 0.02
Log Output Level= 0
Friction Slope Method= 1
Unsteady Friction Slope Method= 2
Unsteady Bridges Friction Slope Method= 1
Parabolic Critical Depth
Global Vel Dist=  1 , 1 , 1
Global Log Level= 0
CheckData=True
Encroach Param= -1, 0, 0, 0
BEGIN DESCRIPTION:
Multiple Run
END DESCRIPTION:

--- UNT105 IN ROCK.f01 (steady flow) ---

Flow Title=Multiple
Number of Profiles=7
Profile Names=10-year,25-year,50-year,1pct_min,100-year,1pct_plu,500-year
River Rch & RM= UNT105 IN ROCK,Reach-1,1852
     942    1296    1592    1431    1935    2617    2864
Boundary for River Rch & Prof#=UNT105 IN ROCK,Reach-1,1
Up Type=0
Dn Type=3
Dn Slope=0.005
Boundary for River Rch & Prof#=UNT105 IN ROCK,Reach-1,2
Up Type=0
Dn Type=3
Dn Slope=0.005
Boundary for River Rch & Prof#=UNT105 IN ROCK,Reach-1,3
Up Type=0
Dn Type=3
Dn Slope=0.005
Boundary for River Rch & Prof#=UNT105 IN ROCK,Reach-1,4
Up Type=0
Dn Type=3
Dn Slope=0.005
Boundary for River Rch & Prof#=UNT105 IN ROCK,Reach-1,5
Up Type=0
Dn Type=3
Dn Slope=0.005
Boundary for River Rch & Prof#=UNT105 IN ROCK,Reach-1,6
Up Type=0
Dn Type=3
Dn Slope=0.005
Boundary for River Rch & Prof#=UNT105 IN ROCK,Reach-1,7
Up Type=0
Dn Type=3
Dn Slope=0.005

--- UNT105 IN ROCK.g01 (geometry) ---

Geom Title=Existing Conditions
Program Version=4.10

River Reach=UNT105 IN ROCK  ,Reach-1
Reach XY= 30
      3635351.74     10153055.65      3635394.27     10152953.22
      3635422.05      10152915.9      3635482.81     10152864.68
      3635514.06     10152800.45      3635546.18     10152712.77
      3635558.75      10152664.4      3635564.48      10152614.4
      3635610.83     10152598.78      3635635.83     10152584.72
      3635708.75     10152487.84      3635728.47     10152477.53
      3635831.77     10152485.34      3635909.03     10152477.53
      3635940.28     10152462.95      3635982.46     10152428.05
      3636108.51     10152393.68      3636250.26     10152382.65
      3636288.02     10152360.95      3636344.01     10152321.02
      3636413.45     10152252.88      3636491.58     10152159.56
      3636557.12     10152092.29      3636609.63     10151981.61
      3636618.75     10151949.92      3636609.63     10151928.66
      3636613.98     10151895.67      3636672.13     10151890.46
       3636712.5     10151892.63      3636727.58      10151884.6

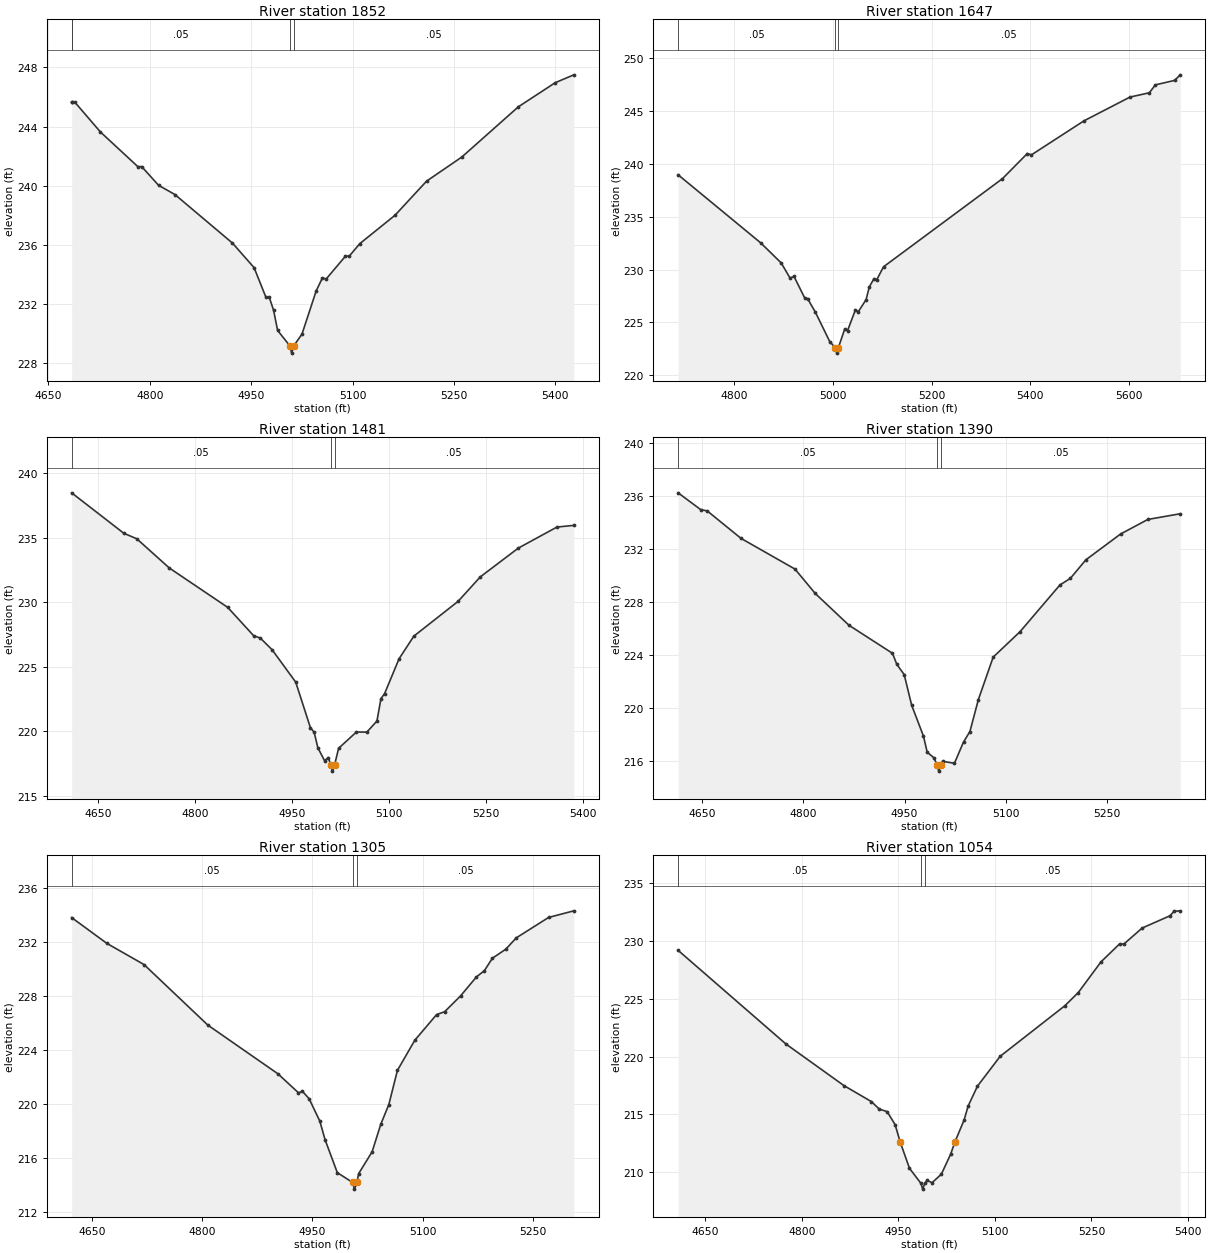
Type RM Length L Ch R = 1 ,1852    ,205,205,205
BEGIN DESCRIPTION:
Mapping XS c171dcccc
END DESCRIPTION:
XS GIS Cut Line= 4
      3635552.42      10153194.9       3635452.6     10152923.63
      3635354.94     10152858.53      3635046.97     10152994.08
#Sta/Elev= 30
  4684.4  245.66  4684.7  245.66  4688.8  245.66    4727  243.63  4782.6  241.28
  4787.9   241.3    4813  240.03  4837.1  239.41  4922.3  236.13  4954.3  234.47
  4971.9  232.46  4976.8  232.46  4983.1   231.6  4989.1  230.23  5007.1   229.2
  5009.8   228.7  5013.1   229.2  5025.1  229.98  5046.2  232.91  5055.2  233.76
  5061.2  233.72  5089.5  235.25  5095.1  235.25  5110.6  236.09  5162.8  238.01
  5209.4  240.31  5261.6  241.94  5345.2  245.33  5399.8  246.96  5427.3  247.49
#Mann= 4 ,-1 , 0
  4684.4     .08       0  4684.7     .05       0  5007.1     .03       0
  5013.1     .05       0
Bank Sta=5007.1,5013.1
XS Rating Curve= 0 ,0
Exp/Cntr=0.3,0.1

Type RM Length L Ch R = 1 ,1647    ,166,166,166
BEGIN DESCRIPTION:
Mapping XS e00a0eeb
END DESCRIPTION:
XS GIS Cut Line= 5
      3635653.87     10152997.52      3635627.83     10152790.49
      3635446.84     10152688.93      3635195.54     10152871.22
      3634910.58     10152926.92
#Sta/Elev= 30
  4686.6  238.98  4853.8  232.53  4895.3  230.63  4913.3  229.19  4921.3  229.35
    4943   227.3  4948.7  227.25  4964.7  225.95  4993.6  223.18    5005  222.58
  5007.8  222.08    5011  222.58    5024  224.36  5029.7  224.21  5045.7  226.18
  5051.4     226  5067.3  227.15  5073.8  228.36  5083.3  229.14    5089  229.05
  5102.6  230.26  5343.4  238.61  5393.7  240.99  5402.2  240.87  5508.5  244.09
  5601.6  246.34  5640.9  246.75  5653.1   247.5  5691.9  247.92  5703.6  248.45
#Mann= 3 ,-1 , 0
  4686.6     .05       0    5005     .03       0    5011     .05       0
Bank Sta=5005,5011
XS Rating Curve= 0 ,0
Exp/Cntr=0.3,0.1

Type RM Length L Ch R = 1 ,1481    ,91,91,91
BEGIN DESCRIPTION:
Mapping XS 56b21572
END DESCRIPTION:
XS GIS Cut Line= 3
       3635666.9     10152981.92      3635639.55     10152675.91
      3635413.94     10152264.89
#Sta/Elev= 30
  4609.2  238.47  4689.8  235.34  4709.9  234.91  4760.1  232.65  4850.4   229.6
  4890.6   227.4  4900.6  227.23    4919  226.32  4955.5  223.81  4978.2  220.28
    4984  219.93  4989.7  218.73    5000  217.73  5005.8  217.97  5009.6  217.42
  5012.3  216.92  5015.6  217.42  5021.8  218.69  5049.3  219.95  5065.4  219.94
    5081   220.8  5087.2  222.53  5092.9  222.93  5115.2  225.62    5138  227.37
  5206.5  230.07  5240.7  231.96  5299.5  234.19  5359.2  235.82  5385.3  235.95
#Mann= 3 ,-1 , 0
  4609.2     .05       0  5009.6     .03       0  5015.6     .05       0
Bank Sta=5009.6,5015.6
XS Rating Curve= 0 ,0
Exp/Cntr=0.3,0.1

Type RM Length L Ch R = 1 ,1390    ,85,85,85
BEGIN DESCRIPTION:
Mapping XS 20bba42b
END DESCRIPTION:
XS GIS Cut Line= 3
      3635689.29     10152924.95      3635698.41     10152611.18
      3635518.74      10152219.3
#Sta/Elev= 30
  4614.1  236.23  4647.4  234.97  4657.4  234.86  4707.4  232.79  4787.5  230.47
  4817.5  228.63  4867.5  226.23  4932.1  224.11  4938.5  223.28  4949.5   222.5
  4960.6  220.18  4978.1  217.85  4983.6  216.64  4993.5  216.22    4998  215.71
  5000.8  215.21    5004  215.71  5006.5  215.95    5024   215.8  5037.5  217.41
    5047   218.2  5059.5  220.61  5081.5  223.82  5121.5  225.75  5180.5  229.27
    5196  229.77    5219  231.17  5270.5  233.12    5311  234.22  5359.1  234.65
#Mann= 3 ,-1 , 0
  4614.1     .05       0    4998     .03       0    5004     .05       0
Bank Sta=4998,5004
XS Rating Curve= 0 ,0
Exp/Cntr=0.3,0.1

Type RM Length L Ch R = 1 ,1305    ,251,251,251
BEGIN DESCRIPTION:
Mapping XS b037db60
END DESCRIPTION:
XS GIS Cut Line= 3
      3635707.27     10152849.06      3635754.14     10152560.03
      3635601.81     10152199.39
#Sta/Elev= 30
  4621.9  233.78  4669.9  231.87  4720.6   230.3  4807.5  225.82  4902.9  222.22
    4931  220.81  4936.4  220.92  4945.5  220.37  4960.1  218.71  4967.2  217.34
  4983.9   214.9  5004.6  214.18  5007.3  213.68  5010.6  214.18    5013  214.83
  5031.3  216.44  5043.2  218.49  5054.1  219.94  5065.8  222.47  5089.5   224.7
  5119.2   226.6  5130.1  226.81  5151.8  227.98  5173.5  229.39  5184.3  229.85
  5195.2  230.77  5213.5  231.44  5227.8  232.28  5271.8  233.79  5306.2  234.28
#Mann= 3 ,-1 , 0
  4621.9     .05       0  5004.6     .03       0  5010.6     .05       0
Bank Sta=5004.6,5010.6
XS Rating Curve= 0 ,0
Exp/Cntr=0.3,0.1

Type RM Length L Ch R = 1 ,1054    ,194,194,194
BEGIN DESCRIPTION:
Mapping XS 6acf24fd
END DESCRIPTION:
XS GIS Cut Line= 3
      3635886.95     10152802.22      3636002.83     10152498.83
      3635717.67     10152143.34
#Sta/Elev= 30
  4607.7   229.2  4775.3  221.09  4865.5  217.49    4908  216.11  4920.3  215.46
  4932.5  215.24  4944.9  214.12  4952.9   212.6  4967.3  210.33  4985.1  209.03
  4987.8  208.53  4991.1  209.03  4994.5  209.28  5002.5  209.09  5016.9  209.83
  5031.3  211.56  5037.7  212.59  5052.1   214.5  5058.5  215.73  5072.9  217.44
  5108.3  220.03  5208.9  224.41  5229.7  225.55  5264.9   228.2  5293.7  229.75
  5300.6  229.75  5328.9  231.13  5372.1  232.19  5378.5  232.58  5388.2  232.62
#Mann= 3 ,-1 , 0
  4607.7     .05       0  4985.1     .03       0  4991.1     .05       0
Bank Sta=4952.9,5037.7
XS Rating Curve= 0 ,0
Exp/Cntr=0.3,0.1

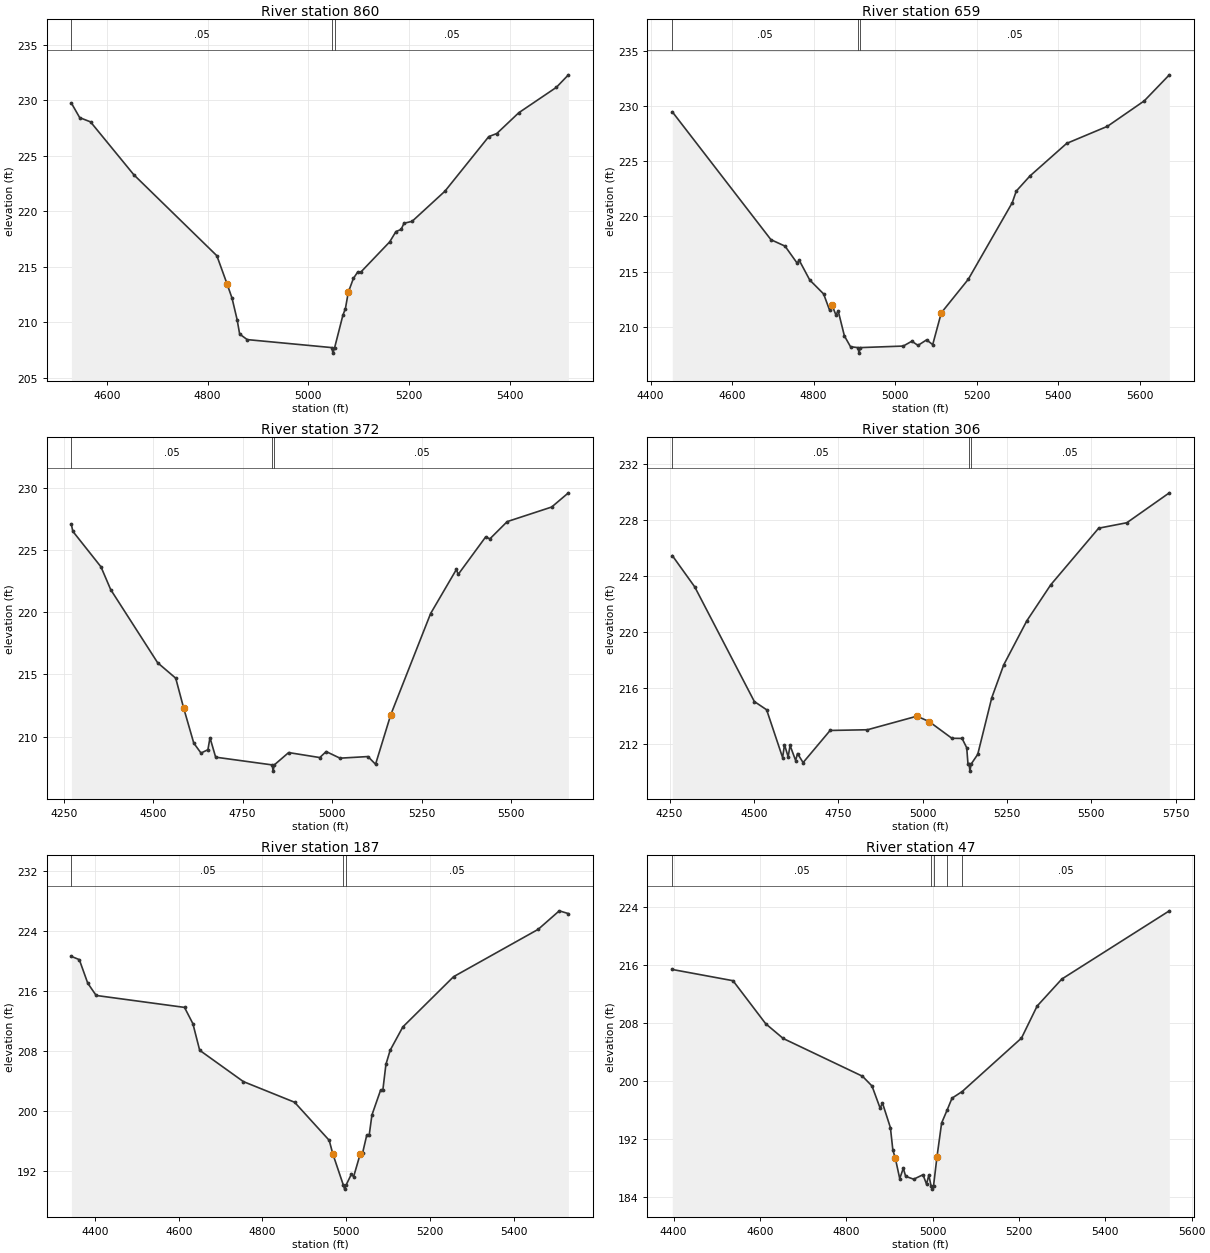
Type RM Length L Ch R = 1 ,860     ,201,201,201
BEGIN DESCRIPTION:
Mapping XS 074d52ad
END DESCRIPTION:
XS GIS Cut Line= 3
      3636189.03     10152859.46      3636134.34     10152289.19
      3635771.09     10152088.69
#Sta/Elev= 30
  4529.3  229.75  4545.8  228.44  4567.3  228.06  4653.4  223.29  4818.4  215.99
  4838.5  213.47  4848.6  212.16  4858.6  210.24  4863.7  208.93  4878.7  208.43
  5046.5  207.71  5049.2  207.21  5052.5  207.71  5068.9  210.63  5073.9  211.23
  5079.6  212.69  5089.7  213.94  5098.4  214.53  5104.8  214.53  5161.9  217.24
  5174.3  218.17  5184.6  218.36  5190.3  218.92  5206.4  219.09  5271.7  221.81
  5358.8  226.73  5374.8  227.01  5418.4  228.88  5493.1  231.17  5517.1   232.3
#Mann= 3 ,-1 , 0
  4529.3     .05       0  5046.5     .03       0  5052.5     .05       0
Bank Sta=4838.5,5079.6
XS Rating Curve= 0 ,0
Exp/Cntr=0.3,0.1

Type RM Length L Ch R = 1 ,659     ,287,287,287
BEGIN DESCRIPTION:
Mapping XS 553e4f0e
END DESCRIPTION:
XS GIS Cut Line= 4
      3636371.32     10152845.21      3636426.01     10152477.99
      3636165.59     10152083.46      3635790.62     10152060.03
#Sta/Elev= 30
  4453.2  229.47  4695.3  217.89  4729.8  217.31  4759.5  215.77  4764.6  216.03
  4790.5  214.24  4824.5  212.98  4839.4  211.49  4845.3  211.95  4854.4   211.1
  4860.4  211.42  4875.5  209.18  4890.5   208.2  4908.6  208.12  4911.4  207.62
  4914.6  208.12    5020  208.26    5041   208.7  5056.1  208.32  5077.2  208.82
  5092.2  208.39  5113.3  211.27  5179.6  214.31  5287.4  221.24  5297.2  222.29
  5330.8  223.66  5420.9  226.61  5521.1  228.16  5611.3  230.46  5672.9  232.82
#Mann= 3 ,-1 , 0
  4453.2     .05       0  4908.6    .033       0  4914.6     .05       0
Bank Sta=4845.3,5113.3
XS Rating Curve= 0 ,0
Exp/Cntr=0.3,0.1

Type RM Length L Ch R = 1 ,372     ,66,66,66
BEGIN DESCRIPTION:
Mapping XS 4bacb8ba
END DESCRIPTION:
XS GIS Cut Line= 6
      3636497.63     10152790.52      3636449.45     10152424.61
      3636570.54     10152214.97      3636561.43     10152136.85
      3636251.53     10152010.55       3635892.2     10152052.21
#Sta/Elev= 30
  4271.6  227.04  4275.6  226.49  4354.2  223.64  4381.4  221.81  4512.5  215.94
    4563   214.7  4585.1  212.31  4613.4  209.49  4633.6  208.69  4652.9  208.96
  4658.7  209.92  4674.5  208.36  4832.3  207.74    4835  207.24  4838.3  207.74
  4878.4  208.73  4965.3  208.33  4983.2  208.81  5021.8  208.28  5099.9  208.41
  5121.1  207.79  5163.5  211.76  5274.9  219.89  5346.9  223.43  5351.9  223.03
  5428.4  226.03  5440.6  225.89  5488.8  227.27    5613  228.44  5659.8  229.58
#Mann= 3 ,-1 , 0
  4271.6     .05       0  4832.3    .033       0  4838.3     .05       0
Bank Sta=4585.1,5163.5
XS Rating Curve= 0 ,0
Exp/Cntr=0.3,0.1

Type RM Length L Ch R = 1 ,306     ,119,119,119
BEGIN DESCRIPTION:
Mapping XS 93f84341
END DESCRIPTION:
XS GIS Cut Line= 6
      3636561.43     10152754.03      3636491.12     10152448.05
        3636607.     10152216.28      3636592.68     10152083.46
      3636345.28     10151977.99      3635867.37     10152045.71
#Sta/Elev= 30
  4258.1  225.47  4324.6  223.23  4501.2  215.03  4537.6  214.44    4585  211.02
  4590.6  211.94  4601.5  211.07  4607.1  211.89  4623.6  210.81  4629.2  211.31
  4645.7  210.66  4725.8  212.96  4836.5  213.01    4983  213.98    5019   213.6
  5086.7   212.4  5116.9  212.39  5130.7  211.72  5134.3  210.59  5137.6  210.55
  5140.3  210.05  5143.6  210.55  5163.3  211.25  5204.9   215.3  5240.3  217.65
  5308.7   220.8  5379.7  223.38  5521.7  227.43  5605.2  227.82  5731.2  229.96
#Mann= 3 ,-1 , 0
  4258.1     .05       0  5137.6     .03       0  5143.6     .05       0
#XS Ineff= 2 , 0
       0 4959.87  213.42 5024.89       0  213.36
Permanent Ineff=
       T       T
Bank Sta=4983,5019
XS Rating Curve= 0 ,0
Exp/Cntr=0.3,0.1

Type RM Length L Ch R = 1 ,187     ,140,140,140
BEGIN DESCRIPTION:
Mapping XS b397d9ff
END DESCRIPTION:
XS GIS Cut Line= 5
      3636659.08     10152570.48      3636707.26      10152044.4
      3636694.24     10152011.85       3636541.9      10151920.7
      3636100.51      10151980.6
#Sta/Elev= 30
  4343.9  220.61  4362.8  220.18  4382.9  217.05    4403  215.41  4613.9  213.82
  4633.9  211.65  4650.1  208.11  4754.4  203.94  4876.6  201.19  4959.2  196.12
    4968  194.29  4993.2  190.12    4996  189.62  4999.2  190.12  5011.8  191.57
  5017.6  191.29  5033.2  194.29    5039  194.45  5048.7  196.77  5054.6  196.77
  5061.2  199.49  5081.7  202.77  5087.2  202.77  5094.6  206.23  5104.7  208.11
    5135  211.22  5256.1  217.91  5457.9  224.21  5508.4  226.68  5530.2  226.31
#Mann= 3 ,-1 , 0
  4343.9     .05       0  4993.2     .03       0  4999.2     .05       0
Bank Sta=4968,5033.2
XS Rating Curve= 0 ,0
Exp/Cntr=0.3,0.1

Type RM Length L Ch R = 1 ,47      ,0,0,0
BEGIN DESCRIPTION:
UNT105 IN ROCK 1.0
END DESCRIPTION:
XS GIS Cut Line= 5
       3636682.1     10152464.61      3636773.23     10152115.26
      3636662.56     10151840.73      3636472.67     10151848.33
       3636189.5     10151958.99
#Sta/Elev= 30
  4397.2  215.42  4537.8  213.87  4613.6  207.92  4654.1  205.89  4837.6  200.68
  4859.7  199.33  4878.5  196.27  4883.9  196.99  4902.3  193.58    4908  190.47
  4913.4  189.43  4923.9  186.54  4932.2  187.98  4937.6  186.86  4956.2  186.46
  4977.8  187.08  4985.9  185.78  4991.3  187.02  4996.3  185.59  4999.1  185.09
  5002.3  185.59    5010  189.47  5020.9  194.22  5033.9  196.04    5045  197.65
  5068.6  198.57  5205.9  205.95  5242.1  210.37  5299.3   214.1  5548.3  223.52
#Mann= 5 ,-1 , 0
  4397.2     .05       0  4996.3     .03       0  5002.3     .05       0
  5033.9     .12       0  5068.6     .05       0
Bank Sta=4913.4,5010
XS Rating Curve= 0 ,0
Exp/Cntr=0.3,0.1

Chan Stop Cuts=-1
Use User Specified Reach Order=0
Composite Channel Slope=5