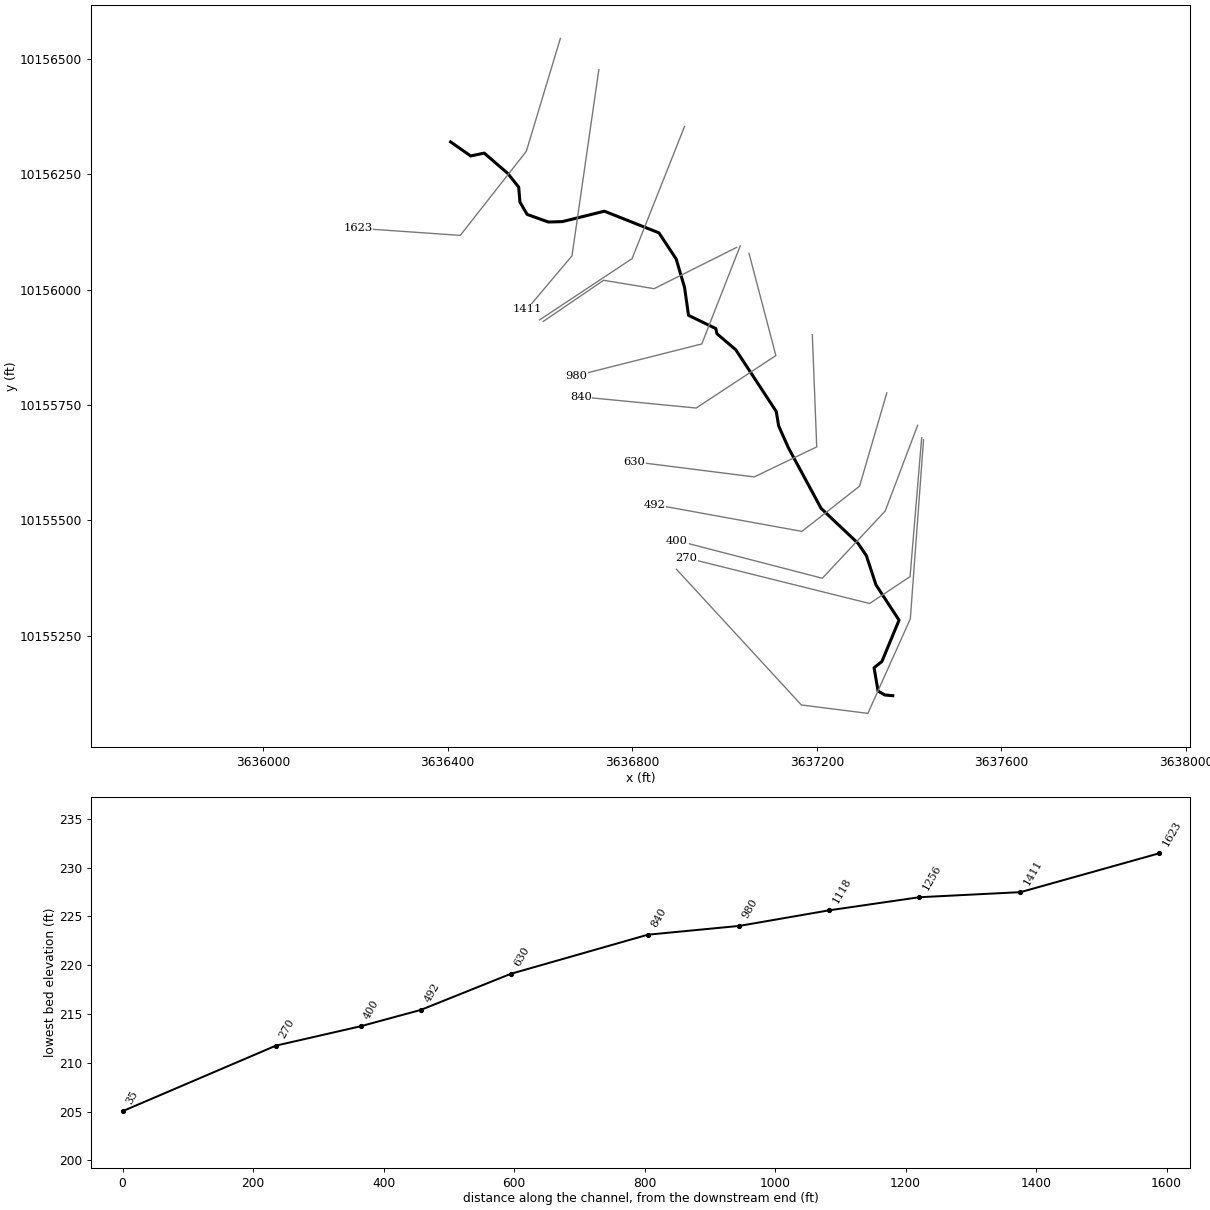
--- UNT106 IN ROCK.prj (project) ---

Proj Title=UNT106 IN ROCK Base Level Engineering
Current Plan=p01
Default Exp/Contr=0.3,0.1
English Units
Geom File=g01
Flow File=f01
Plan File=p01
Y Axis Title=Elevation
X Axis Title(PF)=Main Channel Distance
X Axis Title(XS)=Station
BEGIN DESCRIPTION:
UNT106 IN ROCK
END DESCRIPTION:
DSS Export Rating Curves= 0
DSS Export Rating Curve Sorted= 0
DSS Export Volume Flow Curves= 0
DXF OffsetX= 0
DXF OffsetY= 0
DXF ScaleX= 1
DXF ScaleY= 10

--- UNT106 IN ROCK.p01 (plan) ---

Plan Title=Multiple Run
Short Identifier=Multiple
Geom File=g01
Flow File=f01
Subcritical Flow
K Sum by GR= 0
Std Step Tol= 0.01
Critical Tol= 0.01
Num of Std Step Trials= 20
Max Error Tol= 0.3
Flow Tol Ratio= 0.001
Split Flow NTrial= 30
Split Flow Tol= 0.02
Split Flow Ratio= 0.02
Log Output Level= 0
Friction Slope Method= 1
Unsteady Friction Slope Method= 2
Unsteady Bridges Friction Slope Method= 1
Parabolic Critical Depth
Global Vel Dist=  1 , 1 , 1
Global Log Level= 0
CheckData=True
Encroach Param= -1, 0, 0, 0
BEGIN DESCRIPTION:
Multiple Run
END DESCRIPTION:

--- UNT106 IN ROCK.f01 (steady flow) ---

Flow Title=Multiple
Number of Profiles=7
Profile Names=10-year,25-year,50-year,1pct_min,100-year,1pct_plu,500-year
River Rch & RM= UNT106 IN ROCK,Reach-1,1623
      90     106     118      97     131     178     161
Boundary for River Rch & Prof#=UNT106 IN ROCK,Reach-1,1
Up Type=0
Dn Type=3
Dn Slope=0.005
Boundary for River Rch & Prof#=UNT106 IN ROCK,Reach-1,2
Up Type=0
Dn Type=3
Dn Slope=0.005
Boundary for River Rch & Prof#=UNT106 IN ROCK,Reach-1,3
Up Type=0
Dn Type=3
Dn Slope=0.005
Boundary for River Rch & Prof#=UNT106 IN ROCK,Reach-1,4
Up Type=0
Dn Type=3
Dn Slope=0.005
Boundary for River Rch & Prof#=UNT106 IN ROCK,Reach-1,5
Up Type=0
Dn Type=3
Dn Slope=0.005
Boundary for River Rch & Prof#=UNT106 IN ROCK,Reach-1,6
Up Type=0
Dn Type=3
Dn Slope=0.005
Boundary for River Rch & Prof#=UNT106 IN ROCK,Reach-1,7
Up Type=0
Dn Type=3
Dn Slope=0.005

--- UNT106 IN ROCK.g01 (geometry) ---

Geom Title=Existing Conditions
Program Version=4.10

River Reach=UNT106 IN ROCK  ,Reach-1
Reach XY= 30
       3636406.3     10156320.09       3636449.7     10156289.71
      3636479.21     10156295.79      3636530.43     10156251.52
      3636553.87       10156222.      3636556.47     10156189.88
       3636572.1     10156162.97       3636618.1     10156146.48
      3636648.48     10156147.35      3636739.63     10156169.92
      3636857.69     10156123.04      3636895.01     10156066.62
      3636913.24     10156004.99      3636921.92     10155944.23
      3636980.95     10155915.58      3636983.55     10155904.29
      3637024.35     10155869.57      3637112.03     10155735.89
      3637117.23     10155704.64      3637138.07     10155657.77
      3637209.25     10155525.82      3637289.11      10155450.3
      3637307.34     10155423.39      3637328.17     10155360.02
      3637378.17     10155283.63      3637341.02     10155194.05
      3637324.01     10155180.51      3637332.69     10155129.82
      3637347.27     10155121.48      3637364.63     10155119.93

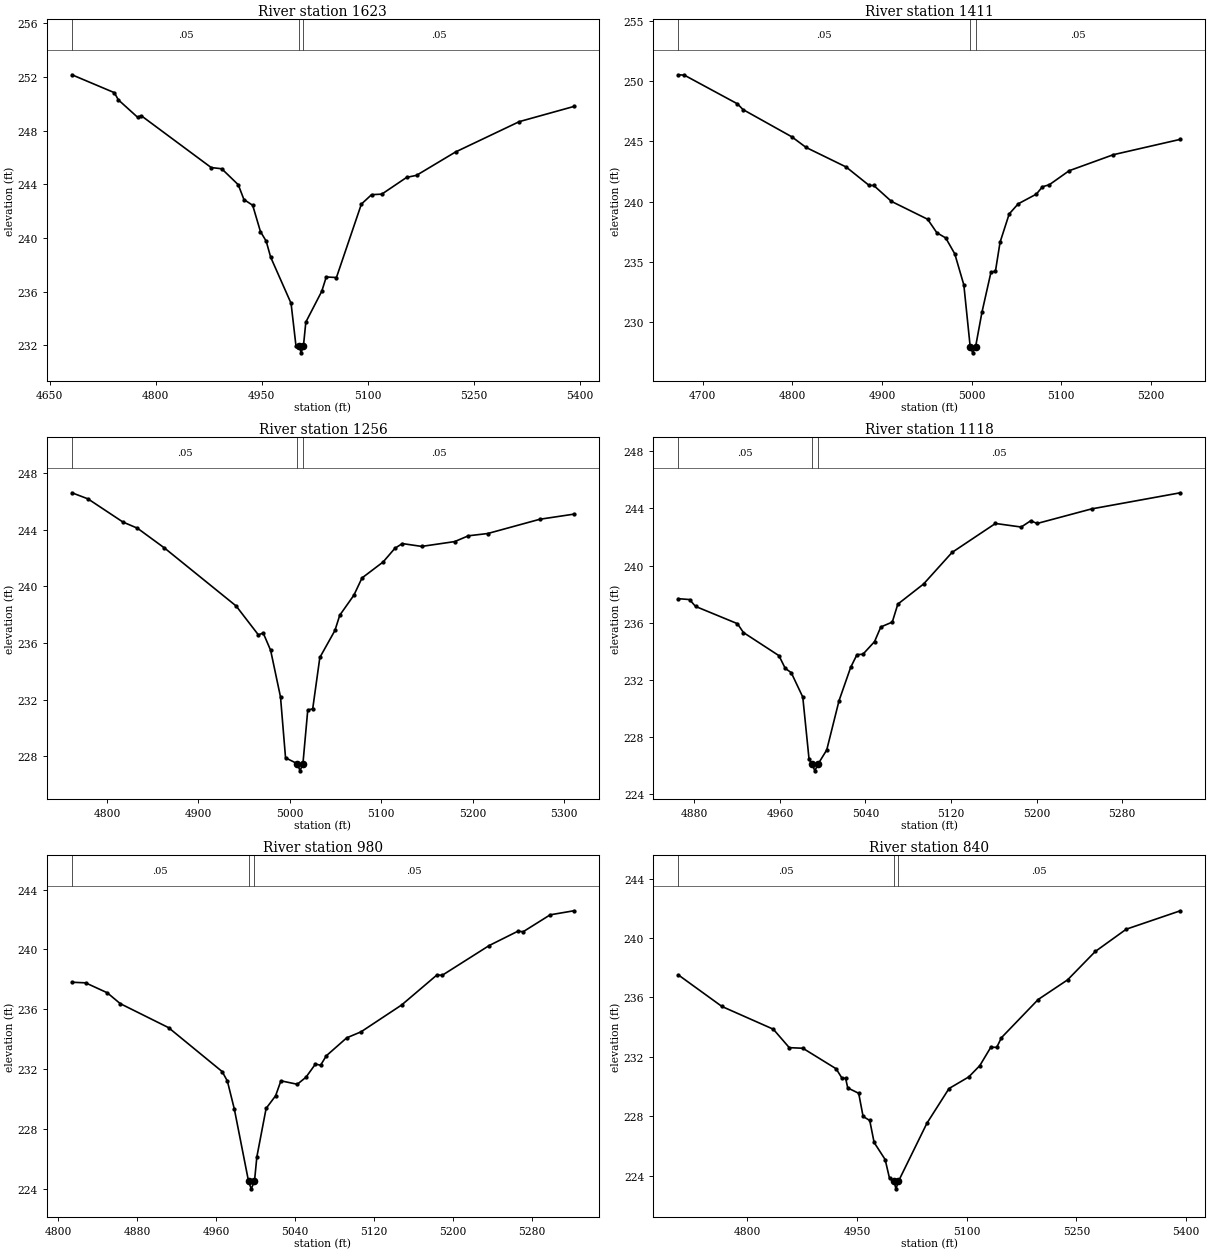
Type RM Length L Ch R = 1 ,1623    ,212,212,212
BEGIN DESCRIPTION:
UNT106 IN ROCK 2.0
END DESCRIPTION:
XS GIS Cut Line= 4
      3636644.19     10156544.56      3636570.41     10156299.76
      3636427.18     10156117.47      3636205.12     10156132.97
#Sta/Elev= 30
  4681.3  252.16  4741.2  250.83    4747  250.29  4774.1     249  4779.4  249.11
  4878.3  245.25  4893.2  245.16  4916.6  243.97  4924.6  242.87    4937  242.44
    4948  240.48  4956.1  239.77  4962.4  238.58  4991.3  235.14  4998.2  231.99
  5002.8  231.95  5005.5  231.45  5008.8  231.95  5012.2  233.74  5034.7  236.03
  5041.1   237.1  5055.5  237.06  5090.8  242.53  5105.2  243.23  5119.7  243.27
  5154.9  244.52  5168.8  244.67    5224  246.41  5314.2  248.67  5391.4   249.8
#Mann= 3 ,-1 , 0
  4681.3     .05       0  5002.8     .03       0  5008.8     .05       0
Bank Sta=5002.8,5008.8
XS Rating Curve= 0 ,0
Exp/Cntr=0.3,0.1

Type RM Length L Ch R = 1 ,1411    ,155,155,155
BEGIN DESCRIPTION:
Mapping XS 86e5b6d7
END DESCRIPTION:
XS GIS Cut Line= 3
      3636727.52     10156476.82      3636669.37      10156073.2
      3636571.31     10155956.92
#Sta/Elev= 30
  4672.9  250.52  4679.5  250.49  4738.8  248.11  4744.9  247.64  4799.4  245.38
  4815.3   244.5    4860  242.88  4885.7  241.35  4890.8  241.35  4910.5  240.03
  4950.9  238.55  4961.2  237.43  4971.1     237  4981.2  235.68  4991.3  233.11
  4998.4  227.98  5001.2  227.48  5004.4  227.98  5011.5  230.84  5021.5  234.14
  5026.6  234.26  5031.7  236.64  5041.9  238.99    5052  239.83  5072.2  240.63
    5079  241.24  5086.7  241.41  5108.8  242.57  5158.2   243.9  5232.8  245.17
#Mann= 3 ,-1 , 0
  4672.9     .05       0  4998.4    .035       0  5004.4     .05       0
Bank Sta=4998.4,5004.4
XS Rating Curve= 0 ,0
Exp/Cntr=0.3,0.1

Type RM Length L Ch R = 1 ,1256    ,138,138,138
BEGIN DESCRIPTION:
Mapping XS 74870e73
END DESCRIPTION:
XS GIS Cut Line= 3
      3636913.28     10156353.55      3636799.58     10156067.13
      3636599.04      10155934.3
#Sta/Elev= 30
  4761.8  246.61  4779.3  246.18  4817.6  244.54  4833.3  244.11  4862.9  242.71
  4941.3  238.61  4965.6  236.57  4970.9   236.7    4979  235.48  4989.8  232.18
  4995.3  227.88  5008.3  227.46  5011.1  226.96  5014.3  227.46  5019.6  231.26
    5025  231.34  5032.8  234.97  5049.3  236.88  5054.6  237.96    5070  239.37
  5078.9  240.59    5102  241.72  5114.9  242.69    5123  243.02  5144.1  242.82
  5180.2  243.16  5195.2  243.57  5216.3  243.73  5273.4  244.74  5310.5   245.1
#Mann= 3 ,-1 , 0
  4761.8     .05       0  5008.3    .035       0  5014.3     .05       0
Bank Sta=5008.3,5014.3
XS Rating Curve= 0 ,0
Exp/Cntr=0.3,0.1

Type RM Length L Ch R = 1 ,1118    ,138,138,138
BEGIN DESCRIPTION:
Mapping XS 02600267
END DESCRIPTION:
XS GIS Cut Line= 4
      3637026.17     10156091.45      3636847.32     10156002.02
      3636737.94     10156020.25      3636606.96     10155930.91
#Sta/Elev= 30
  4865.1  237.68  4875.5  237.62  4881.1  237.14  4920.3  235.93  4925.9  235.31
  4959.1  233.69    4965   232.8  4970.6   232.5  4981.4  230.79  4987.3  226.42
  4989.9  226.12  4992.7  225.62  4995.9  226.12  5003.8  227.08  5015.3  230.53
  5026.2  232.87  5032.1  233.76  5037.7  233.79  5048.5  234.67  5054.4   235.7
  5065.1  236.04  5070.3   237.3  5094.4  238.71    5121  240.92  5161.6  242.95
  5185.7   242.7  5194.6  243.14  5200.6  242.95  5251.5  243.97  5334.5   245.1
#Mann= 3 ,-1 , 0
  4865.1     .05       0  4989.9    .035       0  4995.9     .05       0
Bank Sta=4989.9,4995.9
XS Rating Curve= 0 ,0
Exp/Cntr=0.3,0.1

Type RM Length L Ch R = 1 ,980     ,140,140,140
BEGIN DESCRIPTION:
Mapping XS ff675c52
END DESCRIPTION:
XS GIS Cut Line= 3
      3637033.96     10156094.92      3636950.62     10155882.23
      3636678.88     10155813.64
#Sta/Elev= 30
  4814.1  237.81  4827.9  237.77  4849.8  237.11  4863.1  236.38    4912  234.78
  4966.3  231.85  4971.6  231.22  4978.7  229.34  4993.1  224.52  4995.8  224.02
  4999.1  224.52  5001.5  226.15  5010.9  229.39  5020.5  230.23  5025.9  231.23
  5042.5     231  5051.3  231.47  5060.9  232.35  5066.1  232.27  5071.9   232.9
  5092.6   234.1  5107.1   234.5  5148.2  236.29  5184.1   238.3  5189.3  238.27
    5237  240.26  5266.2  241.22  5271.4  241.18  5298.8  242.31  5322.8  242.58
#Mann= 3 ,-1 , 0
  4814.1     .05       0  4993.1    .035       0  4999.1     .05       0
Bank Sta=4993.1,4999.1
XS Rating Curve= 0 ,0
Exp/Cntr=0.3,0.1

Type RM Length L Ch R = 1 ,840     ,210,210,210
BEGIN DESCRIPTION:
Mapping XS 6615a5c7
END DESCRIPTION:
XS GIS Cut Line= 4
      3637053.06     10156078.37      3637111.21     10155857.06
      3636938.46     10155743.34      3636688.49     10155767.64
#Sta/Elev= 30
  4705.5  237.51  4765.1  235.39  4835.4  233.86  4857.2  232.62  4875.8  232.58
  4921.3   231.2  4929.4  230.56  4934.3  230.56  4937.2  229.91  4952.2  229.55
  4958.2  227.99  4967.3  227.72  4973.3  226.24  4988.4  225.09  4994.4  223.82
  5000.5  223.62  5003.2  223.12  5006.5  223.62  5045.6  227.54  5075.8  229.87
  5102.8  230.65  5117.9  231.41    5133  232.65  5141.1  232.64  5147.5  233.29
  5197.8  235.86    5238  237.18  5275.9  239.09  5318.3  240.59  5392.3  241.83
#Mann= 3 ,-1 , 0
  4705.5     .05       0  5000.5    .035       0  5006.5     .05       0
Bank Sta=5000.5,5006.5
XS Rating Curve= 0 ,0
Exp/Cntr=0.3,0.1

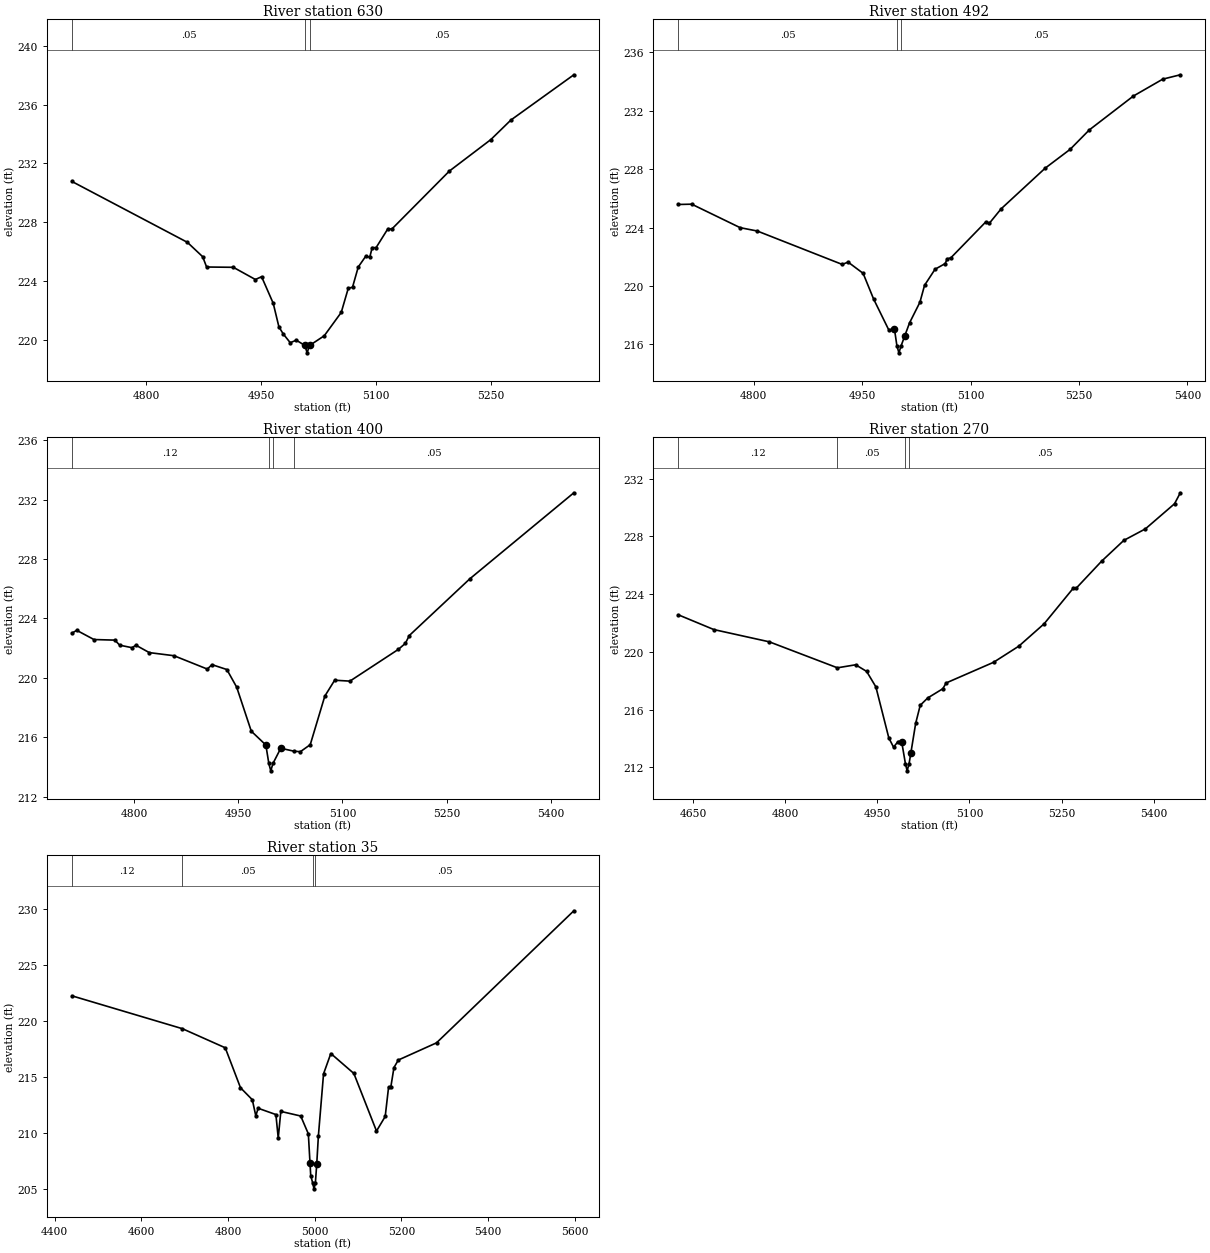
Type RM Length L Ch R = 1 ,630     ,138,138,138
BEGIN DESCRIPTION:
Mapping XS a70ce36a
END DESCRIPTION:
XS GIS Cut Line= 4
       3637190.2     10155902.19      3637199.75     10155659.14
      3637064.33     10155594.04      3636804.59     10155626.83
#Sta/Elev= 30
  4702.8  230.77  4853.5  226.63  4873.5  225.65  4878.6  224.95  4913.5  224.93
  4942.3   224.1  4950.4  224.29  4965.6  222.48    4973  220.88  4978.6   220.4
  4987.8   219.8  4995.7  219.97    5007  219.61  5009.8  219.11    5013  219.61
  5032.2  220.27  5054.4  221.86  5063.6  223.51  5069.1  223.57  5076.6  224.95
  5086.2  225.67  5091.7  225.63  5094.8  226.27  5099.9  226.27  5115.4  227.56
  5120.4  227.53  5195.6  231.48  5249.7  233.62  5275.9  234.95  5358.1  238.03
#Mann= 3 ,-1 , 0
  4702.8     .05       0    5007    .035       0    5013     .05       0
Bank Sta=5007,5013
XS Rating Curve= 0 ,0
Exp/Cntr=0.3,0.1

Type RM Length L Ch R = 1 ,492     ,92,92,92
BEGIN DESCRIPTION:
Mapping XS da426861
END DESCRIPTION:
XS GIS Cut Line= 4
      3637351.67     10155776.35      3637292.63     10155574.07
      3637167.63     10155475.98      3636848.19     10155534.14
#Sta/Elev= 30
  4695.9  225.58  4714.3   225.6  4781.3  223.99    4805  223.76  4922.5  221.47
  4930.6  221.63  4951.4  220.86  4965.9   219.1  4986.7     217  4994.8  217.02
  4998.1  215.91  5000.9  215.41  5004.1  215.91    5009  216.57  5015.6  217.46
    5030  218.88  5036.4  220.04  5050.9  221.14    5065  221.53  5067.6  221.85
  5072.7  221.92    5121  224.38    5126  224.29  5142.3  225.28  5203.3  228.07
  5237.8  229.36  5264.3  230.69  5325.2  233.01  5365.9  234.17  5390.2  234.47
#Mann= 3 ,-1 , 0
  4695.9     .05       0  4998.1     .03       0  5004.1     .05       0
Bank Sta=4994.8,5009
XS Rating Curve= 0 ,0
Exp/Cntr=0.3,0.1

Type RM Length L Ch R = 1 ,400     ,130,130,130
BEGIN DESCRIPTION:
Mapping XS 7e4fed5d
END DESCRIPTION:
XS GIS Cut Line= 4
      3637418.48     10155705.97      3637348.19     10155520.25
       3637211.9     10155374.42      3636896.97     10155455.97
#Sta/Elev= 30
    4710  223.01  4716.9   223.2  4741.7  222.58  4771.9  222.54  4778.8   222.2
  4796.7  222.03  4802.1   222.2  4821.5   221.7  4857.1  221.49  4905.2  220.59
  4911.8  220.89  4933.3  220.56  4947.5  219.37  4968.5  216.41  4989.5  215.48
  4993.8  214.24  4996.6  213.74  4999.8  214.24    5011  215.26  5030.3  215.06
  5039.3  215.03  5053.5   215.5  5074.5  218.77  5088.7  219.84  5110.7  219.78
  5180.3  221.91  5190.6  222.32  5196.3  222.85  5283.6  226.67  5433.5  232.46
#Mann= 4 ,-1 , 0
    4710     .12       0  4993.8     .07       0  4999.8     .12       0
  5030.3     .05       0
Bank Sta=4989.5,5011
XS Rating Curve= 0 ,0
Exp/Cntr=0.3,0.1

Type RM Length L Ch R = 1 ,270     ,235,235,235
BEGIN DESCRIPTION:
Mapping XS 895f0365
END DESCRIPTION:
XS GIS Cut Line= 4
      3637427.18     10155679.14      3637402.01     10155377.89
      3637314.33     10155319.73      3636916.97     10155418.64
#Sta/Elev= 30
  4626.2  222.56  4683.9  221.54  4774.2  220.69    4885  218.89  4914.7   219.1
  4932.6  218.64  4947.6  217.57  4968.7  214.03  4976.4  213.39  4983.7  213.78
  4989.7  213.75  4995.7  212.25  4998.5  211.75  5001.7  212.25  5004.7  213.02
  5012.4  215.04  5019.8  216.29    5032   216.8  5056.6  217.44    5062  217.84
  5139.1  219.27  5180.3  220.39  5221.5  221.94  5268.6  224.39  5273.8  224.41
  5315.1  226.28  5351.2  227.72  5386.4  228.52  5433.8  230.26  5443.2  231.02
#Mann= 4 ,-1 , 0
  4626.2     .12       0    4885     .05       0  4995.7     .03       0
  5001.7     .05       0
Bank Sta=4989.7,5004.7
XS Rating Curve= 0 ,0
Exp/Cntr=0.3,0.1

Type RM Length L Ch R = 1 ,35      ,0,0,0
BEGIN DESCRIPTION:
UNT106 IN ROCK 1.0
END DESCRIPTION:
XS GIS Cut Line= 5
      3637431.23      10155674.5      3637402.58     10155286.45
      3637310.57     10155081.59      3637166.47     10155099.82
      3636895.91     10155393.72
#Sta/Elev= 30
  4439.8  222.23  4694.8   219.3  4793.6   217.6  4828.8  214.04  4856.1  212.97
  4864.1  211.54  4869.6  212.21  4910.5  211.65  4915.9  209.56  4921.9  211.93
  4967.8  211.52  4985.4  209.93 4989.27   207.3  4990.9  206.21  4995.6  205.53
  4998.4  205.03  5001.6  205.53 5004.81  207.26  5008.6  209.76  5020.5  215.28
  5037.3  217.09  5090.5  215.31  5142.7  210.18  5162.8  211.48  5170.6   214.1
  5175.7  214.09    5183  215.84  5193.1  216.51  5281.2  218.04  5598.2  229.81
#Mann= 4 ,-1 , 0
  4439.8     .12       0  4694.8     .05       0  4995.6    .035       0
  5001.6     .05       0
Bank Sta=4989.27,5004.81
XS Rating Curve= 0 ,0
Exp/Cntr=0.3,0.1

Chan Stop Cuts=-1
Use User Specified Reach Order=0
Composite Channel Slope=5