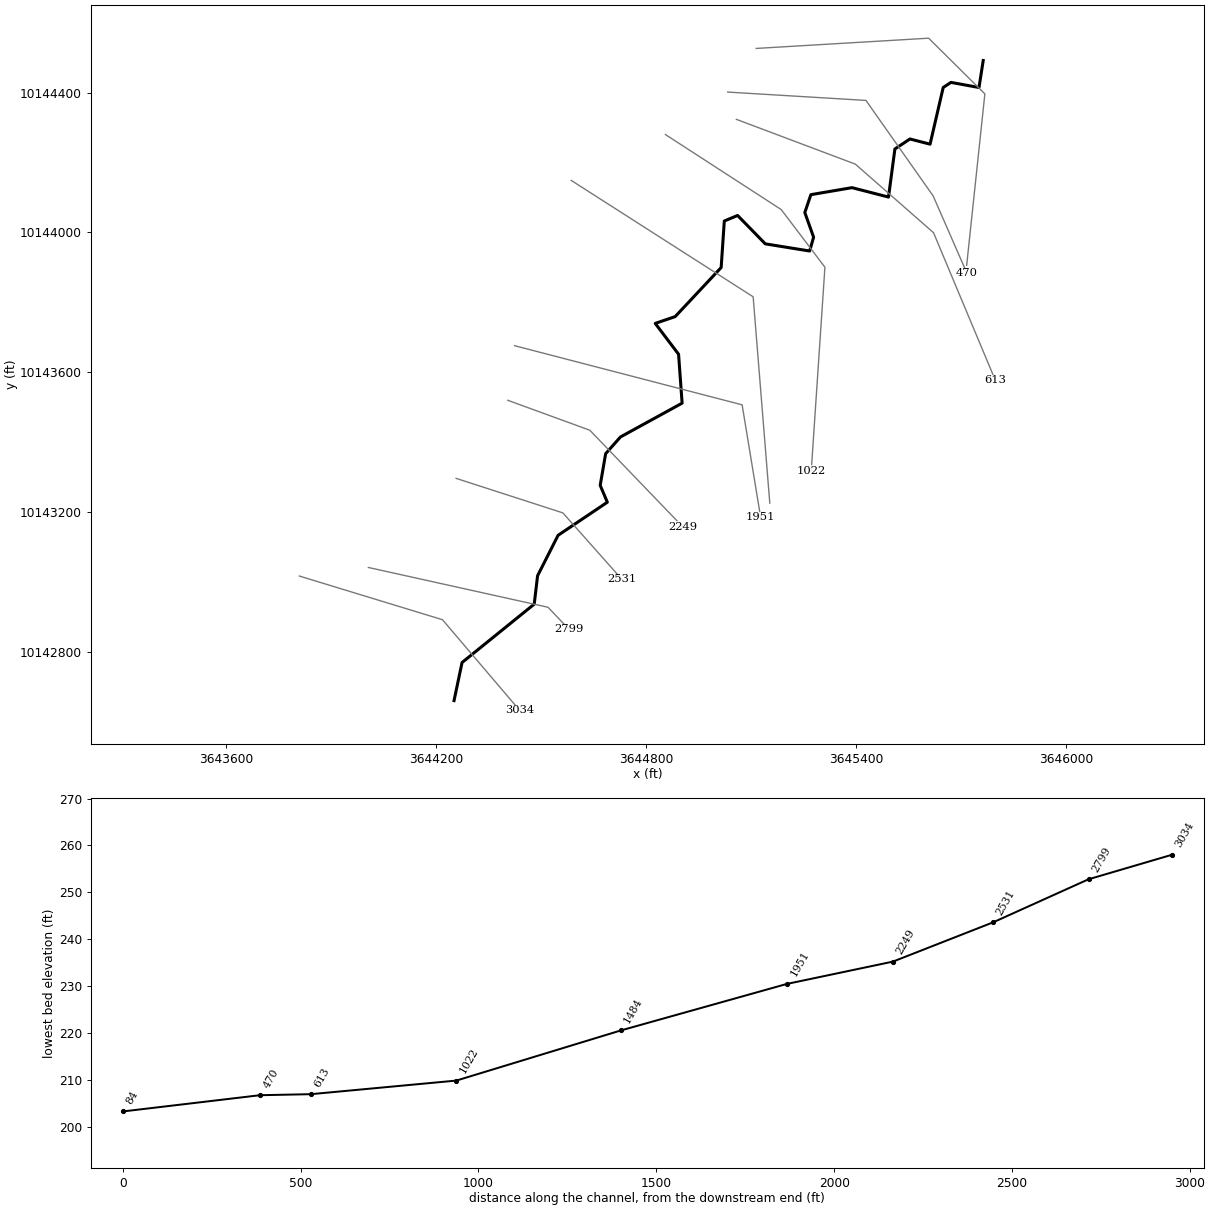
--- UNT107 IN ROCK.prj (project) ---

Proj Title=UNT107 IN ROCK Base Level Engineering
Current Plan=p01
Default Exp/Contr=0.3,0.1
English Units
Geom File=g01
Flow File=f01
Plan File=p01
Y Axis Title=Elevation
X Axis Title(PF)=Main Channel Distance
X Axis Title(XS)=Station
BEGIN DESCRIPTION:
UNT107 IN ROCK
END DESCRIPTION:
DSS Export Rating Curves= 0
DSS Export Rating Curve Sorted= 0
DSS Export Volume Flow Curves= 0
DXF OffsetX= 0
DXF OffsetY= 0
DXF ScaleX= 1
DXF ScaleY= 10

--- UNT107 IN ROCK.p01 (plan) ---

Plan Title=Multiple Run
Short Identifier=Multiple
Geom File=g01
Flow File=f01
Subcritical Flow
K Sum by GR= 0
Std Step Tol= 0.01
Critical Tol= 0.01
Num of Std Step Trials= 20
Max Error Tol= 0.3
Flow Tol Ratio= 0.001
Split Flow NTrial= 30
Split Flow Tol= 0.02
Split Flow Ratio= 0.02
Log Output Level= 0
Friction Slope Method= 1
Unsteady Friction Slope Method= 2
Unsteady Bridges Friction Slope Method= 1
Parabolic Critical Depth
Global Vel Dist=  1 , 1 , 1
Global Log Level= 0
CheckData=True
Encroach Param= -1, 0, 0, 0
BEGIN DESCRIPTION:
Multiple Run
END DESCRIPTION:

--- UNT107 IN ROCK.f01 (steady flow) ---

Flow Title=Multiple
Program Version=4.10
Number of Profiles= 7
Profile Names=10-year,25-year,50-year,1pct_min,100-year,1pct_plu,500-year
River Rch & RM=UNT107 IN ROCK,Reach-1         ,3034
     370     488     584     514     695     940     983
Boundary for River Rch & Prof#=UNT107 IN ROCK,Reach-1         , 1
Up Type= 0
Dn Type= 3
Dn Slope=0.014
Boundary for River Rch & Prof#=UNT107 IN ROCK,Reach-1         , 2
Up Type= 0
Dn Type= 3
Dn Slope=0.014
Boundary for River Rch & Prof#=UNT107 IN ROCK,Reach-1         , 3
Up Type= 0
Dn Type= 3
Dn Slope=0.014
Boundary for River Rch & Prof#=UNT107 IN ROCK,Reach-1         , 4
Up Type= 0
Dn Type= 3
Dn Slope=0.014
Boundary for River Rch & Prof#=UNT107 IN ROCK,Reach-1         , 5
Up Type= 0
Dn Type= 3
Dn Slope=0.014
Boundary for River Rch & Prof#=UNT107 IN ROCK,Reach-1         , 6
Up Type= 0
Dn Type= 3
Dn Slope=0.014
Boundary for River Rch & Prof#=UNT107 IN ROCK,Reach-1         , 7
Up Type= 0
Dn Type= 3
Dn Slope=0.014
DSS Import GetInterval= 0
DSS Import GetPeak= 0
DSS Import FillOption= 0

--- UNT107 IN ROCK.g01 (geometry) ---

Geom Title=Existing Conditions
Program Version=4.10

River Reach=UNT107 IN ROCK  ,Reach-1
Reach XY= 30
      3644250.29     10142659.61      3644273.19     10142768.65
      3644479.36     10142935.76      3644488.98     10143017.05
      3644547.54     10143132.78      3644688.28     10143227.46
      3644667.85     10143275.77      3644683.42     10143366.35
      3644725.78     10143414.27       3644901.9     10143511.02
      3644891.75     10143651.07      3644825.09     10143739.27
      3644882.03     10143758.71      3645013.45      10143899.2
      3645022.44      10144032.3      3645060.36     10144048.26
      3645139.55     10143966.95      3645266.31     10143946.44
      3645277.55     10143986.08      3645252.42      10144056.6
      3645269.78     10144107.76       3645387.2      10144127.8
      3645491.53     10144100.88       3645509.8     10144238.45
      3645552.73     10144267.13      3645610.28     10144252.23
      3645647.84     10144414.51      3645669.96     10144429.11
      3645750.08     10144414.45      3645762.11     10144491.64

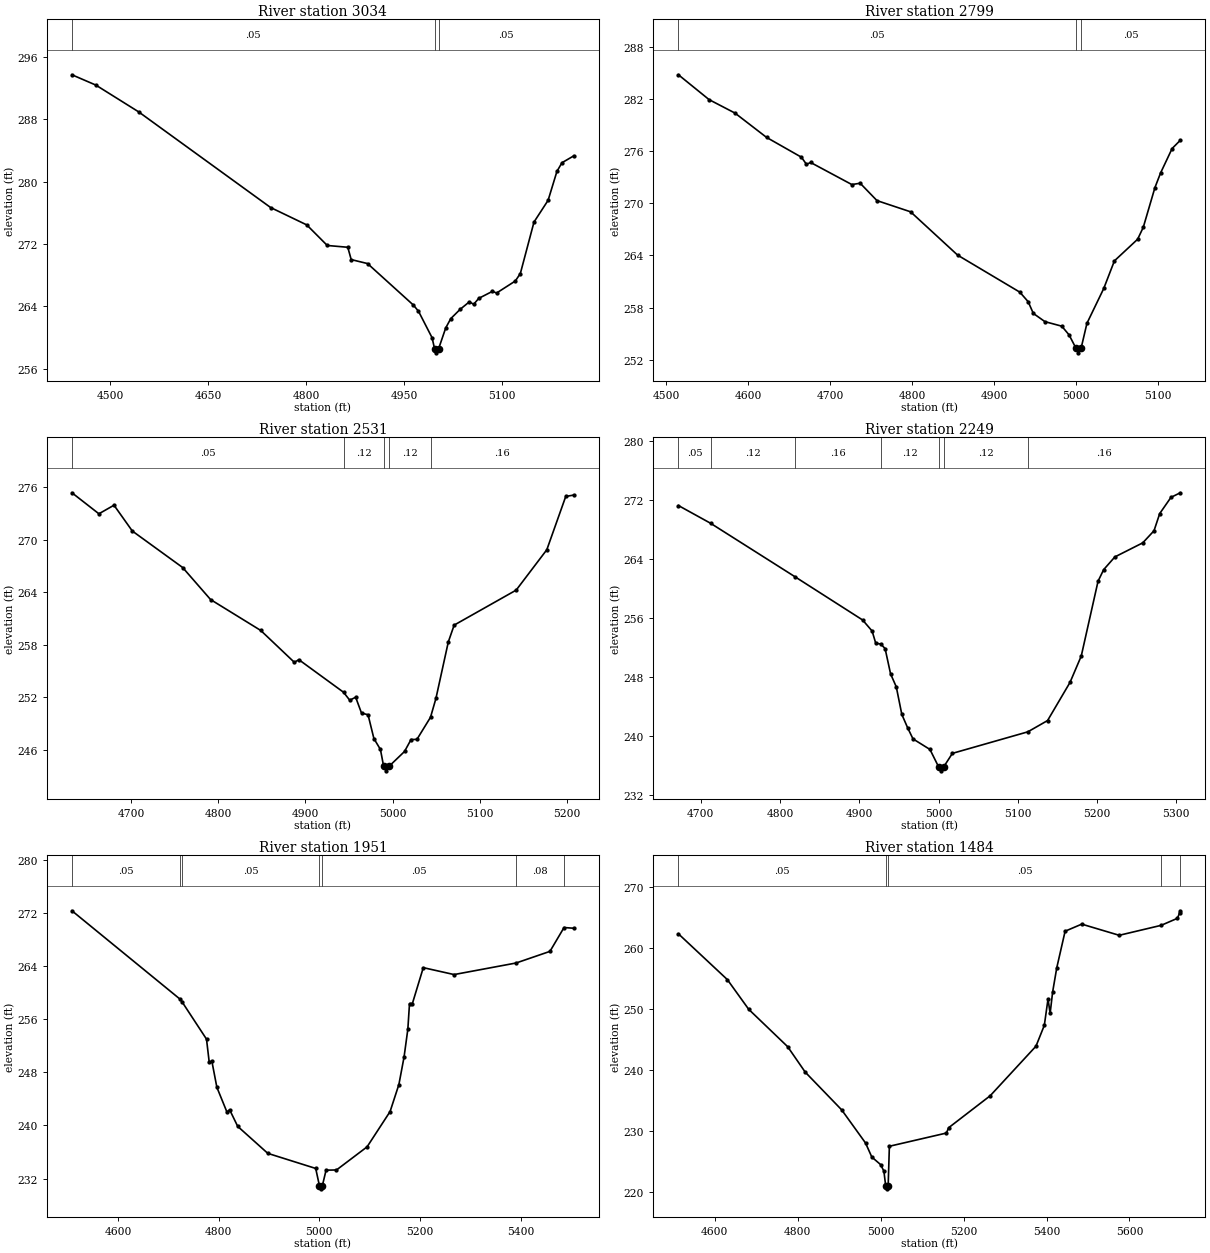
Type RM Length L Ch R = 1 ,3034    ,235,235,235
BEGIN DESCRIPTION:
UNT107 IN ROCK 2.0
END DESCRIPTION:
XS GIS Cut Line= 3
       3643808.4     10143016.17      3644217.22     10142891.18
      3644437.87     10142631.59
#Sta/Elev= 30
  4441.4  293.71  4477.9  292.39  4543.5  288.95  4745.5  276.67  4800.8  274.44
  4832.2   271.8  4863.6  271.57  4868.8  269.99  4893.8  269.48    4964  264.15
  4971.8  263.36  4992.6  259.96  4996.5  258.52  4999.3  258.02  5002.5  258.52
  5013.5  261.22  5021.2  262.41  5035.5   263.6  5049.7  264.57  5056.3  264.25
    5064  265.01  5084.9  265.91  5091.4   265.7    5120  267.24  5127.7   268.2
  5148.6  274.81  5170.2   277.6  5183.7  281.31  5191.4  282.42  5209.6  283.31
#Mann= 3 ,-1 , 0
  4441.4     .05       0  4996.5     .04       0  5002.5     .05       0
Bank Sta=4996.5,5002.5
XS Rating Curve= 0 ,0
Exp/Cntr=0.3,0.1

Type RM Length L Ch R = 1 ,2799    ,268,268,268
BEGIN DESCRIPTION:
Mapping XS 47deff79
END DESCRIPTION:
XS GIS Cut Line= 3
      3644005.63      10143040.7      3644518.87     10142926.77
       3644578.4     10142864.05
#Sta/Elev= 30
  4514.9   284.8  4552.3  281.94  4583.9  280.39  4622.4  277.59  4664.9  275.31
  4671.1  274.49  4676.2   274.7  4726.4  272.16  4736.6  272.31  4757.1  270.31
  4798.1  269.02  4855.5  264.03  4931.3  259.77  4941.5  258.67  4947.8  257.32
    4962  256.37  4982.5  255.85  4991.3  254.86    5000  253.28  5002.7  252.78
    5006  253.28  5013.2  256.18  5033.7  260.19  5046.7  263.37    5075  265.86
  5081.9  267.23  5096.1   271.8    5103  273.49  5117.1  276.31  5127.1  277.26
#Mann= 3 ,-1 , 0
  4514.9     .05       0    5000     .03       0    5006     .05       0
Bank Sta=5000,5006
XS Rating Curve= 0 ,0
Exp/Cntr=0.3,0.1

Type RM Length L Ch R = 1 ,2531    ,282,282,282
BEGIN DESCRIPTION:
Mapping XS b2b08c7b
END DESCRIPTION:
XS GIS Cut Line= 3
      3644256.27      10143295.7      3644561.19     10143196.95
      3644730.19     10143006.28
#Sta/Elev= 30
  4632.3  275.37  4663.2  272.97  4680.5  273.95  4701.5     271  4759.2  266.83
  4791.2  263.17  4848.7  259.64  4887.2     256  4892.4   256.3  4943.6  252.58
  4950.7  251.67  4957.5  252.01  4964.2   250.2  4971.7  250.01  4978.4  247.29
  4985.9  246.04  4989.6   244.1  4992.3   243.6  4995.6   244.1  5013.5  245.81
    5021  247.18  5027.7  247.19  5043.3  249.72  5049.5  251.87  5063.7  258.33
  5070.4  260.25  5141.5  264.25  5176.6  268.86  5198.3  274.95  5207.6  275.11
#Mann= 5 ,-1 , 0
  4632.3     .05       0  4943.6     .12       0  4989.6     .07       0
  4995.6     .12       0  5043.3     .16       0
Bank Sta=4989.6,4995.6
XS Rating Curve= 0 ,0
Exp/Cntr=0.3,0.1

Type RM Length L Ch R = 1 ,2249    ,298,298,298
BEGIN DESCRIPTION:
Mapping XS 1aabe5f5
END DESCRIPTION:
XS GIS Cut Line= 3
      3644403.81     10143519.23      3644638.23      10143433.5
      3644904.06     10143156.81
#Sta/Elev= 30
  4671.8  271.19  4712.3  268.79  4818.9  261.53  4904.2  255.67  4916.2  254.17
  4920.8  252.51  4927.1  252.41  4932.6  251.79  4939.5  248.36  4946.7   246.6
  4953.7  242.86  4960.9  241.08  4967.8  239.54  4989.2  238.11  5000.3  235.71
  5003.1  235.21  5006.3  235.71  5017.5  237.58  5112.7   240.5  5137.6  242.03
  5165.9   247.2  5180.1  250.78  5201.3  260.93  5208.4   262.5  5222.5  264.22
  5257.7  266.13  5271.9  267.77  5279.1   270.1  5293.3   272.3  5305.1  272.92
#Mann= 7 ,-1 , 0
  4671.8     .05       0  4712.3     .12       0  4818.9     .16       0
  4927.1     .12       0  5000.3     .07       0  5006.3     .12       0
  5112.7     .16       0
Bank Sta=5000.3,5006.3
XS Rating Curve= 0 ,0
Exp/Cntr=0.3,0.1

Type RM Length L Ch R = 1 ,1951    ,467,467,467
BEGIN DESCRIPTION:
Mapping XS ac2bec67
END DESCRIPTION:
XS GIS Cut Line= 3
      3644423.37     10143675.47      3645073.34      10143506.2
      3645126.19     10143184.76
#Sta/Elev= 30
  4508.6   272.3  4724.2  258.95    4727  258.64    4776  252.98  4781.4   249.5
  4786.6  249.68  4796.6  245.73  4816.7  241.99  4821.9  242.36    4838  239.85
  4897.8  235.79    4993  233.52  5000.3  230.95    5003  230.45  5006.3  230.95
  5013.6  233.26  5034.3  233.29  5095.1  236.77  5140.8  242.08  5158.3  246.15
  5168.6   250.3  5176.1  254.48  5179.4  258.33  5185.1  258.33  5206.8  263.74
    5268   262.7  5391.2  264.44  5458.5  266.19  5486.5  269.78    5506  269.67
#Mann= 7 ,-1 , 0
  4508.6     .05       0  4724.2     .12       0    4727     .05       0
  5000.3     .03       0  5006.3     .05       0  5391.2     .08       0
  5486.5     .05       0
Bank Sta=5000.3,5006.3
XS Rating Curve= 0 ,0
Exp/Cntr=0.3,0.1

Type RM Length L Ch R = 1 ,1484    ,462,462,462
BEGIN DESCRIPTION:
Mapping XS b2aabbe1
END DESCRIPTION:
XS GIS Cut Line= 3
      3644585.09     10144148.54      3645104.81     10143815.44
       3645152.4     10143224.85
#Sta/Elev= 30
  4512.7  262.33  4630.6  254.83  4682.2  249.95    4776  243.83  4818.3  239.66
  4906.2  233.47  4963.7  228.04  4978.9  225.73  5000.1  224.49    5008  223.42
  5012.3  221.02    5015  220.52  5018.3  221.02  5021.2   227.5  5158.8  229.67
  5163.9  230.53  5264.2  235.78  5374.6  243.91  5394.7  247.33  5403.6  251.64
  5408.7  249.29  5414.7  252.79  5424.7  256.77  5444.8  262.76  5484.9  263.92
  5575.2  262.09  5676.2  263.72  5715.7  264.88  5720.7  265.78  5722.5  266.11
#Mann= 5 ,-1 , 0
  4512.7     .05       0  5012.3     .03       0  5018.3     .05       0
  5676.2     .08       0  5720.7     .05       0
Bank Sta=5012.3,5018.3
XS Rating Curve= 0 ,0
Exp/Cntr=0.3,0.1

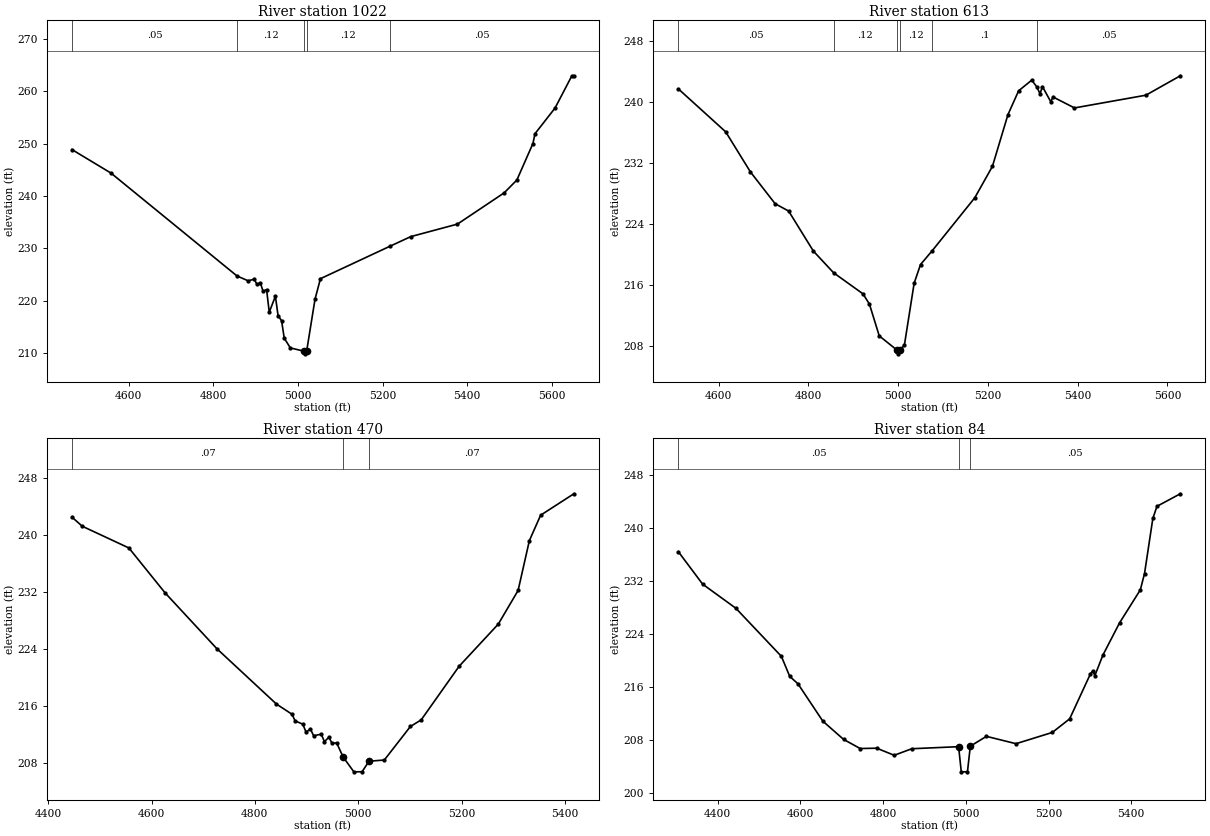
Type RM Length L Ch R = 1 ,1022    ,409,409,409
BEGIN DESCRIPTION:
Mapping XS 5c6e0b20
END DESCRIPTION:
XS GIS Cut Line= 4
      3644854.16     10144279.85       3645185.1     10144065.01
      3645309.88     10143900.08      3645270.82     10143317.37
#Sta/Elev= 30
  4466.3  248.86  4558.6  244.36  4856.1  224.71  4882.3  223.79  4896.9  224.09
  4903.2   223.1  4911.4  223.37  4917.7  221.78    4926   222.1  4932.3  217.79
  4946.8  220.84  4953.1  217.14  4961.4  216.15  4967.7  212.81  4982.2  210.96
  5014.6  210.33  5017.3  209.83  5020.6  210.33  5040.4  220.28  5053.2  224.19
  5216.6  230.36  5266.6  232.23  5376.8  234.62  5487.1  240.59  5517.1  243.04
    5555  250.01    5560   251.9  5607.3   256.8    5647  262.96  5651.7  262.96
#Mann= 5 ,-1 , 0
  4466.3     .05       0  4856.1     .12       0  5014.6     .07       0
  5020.6     .12       0  5216.6     .05       0
Bank Sta=5014.6,5020.6
XS Rating Curve= 0 ,0
Exp/Cntr=0.3,0.1

Type RM Length L Ch R = 1 ,613     ,143,143,143
BEGIN DESCRIPTION:
Mapping XS 1c3b4d1f
END DESCRIPTION:
XS GIS Cut Line= 4
      3645057.02     10144323.27      3645396.69     10144195.21
      3645620.21     10143998.82      3645796.89     10143576.11
#Sta/Elev= 30
  4510.1   241.7  4615.5  236.07  4670.6  230.81  4725.6  226.64  4755.8  225.67
  4810.9  220.42    4856  217.57  4921.6   214.8  4935.9  213.45  4957.7  209.29
  4997.1  207.43  4999.9  206.93  5003.1  207.43  5013.7  208.04  5035.5  216.19
  5049.7  218.65    5076  220.48  5170.7  227.42    5210  231.54  5244.6  238.33
  5268.4  241.46  5297.7  242.86  5309.3  241.94    5316  241.06  5321.5  242.01
  5339.9  240.04  5345.3  240.64  5392.9  239.21    5552  240.88  5628.8  243.43
#Mann= 6 ,-1 , 0
  4510.1     .05       0    4856     .12       0  4997.1     .07       0
  5003.1     .12       0    5076      .1       0  5309.3     .05       0
Bank Sta=4997.1,5003.1
XS Rating Curve= 0 ,0
Exp/Cntr=0.3,0.1

Type RM Length L Ch R = 1 ,470     ,386,386,386
BEGIN DESCRIPTION:
Mapping XS 794ab71b
END DESCRIPTION:
XS GIS Cut Line= 4
      3645032.14     10144401.38      3645427.07     10144377.51
      3645619.13     10144104.07       3645715.7     10143882.72
#Sta/Elev= 30
    4446  242.48    4466   241.2  4556.2  238.15  4626.3  231.84  4726.5     224
  4841.7  216.23  4871.8   214.8  4877.9  213.87  4892.7   213.4  4898.9  212.32
  4907.6   212.7  4913.7  211.78  4928.5     212  4934.6  210.94  4943.3  211.58
  4949.4  210.69  4958.1  210.79    4971  208.77 4991.55  206.71 5007.41  206.72
  5020.9   208.2  5050.5  208.37    5101  213.08  5121.9  214.01  5195.3  221.54
    5271  227.45  5309.4  232.18  5331.2  239.18    5353  242.75  5417.3  245.76
#Mann= 3 , 0 , 0
    4446     .07       0    4971     .05       0  5020.9     .07       0
Bank Sta=4971,5020.9
XS Rating Curve= 0 ,0
Exp/Cntr=0.3,0.1

Type RM Length L Ch R = 1 ,84      ,0,0,0
BEGIN DESCRIPTION:
UNT107 IN ROCK 1.0
END DESCRIPTION:
XS GIS Cut Line= 4
      3645113.62     10144526.31      3645606.25      10144555.6
      3645766.84      10144396.1      3645714.87     10143905.58
#Sta/Elev= 30
  4305.4  236.47    4364  231.58  4444.1  227.95  4554.3  220.68  4574.4  217.66
  4594.4  216.53  4654.5  210.89  4704.6  208.14  4744.7  206.76  4784.7  206.81
    4827  205.74  4869.5  206.73  4982.6  207.04 4989.08  203.24 5004.03  203.25
  5010.9  207.11  5049.8   208.6  5121.4  207.49  5209.1  209.19    5251  211.24
  5301.2  218.03  5306.9  218.48  5311.9  217.77  5331.4  220.87  5371.6  225.73
  5421.9  230.73    5432  233.19  5452.1  241.51  5462.1  243.34  5518.5  245.23
#Mann= 3 , 0 , 0
  4305.4     .05       0  4982.6     .03       0  5010.9     .05       0
Bank Sta=4982.6,5010.9
XS Rating Curve= 0 ,0
Exp/Cntr=0.3,0.1

Chan Stop Cuts=-1
Use User Specified Reach Order=0
Composite Channel Slope=5