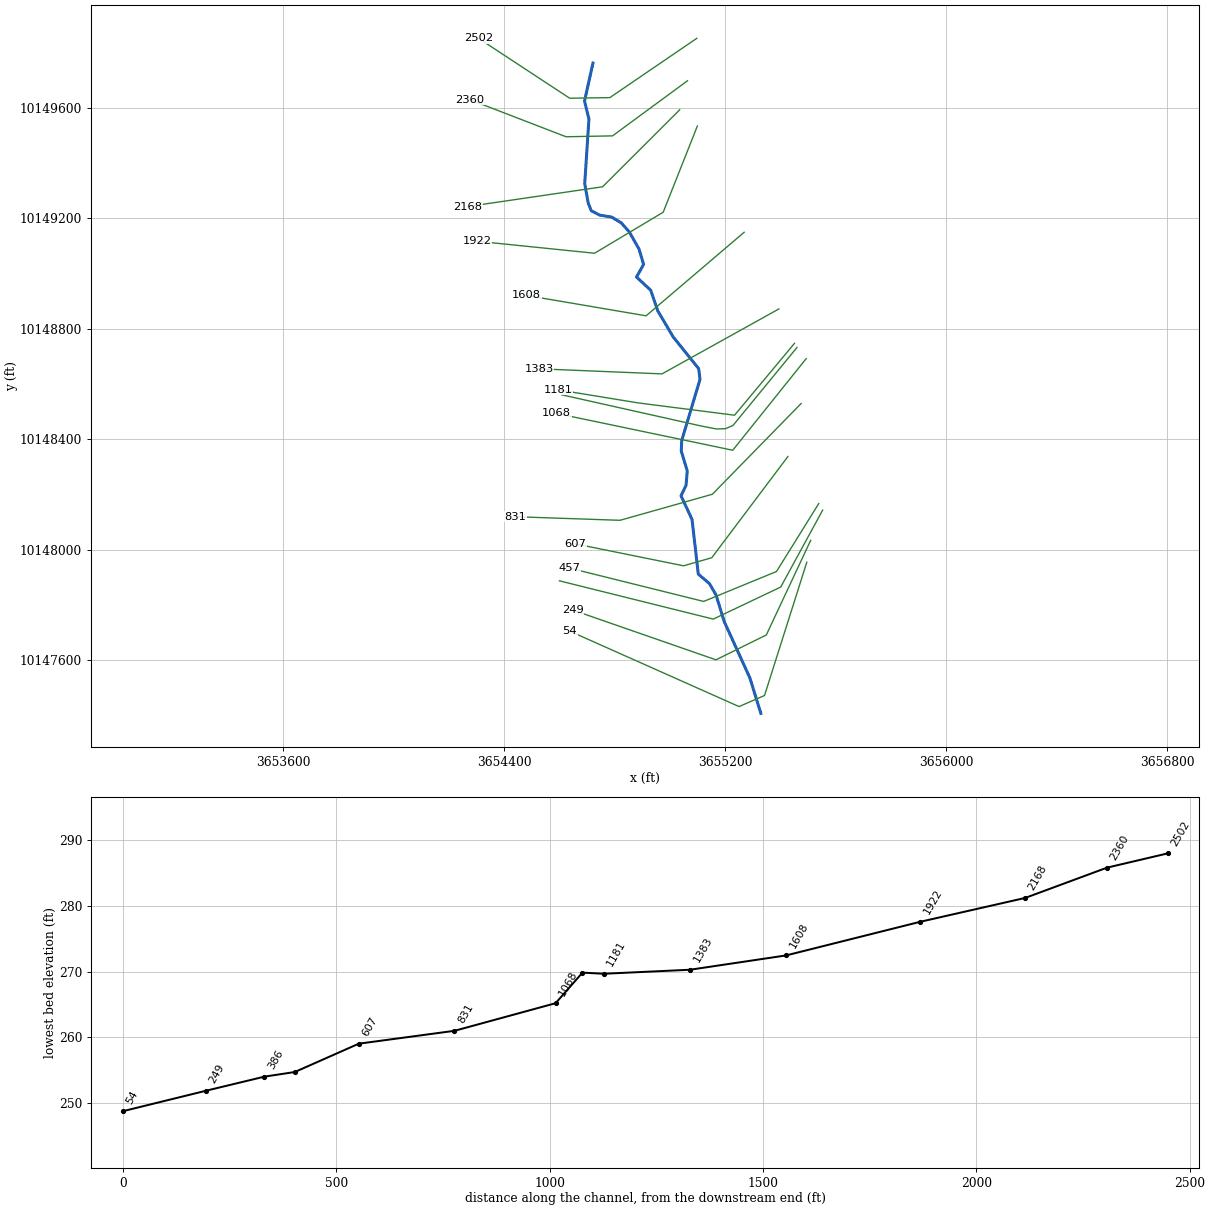
--- UNT108 IN ROCK.prj (project) ---

Proj Title=UNT108 IN ROCK Base Level Engineering
Current Plan=p01
Default Exp/Contr=0.3,0.1
English Units
Geom File=g01
Flow File=f01
Plan File=p01
Y Axis Title=Elevation
X Axis Title(PF)=Main Channel Distance
X Axis Title(XS)=Station
BEGIN DESCRIPTION:
UNT108 IN ROCK
END DESCRIPTION:
DSS Export Rating Curves= 0
DSS Export Rating Curve Sorted= 0
DSS Export Volume Flow Curves= 0
DXF OffsetX= 0
DXF OffsetY= 0
DXF ScaleX= 1
DXF ScaleY= 10

--- UNT108 IN ROCK.p01 (plan) ---

Plan Title=Multiple Run
Short Identifier=Multiple
Geom File=g01
Flow File=f01
Subcritical Flow
K Sum by GR= 0
Std Step Tol= 0.01
Critical Tol= 0.01
Num of Std Step Trials= 20
Max Error Tol= 0.3
Flow Tol Ratio= 0.001
Split Flow NTrial= 30
Split Flow Tol= 0.02
Split Flow Ratio= 0.02
Log Output Level= 0
Friction Slope Method= 1
Unsteady Friction Slope Method= 2
Unsteady Bridges Friction Slope Method= 1
Parabolic Critical Depth
Global Vel Dist=  1 , 1 , 1
Global Log Level= 0
CheckData=True
Encroach Param= -1, 0, 0, 0
BEGIN DESCRIPTION:
Multiple Run
END DESCRIPTION:

--- UNT108 IN ROCK.f01 (steady flow) ---

Flow Title=Multiple
Number of Profiles=7
Profile Names=10-year,25-year,50-year,1pct_min,100-year,1pct_plu,500-year
River Rch & RM= UNT108 IN ROCK,Reach-1,2502
     153     189     216     183     248     335     323
Boundary for River Rch & Prof#=UNT108 IN ROCK,Reach-1,1
Up Type=0
Dn Type=3
Dn Slope=0.005
Boundary for River Rch & Prof#=UNT108 IN ROCK,Reach-1,2
Up Type=0
Dn Type=3
Dn Slope=0.005
Boundary for River Rch & Prof#=UNT108 IN ROCK,Reach-1,3
Up Type=0
Dn Type=3
Dn Slope=0.005
Boundary for River Rch & Prof#=UNT108 IN ROCK,Reach-1,4
Up Type=0
Dn Type=3
Dn Slope=0.005
Boundary for River Rch & Prof#=UNT108 IN ROCK,Reach-1,5
Up Type=0
Dn Type=3
Dn Slope=0.005
Boundary for River Rch & Prof#=UNT108 IN ROCK,Reach-1,6
Up Type=0
Dn Type=3
Dn Slope=0.005
Boundary for River Rch & Prof#=UNT108 IN ROCK,Reach-1,7
Up Type=0
Dn Type=3
Dn Slope=0.005

--- UNT108 IN ROCK.g01 (geometry) ---

Geom Title=Existing Conditions
Program Version=4.10

River Reach=UNT108 IN ROCK  ,Reach-1
Reach XY= 30
      3654721.62     10149763.15      3654691.01     10149625.35
      3654706.98     10149560.08       3654691.7     10149326.05
       3654704.2      10149256.6      3654715.31     10149228.13
      3654745.87     10149212.16      3654788.92     10149205.22
      3654823.65     10149184.38      3654852.81     10149151.74
      3654888.23     10149089.24       3654904.9     10149033.69
       3654879.2     10148987.85      3654930.59     10148939.94
      3654956.28     10148864.94      3655012.53      10148769.8
       3655104.2     10148655.91      3655109.06     10148617.02
      3655042.92     10148395.49      3655041.18      10148357.3
      3655062.88     10148285.25      3655058.54     10148233.17
      3655040.31     10148194.97      3655080.24     10148109.03
      3655102.81     10147911.12      3655142.74     10147877.26
      3655167.05      10147835.6      3655196.56     10147739.24
      3655289.44     10147535.25      3655329.26     10147406.43

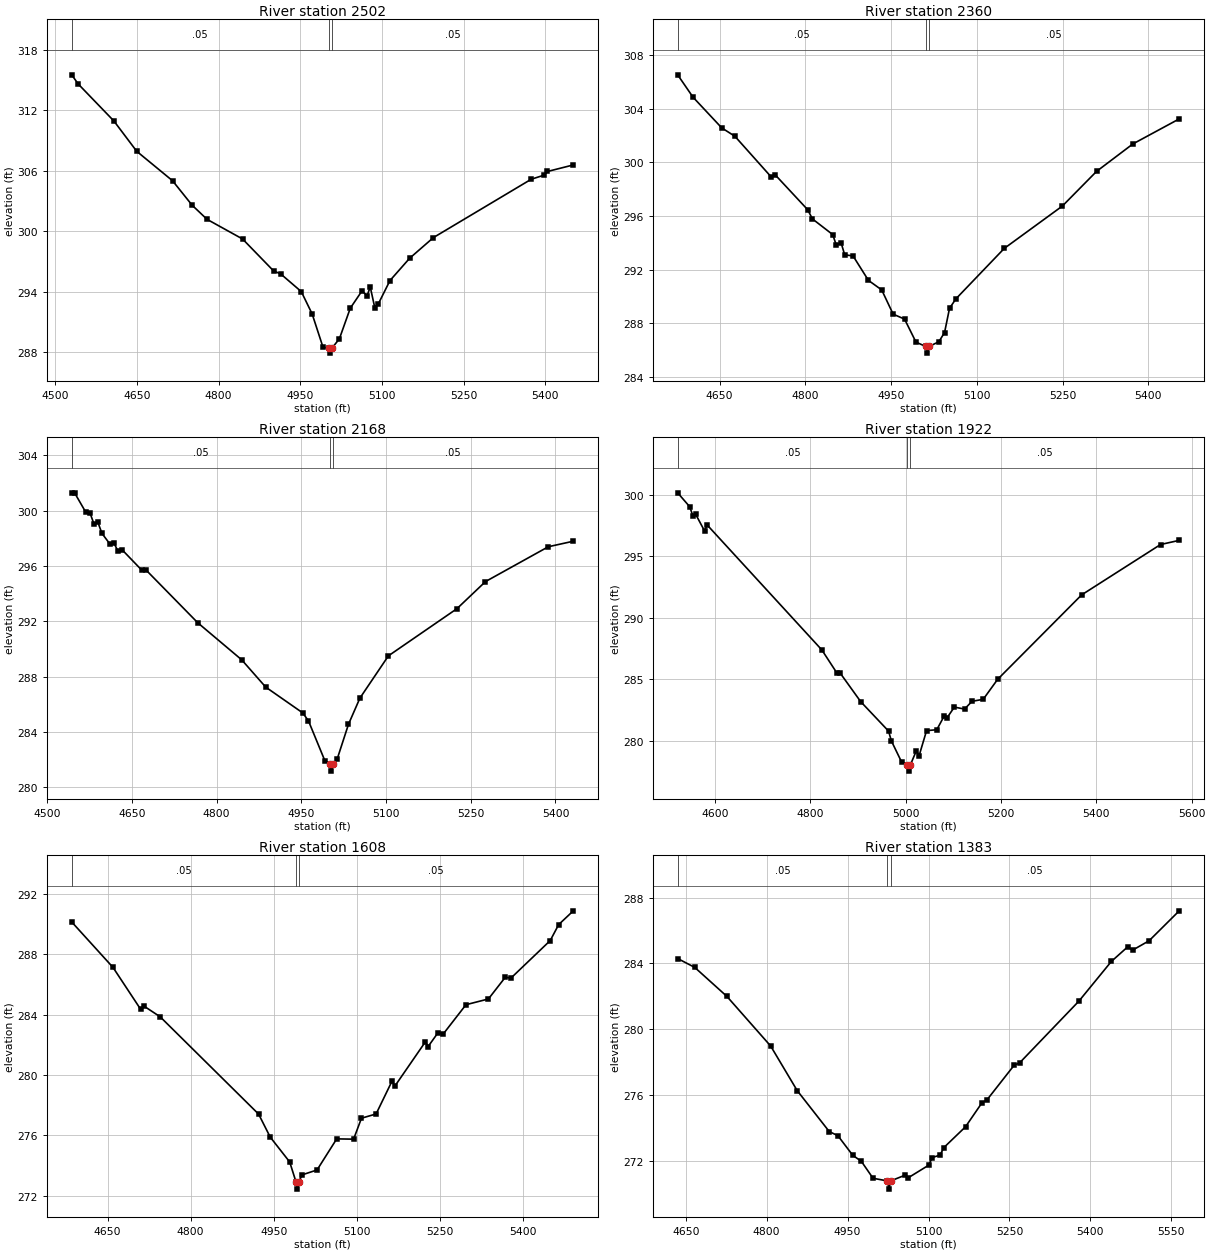
Type RM Length L Ch R = 1 ,2502    ,142,142,142
BEGIN DESCRIPTION:
UNT108 IN ROCK 3.0
END DESCRIPTION:
XS GIS Cut Line= 4
      3655097.35     10149852.88      3654782.65     10149638.02
      3654637.25     10149635.85       3654307.4     10149852.86
#Sta/Elev= 30
  4530.2   315.5  4541.9   314.6  4607.7  310.92  4649.6  307.92  4715.4     305
  4751.3  302.58  4778.7  301.18    4844  299.23  4900.9  296.07    4914  295.77
  4951.8  294.02  4971.8   291.8  4991.8  288.49  5002.2  288.42  5004.9  287.92
  5008.2  288.42  5021.8  289.34  5041.8  292.37  5063.5   294.1  5072.6   293.6
  5078.5  294.48  5086.8  292.43  5093.6  292.83  5114.7  295.11  5150.8  297.32
  5194.5  299.37  5374.1  305.15  5397.9  305.56  5403.9  305.92  5451.5  306.57
#Mann= 3 ,-1 , 0
  4530.2     .05       0  5002.2     .03       0  5008.2     .05       0
Bank Sta=5002.2,5008.2
XS Rating Curve= 0 ,0
Exp/Cntr=0.3,0.1

Type RM Length L Ch R = 1 ,2360    ,192,192,192
BEGIN DESCRIPTION:
Mapping XS 02e28e85
END DESCRIPTION:
XS GIS Cut Line= 4
      3655063.67     10149699.04      3654792.42      10149499.4
      3654624.23     10149496.15      3654276.49     10149630.48
#Sta/Elev= 30
  4576.5  306.54  4603.4  304.87  4653.6  302.58  4676.7  301.95  4739.9  298.93
  4747.7  299.05    4804  296.47  4812.4  295.78  4847.9  294.61  4854.1  293.82
  4862.6  293.99  4868.8   293.1  4883.4  293.02  4910.4  291.19  4933.6  290.48
  4953.6  288.67  4973.6   288.3  4993.6  286.58  5010.6  286.26  5013.4  285.76
  5016.6  286.26  5033.6  286.61  5043.6   287.3  5052.3  289.11  5063.6  289.82
  5148.1  293.58  5249.7  296.74  5309.6  299.33  5373.2  301.38  5454.3  303.25
#Mann= 3 ,-1 , 0
  4576.5     .05       0  5010.6     .03       0  5016.6     .05       0
Bank Sta=5010.6,5016.6
XS Rating Curve= 0 ,0
Exp/Cntr=0.3,0.1

Type RM Length L Ch R = 1 ,2168    ,246,246,246
BEGIN DESCRIPTION:
Mapping XS 5e9507fc
END DESCRIPTION:
XS GIS Cut Line= 3
      3655035.46     10149593.79      3654756.61     10149314.94
      3654268.29     10149243.32
#Sta/Elev= 30
  4543.7  301.29  4548.7  301.29  4568.8  299.87  4575.9  299.85  4582.9  299.05
    4590  299.16  4597.1  298.36  4611.2  297.59  4618.3  297.67  4625.4  297.08
  4632.4  297.19  4667.8  295.69  4674.9  295.72  4766.8  291.89  4844.6  289.21
    4887  287.24  4952.7  285.37  4962.8  284.79  4991.7  281.92  5000.2  281.66
    5003  281.16  5006.2  281.66  5013.4  282.01  5033.6  284.55  5053.8  286.44
  5104.3   289.5  5225.6  292.91  5276.1  294.87  5387.3  297.39  5431.6  297.79
#Mann= 3 ,-1 , 0
  4543.7     .05       0  5000.2    .035       0  5006.2     .05       0
Bank Sta=5000.2,5006.2
XS Rating Curve= 0 ,0
Exp/Cntr=0.3,0.1

Type RM Length L Ch R = 1 ,1922    ,314,314,314
BEGIN DESCRIPTION:
Mapping XS 2cd24bf9
END DESCRIPTION:
XS GIS Cut Line= 4
      3655099.49     10149535.19       3654975.8     10149222.71
      3654727.32     10149074.05      3654303.06     10149117.46
#Sta/Elev= 30
  4521.9  300.14  4547.2  299.01  4554.1  298.24  4559.5  298.41  4578.4  297.04
  4583.8  297.53  4824.4  287.38  4856.2  285.49    4863  285.49  4905.9  283.18
  4964.3  280.79  4970.1     280  4991.5  278.29    5004  278.04  5006.8  277.54
    5010  278.04  5022.6   279.2  5028.4   278.8    5044  280.83  5065.4   280.9
    5081  282.02  5086.8  281.86  5102.3  282.74  5123.7  282.58  5139.3  283.21
  5162.8  283.37    5193  284.99  5369.2  291.85  5534.7  295.94    5574  296.28
#Mann= 3 ,-1 , 0
  4521.9     .05       0    5004    .035       0    5010     .05       0
Bank Sta=5004,5010
XS Rating Curve= 0 ,0
Exp/Cntr=0.3,0.1

Type RM Length L Ch R = 1 ,1608    ,225,225,225
BEGIN DESCRIPTION:
Mapping XS b7839e20
END DESCRIPTION:
XS GIS Cut Line= 3
      3655268.78     10149150.02      3654913.95     10148847.27
      3654481.02     10148921.06
#Sta/Elev= 30
  4585.3  290.14  4659.8  287.13  4709.8  284.35  4716.4  284.55  4744.9  283.86
  4922.7  277.41  4943.6  275.89  4978.8  274.24    4990  272.94  4992.8  272.44
    4996  272.94  5000.7  273.38  5028.2  273.71  5063.7  275.77  5094.2  275.75
  5108.4  277.14  5134.8  277.42  5163.6   279.6  5168.6  279.26  5223.8   282.2
  5228.8  281.89  5246.3  282.79  5256.5  282.74  5297.1  284.66  5337.6  285.04
  5368.1  286.48  5378.2  286.42  5449.2  288.91  5464.5  289.97  5490.9  290.88
#Mann= 3 ,-1 , 0
  4585.3     .05       0    4990     .03       0    4996     .05       0
Bank Sta=4990,4996
XS Rating Curve= 0 ,0
Exp/Cntr=0.3,0.1

Type RM Length L Ch R = 1 ,1383    ,202,202,202
BEGIN DESCRIPTION:
Mapping XS 4aa0ac92
END DESCRIPTION:
XS GIS Cut Line= 3
       3655394.6     10148872.21      3654971.46     10148636.77
      3654526.27     10148655.19
#Sta/Elev= 30
    4635  284.29  4666.7  283.75  4726.2  281.99  4807.4  278.97  4856.6  276.26
    4916  273.77    4932  273.52  4959.5  272.33  4975.5  271.96  4997.2  270.93
  5023.9  270.77  5026.7  270.27  5029.9  270.77  5056.7  271.12  5062.4  270.96
  5100.1  271.72    5107  272.19  5121.4  272.34  5128.6   272.8  5168.6  274.06
  5198.7   275.5  5208.7  275.71  5258.7   277.8  5268.7  277.94  5378.8   281.7
  5438.9  284.11  5468.9  284.99  5478.9  284.81  5508.9  285.37  5564.8  287.19
#Mann= 3 ,-1 , 0
    4635     .05       0  5023.9     .03       0  5029.9     .05       0
Bank Sta=5023.9,5029.9
XS Rating Curve= 0 ,0
Exp/Cntr=0.3,0.1

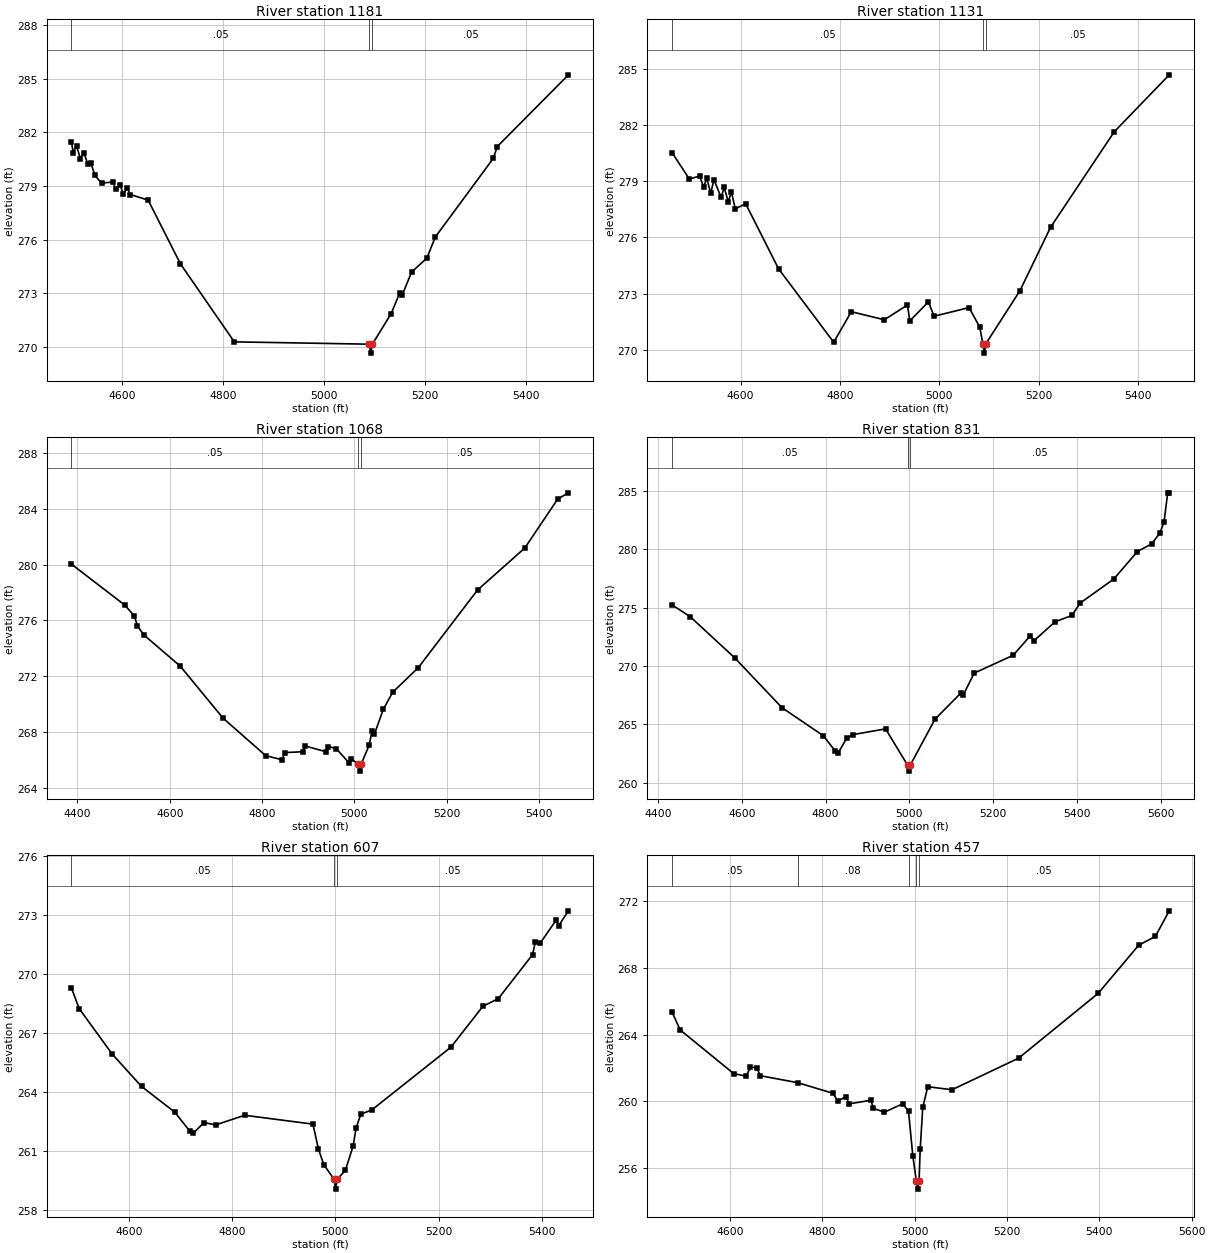
Type RM Length L Ch R = 1 ,1181    ,50,50,50
BEGIN DESCRIPTION:
Mapping XS cce807d9
END DESCRIPTION:
XS GIS Cut Line= 4
      3655451.08     10148747.48      3655234.04     10148487.03
      3654885.74     10148531.52      3654595.46       10148579.
#Sta/Elev= 30
  4499.1  281.47  4502.8  280.87  4509.3  281.23  4517.1  280.52  4523.6  280.87
  4531.4  280.24  4537.9  280.27  4545.7  279.59  4558.8  279.16  4580.9  279.22
  4587.4  278.81  4595.2  279.08  4601.7  278.56  4609.5  278.87    4616  278.52
  4651.1  278.21    4715  274.65  4821.7  270.29  5089.1  270.16  5091.9  269.66
  5095.1  270.16  5132.4  271.87  5149.2  273.02  5154.2   272.9  5172.8  274.19
  5203.1  274.97  5219.6  276.14  5334.8  280.55  5342.4   281.2  5483.4  285.21
#Mann= 3 ,-1 , 0
  4499.1     .05       0  5089.1     .03       0  5095.1     .05       0
Bank Sta=5089.1,5095.1
XS Rating Curve= 0 ,0
Exp/Cntr=0.3,0.1

Type RM Length L Ch R = 1 ,1131    ,63,63,63
BEGIN DESCRIPTION:
Mapping XS c5105399
END DESCRIPTION:
XS GIS Cut Line= 6
      3655459.77     10148732.29      3655228.62     10148450.14
      3655201.49      10148438.2      3655168.94     10148437.12
      3655117.94     10148446.88      3654609.02     10148560.82
#Sta/Elev= 30
  4462.2  280.52  4496.7  279.12  4517.5  279.28  4525.4  278.68  4531.8  279.17
  4539.7  278.35  4546.2  279.09  4560.5  278.15    4567  278.67  4574.9  277.91
  4581.4  278.43  4589.2  277.53  4610.1   277.8  4676.3  274.33  4787.3  270.41
  4822.7  272.04  4889.2  271.61  4935.8   272.4  4940.4  271.55  4977.8  272.56
  4989.5   271.8  5059.8  272.26  5081.3  271.21  5087.5  270.33  5090.3  269.83
  5093.5  270.33  5162.3  273.17  5223.7  276.54  5351.9  281.64  5462.6  284.68
#Mann= 3 ,-1 , 0
  4462.2     .05       0  5087.5     .03       0  5093.5     .05       0
Bank Sta=5087.5,5093.5
XS Rating Curve= 0 ,0
Exp/Cntr=0.3,0.1

Type RM Length L Ch R = 1 ,1068    ,237,237,237
BEGIN DESCRIPTION:
Mapping XS 4edec72b
END DESCRIPTION:
XS GIS Cut Line= 3
      3655493.37      10148692.1      3655227.53     10148360.08
      3654589.48     10148493.55
#Sta/Elev= 30
  4386.9  280.03  4502.6  277.09  4523.5  276.31  4529.9   275.6  4544.3  274.94
  4622.7  272.72  4715.5  268.99    4808   266.3  4843.8     266  4848.9  266.52
  4888.7  266.58  4893.8  266.99  4938.6  266.58  4943.7  266.95  4960.8  266.81
  4988.6  265.78  4993.7  266.06  5008.9  265.69  5011.6  265.19  5014.9  265.69
  5032.3  267.06  5038.5  268.08  5043.6  267.84    5063  269.63  5083.4  270.85
  5138.5   272.6  5267.3  278.18  5369.5  281.18    5441   284.7  5464.1  285.14
#Mann= 3 ,-1 , 0
  4386.9     .05       0  5008.9     .03       0  5014.9     .05       0
Bank Sta=5008.9,5014.9
XS Rating Curve= 0 ,0
Exp/Cntr=0.3,0.1

Type RM Length L Ch R = 1 ,831     ,224,224,224
BEGIN DESCRIPTION:
Mapping XS 34ce0996
END DESCRIPTION:
XS GIS Cut Line= 4
      3655474.94     10148529.36      3655153.75     10148200.57
      3654819.55     10148106.17      3654439.79     10148119.19
#Sta/Elev= 30
  4433.5  275.24  4476.3  274.24  4582.5  270.72  4695.6  266.44  4794.5  264.03
  4822.8  262.72  4829.9  262.56    4851  263.87  4865.2  264.13    4943  264.62
  4995.8   261.5  4998.5     261  5001.8   261.5  5061.1  265.45  5123.3  267.71
  5128.5  267.52  5154.6   269.4  5247.9  270.93  5287.9  272.57  5297.9  272.19
  5347.9   273.8  5387.9  274.34    5408  275.41    5488  277.46  5544.5  279.82
  5578.1  280.47  5598.1   281.4  5608.1  282.37  5616.7  284.85  5620.4  284.85
#Mann= 3 ,-1 , 0
  4433.5     .05       0  4995.8     .03       0  5001.8     .05       0
Bank Sta=4995.8,5001.8
XS Rating Curve= 0 ,0
Exp/Cntr=0.3,0.1

Type RM Length L Ch R = 1 ,607     ,150,150,150
BEGIN DESCRIPTION:
Mapping XS c7973a5b
END DESCRIPTION:
XS GIS Cut Line= 4
      3655427.19     10148337.29      3655151.58     10147970.54
      3655049.58     10147941.24      3654658.92     10148020.46
#Sta/Elev= 30
  4488.3   269.3  4503.4  268.24  4567.9  265.91  4624.2  264.28  4688.7  262.97
  4717.9     262  4724.1  261.89  4745.5  262.44  4767.9  262.32  4824.1  262.81
  4956.5  262.36  4967.3  261.08  4977.7  260.29  4997.6  259.55  5000.3  259.05
  5003.6  259.55  5019.4  260.01  5034.3  261.23  5040.2  262.16  5049.3  262.86
    5071  263.09  5224.1  266.28    5286  268.36  5315.9  268.75  5382.3  270.99
  5387.4  271.61  5397.5  271.59  5427.8  272.74  5432.9  272.46  5451.8  273.22
#Mann= 3 ,-1 , 0
  4488.3     .05       0  4997.6     .03       0  5003.6     .05       0
Bank Sta=4997.6,5003.6
XS Rating Curve= 0 ,0
Exp/Cntr=0.3,0.1

Type RM Length L Ch R = 1 ,457     ,71,71,71
BEGIN DESCRIPTION:
Mapping XS b8d2bf3b
END DESCRIPTION:
XS GIS Cut Line= 4
      3655538.94     10148166.93      3655385.95     10147920.63
      3655122.28     10147812.12       3654635.5     10147933.27
#Sta/Elev= 30
  4474.7  265.33    4492  264.28  4607.7  261.67  4634.8  261.51  4644.3  262.05
  4657.5  262.03  4665.5  261.54  4746.9  261.12  4822.6  260.49  4833.7  260.03
  4851.9  260.29  4857.3  259.85  4905.2  260.07  4910.6  259.58  4934.6  259.36
  4974.3  259.86  4986.6  259.41  4995.9  256.76  5003.5  255.25  5006.2  254.75
  5009.5  255.25  5011.9  257.13  5017.5  259.64  5028.3  260.88  5080.9   260.7
  5225.1  262.59  5397.5  266.47  5485.2  269.35  5521.4  269.88  5551.4  271.41
#Mann= 5 ,-1 , 0
  4474.7     .05       0  4746.9     .08       0  4986.6     .05       0
  5003.5     .03       0  5009.5     .05       0
Bank Sta=5003.5,5009.5
XS Rating Curve= 0 ,0
Exp/Cntr=0.3,0.1

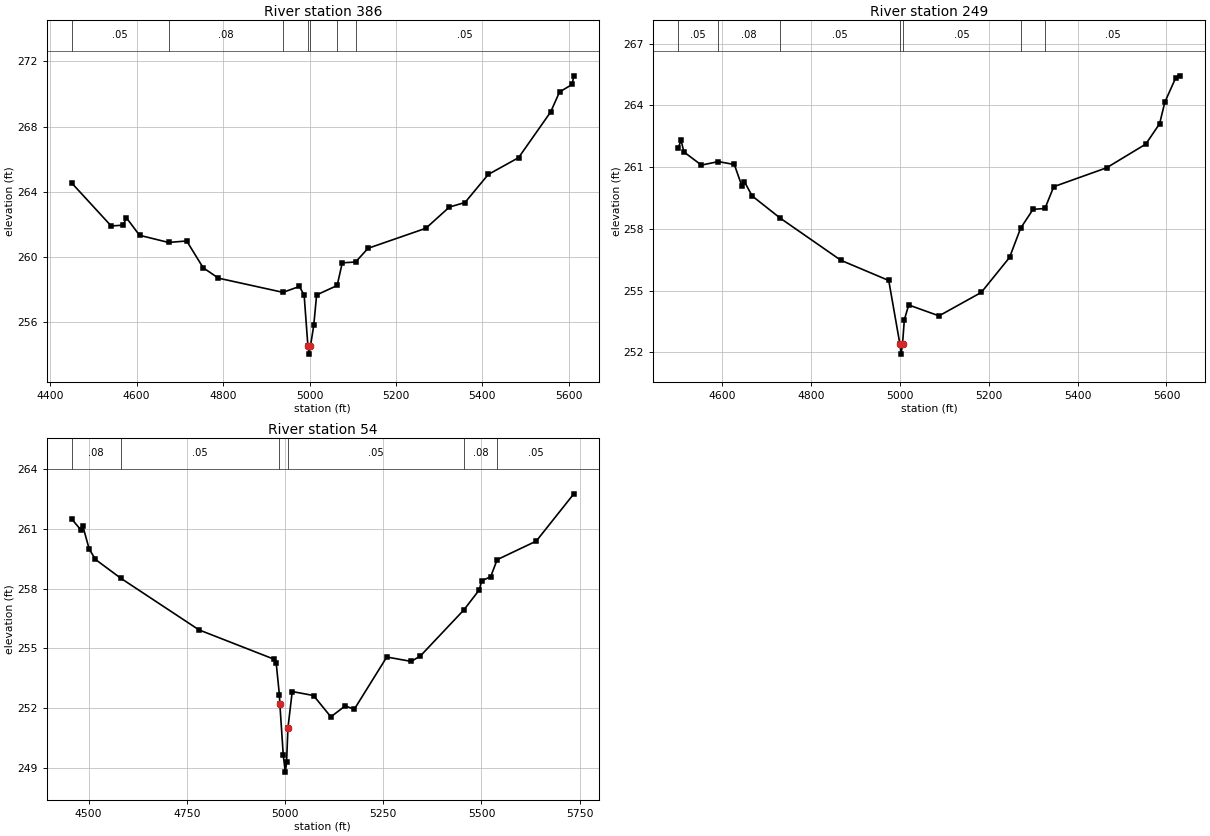
Type RM Length L Ch R = 1 ,386     ,137,137,137
BEGIN DESCRIPTION:
Mapping XS b6f5fce6
END DESCRIPTION:
XS GIS Cut Line= 4
      3655553.03     10148143.03      3655401.14      10147864.2
        3655157.      10147748.1      3654599.97     10147886.82
#Sta/Elev= 30
  4449.6  264.55  4541.1  261.91  4568.6  261.96  4576.4  262.41  4606.6  261.34
  4673.7   260.9  4715.8  260.99  4753.8  259.35  4789.2  258.71  4938.5  257.84
  4976.5   258.2  4987.5  257.67  4996.2  254.55    4999  254.05  5002.2  254.55
  5009.7  255.81  5016.4  257.68  5063.9  258.26  5075.7  259.65  5106.5   259.7
  5135.3  260.54  5269.2  261.77  5323.5  263.07  5359.7  263.35  5413.5  265.07
  5483.6   266.1  5557.8   268.9  5578.4  270.13  5607.5  270.59  5611.5  271.12
#Mann= 7 ,-1 , 0
  4449.6     .05       0  4673.7     .08       0  4938.5     .05       0
  4996.2     .03       0  5002.2     .05       0  5063.9     .08       0
  5106.5     .05       0
Bank Sta=4996.2,5002.2
XS Rating Curve= 0 ,0
Exp/Cntr=0.3,0.1

Type RM Length L Ch R = 1 ,249     ,195,195,195
BEGIN DESCRIPTION:
Mapping XS 6e25e19e
END DESCRIPTION:
XS GIS Cut Line= 4
      3655509.63     10148033.44      3655349.06     10147690.59
      3655166.77     10147600.53      3654649.23     10147780.64
#Sta/Elev= 30
  4501.3  261.93    4508   262.3  4514.3  261.74  4553.7   261.1  4591.7  261.27
  4627.7  261.13    4645  260.07  4650.5  260.29  4667.9   259.6  4731.1  258.52
  4867.7  256.47  4975.2  255.49  5000.2  252.41    5003  251.91  5006.2  252.41
  5010.3  253.58  5020.1   254.3  5088.3  253.77  5183.4  254.91    5247  256.61
  5271.9  258.03  5299.9  258.95  5326.7  258.99  5346.4  260.05  5465.5  260.97
  5553.5  262.12  5584.6  263.11  5596.4  264.16    5621  265.35  5631.2  265.44
#Mann= 7 ,-1 , 0
  4501.3     .05       0  4591.7     .08       0  4731.1     .05       0
  5000.2     .03       0  5006.2     .05       0  5271.9     .08       0
  5326.7     .05       0
Bank Sta=5000.2,5006.2
XS Rating Curve= 0 ,0
Exp/Cntr=0.3,0.1

Type RM Length L Ch R = 1 ,54      ,0,0,0
BEGIN DESCRIPTION:
UNT108 IN ROCK 1.0
END DESCRIPTION:
XS GIS Cut Line= 4
      3655495.54     10147954.08      3655342.55     10147471.23
      3655250.32     10147431.08      3654637.24     10147704.52
#Sta/Elev= 30
  4456.7  261.49  4479.8  260.95  4485.1  261.14  4501.2  259.99  4517.3  259.46
  4581.7  258.52  4780.9  255.93  4971.9  254.46  4977.4  254.27  4985.5  252.68
 4986.79  252.19  4995.4  249.65  5000.6   248.8  5003.8   249.3  5007.3  251.02
  5018.2  252.84  5072.4  252.64  5116.6  251.57    5153  252.12  5176.2  251.95
  5258.9  254.57  5321.1  254.35  5344.3  254.62  5455.1  256.93  5494.6  257.94
  5500.1  258.39  5523.3  258.59  5539.9  259.45  5639.4  260.38  5735.1  262.75
#Mann= 6 ,-1 , 0
  4456.7     .08       0  4581.7     .05       0  4985.5     .03       0
  5007.3     .05       0  5455.1     .08       0  5539.9     .05       0
Bank Sta=4986.79,5007.3
XS Rating Curve= 0 ,0
Exp/Cntr=0.3,0.1

Chan Stop Cuts=-1
Use User Specified Reach Order=0
Composite Channel Slope=5