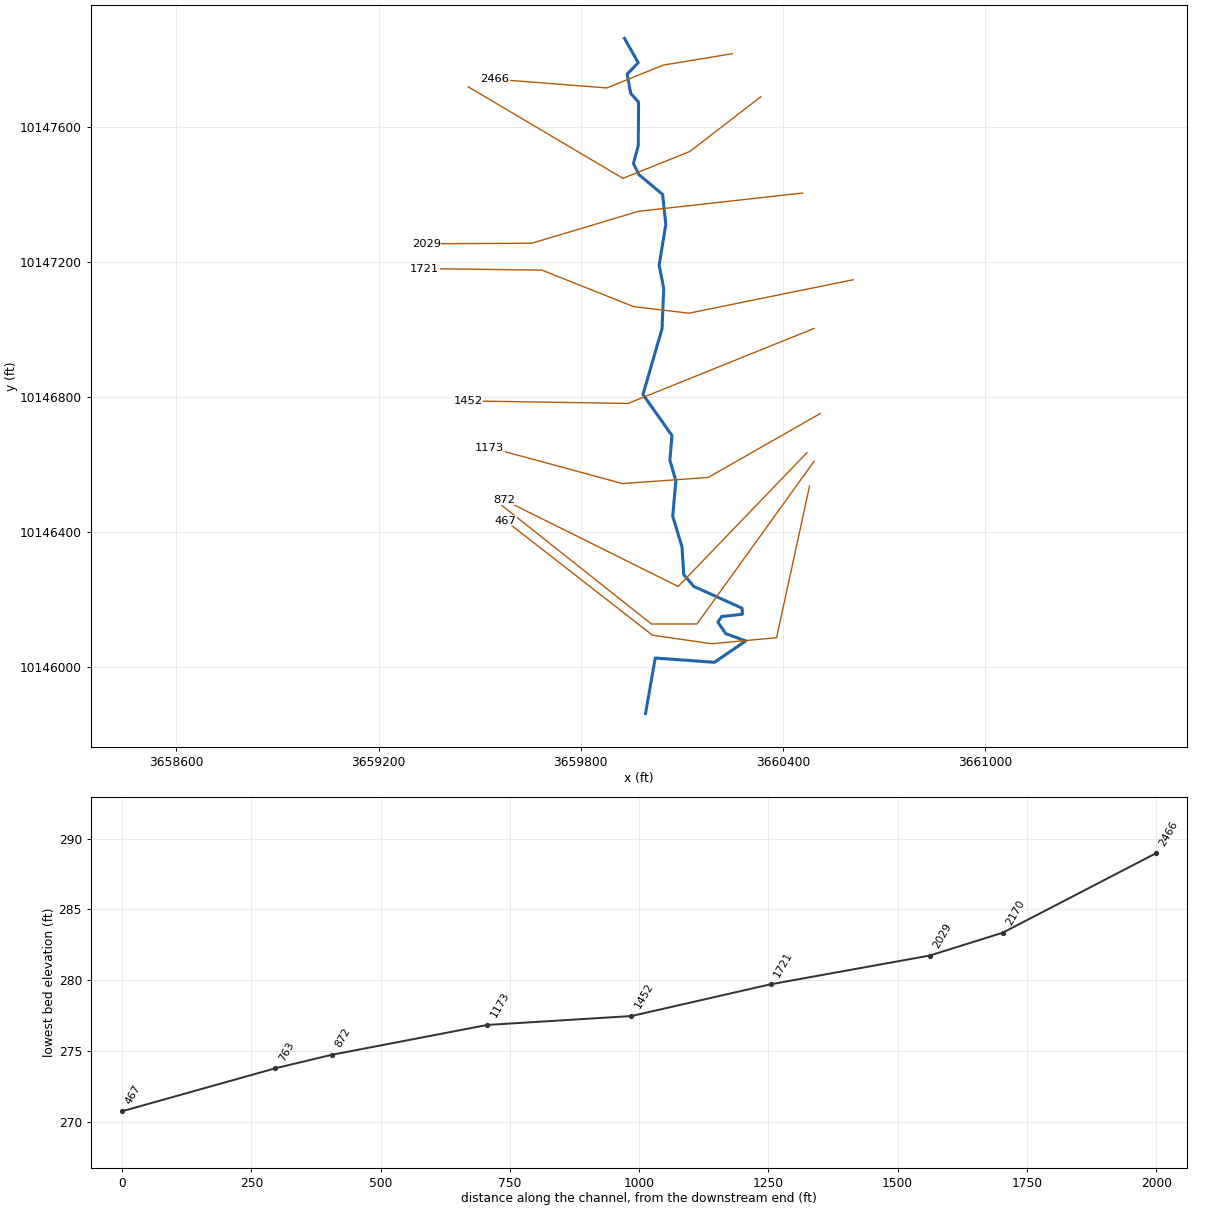
--- UNT109 IN ROCK.prj (project) ---

Proj Title=UNT109 IN ROCK Base Level Engineering
Current Plan=p01
Default Exp/Contr=0.3,0.1
English Units
Geom File=g01
Flow File=f01
Plan File=p01
Y Axis Title=Elevation
X Axis Title(PF)=Main Channel Distance
X Axis Title(XS)=Station
BEGIN DESCRIPTION:
UNT109 IN ROCK
END DESCRIPTION:
DSS Export Rating Curves= 0
DSS Export Rating Curve Sorted= 0
DSS Export Volume Flow Curves= 0
DXF OffsetX= 0
DXF OffsetY= 0
DXF ScaleX= 1
DXF ScaleY= 10

--- UNT109 IN ROCK.p01 (plan) ---

Plan Title=Multiple Run
Short Identifier=Multiple
Geom File=g01
Flow File=f01
Subcritical Flow
K Sum by GR= 0
Std Step Tol= 0.01
Critical Tol= 0.01
Num of Std Step Trials= 20
Max Error Tol= 0.3
Flow Tol Ratio= 0.001
Split Flow NTrial= 30
Split Flow Tol= 0.02
Split Flow Ratio= 0.02
Log Output Level= 0
Friction Slope Method= 1
Unsteady Friction Slope Method= 2
Unsteady Bridges Friction Slope Method= 1
Parabolic Critical Depth
Global Vel Dist=  1 , 1 , 1
Global Log Level= 0
CheckData=True
Encroach Param= -1, 0, 0, 0
BEGIN DESCRIPTION:
Multiple Run
END DESCRIPTION:

--- UNT109 IN ROCK.f01 (steady flow) ---

Flow Title=Multiple
Number of Profiles=7
Profile Names=10-year,25-year,50-year,1pct_min,100-year,1pct_plu,500-year
River Rch & RM= UNT109 IN ROCK,Reach-1,2466
     502     670     806     712     963    1303    1375
Boundary for River Rch & Prof#=UNT109 IN ROCK,Reach-1,1
Up Type=0
Dn Type=3
Dn Slope=0.005
Boundary for River Rch & Prof#=UNT109 IN ROCK,Reach-1,2
Up Type=0
Dn Type=3
Dn Slope=0.005
Boundary for River Rch & Prof#=UNT109 IN ROCK,Reach-1,3
Up Type=0
Dn Type=3
Dn Slope=0.005
Boundary for River Rch & Prof#=UNT109 IN ROCK,Reach-1,4
Up Type=0
Dn Type=3
Dn Slope=0.005
Boundary for River Rch & Prof#=UNT109 IN ROCK,Reach-1,5
Up Type=0
Dn Type=3
Dn Slope=0.005
Boundary for River Rch & Prof#=UNT109 IN ROCK,Reach-1,6
Up Type=0
Dn Type=3
Dn Slope=0.005
Boundary for River Rch & Prof#=UNT109 IN ROCK,Reach-1,7
Up Type=0
Dn Type=3
Dn Slope=0.005

--- UNT109 IN ROCK.g01 (geometry) ---

Geom Title=Existing Conditions
Program Version=4.10

River Reach=UNT109 IN ROCK  ,Reach-1
Reach XY= 30
      3659929.41     10147863.89      3659970.45     10147791.63
      3659937.44     10147757.72      3659948.14     10147700.62
       3659971.4     10147674.36      3659970.45     10147545.38
      3659956.17     10147492.74      3659972.23     10147459.73
      3660042.72     10147400.84      3660052.13     10147311.44
      3660032.41     10147191.45      3660045.98     10147121.57
      3660040.94     10147002.21      3659984.39     10146807.52
      3660070.47     10146685.93      3660064.26     10146612.14
      3660082.06     10146551.71      3660072.64     10146446.96
      3660100.16     10146355.82      3660105.49     10146272.83
      3660135.56     10146238.02      3660278.42     10146173.63
      3660279.44     10146155.67      3660217.82     10146148.96
      3660206.48     10146132.47      3660230.13     10146098.01
      3660289.22      10146076.6       3660196.4      10146013.1
       3660020.9     10146025.85      3659992.11     10145861.64

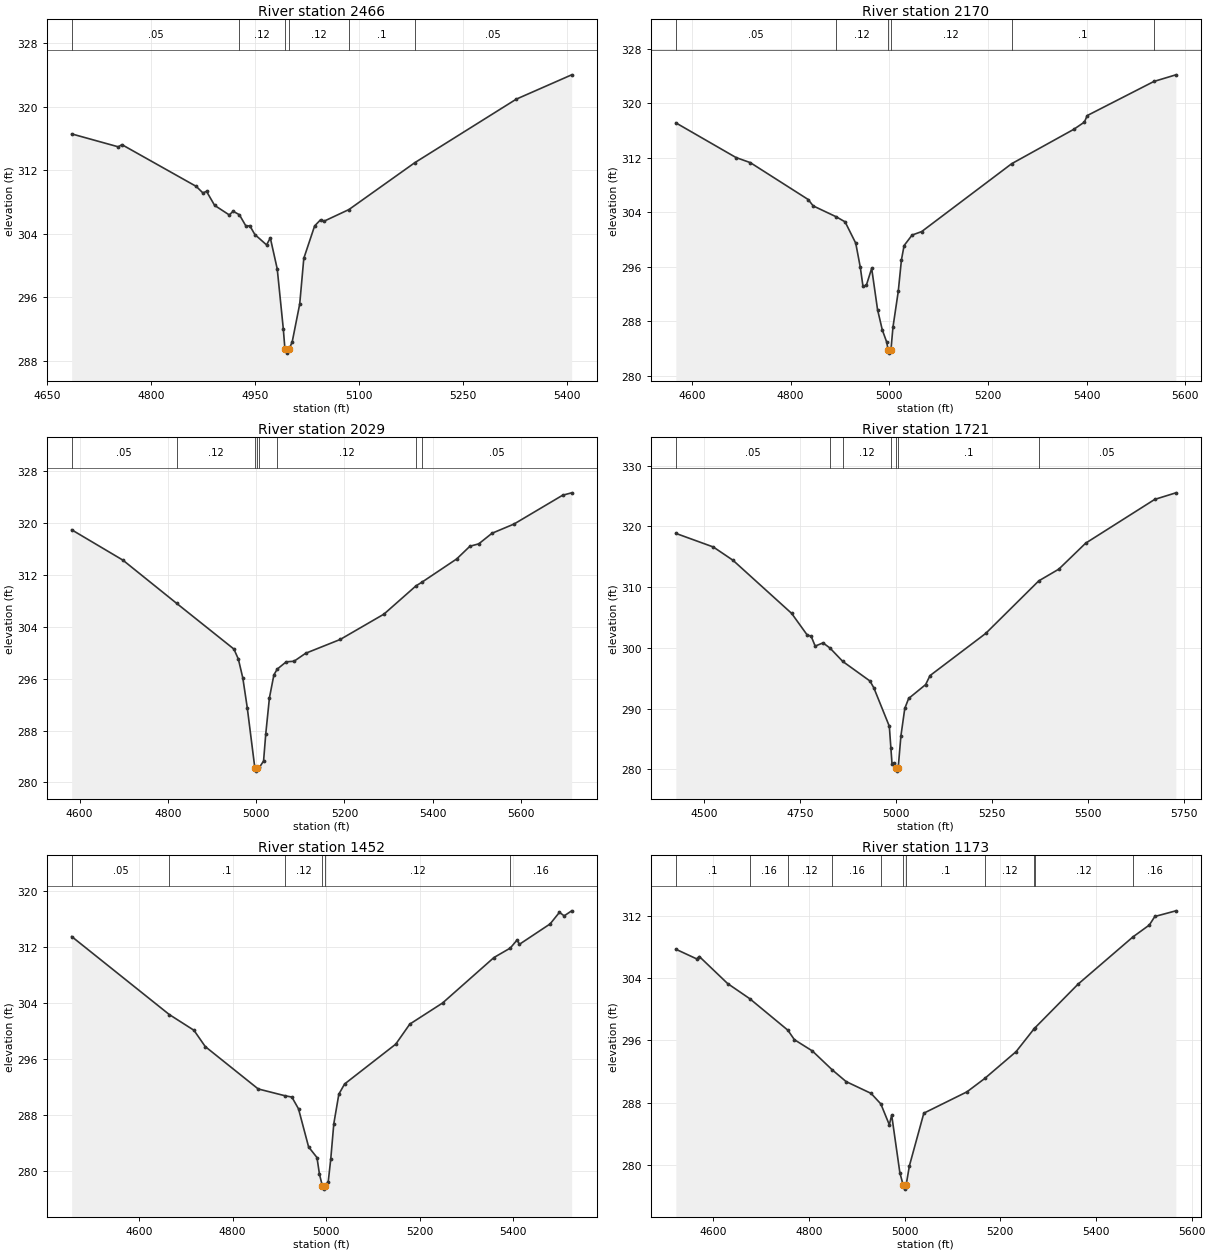
Type RM Length L Ch R = 1 ,2466    ,296,296,296
BEGIN DESCRIPTION:
UNT109 in ROCK 54.0
END DESCRIPTION:
XS GIS Cut Line= 4
      3660249.28     10147818.34      3660044.83     10147784.48
      3659876.86     10147716.77       3659545.3     10147742.67
#Sta/Elev= 30
  4685.9  316.56  4753.2  314.93  4758.3  315.21  4865.5  309.95  4875.2  309.12
  4880.3  309.33    4892  307.56  4913.2  306.35  4918.6  306.82  4927.7  306.38
  4937.3  304.93  4942.7     305    4950  303.89  4966.9  302.58  4972.3  303.46
  4982.3  299.55    4991  292.04  4993.4  289.45  4996.2  288.95  4999.4  289.45
  5003.9  290.38  5014.7  295.14  5020.6  300.89  5036.2  304.97  5044.7  305.74
  5050.1  305.58  5085.6  307.03  5180.7  312.94    5327  320.94  5406.8     324
#Mann= 6 ,-1 , 0
  4685.9     .05       0  4927.7     .12       0  4993.4     .07       0
  4999.4     .12       0  5085.6      .1       0  5180.7     .05       0
Bank Sta=4993.4,4999.4
XS Rating Curve= 0 ,0
Exp/Cntr=0.3,0.1

Type RM Length L Ch R = 1 ,2170    ,141,141,141
BEGIN DESCRIPTION:
Mapping XS fcfa3166
END DESCRIPTION:
XS GIS Cut Line= 4
       3660334.1     10147690.71      3660123.57      10147528.3
      3659925.07      10147448.6      3659465.97     10147720.15
#Sta/Elev= 30
  4567.6  317.15  4689.5  312.06  4718.5  311.31  4835.7   305.9  4845.9  304.96
  4892.6  303.36  4910.5  302.62  4932.1  299.49  4941.4  295.93  4946.8  293.14
  4953.6  293.31  4964.4  295.79  4976.3  289.74  4985.9  286.76  4995.1  284.92
  4997.5  283.85  5000.3  283.35  5003.5  283.85  5007.5  287.14  5018.3  292.42
  5024.7  297.04  5030.1  299.14  5046.3  300.68  5065.7  301.19  5248.2  311.16
  5373.9   316.2  5395.4  317.26  5401.2  318.22  5536.4  323.23  5580.8   324.2
#Mann= 6 ,-1 , 0
  4567.6     .05       0  4892.6     .12       0  4997.5     .07       0
  5003.5     .12       0  5248.2      .1       0  5536.4     .05       0
Bank Sta=4997.5,5003.5
XS Rating Curve= 0 ,0
Exp/Cntr=0.3,0.1

Type RM Length L Ch R = 1 ,2029    ,308,308,308
BEGIN DESCRIPTION:
Mapping XS ebc9915d
END DESCRIPTION:
XS GIS Cut Line= 4
      3660457.39     10147404.98      3659971.69     10147350.85
      3659654.39     10147256.11      3659341.64     10147254.61
#Sta/Elev= 30
  4582.1  318.97  4698.1  314.29  4819.9  307.62  4949.6  300.57  4959.7  299.02
  4969.8   296.1  4979.8  291.55    4997  282.24  4999.7  281.74    5003  282.24
  5007.5  282.33  5016.8   283.3  5021.8  287.52  5030.1  293.06  5040.2  296.59
  5047.8  297.48  5068.1   298.6  5085.8  298.69  5112.1  299.92  5190.4  302.05
  5289.5  305.96  5361.9  310.31  5376.5  310.93  5454.2  314.47  5484.2  316.43
  5504.2   316.8  5534.2  318.43  5584.2  319.86  5694.2   324.3  5714.7  324.67
#Mann= 8 ,-1 , 0
  4582.1     .05       0  4819.9     .12       0    4997     .07       0
    5003     .12       0  5007.5     .05       0  5047.8     .12       0
  5361.9      .1       0  5376.5     .05       0
Bank Sta=4997,5003
XS Rating Curve= 0 ,0
Exp/Cntr=0.3,0.1

Type RM Length L Ch R = 1 ,1721    ,269,269,269
BEGIN DESCRIPTION:
Mapping XS 7afeaa4c
END DESCRIPTION:
XS GIS Cut Line= 5
      3660607.78     10147147.84      3660120.56     10147048.59
      3659956.65     10147068.14      3659684.46     10147176.41
      3659337.13     10147180.92
#Sta/Elev= 30
  4425.8  318.86  4523.4  316.62  4574.5  314.44  4727.4  305.69  4768.4  302.09
    4778  301.96  4788.8   300.3  4809.2  300.83  4827.3  299.98  4860.7  297.77
  4931.5  294.55  4941.6  293.42  4981.9   287.1    4986  283.49    4989  280.85
    4994  281.08    4999  280.21  5001.8  279.71    5005  280.21  5012.1  285.51
  5022.2  290.04  5032.3  291.68  5076.5  293.96  5087.9  295.44  5232.9  302.38
  5371.2  311.04  5423.4  312.97  5493.4  317.25  5673.4  324.46  5728.4  325.54
#Mann= 7 ,-1 , 0
  4425.8     .05       0  4827.3      .1       0  4860.7     .12       0
    4986      .1       0    4999     .07       0    5005      .1       0
  5371.2     .05       0
Bank Sta=4999,5005
XS Rating Curve= 0 ,0
Exp/Cntr=0.3,0.1

Type RM Length L Ch R = 1 ,1452    ,279,279,279
BEGIN DESCRIPTION:
Mapping XS f0e1db7d
END DESCRIPTION:
XS GIS Cut Line= 3
      3660492.01     10147003.48      3659940.11     10146780.92
      3659465.96     10146788.42
#Sta/Elev= 30
  4455.7  313.55  4664.4  302.41  4717.2  300.16  4741.4  297.83  4854.6  291.78
  4912.3   290.8  4926.6  290.62  4940.8  288.94  4962.4   283.5  4980.3  281.98
  4985.7  279.58  4991.7  277.97  4994.5  277.47  4997.7  277.97  5004.4  278.53
  5009.8  281.78  5016.3  286.81  5027.1  291.04  5039.4  292.49  5148.8  298.18
  5178.8  301.04  5248.8  304.05  5358.8  310.55  5393.7   311.9  5408.3  313.06
  5413.3  312.44  5478.9  315.35  5498.9  317.01  5508.9   316.5    5525  317.22
#Mann= 6 ,-1 , 0
  4455.7     .05       0  4664.4      .1       0  4912.3     .12       0
  4991.7     .07       0  4997.7     .12       0  5393.7     .16       0
Bank Sta=4991.7,4997.7
XS Rating Curve= 0 ,0
Exp/Cntr=0.3,0.1

Type RM Length L Ch R = 1 ,1173    ,301,301,301
BEGIN DESCRIPTION:
Mapping XS 50d6a0b4
END DESCRIPTION:
XS GIS Cut Line= 4
      3660510.04     10146750.84       3660177.7     10146561.36
      3659923.57     10146543.32      3659529.61     10146650.08
#Sta/Elev= 30
  4521.5  307.76  4564.9  306.52  4570.6  306.82  4629.7  303.34  4675.9  301.39
  4755.6  297.33  4769.4   296.1  4806.9  294.65  4848.5  292.21  4877.5   290.7
  4929.7  289.18  4950.1  287.82  4967.8  285.14  4972.8  286.38  4989.9  278.95
  4996.9  277.34  4999.6  276.84  5002.9  277.34  5009.9  279.86    5040  286.63
  5130.2  289.38  5167.3   291.1  5232.9  294.56  5270.6  297.51  5271.6  297.58
  5362.5  303.26  5477.3  309.35  5511.5  310.88    5523  311.98    5567  312.71
#Mann= 11 ,-1 , 0
  4521.5      .1       0  4675.9     .16       0  4755.6     .12       0
  4848.5     .16       0  4950.1      .1       0  4996.9     .07       0
  5002.9      .1       0  5167.3     .12       0  5270.6     .16       0
  5271.6     .12       0  5477.3     .16       0
Bank Sta=4996.9,5002.9
XS Rating Curve= 0 ,0
Exp/Cntr=0.3,0.1

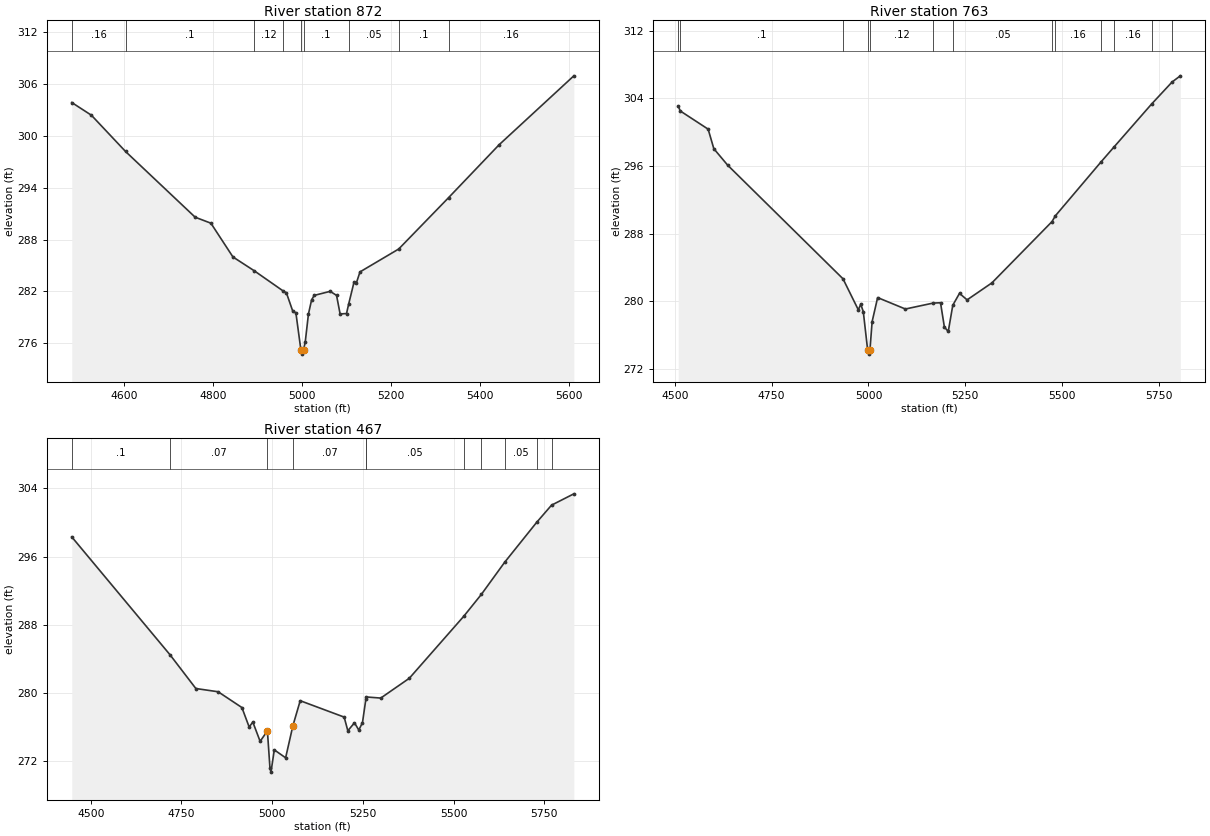
Type RM Length L Ch R = 1 ,872     ,109,109,109
BEGIN DESCRIPTION:
Mapping XS ce5d30e1
END DESCRIPTION:
XS GIS Cut Line= 3
      3660470.94     10146635.04      3660088.98     10146238.05
      3659571.67      10146495.2
#Sta/Elev= 30
  4481.9  303.86    4526  302.39  4602.8  298.19  4759.3  290.58  4794.6  289.89
  4844.2  285.98  4891.8  284.39  4956.3  282.07  4964.4  281.82  4978.5  279.73
  4985.7  279.51  4996.9  275.23  4999.6  274.73  5002.9  275.23  5006.8  276.17
  5013.9  279.37    5021  281.01  5026.9  281.53  5062.8     282  5077.1  281.53
  5085.1  279.38  5099.5  279.43  5104.4  280.54  5116.3  283.05  5121.9  283.01
  5129.8  284.25  5216.8   286.9  5329.2  292.86  5442.5  298.97  5610.5  306.95
#Mann= 9 ,-1 , 0
  4481.9     .16       0  4602.8      .1       0  4891.8     .12       0
  4956.3      .1       0  4996.9     .07       0  5002.9      .1       0
  5104.4     .05       0  5216.8      .1       0  5329.2     .16       0
Bank Sta=4996.9,5002.9
XS Rating Curve= 0 ,0
Exp/Cntr=0.3,0.1

Type RM Length L Ch R = 1 ,763     ,296,296,296
BEGIN DESCRIPTION:
Mapping XS 5f1428d1
END DESCRIPTION:
XS GIS Cut Line= 4
      3660492.01      10146609.5      3660144.62     10146126.77
      3660009.28     10146126.77      3659565.67     10146478.65
#Sta/Elev= 30
  4508.8  303.09    4514  302.51    4586  300.36  4600.7  298.05  4636.3  296.11
  4934.2  282.68  4973.8  279.01    4980  279.68  4986.6   278.8  4997.8  274.28
  5000.6  273.78  5003.8  274.28  5009.4  277.62  5023.6  280.46  5095.3  279.11
  5166.8  279.81    5186  279.85    5196  276.97    5206  276.46  5217.7  279.56
    5235  280.96  5254.6  280.19  5318.7   282.2  5473.9  289.44  5482.3  290.11
    5601  296.52  5633.1  298.21    5731  303.33  5783.9  305.93  5805.1  306.66
#Mann= 13 ,-1 , 0
  4508.8     .16       0    4514      .1       0  4934.2     .12       0
  4997.8     .07       0  5003.8     .12       0  5166.8      .1       0
  5217.7     .05       0  5473.9      .1       0  5482.3     .16       0
    5601     .05       0  5633.1     .16       0    5731      .1       0
  5783.9     .16       0
Bank Sta=4997.8,5003.8
XS Rating Curve= 0 ,0
Exp/Cntr=0.3,0.1

Type RM Length L Ch R = 1 ,467     ,0,0,0
BEGIN DESCRIPTION:
UNT109 IN ROCK 1.0
END DESCRIPTION:
XS GIS Cut Line= 5
      3660478.45     10146535.77      3660380.72     10146086.17
      3660188.23     10146068.12      3660012.29     10146093.69
      3659576.67     10146433.17
#Sta/Elev= 30
  4447.7  298.32  4718.7  284.49  4789.6  280.55    4851  280.17  4916.5  278.32
  4936.5  276.04  4946.6  276.62  4966.7  274.36  4986.8  275.58  4993.8  271.25
  4996.6  270.75  5005.8  273.36    5037  272.43  5057.1   276.2  5077.2  279.12
  5198.3   277.2  5208.4   275.6  5226.7  276.53  5238.7  275.68  5248.8  276.56
    5258  279.28  5259.2  279.56  5299.1  279.43  5377.8  281.75  5527.7  289.01
  5576.3  291.58  5640.6  295.35  5728.6  300.02  5769.7  302.04  5831.2  303.37
#Mann= 11 ,-1 , 0
  4447.7      .1       0  4718.7     .07       0  4986.8    .035       0
  5057.1     .07       0    5258      .1       0  5259.2     .05       0
  5527.7      .1       0  5576.3     .16       0  5640.6     .05       0
  5728.6     .16       0  5769.7      .1       0
Bank Sta=4986.8,5057.1
XS Rating Curve= 0 ,0
Exp/Cntr=0.3,0.1

Chan Stop Cuts=-1
Use User Specified Reach Order=0
Composite Channel Slope=5