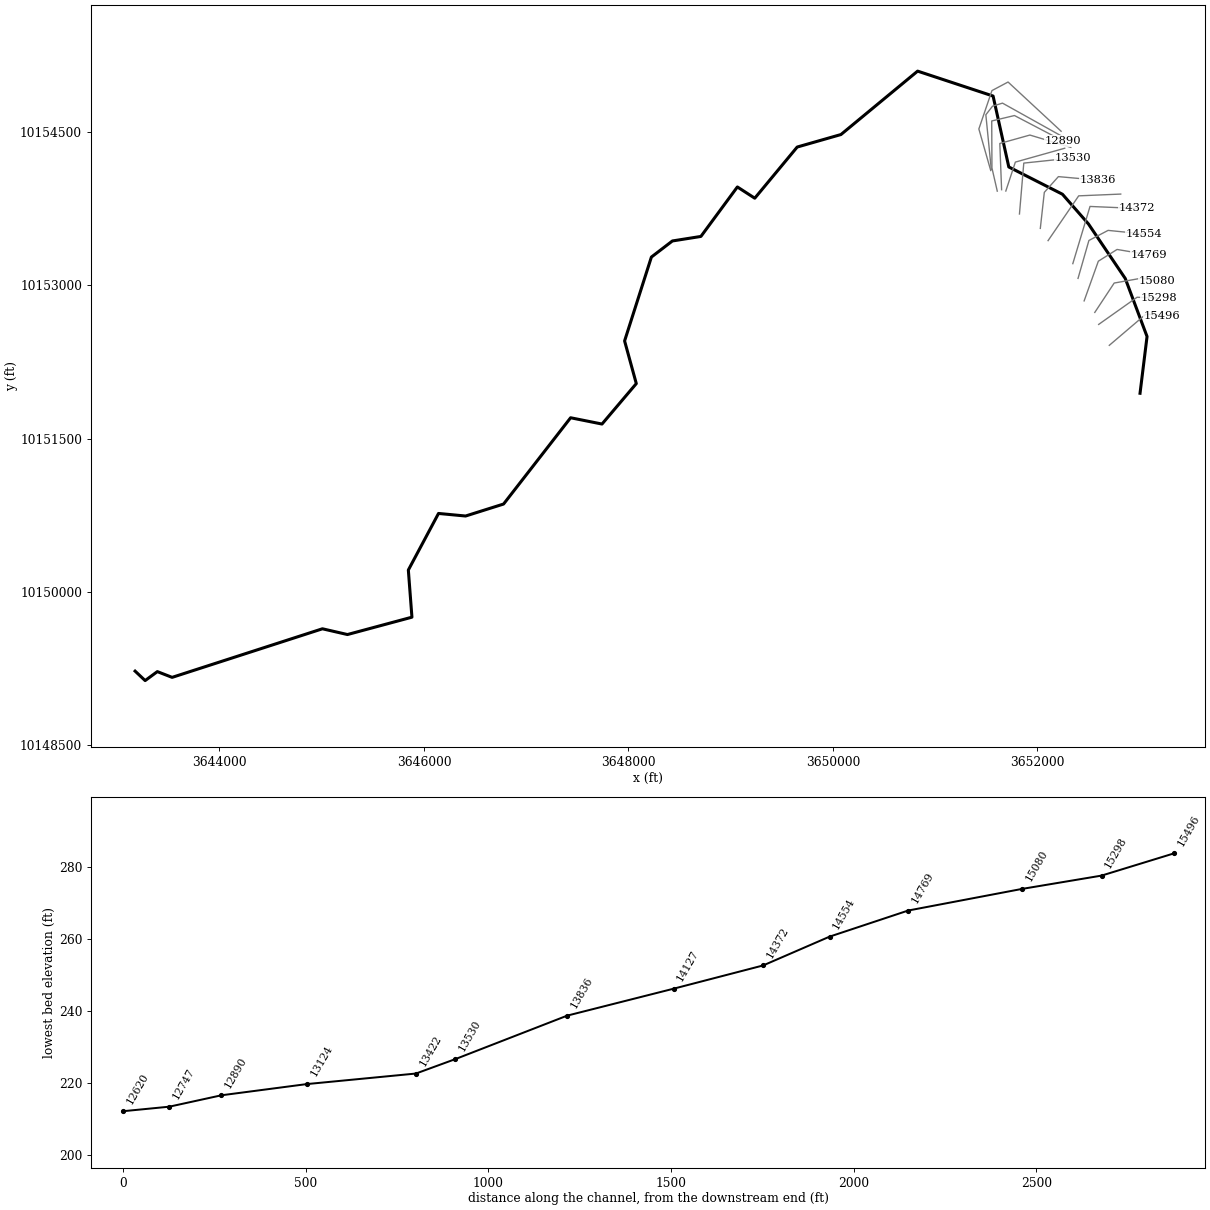
--- UNT110 IN ROCK.prj (project) ---

Proj Title=UNT110 IN ROCK Base Level Engineering
Current Plan=p01
Default Exp/Contr=0.3,0.1
English Units
Geom File=g01
Flow File=f01
Plan File=p01
Y Axis Title=Elevation
X Axis Title(PF)=Main Channel Distance
X Axis Title(XS)=Station
BEGIN DESCRIPTION:
UNT110 IN ROCK
END DESCRIPTION:
DSS Export Rating Curves= 0
DSS Export Rating Curve Sorted= 0
DSS Export Volume Flow Curves= 0
DXF OffsetX= 0
DXF OffsetY= 0
DXF ScaleX= 1
DXF ScaleY= 10

--- UNT110 IN ROCK.p01 (plan) ---

Plan Title=Multiple Run
Short Identifier=Multiple
Geom File=g01
Flow File=f01
Subcritical Flow
K Sum by GR= 0
Std Step Tol= 0.01
Critical Tol= 0.01
Num of Std Step Trials= 20
Max Error Tol= 0.3
Flow Tol Ratio= 0.001
Split Flow NTrial= 30
Split Flow Tol= 0.02
Split Flow Ratio= 0.02
Log Output Level= 0
Friction Slope Method= 1
Unsteady Friction Slope Method= 2
Unsteady Bridges Friction Slope Method= 1
Parabolic Critical Depth
Global Vel Dist=  1 , 1 , 1
Global Log Level= 0
CheckData=True
Encroach Param= -1, 0, 0, 0
BEGIN DESCRIPTION:
Multiple Run
END DESCRIPTION:

--- UNT110 IN ROCK.f01 (steady flow) ---

Flow Title=Multiple
Program Version=4.10
Number of Profiles= 7
Profile Names=10-year,25-year,50-year,1pct_min,100-year,1pct_plu,500-year
River Rch & RM=UNT110 IN ROCK,Reach-1         ,15496
     643     873    1064     951    1285    1738    1879
Boundary for River Rch & Prof#=UNT110 IN ROCK,Reach-1         , 1
Up Type= 0
Dn Type= 3
Dn Slope=0.0148
Boundary for River Rch & Prof#=UNT110 IN ROCK,Reach-1         , 2
Up Type= 0
Dn Type= 3
Dn Slope=0.0148
Boundary for River Rch & Prof#=UNT110 IN ROCK,Reach-1         , 3
Up Type= 0
Dn Type= 3
Dn Slope=0.0148
Boundary for River Rch & Prof#=UNT110 IN ROCK,Reach-1         , 4
Up Type= 0
Dn Type= 3
Dn Slope=0.0148
Boundary for River Rch & Prof#=UNT110 IN ROCK,Reach-1         , 5
Up Type= 0
Dn Type= 3
Dn Slope=0.0148
Boundary for River Rch & Prof#=UNT110 IN ROCK,Reach-1         , 6
Up Type= 0
Dn Type= 3
Dn Slope=0.0148
Boundary for River Rch & Prof#=UNT110 IN ROCK,Reach-1         , 7
Up Type= 0
Dn Type= 3
Dn Slope=0.0148
DSS Import GetInterval= 0
DSS Import GetPeak= 0
DSS Import FillOption= 0

--- UNT110 IN ROCK.g01 (geometry) ---

Geom Title=Existing Conditions
Program Version=4.10

River Reach=UNT110 IN ROCK  ,Reach-1
Reach XY= 30
      3653004.03     10151944.14       3653072.6      10152499.7
      3652859.63     10153067.34      3652499.14     10153601.86
      3652245.24     10153892.22       3651720.5     10154159.15
      3651566.68     10154853.31      3650828.58     10155097.28
      3650078.58     10154476.62      3649650.62     10154354.22
      3649235.69     10153853.35      3649065.56      10153963.6
      3648708.78     10153479.22      3648430.14     10153434.95
       3648224.5      10153277.3      3647962.36     10152456.37
      3648076.93     10152038.88       3647741.5     10151642.96
      3647434.41     10151704.44      3646778.66     10150859.93
      3646407.12     10150742.67      3646142.37     10150767.84
      3645847.23     10150214.03      3645882.34     10149752.47
      3645251.56     10149582.59       3645006.9     10149638.95
       3643536.7     10149163.39      3643392.04     10149219.74
      3643272.83      10149131.9      3643174.56     10149224.61

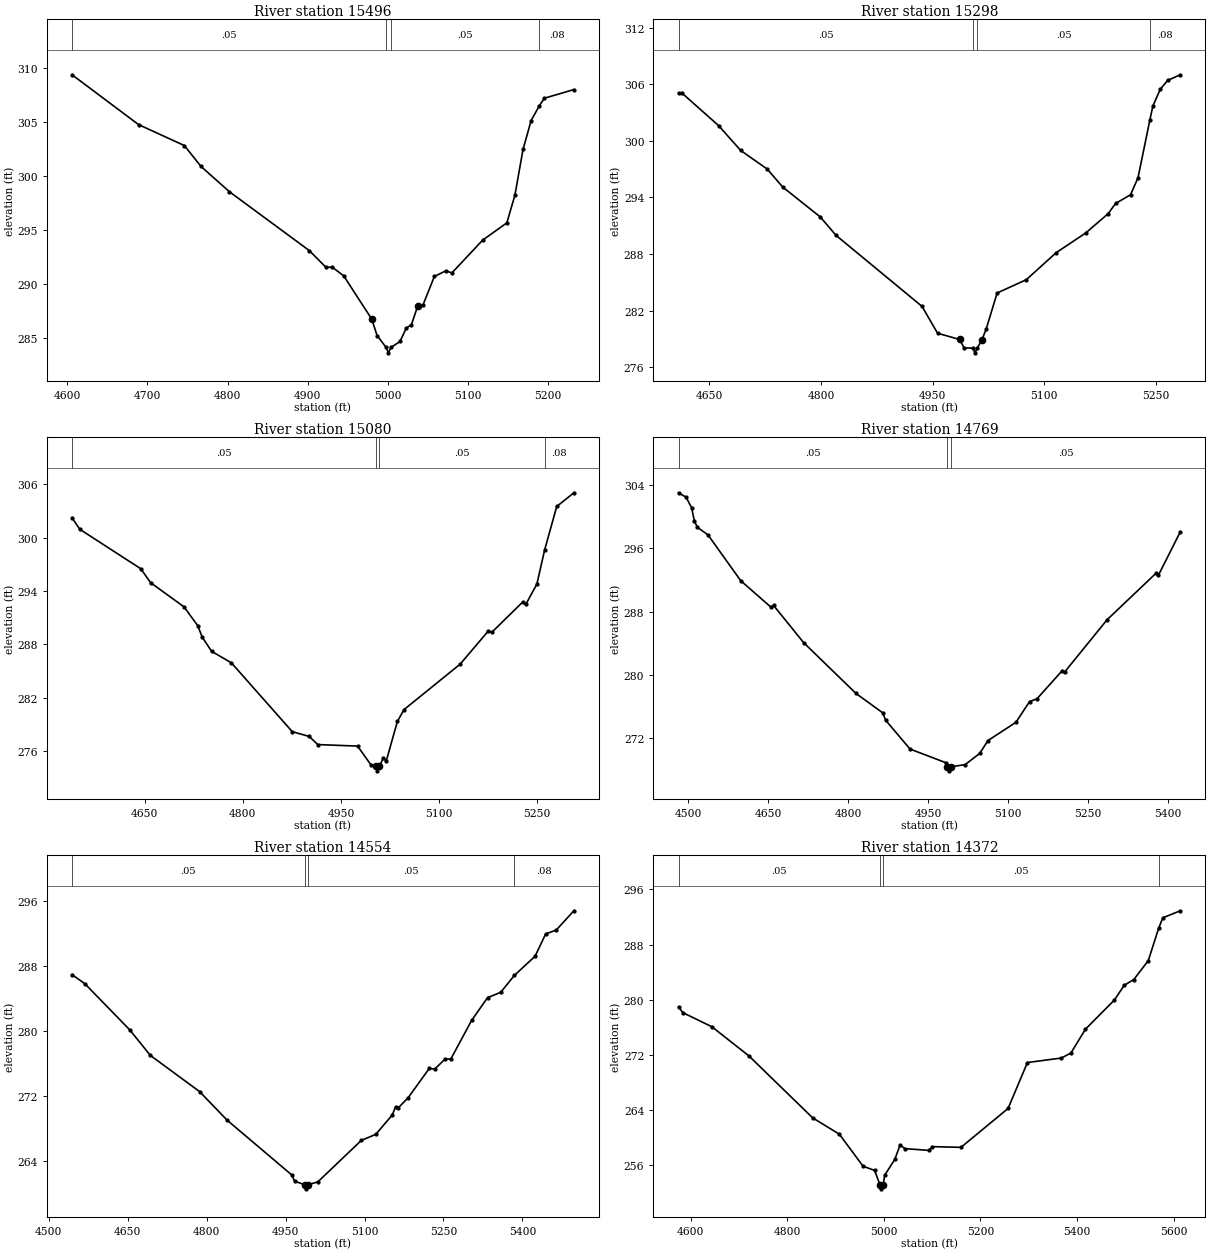
Type RM Length L Ch R = 1 ,15496   ,198,198,198
BEGIN DESCRIPTION:
UNT110 IN ROCK 6.0
END DESCRIPTION:
XS GIS Cut Line= 3
      3652703.39     10152413.37      3653064.03     10152720.63
      3653215.05      10152702.4
#Sta/Elev= 30
    4606  309.41  4688.9   304.8    4746  302.86  4766.9  300.92    4802   298.6
    4902  293.13  4922.8  291.58  4930.5   291.6  4944.8   290.8  4979.9  286.78
  4986.5  285.26  4997.8  284.17  5000.5  283.67  5003.8  284.17    5015  284.72
  5022.8  285.95  5029.3  286.28    5037  287.97  5043.6  288.08  5057.9  290.74
  5072.2  291.26  5079.8  291.07  5118.1   294.1  5148.3   295.7  5158.4  298.27
  5168.5   302.5  5178.6  305.17  5188.8  306.54  5195.1  307.24  5231.9  308.04
#Mann= 4 ,-1 , 0
    4606     .05       0  4997.8     .04       0  5003.8     .05       0
  5188.8     .08       0
Bank Sta=4979.9,5037
XS Rating Curve= 0 ,0
Exp/Cntr=0.3,0.1

Type RM Length L Ch R = 1 ,15298   ,218,218,218
BEGIN DESCRIPTION:
Mapping XS 9abcbb43
END DESCRIPTION:
XS GIS Cut Line= 3
      3652599.44     10152618.06      3652974.91     10152883.93
      3653189.01      10152876.4
#Sta/Elev= 30
  4608.6  305.07  4613.3  305.07  4662.5  301.62  4692.1  298.99  4727.8  297.01
  4748.7   295.1  4799.1  291.93  4820.2  289.98  4935.8  282.44  4956.7  279.59
  4986.2  278.93  4992.3  278.04  5004.1  278.01  5006.9  277.51  5010.1  278.01
  5015.8  278.82  5021.9     280  5036.7  283.86  5075.9  285.27  5115.9  288.13
  5155.9  290.24  5185.9  292.28  5195.9  293.36    5216  294.29    5226  296.08
    5242  302.24    5246   303.7    5256  305.49    5266  306.43  5282.9  307.02
#Mann= 4 ,-1 , 0
  4608.6     .05       0  5004.1     .03       0  5010.1     .05       0
    5242     .08       0
Bank Sta=4986.2,5015.8
XS Rating Curve= 0 ,0
Exp/Cntr=0.3,0.1

Type RM Length L Ch R = 1 ,15080   ,311,311,311
BEGIN DESCRIPTION:
Mapping XS 3ab85541
END DESCRIPTION:
XS GIS Cut Line= 4
      3652561.43     10152735.49      3652751.31     10153023.04
      3653019.33     10153070.78      3653167.57     10153042.65
#Sta/Elev= 30
  4538.7  302.22  4550.5  300.94  4643.8  296.51  4658.9  294.94  4710.1  292.22
  4731.1   290.1  4737.8  288.83  4752.2  287.23  4782.3  285.95  4875.6  278.21
  4901.6  277.67  4914.6  276.76  4975.5  276.59  4995.8   274.5    5003  274.31
  5005.7  273.81    5009  274.31  5014.5   275.2  5019.5  274.94  5036.4  279.36
  5046.6  280.69  5132.4  285.79  5175.7  289.53  5180.7  289.36  5227.9  292.75
    5233  292.52  5249.9   294.8  5261.6   298.6  5280.2   303.5  5306.4  305.04
#Mann= 4 ,-1 , 0
  4538.7     .05       0    5003     .03       0    5009     .05       0
  5261.6     .08       0
Bank Sta=5003,5009
XS Rating Curve= 0 ,0
Exp/Cntr=0.3,0.1

Type RM Length L Ch R = 1 ,14769   ,215,215,215
BEGIN DESCRIPTION:
Mapping XS c606078f
END DESCRIPTION:
XS GIS Cut Line= 4
      3652457.26     10152848.33      3652596.15     10153236.79
      3652779.53     10153351.81      3653087.35     10153299.79
#Sta/Elev= 30
  4481.5  303.04  4495.6  302.48  4505.9  301.17  4511.2  299.48  4516.9  298.66
  4536.6  297.72  4598.2   291.9  4654.4  288.58  4659.8  288.77    4716  284.07
  4814.2  277.63  4864.6  275.16  4869.9  274.24  4915.7  270.58  4982.8  268.85
  4985.7  268.32  4988.5  267.82  4991.7  268.32  5019.1  268.61  5046.5  270.03
  5061.8  271.65  5114.4  273.97    5140   276.6  5153.7  276.94  5200.4  280.45
  5205.5  280.32  5285.5  286.97  5376.7  292.82  5381.7  292.61  5422.7   298.1
#Mann= 3 ,-1 , 0
  4481.5     .05       0  4985.7     .03       0  4991.7     .05       0
Bank Sta=4985.7,4991.7
XS Rating Curve= 0 ,0
Exp/Cntr=0.3,0.1

Type RM Length L Ch R = 1 ,14554   ,182,182,182
BEGIN DESCRIPTION:
Mapping XS f9fab45f
END DESCRIPTION:
XS GIS Cut Line= 4
      3652397.58     10153068.61      3652503.92      10153439.7
      3652691.64     10153538.44       3653045.4     10153502.63
#Sta/Elev= 30
  4544.1  286.92  4568.1  285.83  4653.9  280.12  4692.9  276.99  4786.5  272.54
  4838.5  269.04  4961.4   262.3  4967.1  261.53  4986.1  261.08  4988.9  260.58
  4992.1  261.08  5011.1  261.43  5093.7  266.53  5121.3  267.28  5152.8  269.68
  5158.9  270.67    5164  270.54  5182.9  271.79  5223.1   275.4  5233.2   275.3
  5253.3  276.56  5263.9  276.54  5303.5   281.3  5333.7  284.09  5358.8  284.75
  5384.7  286.83  5424.1  289.19  5444.2  291.93  5464.3  292.41  5497.8  294.78
#Mann= 4 ,-1 , 0
  4544.1     .05       0  4986.1     .03       0  4992.1     .05       0
  5384.7     .08       0
Bank Sta=4986.1,4992.1
XS Rating Curve= 0 ,0
Exp/Cntr=0.3,0.1

Type RM Length L Ch R = 1 ,14372   ,245,245,245
BEGIN DESCRIPTION:
Mapping XS 4b7c49d6
END DESCRIPTION:
XS GIS Cut Line= 3
      3652346.57     10153212.89      3652514.77     10153772.82
      3652968.31     10153753.33
#Sta/Elev= 30
    4575  278.95  4584.1  278.13    4644  276.09  4720.5  271.87  4852.7  262.87
  4907.8  260.51    4957  255.86  4980.9  255.25  4992.3  253.08    4995  252.58
  4998.3  253.08  5001.8  254.58  5022.7  256.86  5033.5  258.94  5043.6  258.41
  5094.4  258.15  5099.6   258.7  5159.6   258.6  5257.1  264.24  5297.1   270.9
  5367.2  271.55  5387.2  272.28  5417.2  275.73  5477.3  279.98  5497.3  282.09
  5517.3  282.94  5547.3  285.68  5568.7  290.37  5577.4  291.89  5613.6  292.91
#Mann= 4 ,-1 , 0
    4575     .05       0  4992.3     .03       0  4998.3     .05       0
  5568.7     .08       0
Bank Sta=4992.3,4998.3
XS Rating Curve= 0 ,0
Exp/Cntr=0.3,0.1

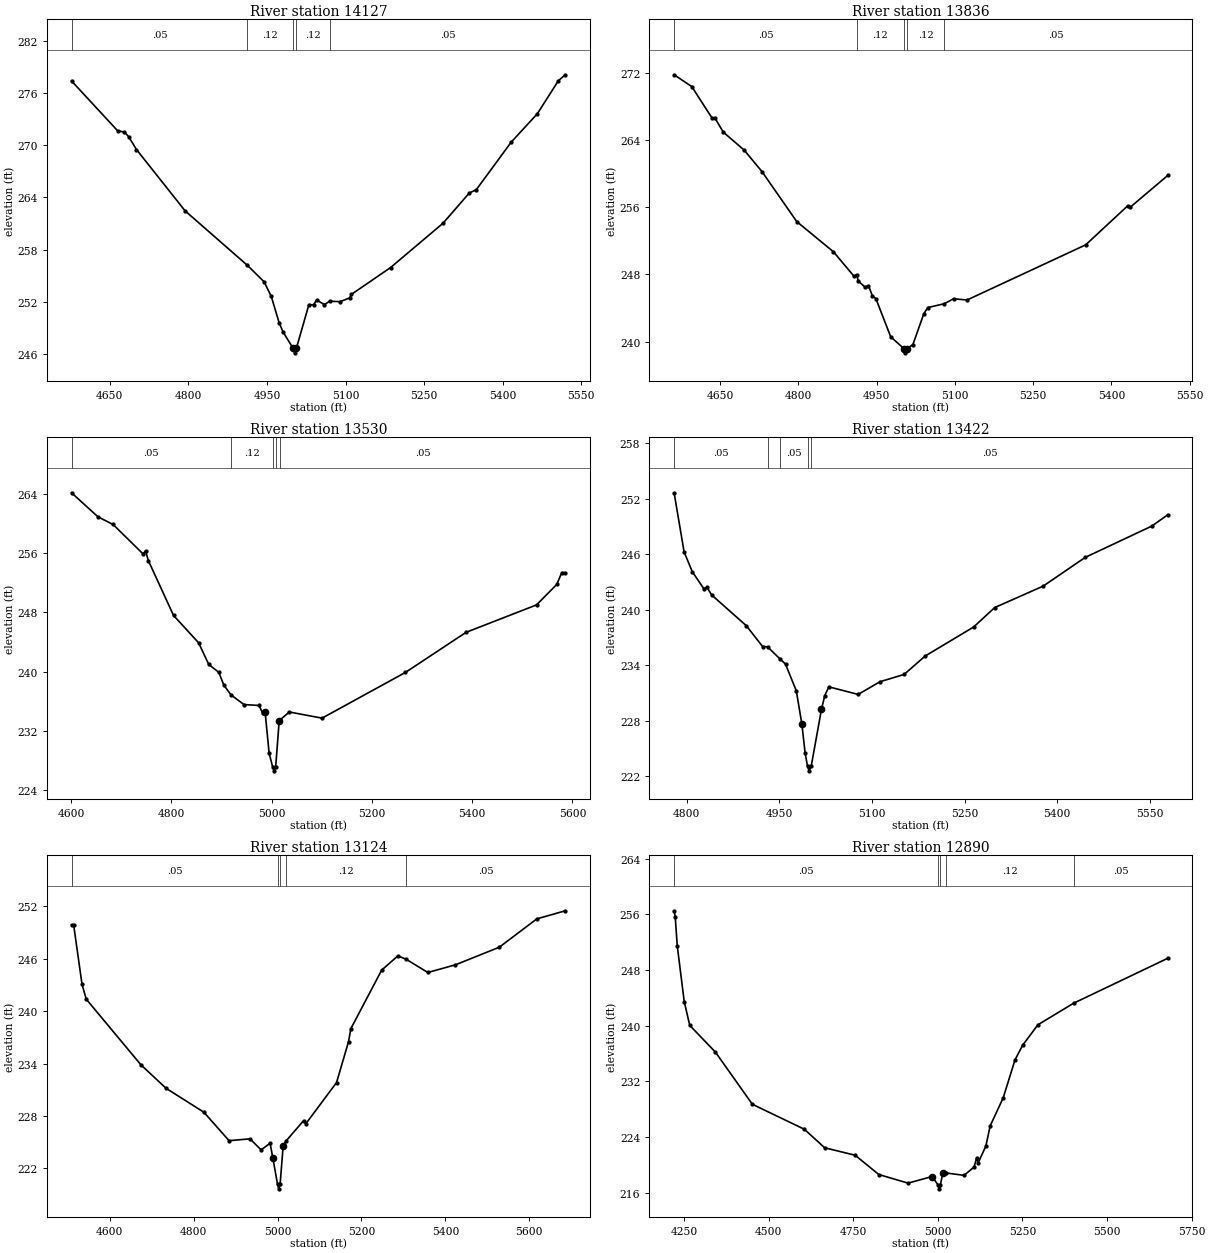
Type RM Length L Ch R = 1 ,14127   ,291,291,291
BEGIN DESCRIPTION:
Mapping XS 22076d7f
END DESCRIPTION:
XS GIS Cut Line= 3
      3652104.51     10153438.13      3652403.98      10153876.5
      3652815.22     10153893.86
#Sta/Elev= 30
  4576.9  277.36    4665  271.63    4678  271.49    4686  270.95  4700.9  269.48
  4793.7  262.44  4912.6  256.18  4944.5  254.29  4958.2  252.61  4973.1   249.6
  4980.8  248.52    5000  246.63  5002.7  246.13    5006  246.63    5030  251.66
  5038.9  251.65  5044.9   252.2  5059.8  251.66  5069.5  252.06  5089.7  252.01
  5107.8  252.44  5111.1  252.84    5186  255.93  5286.1  261.02  5336.1  264.48
  5349.7  264.88  5416.2  270.33  5466.2   273.6  5506.3  277.39  5519.4  278.07
#Mann= 5 ,-1 , 0
  4576.9     .05       0  4912.6     .12       0    5000     .07       0
    5006     .12       0  5069.5     .05       0
Bank Sta=5000,5006
XS Rating Curve= 0 ,0
Exp/Cntr=0.3,0.1

Type RM Length L Ch R = 1 ,13836   ,306,306,306
BEGIN DESCRIPTION:
Mapping XS 0b7c9b1f
END DESCRIPTION:
XS GIS Cut Line= 4
      3652028.66     10153558.01      3652067.72     10153910.62
      3652205.53      10154064.7      3652588.89     10154030.15
#Sta/Elev= 30
  4561.6  271.77  4595.4  270.37  4634.5   266.6  4639.5  266.66  4655.8  264.95
  4696.1  262.79  4730.2  260.23  4796.7  254.29  4867.1  250.69  4906.5  247.78
  4911.6  247.97  4914.4  247.23  4927.4  246.49  4934.2  246.66  4941.7  245.45
  4948.4  245.12  4976.8  240.57  5002.2  239.16  5004.9  238.66  5008.2  239.16
  5019.4  239.65  5040.3  243.32  5047.8  244.05  5079.2   244.5  5097.2   245.1
  5123.1  244.95  5350.6  251.52  5430.8  256.15  5435.8  255.99    5508  259.79
#Mann= 5 ,-1 , 0
  4561.6     .05       0  4911.6     .12       0  5002.2     .07       0
  5008.2     .12       0  5079.2     .05       0
Bank Sta=5002.2,5008.2
XS Rating Curve= 0 ,0
Exp/Cntr=0.3,0.1

Type RM Length L Ch R = 1 ,13530   ,108,108,108
BEGIN DESCRIPTION:
Mapping XS 06416a69
END DESCRIPTION:
XS GIS Cut Line= 3
      3651824.66     10153699.01      3651866.98     10154197.08
      3652349.05     10154247.88
#Sta/Elev= 30
  4601.1  264.12  4653.9  260.87    4684  259.84  4743.6  255.88  4748.7  256.28
  4754.3  254.97  4804.5  247.57  4854.6  243.87  4874.7  240.96  4894.8  239.89
  4904.8  238.17  4919.1  236.85    4945  235.54  4975.1  235.42  4982.2  234.37
  4987.2  234.49  4995.1     229  5002.2   227.1  5004.9   226.6  5008.2   227.1
  5015.2  233.35  5016.5  233.44  5035.3  234.54  5100.7  233.71    5267  239.88
  5387.9  245.29  5528.4  248.99  5568.7  251.75  5578.8  253.35  5585.7  253.32
#Mann= 5 ,-1 , 0
  4601.1     .05       0  4919.1     .12       0  5002.2     .07       0
  5008.2     .12       0  5016.5     .05       0
Bank Sta=4987.2,5015.2
XS Rating Curve= 0 ,0
Exp/Cntr=0.3,0.1

Type RM Length L Ch R = 1 ,13422   ,298,298,298
BEGIN DESCRIPTION:
Mapping XS dba9b860
END DESCRIPTION:
XS GIS Cut Line= 3
      3651691.21     10153923.68      3651784.52     10154206.85
       3652267.1      10154342.4
#Sta/Elev= 30
  4779.7  252.65  4795.9  246.26  4809.1  244.12  4827.7  242.29    4833  242.42
  4840.7  241.59  4896.5  238.29    4923  236.03    4931     236  4950.8  234.71
  4960.1  234.13  4977.6  231.23  4986.6  227.64  4991.8  224.55  4995.7  223.09
  4998.4  222.59  5001.7  223.09  5018.3  229.23  5023.6  230.72  5030.3  231.67
  5077.7  230.85  5112.9  232.22  5152.1  233.01  5186.2     235  5264.7  238.14
  5298.8  240.24  5377.3  242.56  5445.5  245.67  5552.9  249.04  5579.1  250.27
#Mann= 5 ,-1 , 0
  4779.7     .05       0    4931     .12       0  4950.8     .05       0
  4995.7     .03       0  5001.7     .05       0
Bank Sta=4986.6,5018.3
XS Rating Curve= 0 ,0
Exp/Cntr=0.3,0.1

Type RM Length L Ch R = 1 ,13124   ,234,234,234
BEGIN DESCRIPTION:
Mapping XS 01a011d4
END DESCRIPTION:
XS GIS Cut Line= 4
      3651649.97     10153936.64      3651632.61     10154389.14
      3651926.66      10154471.6      3652327.01     10154351.17
#Sta/Elev= 30
  4509.2  249.88  4514.2  249.88  4534.2  243.06  4544.2  241.37  4674.3  233.87
  4734.4  231.17  4824.4  228.44  4884.5  225.18  4934.5  225.39  4960.8  224.13
  4982.3  224.88  4988.6  223.25  5000.1  220.17  5002.8  219.67  5006.1  220.17
  5013.4  224.58  5020.4  225.15    5062  227.47  5067.2   227.1  5140.6  231.83
  5169.2  236.51  5174.7     238  5248.1  244.69  5286.7  246.32    5307  245.92
    5358  244.42    5424   245.3  5528.3  247.31  5617.7  250.55  5685.5  251.48
#Mann= 5 ,-1 , 0
  4509.2     .05       0  5000.1     .03       0  5006.1     .05       0
  5020.4     .12       0    5307     .05       0
Bank Sta=4988.6,5013.4
XS Rating Curve= 0 ,0
Exp/Cntr=0.3,0.1

Type RM Length L Ch R = 1 ,12890   ,143,143,143
BEGIN DESCRIPTION:
Mapping XS 94fc4bdd
END DESCRIPTION:
XS GIS Cut Line= 5
      3651607.65     10153922.54      3651555.57     10154149.34
       3651553.4     10154609.41      3651775.84     10154662.58
      3652252.15     10154413.03
#Sta/Elev= 30
  4220.3  256.51  4223.6  255.67  4229.6  251.48  4250.2  243.47  4266.5  240.05
  4342.5   236.2  4451.6  228.71  4605.3  225.12  4665.3  222.46  4755.3  221.39
  4825.3  218.62  4911.7  217.38  4982.9  218.33  5001.3  217.06    5004  216.56
  5007.3  217.06  5014.6  218.89  5023.9  218.84  5077.3   218.5  5107.1   219.7
  5114.2  220.97  5119.4  220.34  5141.8  222.71  5154.5  225.61    5193  229.64
  5227.9  235.09  5250.5   237.2  5295.6  240.13  5400.8  243.22  5679.5  249.69
#Mann= 5 ,-1 , 0
  4220.3     .05       0  5001.3     .03       0  5007.3     .05       0
  5023.9     .12       0  5400.8     .05       0
Bank Sta=4982.9,5014.6
XS Rating Curve= 0 ,0
Exp/Cntr=0.3,0.1

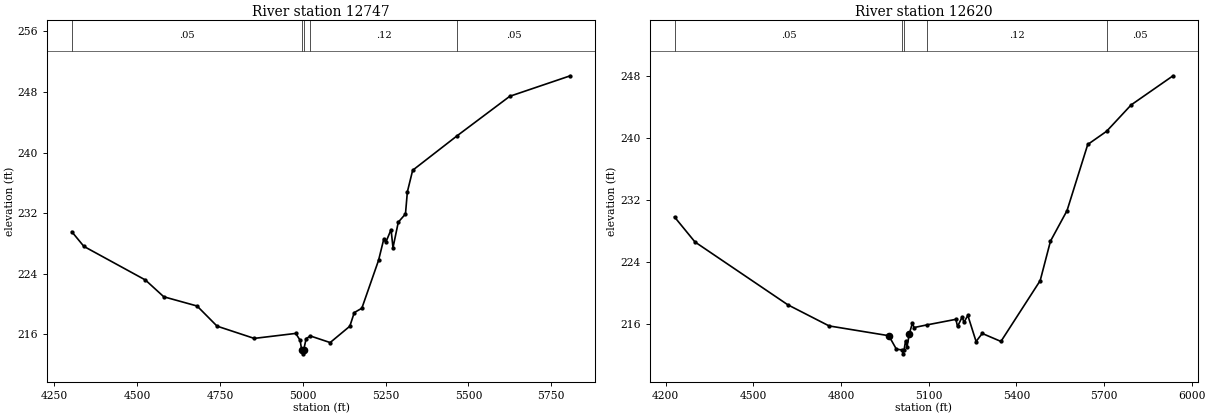
Type RM Length L Ch R = 1 ,12747   ,127,127,127
BEGIN DESCRIPTION:
Mapping XS d6681844
END DESCRIPTION:
XS GIS Cut Line= 5
      3651549.06     10154135.22      3651495.89     10154670.17
      3651560.99     10154753.72      3651658.65      10154784.1
      3652321.61     10154414.11
#Sta/Elev= 30
  4302.7  229.53  4339.3  227.59  4524.9  223.15  4580.5  220.93    4681  219.71
  4741.3  217.05  4853.5  215.43  4978.8  216.09  4992.1  215.18  4996.7  213.89
  4999.5  213.39  5002.7  213.89  5010.2   215.4  5023.1  215.75  5082.7  214.88
  5142.1  217.04  5155.5  218.84  5178.4  219.42  5228.9  225.76  5244.9  228.61
  5250.7  228.13  5266.6  229.81  5272.4  227.42  5288.4  230.79  5310.1  231.88
  5315.8   234.8  5331.8  237.65  5466.9  242.24    5625  247.43  5807.7  250.14
#Mann= 5 ,-1 , 0
  4302.7     .05       0  4996.7     .03       0  5002.7     .05       0
  5023.1     .12       0  5466.9     .05       0
Bank Sta=4996.7,5002.7
XS Rating Curve= 0 ,0
Exp/Cntr=0.3,0.1

Type RM Length L Ch R = 1 ,12620   ,0,0,0
BEGIN DESCRIPTION:
UNT110 IN ROCK 1.0
END DESCRIPTION:
XS GIS Cut Line= 5
      3651543.62     10154124.43      3651427.53     10154531.28
      3651555.57     10154906.72      3651713.13     10154990.62
      3652232.13     10154508.86
#Sta/Elev= 30
  4229.9  229.78  4299.8  226.56  4617.5  218.46    4759  215.73  4963.3  214.47
  4989.3  212.73  5009.6  212.63  5012.4  212.13  5015.6  212.63  5020.7  213.79
  5025.9  213.07  5033.7  214.73  5044.3  216.12  5049.6  215.52  5093.5  215.86
  5192.9  216.58  5198.6  215.66  5214.9  216.91  5220.5  216.18  5233.8  217.09
  5262.1  213.72  5283.1  214.76  5347.2  213.73  5481.5  221.57  5516.7  226.66
  5573.4   230.6  5644.3  239.13  5708.8  240.83  5792.8  244.23  5936.3  247.99
#Mann= 5 ,-1 , 0
  4229.9     .05       0  5009.6     .03       0  5015.6     .05       0
  5093.5     .12       0  5708.8     .05       0
Bank Sta=4963.3,5033.7
XS Rating Curve= 0 ,0
Exp/Cntr=0.3,0.1

Chan Stop Cuts=-1
Use User Specified Reach Order=0
Composite Channel Slope=5