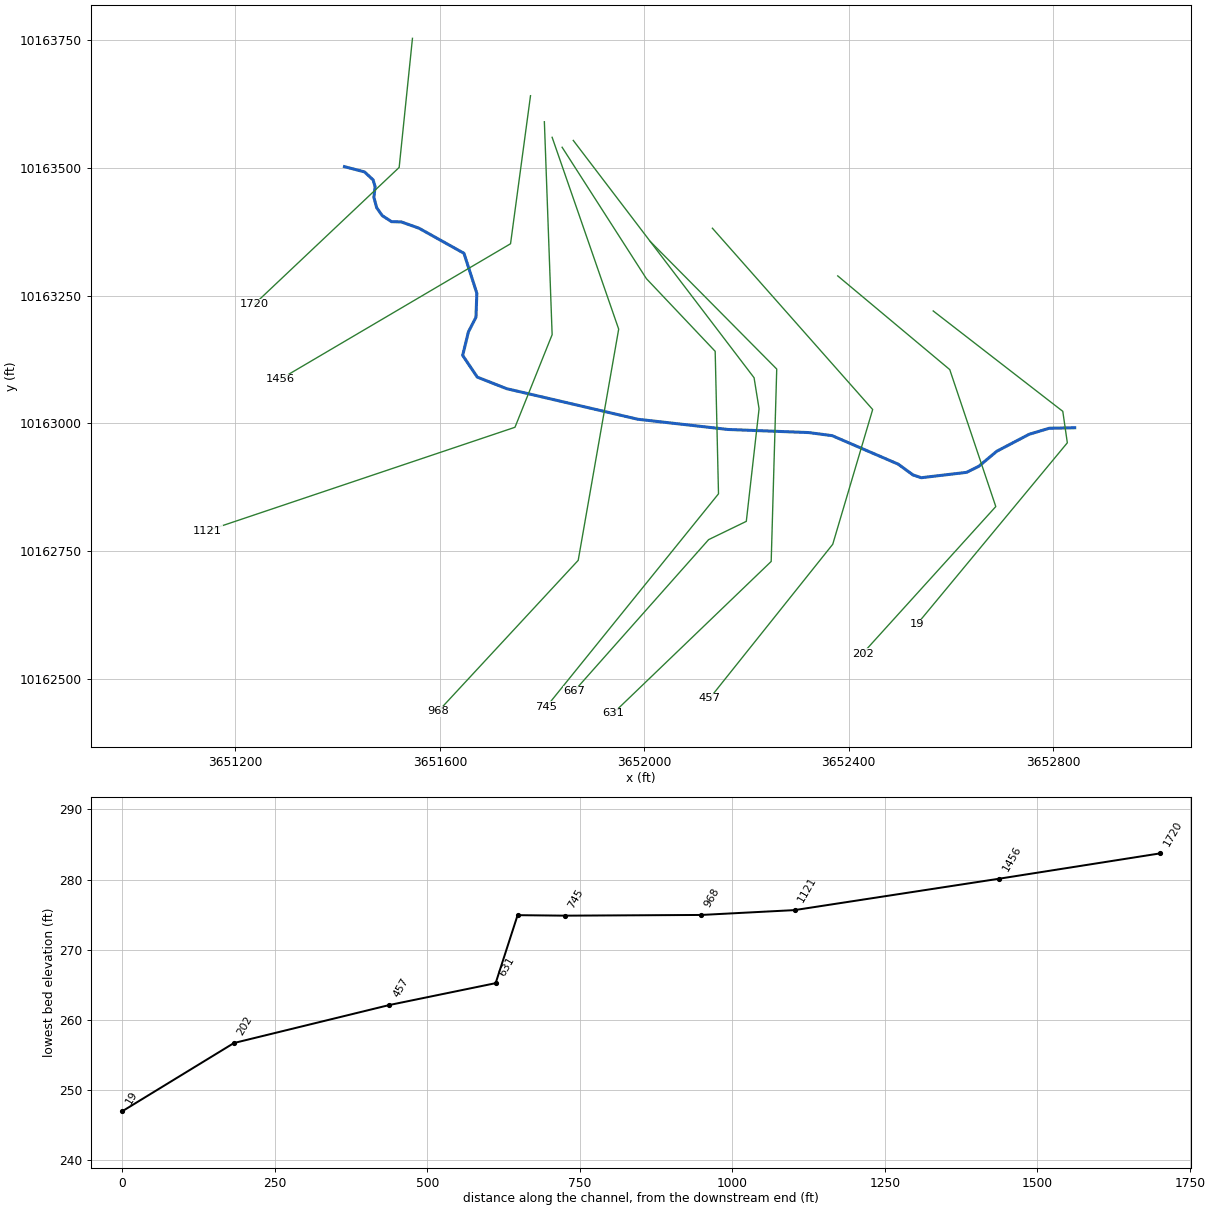
--- UNT111 IN ROCK.prj (project) ---

Proj Title=UNT111 IN ROCK Base Level Engineering
Current Plan=p01
Default Exp/Contr=0.3,0.1
English Units
Geom File=g01
Flow File=f01
Plan File=p01
Y Axis Title=Elevation
X Axis Title(PF)=Main Channel Distance
X Axis Title(XS)=Station
BEGIN DESCRIPTION:
UNT111 IN ROCK
END DESCRIPTION:
DSS Export Rating Curves= 0
DSS Export Rating Curve Sorted= 0
DSS Export Volume Flow Curves= 0
DXF OffsetX= 0
DXF OffsetY= 0
DXF ScaleX= 1
DXF ScaleY= 10

--- UNT111 IN ROCK.p01 (plan) ---

Plan Title=Multiple Run
Short Identifier=Multiple
Geom File=g01
Flow File=f01
Subcritical Flow
K Sum by GR= 0
Std Step Tol= 0.01
Critical Tol= 0.01
Num of Std Step Trials= 20
Max Error Tol= 0.3
Flow Tol Ratio= 0.001
Split Flow NTrial= 30
Split Flow Tol= 0.02
Split Flow Ratio= 0.02
Log Output Level= 0
Friction Slope Method= 1
Unsteady Friction Slope Method= 2
Unsteady Bridges Friction Slope Method= 1
Parabolic Critical Depth
Global Vel Dist=  1 , 1 , 1
Global Log Level= 0
CheckData=True
Encroach Param= -1, 0, 0, 0
BEGIN DESCRIPTION:
Multiple Run
END DESCRIPTION:

--- UNT111 IN ROCK.f01 (steady flow) ---

Flow Title=Multiple
Number of Profiles=7
Profile Names=10-year,25-year,50-year,1pct_min,100-year,1pct_plu,500-year
River Rch & RM= UNT111 IN ROCK,Reach-1,1720
     173     217     250     213     289     390     383
Boundary for River Rch & Prof#=UNT111 IN ROCK,Reach-1,1
Up Type=0
Dn Type=3
Dn Slope=0.005
Boundary for River Rch & Prof#=UNT111 IN ROCK,Reach-1,2
Up Type=0
Dn Type=3
Dn Slope=0.005
Boundary for River Rch & Prof#=UNT111 IN ROCK,Reach-1,3
Up Type=0
Dn Type=3
Dn Slope=0.005
Boundary for River Rch & Prof#=UNT111 IN ROCK,Reach-1,4
Up Type=0
Dn Type=3
Dn Slope=0.005
Boundary for River Rch & Prof#=UNT111 IN ROCK,Reach-1,5
Up Type=0
Dn Type=3
Dn Slope=0.005
Boundary for River Rch & Prof#=UNT111 IN ROCK,Reach-1,6
Up Type=0
Dn Type=3
Dn Slope=0.005
Boundary for River Rch & Prof#=UNT111 IN ROCK,Reach-1,7
Up Type=0
Dn Type=3
Dn Slope=0.005

--- UNT111 IN ROCK.g01 (geometry) ---

Geom Title=Existing Conditions

River Reach=UNT111 IN ROCK,Reach-1
Reach XY= 30
      3651413.24     10163502.60      3651452.39     10163492.35
      3651469.32     10163476.73      3651473.23     10163463.49
      3651470.84     10163442.66      3651476.26     10163422.26
      3651487.33     10163406.63      3651505.56     10163394.91
      3651524.33     10163394.50      3651559.16     10163382.11
      3651647.11     10163333.02      3651672.30     10163254.78
      3651670.56     10163207.90      3651655.81     10163179.26
      3651644.52     10163133.25      3651673.17     10163090.72
      3651730.46     10163068.15      3651987.40     10163008.25
      3652163.62     10162988.29      3652321.61     10162982.21
      3652367.61     10162976.13      3652496.61     10162920.45
      3652525.72     10162899.29      3652541.89     10162893.85
      3652630.62     10162904.37      3652654.56     10162916.32
      3652689.57     10162945.63      3652752.95     10162978.86
      3652792.21     10162990.65      3652842.11     10162991.64

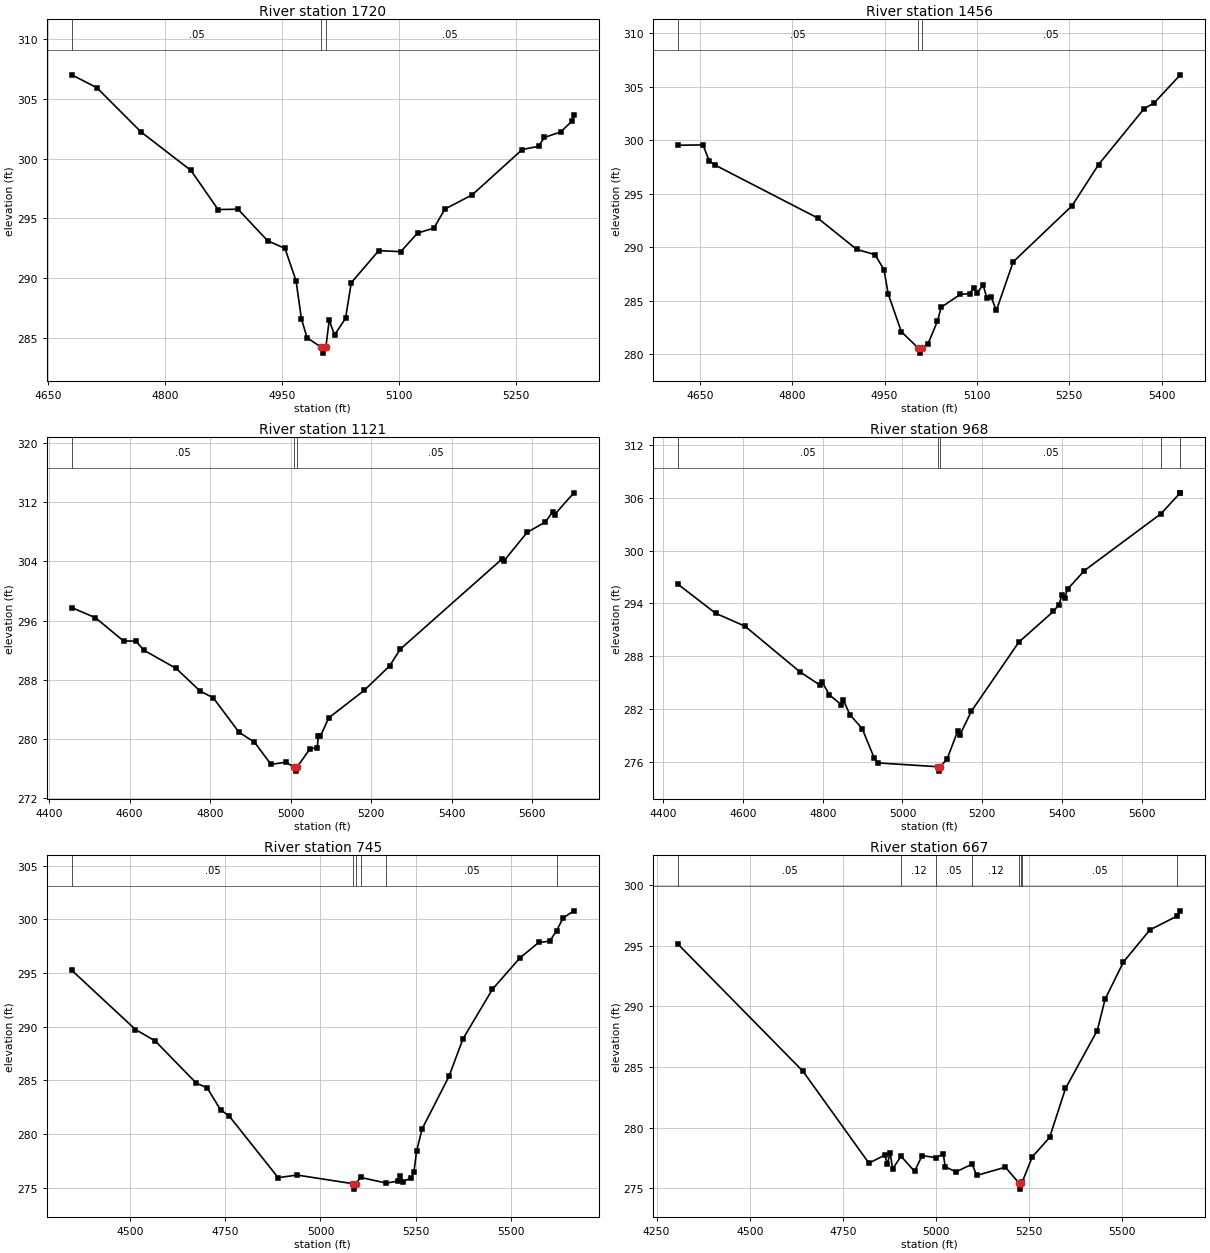
Type RM Length L Ch R = 1,1720,264,264,264
BEGIN DESCRIPTION:
UNT111 IN ROCK 6.0
END DESCRIPTION:
XS GIS Cut Line= 3
      3651546.32     10163753.71      3651520.28     10163501.06
      3651236.80     10163233.19
#Sta/Elev= 30
  4680.6  307.00  4712.8  305.92  4769.3  302.23  4833.5  299.00  4868.3  295.73
  4893.8  295.76  4931.8  293.12  4954.1  292.48  4968.3  289.76  4975.2  286.57
  4982.5  285.00  5000.5  284.22  5003.2  283.72  5006.5  284.22  5010.8  286.46
  5017.7  285.24  5031.8  286.64  5039.1  289.61  5074.3  292.29  5102.6  292.21
  5124.1  293.76  5145.1  294.18  5159.2  295.77  5194.4  296.97  5258.4  300.75
  5279.4  301.02  5286.7  301.76  5307.7  302.22  5321.9  303.11  5324.6  303.68
#Mann=3,-1,0
  4680.6    0.05       0  5000.5    0.03       0  5006.5    0.05       0
Bank Sta=5000.5,5006.5
Exp/Cntr=0.3,0.1

Type RM Length L Ch R = 1,1456,335,335,335
BEGIN DESCRIPTION:
Mapping XS 4bb555c9
END DESCRIPTION:
XS GIS Cut Line= 3
      3651777.29     10163641.46      3651738.23     10163351.74
      3651287.45     10163086.44
#Sta/Elev= 30
  4615.0  299.54  4655.2  299.57  4665.3  298.08  4675.4  297.67  4841.4  292.74
  4904.9  289.80  4934.5  289.32  4949.3  287.90  4955.9  285.65  4977.4  282.11
  5004.3  280.61  5007.0  280.11  5010.3  280.61  5020.3  280.94  5036.0  283.09
  5042.1  284.40  5073.1  285.60  5088.5  285.67  5094.6  286.24  5100.4  285.74
  5110.2  286.48  5116.0  285.30  5123.3  285.32  5131.7  284.11  5159.0  288.64
  5254.7  293.89  5297.6  297.73  5371.8  302.97  5387.5  303.47  5430.4  306.12
#Mann=3,-1,0
  4615.0    0.05       0  5004.3    0.03       0  5010.3    0.05       0
Bank Sta=5004.3,5010.3
Exp/Cntr=0.3,0.1

Type RM Length L Ch R = 1,1121,153,153,153
BEGIN DESCRIPTION:
Mapping XS 1e89342d
END DESCRIPTION:
XS GIS Cut Line= 4
      3651804.42     10163590.50      3651819.61     10163173.79
      3651746.91     10162992.58      3651145.36     10162790.26
#Sta/Elev= 30
  4456.5  297.76  4515.4  296.38  4585.4  293.23  4615.5  293.24  4635.5  291.99
  4715.5  289.54  4775.6  286.45  4807.7  285.57  4872.1  280.88  4910.3  279.55
  4951.2  276.56  4988.3  276.84  5009.5  276.14  5012.2  275.64  5015.5  276.14
  5048.2  278.67  5066.3  278.79  5068.5  280.36  5073.9  280.36  5094.9  282.85
  5183.0  286.57  5246.0  289.88  5272.3  292.13  5524.4  304.30  5529.6  304.06
  5587.4  307.93  5633.0  309.35  5650.4  310.68  5655.7  310.34  5703.4  313.28
#Mann=3,-1,0
  4456.5    0.05       0  5009.5    0.03       0  5015.5    0.05       0
Bank Sta=5009.5,5015.5
Exp/Cntr=0.3,0.1

Type RM Length L Ch R = 1,968,223,223,223
BEGIN DESCRIPTION:
Mapping XS 4af1fbcd
END DESCRIPTION:
XS GIS Cut Line= 4
      3651819.62     10163560.03      3651949.82     10163184.64
      3651870.61     10162732.16      3651596.94     10162436.86
#Sta/Elev= 30
  4437.6  296.16  4531.2  292.89  4605.2  291.41  4742.8  286.23  4793.3  284.72
  4798.6  285.06  4816.9  283.61  4846.9  282.48  4851.9  282.98  4868.4  281.35
  4898.9  279.79  4929.3  276.42  4939.5  275.88  5088.8  275.45  5091.5  274.95
  5094.8  275.45  5112.1  276.34  5139.0  279.56  5144.1  279.07  5173.0  281.77
  5292.0  289.61  5378.3  293.09  5392.5  293.85  5399.8  294.95  5406.7  294.62
  5414.0  295.62  5456.5  297.74  5648.3  304.19  5695.7  306.52  5696.9  306.57
#Mann=5,-1,0
  4437.6    0.05       0  5088.8   0.033       0  5094.8    0.05       0
  5648.3    0.08       0  5695.7    0.05       0
Bank Sta=5088.8,5094.8
Exp/Cntr=0.3,0.1

Type RM Length L Ch R = 1,745,78,78,78
BEGIN DESCRIPTION:
Mapping XS d9ca9446
END DESCRIPTION:
XS GIS Cut Line= 5
      3651839.13     10163540.55      3652004.07     10163283.38
      3652138.62     10163141.23      3652145.13     10162862.37
      3651808.50     10162445.64
#Sta/Elev= 30
  4348.2  295.24  4515.2  289.72  4566.7  288.66  4674.7  284.72  4703.0  284.29
  4738.6  282.21  4759.7  281.71  4889.0  275.92  4939.1  276.16  5086.1  275.35
  5088.9  274.85  5092.1  275.35  5105.0  275.94  5173.0  275.41  5202.4  275.60
  5208.8  276.03  5216.8  275.56  5237.6  275.90  5245.0  276.43  5252.0  278.40
  5266.4  280.46  5336.8  285.35  5373.5  288.85  5450.7  293.47  5522.2  296.37
  5571.8  297.83  5600.6  297.95  5619.2  298.94  5635.8  300.11  5664.1  300.78
#Mann=6,-1,0
  4348.2    0.05       0  5086.1   0.033       0  5092.1    0.05       0
  5105.0    0.12       0  5173.0    0.05       0  5619.2    0.08       0
Bank Sta=5086.1,5092.1
Exp/Cntr=0.3,0.1

Type RM Length L Ch R = 1,667,36,36,36
BEGIN DESCRIPTION:
Mapping XS 3b99bcd6
END DESCRIPTION:
XS GIS Cut Line= 6
      3651860.99     10163553.90      3652214.72     10163089.50
      3652224.49     10163028.73      3652199.53     10162808.46
      3652125.74     10162772.66      3651862.64     10162475.99
#Sta/Elev= 30
  4308.1  295.10  4642.9  284.64  4820.0  277.06  4862.6  277.73  4869.4  276.97
  4876.8  277.94  4883.5  276.58  4906.0  277.63  4942.5  276.39  4962.7  277.68
  5000.5  277.52  5019.6  277.83  5024.6  276.77  5053.3  276.34  5097.0  276.98
  5109.3  276.05  5186.3  276.73  5222.8  275.42  5225.6  274.92  5228.8  275.42
  5231.6  275.52  5258.5  277.58  5304.9  279.18  5347.6  283.22  5432.9  288.00
  5453.8  290.57  5503.1  293.65  5574.2  296.30  5648.0  297.45  5655.8  297.87
#Mann=8,-1,0
  4308.1    0.05       0  4906.0    0.12       0  5000.5    0.05       0
  5097.0    0.12       0  5222.8    0.07       0  5228.8    0.12       0
  5231.6    0.05       0  5648.0    0.08       0
Bank Sta=5222.8,5228.8
Exp/Cntr=0.3,0.1

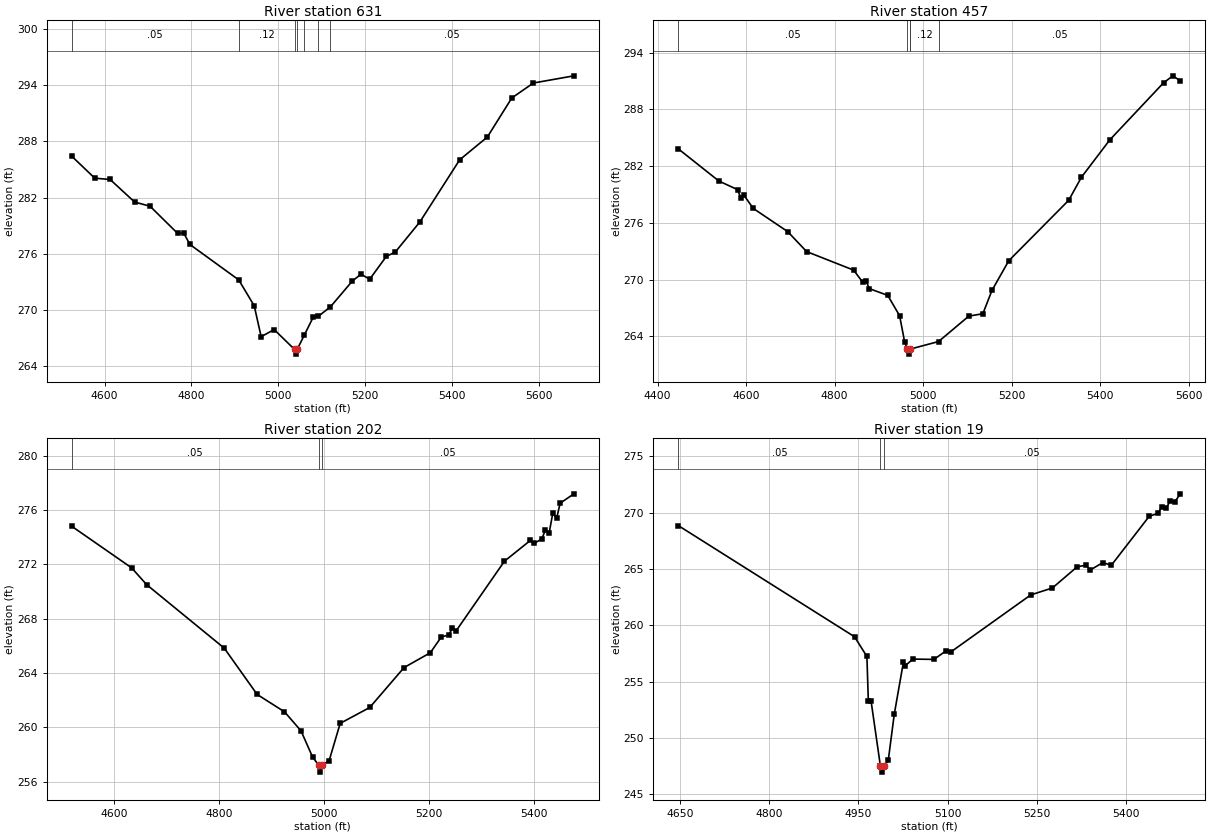
Type RM Length L Ch R = 1,631,174,174,174
BEGIN DESCRIPTION:
Mapping XS d8fc3180
END DESCRIPTION:
XS GIS Cut Line= 4
      3652011.63     10163356.11      3652259.06     10163106.51
      3652248.21     10162729.99      3651938.98     10162432.69
#Sta/Elev= 30
  4524.2  286.42  4577.2  284.07  4612.6  283.93  4669.1  281.51  4704.5  281.07
  4768.1  278.16  4782.3  278.18  4796.4  276.97  4908.9  273.18  4944.6  270.41
  4960.6  267.10  4990.6  267.86  5037.6  265.73  5040.3  265.23  5043.6  265.73
  5060.4  267.30  5080.6  269.19  5092.3  269.28  5120.2  270.29  5170.6  273.05
  5190.7  273.79  5210.7  273.25  5249.0  275.69  5269.7  276.16  5326.3  279.38
  5418.1  286.04  5481.9  288.48  5538.2  292.66  5587.9  294.26  5681.3  295.03
#Mann=7,-1,0
  4524.2    0.05       0  4908.9    0.12       0  5037.6    0.07       0
  5043.6    0.12       0  5060.4    0.05       0  5092.3    0.12       0
  5120.2    0.05       0
Bank Sta=5037.6,5043.6
Exp/Cntr=0.3,0.1

Type RM Length L Ch R = 1,457,255,255,255
BEGIN DESCRIPTION:
Mapping XS 7d62c58a
END DESCRIPTION:
XS GIS Cut Line= 4
      3652133.21     10163382.10      3652446.78     10163027.30
      3652368.66     10162763.63      3652127.79     10162462.01
#Sta/Elev= 30
  4446.7  283.83  4538.6  280.42  4580.8  279.51  4588.0  278.66  4594.6  278.96
  4616.4  277.52  4694.2  275.07  4736.9  272.96  4843.1  271.00  4864.0  269.70
  4871.5  269.86  4878.2  269.05  4920.2  268.33  4947.0  266.18  4958.4  263.40
  4964.8  262.62  4967.6  262.12  4970.8  262.62  4971.5  262.66  5035.0  263.45
  5103.4  266.14  5135.1  266.39  5155.6  268.85  5193.6  271.99  5329.0  278.38
  5357.8  280.82  5421.9  284.77  5543.3  290.80  5564.4  291.54  5581.2  291.01
#Mann=5,-1,0
  4446.7    0.05       0  4964.8    0.07       0  4970.8    0.05       0
  4971.5    0.12       0  5035.0    0.05       0
Bank Sta=4964.8,4970.8
Exp/Cntr=0.3,0.1

Type RM Length L Ch R = 1,202,183,183,183
BEGIN DESCRIPTION:
Mapping XS 9a44baa6
END DESCRIPTION:
XS GIS Cut Line= 4
      3652378.43     10163288.80      3652597.61     10163105.43
      3652687.67     10162837.41      3652427.22     10162549.83
#Sta/Elev= 30
  4519.0  274.80  4633.0  271.74  4661.7  270.50  4809.4  265.83  4872.1  262.42
  4924.2  261.14  4955.7  259.74  4977.6  257.82  4989.5  257.20  4992.2  256.70
  4995.5  257.20  5009.2  257.54  5030.3  260.29  5086.6  261.46  5152.0  264.40
  5202.0  265.49  5222.9  266.65  5237.1  266.80  5243.9  267.29  5251.3  267.11
  5343.2  272.23  5392.6  273.76  5400.0  273.55  5414.2  273.86  5421.0  274.50
  5428.4  274.31  5435.2  275.76  5442.6  275.39  5449.3  276.50  5475.5  277.19
#Mann=3,-1,0
  4519.0    0.05       0  4989.5    0.03       0  4995.5    0.05       0
Bank Sta=4989.5,4995.5
Exp/Cntr=0.3,0.1

Type RM Length L Ch R = 1,19,0,0,0
BEGIN DESCRIPTION:
Mapping XS fa5ff3a0.1
END DESCRIPTION:
XS GIS Cut Line= 4
      3652565.24     10163220.22      3652818.77     10163023.76
      3652827.64     10162962.20      3652533.42     10162606.94
#Sta/Elev= 30
  4646.9  268.86  4943.4  258.99  4964.2  257.24  4966.6  253.29  4971.2  253.29
  4987.0  247.48  4989.7  246.98  4993.0  247.48  5000.1  248.02  5010.2  252.12
  5025.7  256.77  5028.0  256.40  5041.7  257.01  5076.9  256.98  5097.7  257.76
  5105.5  257.65  5239.6  262.70  5276.1  263.32  5317.8  265.20  5332.1  265.33
  5340.0  264.92  5360.8  265.57  5375.1  265.33  5438.9  269.68  5453.3  269.93
  5459.7  270.48  5467.6  270.42  5474.1  271.04  5481.9  270.96  5491.1  271.67
#Mann=3,-1,0
  4646.9    0.05       0  4987.0    0.03       0  4993.0    0.05       0
Bank Sta=4987,4993
Exp/Cntr=0.3,0.1

Chan Stop Cuts=-1