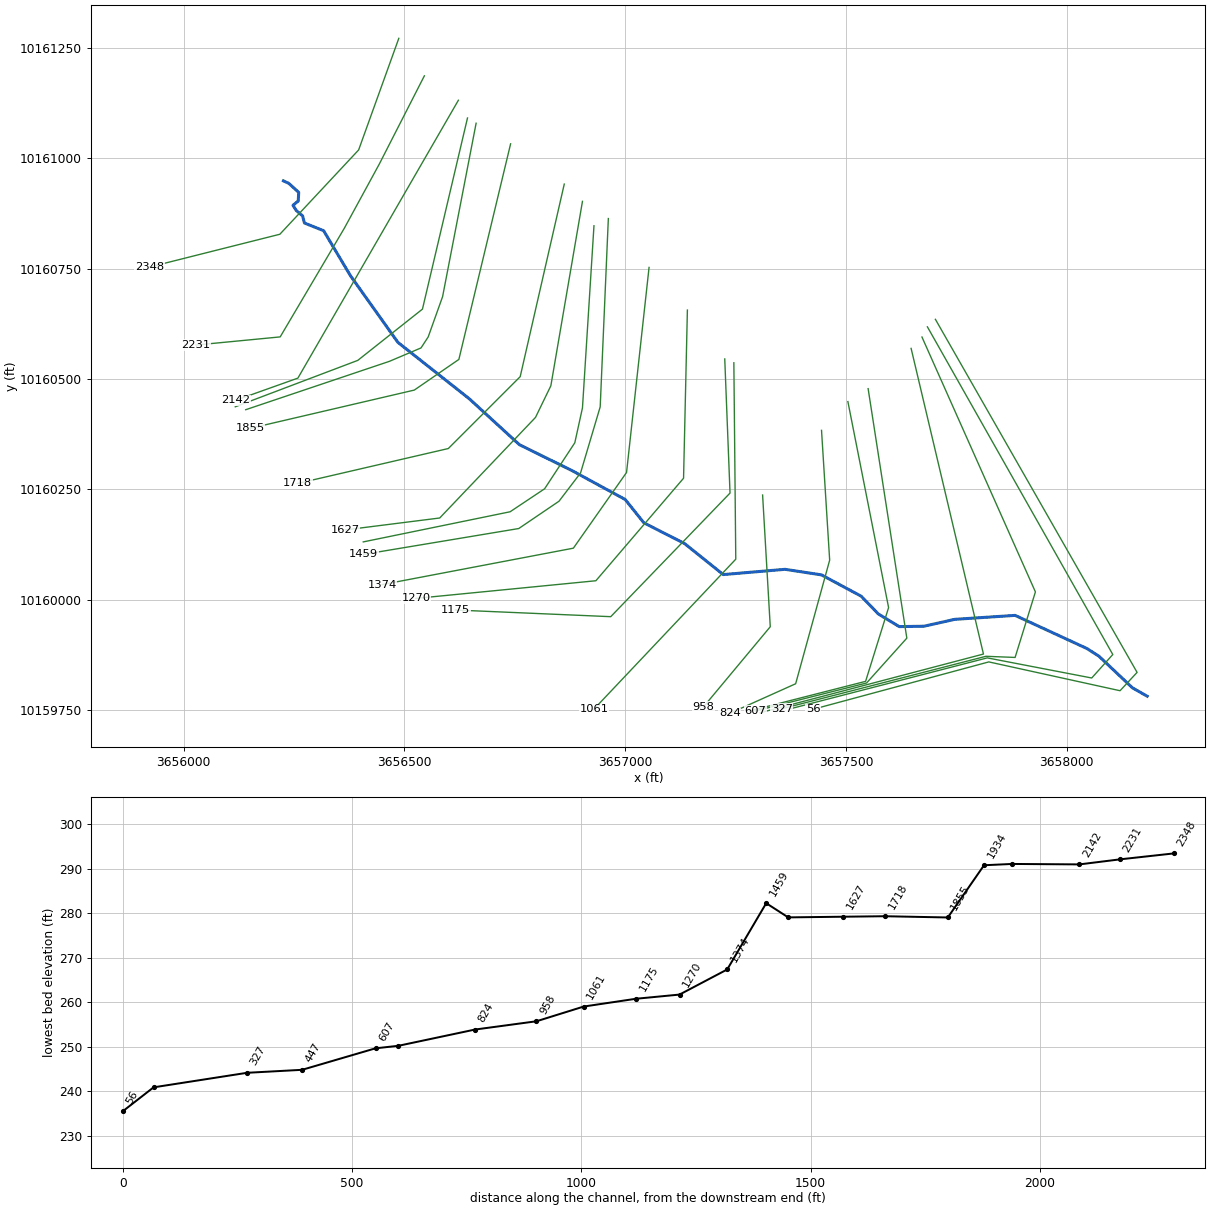
--- UNT112 IN ROCK.prj (project) ---

Proj Title=UNT112 IN ROCK Base Level Engineering
Current Plan=p01
Default Exp/Contr=0.3,0.1
English Units
Geom File=g01
Flow File=f01
Plan File=p01
Y Axis Title=Elevation
X Axis Title(PF)=Main Channel Distance
X Axis Title(XS)=Station
BEGIN DESCRIPTION:
UNT112 IN ROCK
END DESCRIPTION:
DSS Export Rating Curves= 0
DSS Export Rating Curve Sorted= 0
DSS Export Volume Flow Curves= 0
DXF OffsetX= 0
DXF OffsetY= 0
DXF ScaleX= 1
DXF ScaleY= 10

--- UNT112 IN ROCK.p01 (plan) ---

Plan Title=Multiple Run
Short Identifier=Multiple
Geom File=g01
Flow File=f01
Subcritical Flow
K Sum by GR= 0
Std Step Tol= 0.01
Critical Tol= 0.01
Num of Std Step Trials= 20
Max Error Tol= 0.3
Flow Tol Ratio= 0.001
Split Flow NTrial= 30
Split Flow Tol= 0.02
Split Flow Ratio= 0.02
Log Output Level= 0
Friction Slope Method= 1
Unsteady Friction Slope Method= 2
Unsteady Bridges Friction Slope Method= 1
Parabolic Critical Depth
Global Vel Dist=  1 , 1 , 1
Global Log Level= 0
CheckData=True
Encroach Param= -1, 0, 0, 0
BEGIN DESCRIPTION:
Multiple Run
END DESCRIPTION:

--- UNT112 IN ROCK.f01 (steady flow) ---

Flow Title=Multiple
Program Version=4.10
Number of Profiles= 7
Profile Names=10-year,25-year,50-year,1pct_min,100-year,1pct_plu,500-year
River Rch & RM=UNT112 IN ROCK,Reach-1         ,2348
     140     172     195     165     223     301     287
Boundary for River Rch & Prof#=UNT112 IN ROCK,Reach-1         , 1
Up Type= 0
Dn Type= 3
Dn Slope=0.022
Boundary for River Rch & Prof#=UNT112 IN ROCK,Reach-1         , 2
Up Type= 0
Dn Type= 3
Dn Slope=0.022
Boundary for River Rch & Prof#=UNT112 IN ROCK,Reach-1         , 3
Up Type= 0
Dn Type= 3
Dn Slope=0.022
Boundary for River Rch & Prof#=UNT112 IN ROCK,Reach-1         , 4
Up Type= 0
Dn Type= 3
Dn Slope=0.022
Boundary for River Rch & Prof#=UNT112 IN ROCK,Reach-1         , 5
Up Type= 0
Dn Type= 3
Dn Slope=0.022
Boundary for River Rch & Prof#=UNT112 IN ROCK,Reach-1         , 6
Up Type= 0
Dn Type= 3
Dn Slope=0.022
Boundary for River Rch & Prof#=UNT112 IN ROCK,Reach-1         , 7
Up Type= 0
Dn Type= 3
Dn Slope=0.022
DSS Import GetInterval= 0
DSS Import GetPeak= 0
DSS Import FillOption= 0

--- UNT112 IN ROCK.g01 (geometry) ---

Geom Title=Existing Conditions
Program Version=4.10

River Reach=UNT112 IN ROCK  ,Reach-1
Reach XY= 30
      3656225.75     10160948.76      3656237.68     10160943.33
      3656260.47     10160922.72      3656259.39     10160903.18
      3656247.45     10160893.42      3656255.04     10160881.48
      3656269.15     10160869.55      3656273.49     10160853.27
      3656316.89     10160835.91      3656377.66     10160733.91
      3656485.04     10160583.05       3656646.5     10160455.45
      3656760.21     10160351.28      3656880.01     10160292.25
       3656999.8     10160227.15      3657042.33      10160174.2
      3657134.35     10160127.32      3657222.02     10160057.01
      3657361.97     10160068.92      3657444.43     10160056.34
      3657534.28     10160008.16      3657573.34     10159967.79
      3657620.65     10159939.15      3657676.64     10159940.02
      3657746.52     10159955.64      3657883.06     10159964.59
       3658045.8     10159889.48      3658072.96     10159872.13
      3658148.78     10159800.52      3658182.19     10159781.61

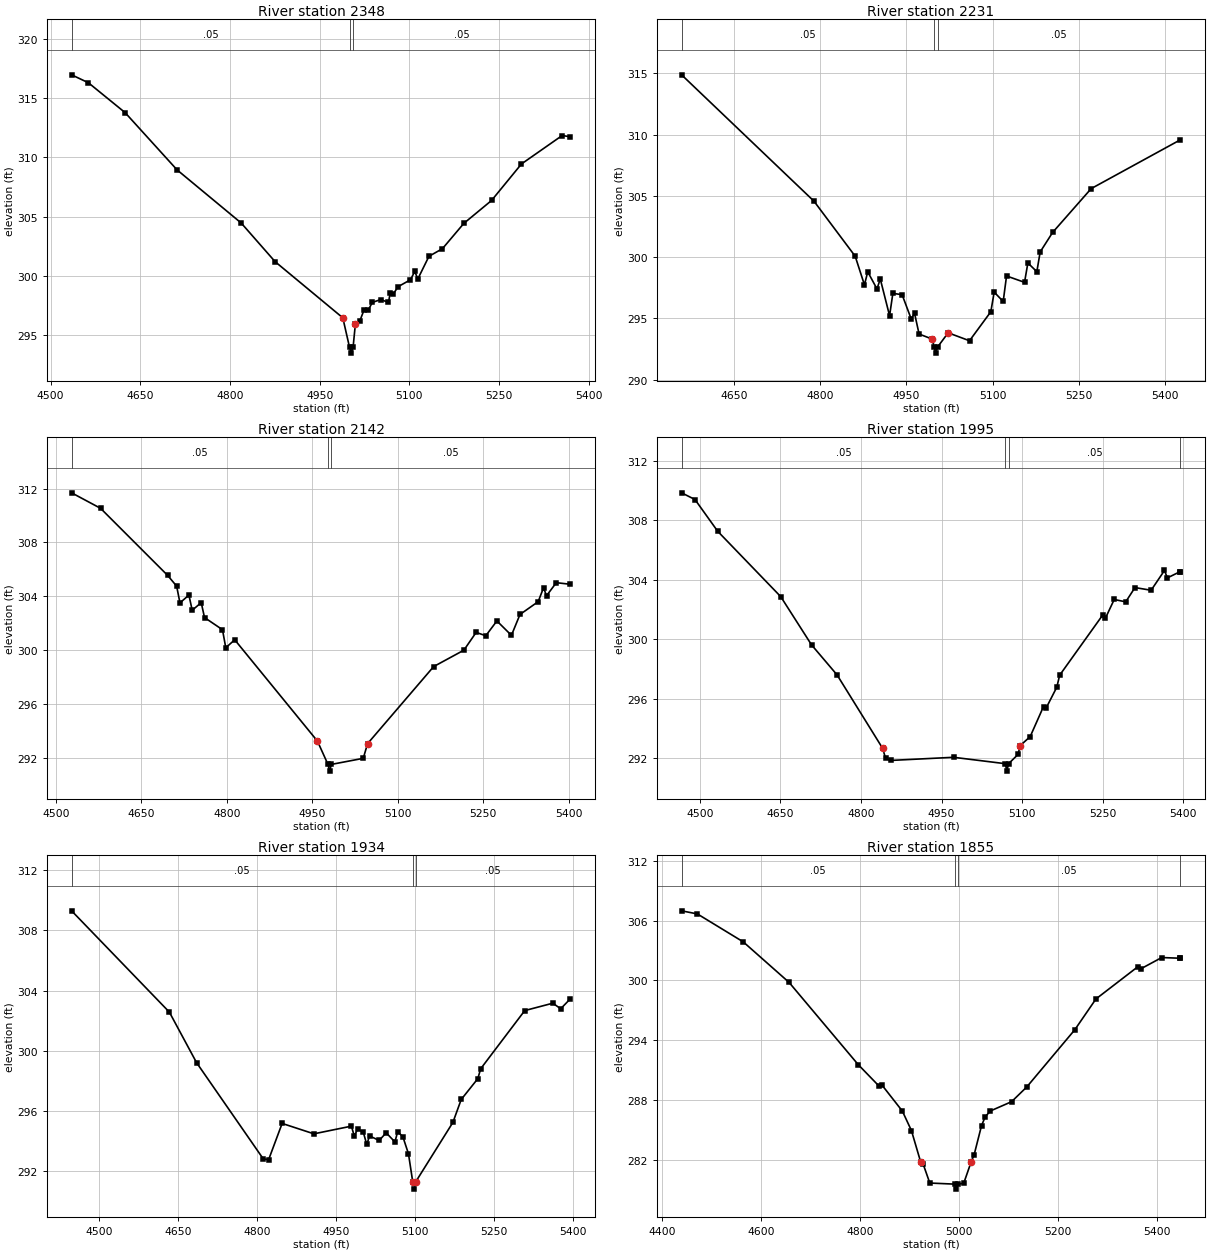
Type RM Length L Ch R = 1 ,2348    ,117,117,117
BEGIN DESCRIPTION:
UNT112 IN ROCK 7.0
END DESCRIPTION:
XS GIS Cut Line= 4
      3656487.18     10161271.58      3656396.21     10161018.81
      3656217.74     10160827.84      3655922.58     10160753.53
#Sta/Elev= 30
  4535.1  316.97  4563.2   316.3  4624.6  313.78  4711.5  308.95  4818.7  304.47
  4875.4  301.21  4988.7  296.47  4999.9  293.99  5002.7  293.49  5005.9  293.99
  5009.7  295.93  5017.1   296.2  5023.9  297.09  5031.2  297.12  5038.1  297.77
  5052.2  298.01  5065.1  297.77  5067.9  298.55  5073.1  298.48  5081.3   299.1
  5101.9  299.68    5109  300.38  5114.2  299.75  5132.8  301.66  5155.3   302.3
  5191.2  304.44  5237.5  306.37  5287.5  309.45  5355.6  311.85  5369.5  311.74
#Mann= 3 ,-1 , 0
  4535.1     .05       0  4999.9     .03       0  5005.9     .05       0
Bank Sta=4988.7,5009.7
XS Rating Curve= 0 ,0
Exp/Cntr=0.3,0.1

Type RM Length L Ch R = 1 ,2231    ,89,89,89
BEGIN DESCRIPTION:
UNT112 IN ROCK 6.0
END DESCRIPTION:
XS GIS Cut Line= 5
      3656545.07     10161186.66       3656443.1     10160987.05
      3656363.89     10160841.65      3656218.49     10160595.34
      3656027.52      10160576.9
#Sta/Elev= 30
  4559.3  314.88  4789.6  304.56  4861.2  300.07  4877.3  297.73    4883   298.8
  4899.1   297.4  4904.8  298.22    4921  295.21  4926.7  297.04  4942.8  296.93
  4958.6  294.95  4964.4  295.42  4972.3  293.72  4995.5   293.3  4998.5  292.66
  5001.2  292.16  5004.5  292.66  5022.9  293.82    5060  293.17  5097.1  295.54
  5102.9  297.14  5118.6  296.38  5124.4  298.46  5155.7  297.94  5161.5  299.52
  5177.1  298.81  5182.9  300.42  5204.5  302.01  5271.6  305.59  5426.9  309.58
#Mann= 3 ,-1 , 0
  4559.3     .05       0  4998.5     .03       0  5004.5     .05       0
Bank Sta=4995.5,5022.9
XS Rating Curve= 0 ,0
Exp/Cntr=0.3,0.1

Type RM Length L Ch R = 1 ,2142    ,147,147,147
BEGIN DESCRIPTION:
UNT112 IN ROCK 5.3
END DESCRIPTION:
XS GIS Cut Line= 3
      3656622.11     10161131.33      3656258.64     10160502.02
       3656118.7     10160452.12
#Sta/Elev= 30
  4527.7  311.68  4578.5  310.53  4696.2  305.55    4712  304.75  4717.8  303.51
  4733.5  304.09  4739.3  302.96  4755.1  303.53  4760.9  302.42  4792.4  301.52
  4798.2  300.18  4813.9  300.77    4959  293.25  4977.5  291.52  4980.3  291.02
  4983.5  291.52  5039.4  291.97    5047  293.06  5162.9  298.78    5216     300
  5237.5  301.32  5254.4  301.07  5273.9  302.17  5299.4   301.1  5314.4  302.65
  5346.3   303.6  5355.7  304.63    5361  304.04  5378.1  305.01    5403  304.89
#Mann= 3 ,-1 , 0
  4527.7     .05       0  4977.5     .03       0  4983.5     .05       0
Bank Sta=4959,5047
XS Rating Curve= 0 ,0
Exp/Cntr=0.3,0.1

Type RM Length L Ch R = 1 ,1995    ,61,61,61
BEGIN DESCRIPTION:
UNT112 IN ROCK 5.2
END DESCRIPTION:
XS GIS Cut Line= 4
      3656642.75     10161091.19      3656540.75     10160658.27
      3656394.27     10160542.17      3656116.81     10160437.04
#Sta/Elev= 30
  4466.1  309.83    4491  309.38  4533.4  307.24  4650.6  302.85  4707.9  299.61
  4755.4  297.59  4840.1  292.66  4845.8  291.97    4856  291.84  4972.2  292.05
  5068.6  291.62  5071.3  291.12  5074.6  291.62  5092.4  292.25    5096  292.83
  5114.8  293.44  5139.6  295.46  5144.9  295.39  5164.3  296.76  5169.7  297.57
  5249.5   301.6  5254.8   301.4  5271.2  302.66  5292.6   302.5  5309.8  303.46
  5339.9  303.28  5364.7  304.61  5370.1  304.11  5394.3  304.54  5394.5  304.54
#Mann= 4 ,-1 , 0
  4466.1     .05       0  5068.6     .03       0  5074.6     .05       0
  5394.3     .08       0
Bank Sta=4840.1,5096
XS Rating Curve= 0 ,0
Exp/Cntr=0.3,0.1

Type RM Length L Ch R = 1 ,1934    ,79,79,79
BEGIN DESCRIPTION:
UNT112 IN ROCK 5.0
END DESCRIPTION:
XS GIS Cut Line= 6
      3656662.28     10161079.28      3656586.33     10160686.49
      3656553.77     10160595.34       3656537.5     10160570.38
      3656465.88       10160540.      3656140.38     10160430.42
#Sta/Elev= 30
  4447.6   309.3  4633.3  302.58  4685.1  299.22  4811.9  292.83    4822  292.79
  4847.6  295.19    4908   294.5  4979.3  295.01  4984.7  294.35    4991  294.81
  5001.8  294.61  5008.4   293.8  5013.8  294.36    5032  294.06  5045.3  294.57
  5061.9  293.96  5067.2  294.65  5077.1   294.3  5087.7  293.17  5095.7  291.33
  5098.5  290.83  5101.7  291.33  5172.1  295.26  5187.9  296.78  5219.4  298.16
  5224.9  298.82  5308.6  302.68    5362  303.17  5376.9   302.8  5395.5  303.47
#Mann= 3 ,-1 , 0
  4447.6     .05       0  5095.7     .03       0  5101.7     .05       0
Bank Sta=5095.7,5101.7
XS Rating Curve= 0 ,0
Exp/Cntr=0.3,0.1

Type RM Length L Ch R = 1 ,1855    ,137,137,137
BEGIN DESCRIPTION:
UNT112 IN ROCK 5.1
END DESCRIPTION:
XS GIS Cut Line= 4
       3656740.4      10161032.6      3656623.22     10160544.34
      3656522.31      10160474.9      3656150.11     10160388.09
#Sta/Elev= 30
    4440  306.97  4471.8  306.66  4564.4  303.86  4656.9   299.8  4796.3  291.57
  4838.3  289.42  4843.5  289.57  4885.5  286.91  4903.8  284.96  4922.3  281.84
  4927.5   281.6  4940.9   279.7  4991.5  279.59  4994.3  279.09  4997.5  279.59
  5009.4  279.68  5024.3  281.81  5030.4  282.54  5045.3  285.45  5052.7  286.33
  5063.1  286.92    5106  287.85  5136.7  289.33  5233.6  295.06  5276.2  298.14
  5361.3  301.39  5366.4  301.15    5409  302.29  5446.6  302.22  5446.8  302.22
#Mann= 4 ,-1 , 0
    4440     .05       0  4991.5     .03       0  4997.5     .05       0
  5446.6     .08       0
Bank Sta=4922.3,5024.3
XS Rating Curve= 0 ,0
Exp/Cntr=0.3,0.1

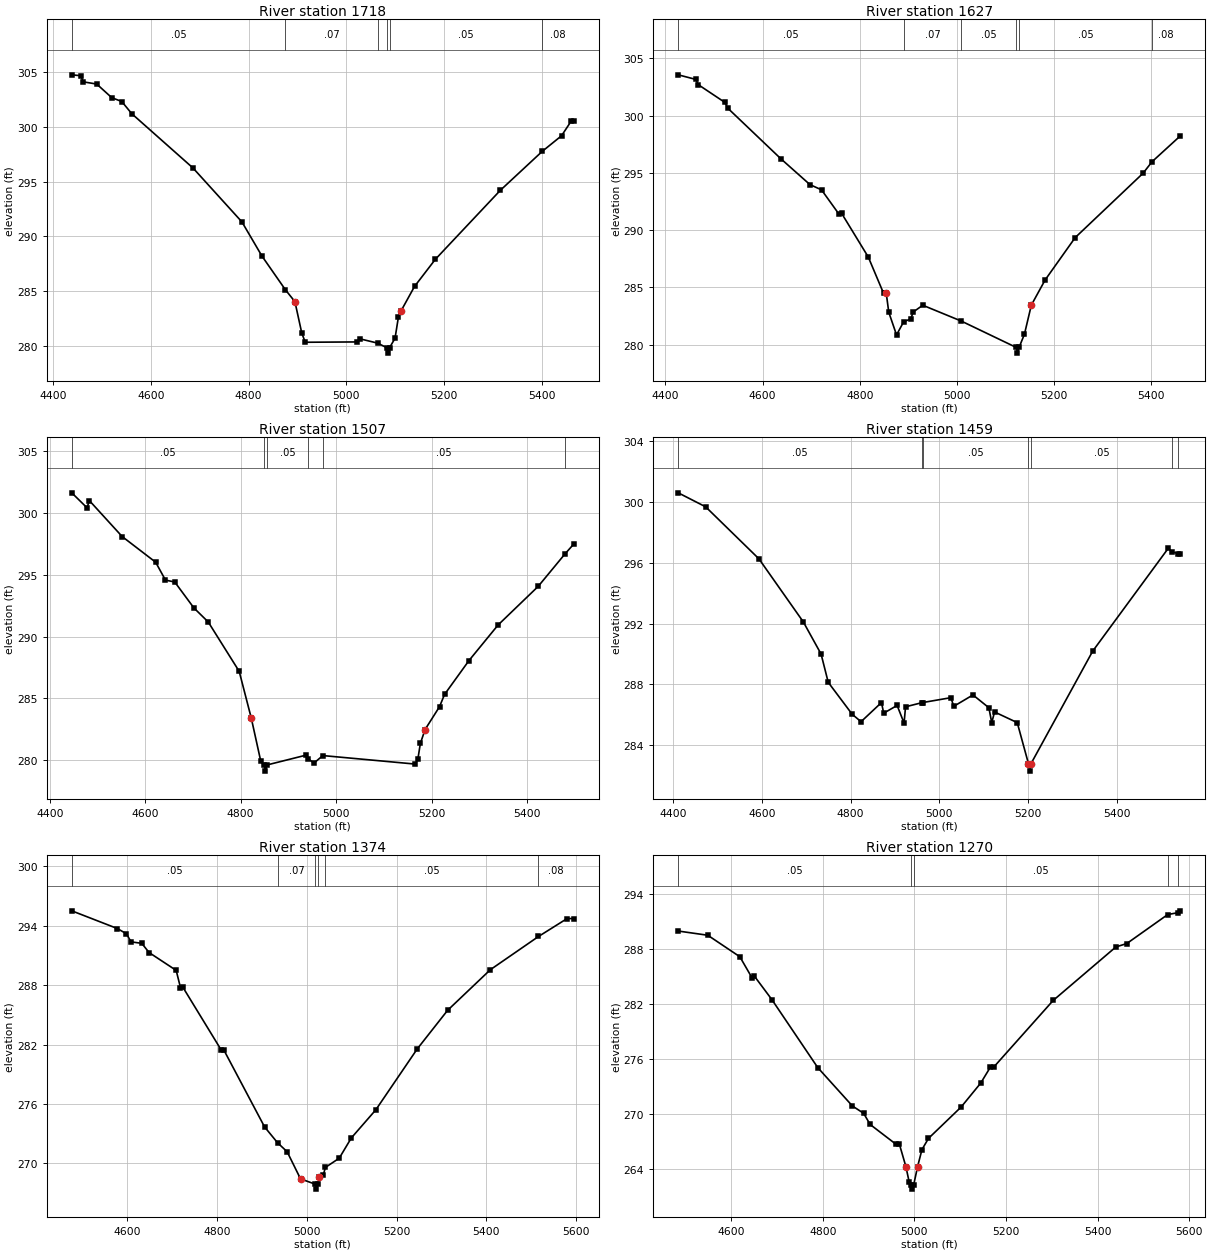
Type RM Length L Ch R = 1 ,1718    ,91,91,91
BEGIN DESCRIPTION:
UNT112 IN ROCK 4.4
END DESCRIPTION:
XS GIS Cut Line= 4
      3656861.93     10160941.46      3656762.11     10160505.28
      3656599.35     10160342.52      3656257.54     10160263.31
#Sta/Elev= 30
  4437.6  304.72    4456  304.64  4461.1  304.08  4488.7  303.88  4519.5  302.64
    4540  302.29  4560.5  301.18    4686  296.23  4786.2  291.32  4827.2  288.21
  4875.4  285.13  4894.7  284.06  4908.8  281.19  4915.9  280.36    5022  280.39
    5029  280.66  5064.2  280.28  5082.6  279.87  5085.4  279.37  5088.6  279.87
  5099.8  280.72  5106.8  282.68  5112.3  283.23  5139.7  285.44  5182.3  287.91
  5315.5   294.2  5401.4  297.75  5440.9  299.17  5461.2  300.54  5466.1  300.54
#Mann= 6 ,-1 , 0
  4437.6     .05       0  4875.4     .07       0  5064.2     .05       0
  5082.6     .07       0  5088.6     .05       0  5401.4     .08       0
Bank Sta=4894.7,5112.3
XS Rating Curve= 0 ,0
Exp/Cntr=0.3,0.1

Type RM Length L Ch R = 1 ,1627    ,120,120,120
BEGIN DESCRIPTION:
UNT112 IN ROCK 4.5
END DESCRIPTION:
XS GIS Cut Line= 5
      3656903.16     10160902.39      3656831.55     10160484.66
      3656796.83     10160413.05      3656579.82     10160185.18
      3656365.99     10160158.19
#Sta/Elev= 30
  4426.3  303.55  4462.4  303.15  4467.6  302.69  4522.4  301.14  4528.5  300.63
  4637.4  296.23  4697.4  293.97  4721.3  293.51  4757.4  291.38  4762.5  291.47
  4817.5  287.65  4849.1  284.47  4854.6  284.47  4859.7  282.83  4875.7  280.85
  4890.3  281.99  4904.8  282.25  4910.4  282.86  4929.7  283.44  5008.9  282.06
    5122  279.76  5124.7  279.26    5128  279.76    5139  280.91  5153.2  283.45
  5181.5  285.64  5243.4  289.34  5383.2  294.96  5401.8  295.97  5459.9  298.22
#Mann= 6 ,-1 , 0
  4426.3     .05       0  4890.3     .07       0  5008.9     .05       0
    5122     .07       0    5128     .05       0  5401.8     .08       0
Bank Sta=4854.6,5153.2
XS Rating Curve= 0 ,0
Exp/Cntr=0.3,0.1

Type RM Length L Ch R = 1 ,1507    ,48,48,48
BEGIN DESCRIPTION:
UNT112 IN ROCK 4.3
END DESCRIPTION:
XS GIS Cut Line= 6
      3656929.21     10160847.05      3656903.17     10160434.75
      3656885.81     10160355.54      3656817.45     10160251.37
      3656739.32     10160199.29      3656406.66     10160131.02
#Sta/Elev= 30
    4446  301.65  4477.9  300.44  4482.9  301.02  4551.6  298.11  4621.8  296.03
  4642.4  294.58  4661.8  294.43  4701.9  292.33    4732  291.19  4796.9  287.19
  4822.2  283.41  4842.2   279.9  4849.2  279.61    4852  279.11  4855.2  279.61
  4936.6   280.4  4941.7  280.11  4953.5  279.76  4972.3  280.37  5166.1  279.68
  5171.5  280.11  5176.6  281.35  5186.5  282.48  5216.8  284.33  5227.3  285.32
  5278.4  288.06  5339.6  290.95  5423.5  294.07  5479.7   296.7  5498.3  297.51
#Mann= 6 ,-1 , 0
    4446     .05       0  4849.2     .03       0  4855.2     .05       0
  4941.7     .07       0  4972.3     .05       0  5479.7     .08       0
Bank Sta=4822.2,5186.5
XS Rating Curve= 0 ,0
Exp/Cntr=0.3,0.1

Type RM Length L Ch R = 1 ,1459    ,85,85,85
BEGIN DESCRIPTION:
UNT112 IN ROCK 4.8
END DESCRIPTION:
XS GIS Cut Line= 6
      3656961.76     10160863.38      3656943.31     10160436.92
      3656898.83     10160287.18        3656850.     10160223.16
      3656758.85     10160161.31      3656407.34     10160102.73
#Sta/Elev= 30
  4411.5   300.6  4473.3  299.68  4593.4  296.26  4693.5  292.11  4733.5     290
  4749.6  288.14  4803.6  286.04  4823.6  285.55  4869.6  286.81  4874.7  286.11
  4904.9  286.62  4920.6  285.46  4923.9  286.53  4960.6   286.8  4962.6  286.81
  5026.2  287.13  5032.5  286.56  5075.9  287.31  5111.7  286.47  5118.2  285.49
  5124.6  286.19  5175.7  285.49  5200.9   282.8  5203.7   282.3  5206.9   282.8
  5345.8  290.19  5516.3  296.96  5524.4  296.71    5539  296.61  5543.3  296.61
#Mann= 7 ,-1 , 0
  4411.5     .05       0  4960.6     .07       0  4962.6     .05       0
  5200.9     .03       0  5206.9     .05       0  5524.4     .08       0
    5539     .05       0
Bank Sta=5200.9,5206.9
XS Rating Curve= 0 ,0
Exp/Cntr=0.3,0.1

Type RM Length L Ch R = 1 ,1374    ,104,104,104
BEGIN DESCRIPTION:
UNT112 IN ROCK 4.1
END DESCRIPTION:
XS GIS Cut Line= 4
      3657053.99     10160752.68      3657002.99     10160288.27
      3656882.55     10160116.82      3656449.57     10160034.35
#Sta/Elev= 30
  4477.2  295.49  4578.8   293.7    4599  293.17    4609  292.36    4633  292.21
  4649.3  291.28  4709.6  289.48  4719.1  287.75  4724.1  287.81  4810.2  281.42
  4815.2  281.49  4906.3  273.69  4935.2  272.09  4956.6  271.18  4986.3  268.45
    5019  267.91  5021.7  267.41    5025  267.91  5028.1   268.6  5036.8   268.8
  5041.7   269.6  5072.5  270.53  5099.5  272.58  5153.9  275.41    5246  281.55
  5313.7  285.45  5408.9  289.55    5516   292.9  5579.7  294.71  5594.7  294.71
#Mann= 6 ,-1 , 0
  4477.2     .05       0  4935.2     .07       0    5019     .07       0
    5025     .07       0  5041.7     .05       0    5516     .08       0
Bank Sta=4986.3,5028.1
XS Rating Curve= 0 ,0
Exp/Cntr=0.3,0.1

Type RM Length L Ch R = 1 ,1270    ,95,95,95
BEGIN DESCRIPTION:
UNT112 IN ROCK 4.2
END DESCRIPTION:
XS GIS Cut Line= 4
       3657140.8     10160656.11      3657132.12     10160275.24
      3656933.55     10160043.04      3656525.81     10160003.02
#Sta/Elev= 30
  4484.5  289.98    4549  289.52    4619  287.17  4645.3  284.89  4650.3  285.08
    4689  282.48  4789.1  275.05  4864.8  270.85  4889.3  270.05  4903.5  268.83
  4960.6  266.64  4967.2   266.7  4981.5  264.23  4988.6  262.57  4992.7  262.26
  4995.5  261.76  4998.7  262.26 5007.13  264.23  5016.6  266.08  5030.9  267.31
  5102.2  270.74    5145  273.36  5165.9  275.09  5174.2  275.15  5303.1  282.39
    5440  288.24  5463.8  288.61  5553.1  291.78  5574.7  291.98  5580.7  292.19
#Mann= 5 ,-1 , 0
  4484.5     .05       0  4992.7     .03       0  4998.7     .05       0
  5553.1     .08       0  5574.7     .05       0
Bank Sta=4981.5,5007.13
XS Rating Curve= 0 ,0
Exp/Cntr=0.3,0.1

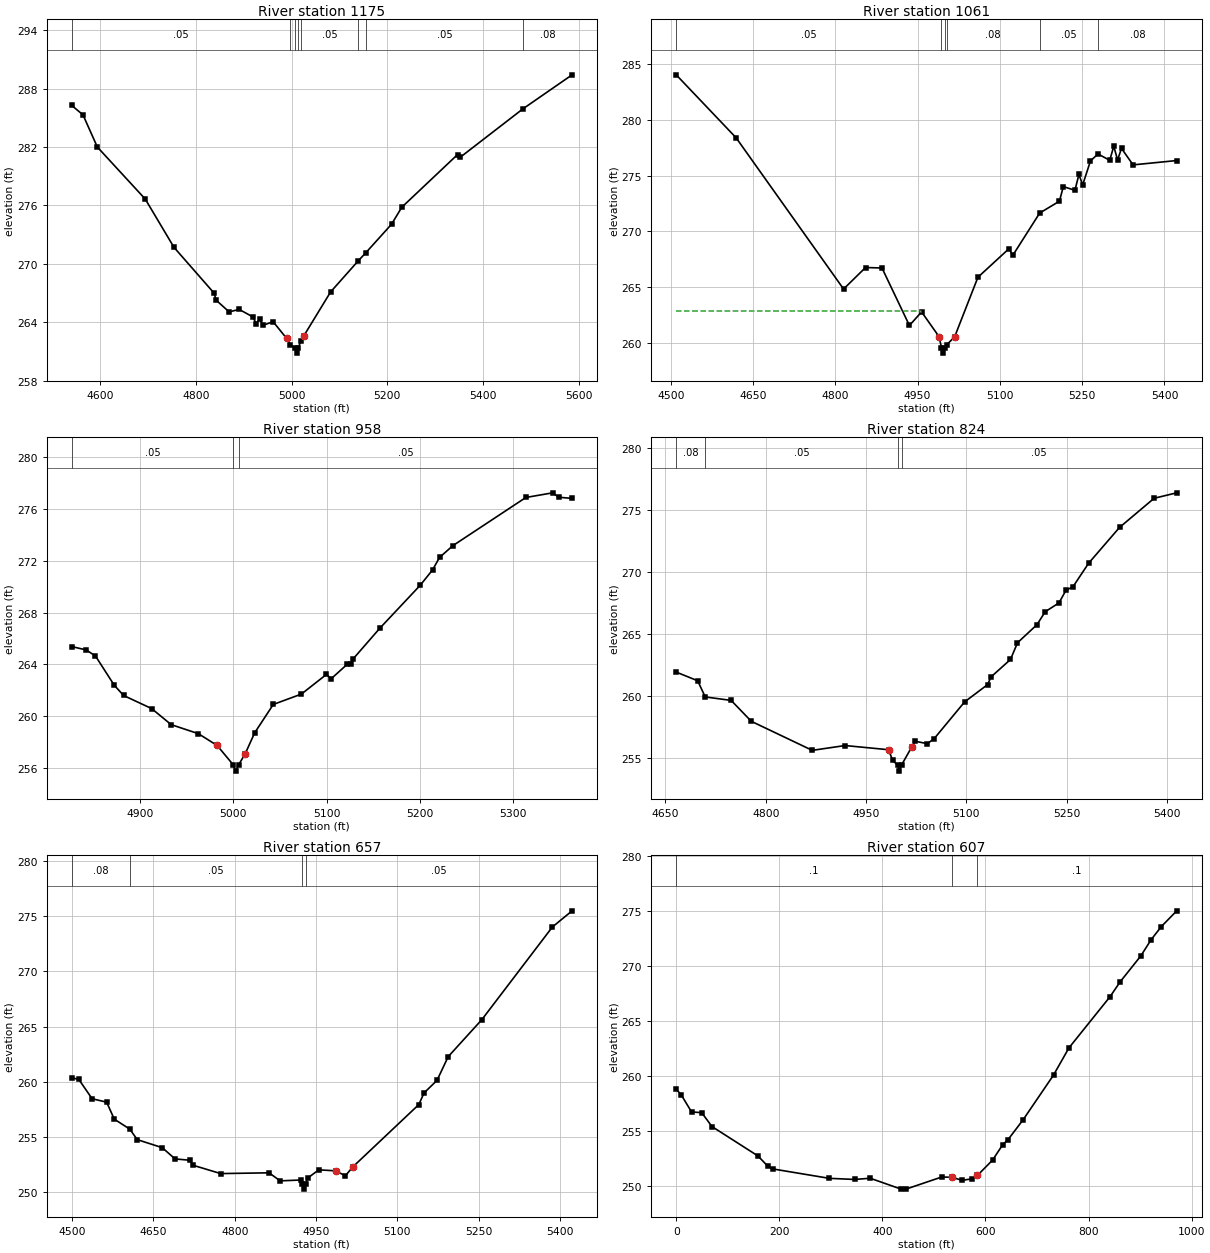
Type RM Length L Ch R = 1 ,1175    ,114,114,114
BEGIN DESCRIPTION:
UNT112 IN ROCK 4.0
END DESCRIPTION:
XS GIS Cut Line= 4
      3657225.43      10160545.4      3657237.37     10160241.61
      3656967.19     10159961.66       3656615.3     10159976.77
#Sta/Elev= 30
  4540.6  286.29  4564.4  285.31  4594.4     282  4694.5  276.65  4754.5  271.69
  4838.7  266.96  4842.1  266.28  4869.6  265.06  4890.7  265.31    4919  264.55
  4926.2  263.86  4933.2  264.32  4940.4  263.68  4961.5  264.05  4989.8  262.33
  4997.7  261.69  5008.1  261.32  5010.9  260.82  5014.1  261.32  5018.8  262.03
  5025.2  262.56  5081.6  267.11  5139.6  270.32  5155.4  271.15  5208.9  274.07
  5230.2  275.81  5346.8  281.23  5351.8  280.93  5483.4  285.93  5585.9  289.42
#Mann= 8 ,-1 , 0
  4540.6     .05       0  4997.7     .08       0  5008.1     .07       0
  5014.1     .08       0  5018.8     .05       0  5139.6     .08       0
  5155.4     .05       0  5483.4     .08       0
Bank Sta=4989.8,5025.2
XS Rating Curve= 0 ,0
Exp/Cntr=0.3,0.1

Type RM Length L Ch R = 1 ,1061    ,103,103,103
BEGIN DESCRIPTION:
UNT112 IN ROCK 3.0
END DESCRIPTION:
XS GIS Cut Line= 3
      3657246.05     10160536.75      3657250.39     10160091.87
      3656929.18     10159752.21
#Sta/Elev= 30
    4510  284.04  4619.2  278.39  4815.1  264.82  4855.1  266.75  4885.1  266.71
  4935.1  261.55  4957.3  262.77  4989.2  260.54  4993.5  259.57  4996.2  259.07
  4999.5  259.57  5002.9  259.81  5017.5  260.53    5060  265.88  5116.6  268.44
  5123.5  267.84  5172.6  271.64  5208.5   272.7  5215.7  274.01  5236.8  273.68
  5244.1   275.1  5250.9  274.16  5265.1  276.31  5278.8  276.94  5300.3  276.37
  5307.6  277.64  5314.5   276.4  5321.7  277.44  5342.8  275.96  5422.4  276.35
#Mann= 6 ,-1 , 0
    4510     .05       0  4993.5     .03       0  4999.5     .05       0
  5002.9     .08       0  5172.6     .05       0  5278.8     .08       0
#XS Ineff= 2 , 0
         4956.19  262.82
Permanent Ineff=
       F       F
Bank Sta=4989.2,5017.5
XS Rating Curve= 0 ,0
Exp/Cntr=0.3,0.1

Type RM Length L Ch R = 1 ,958     ,134,134,134
BEGIN DESCRIPTION:
UNT112 IN ROCK 2.4
END DESCRIPTION:
XS GIS Cut Line= 3
      3657311.16     10160237.22      3657328.51     10159938.87
      3657176.89     10159756.92
#Sta/Elev= 30
  4827.1  265.38  4842.7  265.12  4852.7  264.65  4872.8  262.39  4882.8   261.6
  4912.8  260.59  4933.7  259.35  4962.9  258.65  4982.9  257.74    5000  256.26
  5002.7  255.76    5006  256.26    5013  257.11    5023  258.71    5043  260.91
  5073.1  261.71  5099.9  263.23  5104.9  262.89  5122.1  264.01  5125.9  264.01
  5128.5  264.43  5157.1   266.8  5200.1   270.1  5213.5   271.3  5220.9  272.26
  5235.2  273.17  5313.3  276.89    5342  277.25  5348.5  276.91  5362.8  276.82
#Mann= 3 ,-1 , 0
  4827.1     .05       0    5000     .03       0    5006     .05       0
Bank Sta=4982.9,5013
XS Rating Curve= 0 ,0
Exp/Cntr=0.3,0.1

Type RM Length L Ch R = 1 ,824     ,167,167,167
BEGIN DESCRIPTION:
UNT112 IN ROCK 2.3
END DESCRIPTION:
XS GIS Cut Line= 4
      3657444.62     10160383.71      3657463.06      10160089.7
      3657386.02     10159809.75      3657236.65     10159742.64
#Sta/Elev= 30
  4666.1  261.91  4698.2  261.21  4709.5   259.9  4748.3  259.62  4778.4  257.93
  4869.6  255.58  4918.7  255.97  4983.9  255.63  4989.8  254.76  4997.2   254.4
  4999.9   253.9  5003.2   254.4  5018.3  255.84  5023.5  256.32  5041.7  256.12
    5052  256.53  5097.5   259.5  5131.9   260.9    5137  261.52  5166.1  262.93
  5176.6  264.28  5205.8  265.75    5218  266.79  5238.7  267.51    5249  268.52
  5259.7  268.82  5282.9  270.71  5329.2  273.61    5381  275.97  5414.8  276.41
#Mann= 4 ,-1 , 0
  4666.1     .08       0  4709.5     .05       0  4997.2     .03       0
  5003.2     .05       0
Bank Sta=4983.9,5018.3
XS Rating Curve= 0 ,0
Exp/Cntr=0.3,0.1

Type RM Length L Ch R = 1 ,657     ,50,50,50
BEGIN DESCRIPTION:
UNT112 IN ROCK 2.2
END DESCRIPTION:
XS GIS Cut Line= 4
       3657504.3     10160448.82      3657596.53     10159982.28
      3657544.44     10159815.18      3657280.79     10159747.91
#Sta/Elev= 30
  4499.3  260.36  4512.7   260.2  4537.2  258.45    4564  258.14    4578   256.6
  4606.7  255.69  4620.4  254.74  4666.5  254.01  4690.1  252.99  4717.8  252.87
  4722.9  252.42  4774.2  251.66  4863.4  251.73  4883.8     251  4922.9  251.08
    4925  250.75  4927.7  250.25    4931  250.75  4934.7  251.26  4955.1     252
    4986  251.91  5004.1  251.46  5017.4  252.25  5139.4  257.92  5149.1  258.98
    5173  260.12  5193.6  262.27  5255.5  265.62  5385.6  274.03    5422   275.5
#Mann= 4 ,-1 , 0
  4499.3     .08       0  4606.7     .05       0    4925     .03       0
    4931     .05       0
Bank Sta=4986,5017.4
XS Rating Curve= 0 ,0
Exp/Cntr=0.3,0.1

Type RM Length L Ch R = 1 ,607     ,160,160,160
XS GIS Cut Line= 4
     3657550.153    10160478.152     3657637.827    10159913.048
     3657546.681    10159811.486     3657294.945    10159748.118
#Sta/Elev= 30
       0  258.77     9.9  258.24   29.71   256.7   49.52  256.63   69.33  255.37
  158.47   252.7  178.27  251.74  188.18  251.51  297.12  250.66  346.64  250.56
  376.36  250.67  435.78  249.69  445.68  249.68  515.01  250.78  534.82  250.76
  554.63  250.48  574.44  250.62  584.27  250.92  613.78  252.32  633.45  253.72
  643.28  254.15  672.79  255.97  732.05  260.05  761.93  262.52  841.61  267.17
  861.53  268.54  901.37  270.88  921.29  272.35  941.21  273.55  971.09  274.98
#Mann= 3 , 0 , 0
       0      .1       0  534.82     .07       0  584.27      .1       0
Bank Sta=534.82,584.27
XS Rating Curve= 0 ,0
Exp/Cntr=0.3,0.1

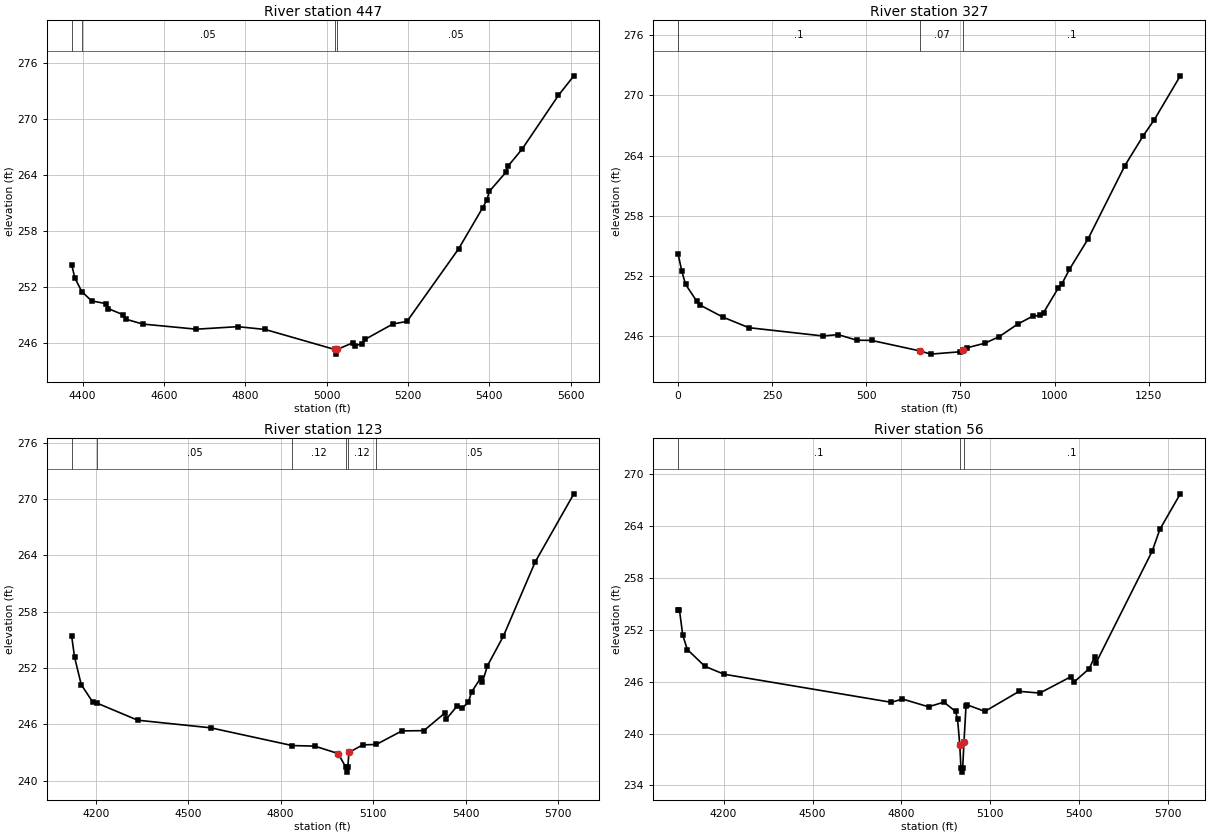
Type RM Length L Ch R = 1 ,447     ,120,120,120
BEGIN DESCRIPTION:
UNT112 IN ROCK 2.1
END DESCRIPTION:
XS GIS Cut Line= 3
      3657647.52     10160569.31      3657811.37     10159877.02
      3657305.37     10159744.04
#Sta/Elev= 30
  4373.1  254.42    4381     253  4398.1  251.54  4422.1  250.55  4458.1  250.25
  4463.2  249.72  4500.4  249.05  4505.5   248.6  4547.8  248.07  4679.7  247.52
  4781.8  247.79  4848.7  247.49  5019.9  245.35  5022.7  244.85  5025.9  245.35
  5065.2  246.08  5070.3  245.75  5087.5  245.98  5094.1  246.42    5163  248.08
  5197.5  248.35  5324.4  256.12  5383.6  260.52  5393.9  261.36  5399.9  262.27
  5440.3   264.3  5445.6  264.96  5480.6   266.8  5569.7  272.54  5607.7  274.64
#Mann= 4 ,-1 , 0
  4373.1     .08       0  4398.1     .05       0  5019.9     .03       0
  5025.9     .05       0
Bank Sta=5019.9,5025.9
XS Rating Curve= 0 ,0
Exp/Cntr=0.3,0.1

Type RM Length L Ch R = 1 ,327     ,204,204,204
XS GIS Cut Line= 5
     3657672.115    10160595.022      3657929.06    10160017.765
     3657883.053    10159869.327      3657817.08    10159871.931
     3657354.407    10159753.008
#Sta/Elev= 30
       0  254.17    9.89  252.45   19.77  251.15   49.43  249.46   59.31  249.06
  118.62  247.88  187.82  246.82  385.52  245.99  425.06  246.13  474.49  245.57
  514.03  245.55  642.26   244.5  671.09  244.18  747.96  244.41  757.57  244.57
  767.18  244.81  815.05  245.27  853.26  245.93  902.33  247.18  941.58  247.96
  961.21  248.05  971.02  248.33 1010.28   250.8 1020.09  251.23 1039.72  252.65
 1088.79  255.66 1186.92     263 1235.99     266 1265.43   267.6 1334.12  271.96
#Mann= 3 , 0 , 0
       0      .1       0  642.26     .07       0  757.57      .1       0
Bank Sta=642.26,757.57
XS Rating Curve= 0 ,0
Exp/Cntr=0.3,0.1

Type RM Length L Ch R = 1 ,123     ,67,67,67
BEGIN DESCRIPTION:
UNT112 IN ROCK 2.0
END DESCRIPTION:
XS GIS Cut Line= 5
      3657684.43     10160618.11      3658104.34     10159875.94
       3658056.6     10159822.77      3657820.05     10159868.34
      3657370.79     10159752.23
#Sta/Elev= 30
  4122.2  255.41  4131.5  253.18  4153.2  250.24  4190.7  248.36    4203  248.28
  4336.5  246.44  4573.2  245.63  4837.6  243.74  4910.9  243.68  4986.6  242.89
    5012  241.41  5014.7  240.91    5018  241.41  5021.7  243.01  5066.5  243.81
  5110.7  243.86  5193.5   245.3  5264.8  245.33  5332.8   247.2    5338  246.58
  5373.5  247.98  5388.4  247.73    5409  248.33  5419.4  249.44  5449.6  250.95
  5454.8  250.51  5471.1  252.24  5522.7  255.39    5626   263.3  5751.3  270.55
#Mann= 6 ,-1 , 0
  4122.2     .08       0    4203     .05       0  4837.6     .12       0
    5012     .07       0    5018     .12       0  5110.7     .05       0
Bank Sta=4986.6,5021.7
XS Rating Curve= 0 ,0
Exp/Cntr=0.3,0.1

Type RM Length L Ch R = 1 ,56      ,0,0,0
BEGIN DESCRIPTION:
UNT112 IN ROCK 1.0
END DESCRIPTION:
XS GIS Cut Line= 5
      3657702.52     10160635.18      3658159.34     10159835.48
      3658120.76     10159793.94      3657823.53     10159859.22
      3657425.62     10159751.95
#Sta/Elev= 30
  4046.6  254.29  4051.2  254.29  4062.2   251.4  4077.7  249.73  4136.8  247.79
  4201.6  246.87    4766  243.62  4803.4     244  4891.4   243.1  4943.1  243.64
  4982.6  242.56  4989.4  241.64  4996.8  238.67  5000.6  236.04  5003.4  235.54
  5006.6  236.04  5010.9     239  5017.8  243.19  5022.4  243.32  5081.4  242.57
    5197  244.89  5266.7  244.69  5371.5  246.58    5382  245.96  5433.6  247.52
  5451.5  248.87  5456.6   248.2  5645.9  261.12  5671.8  263.64  5740.7  267.75
#Mann= 3 , 0 , 0
  4046.6      .1       0  4996.8     .05       0  5010.9      .1       0
#XS Ineff= 2 , 0
                         5022.33          243.31
Permanent Ineff=
       F       F
Bank Sta=4996.8,5010.9
XS Rating Curve= 0 ,0
Exp/Cntr=0.3,0.1

Chan Stop Cuts=-1
Use User Specified Reach Order=0
Composite Channel Slope=5