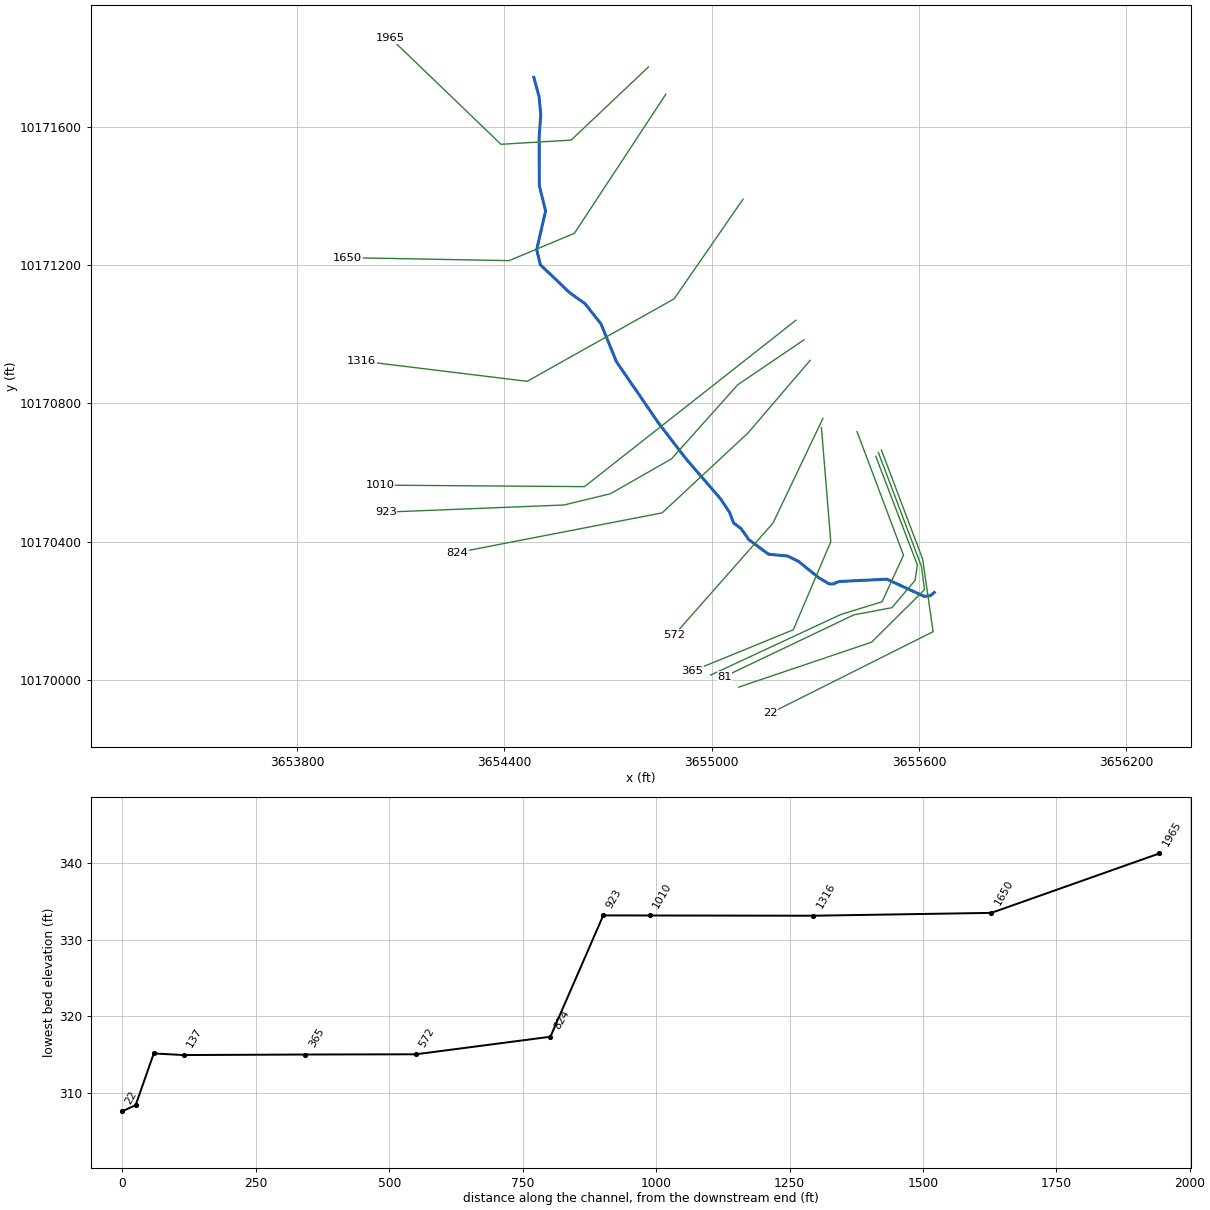
--- UNT113 IN ROCK.prj (project) ---

Proj Title=UNT113 IN ROCK Base Level Engineering
Current Plan=p01
Default Exp/Contr=0.3,0.1
English Units
Geom File=g01
Flow File=f01
Plan File=p01
BEGIN DESCRIPTION:
UNT113 IN ROCK
END DESCRIPTION:

--- UNT113 IN ROCK.p01 (plan) ---

Plan Title=Multiple Run
Short Identifier=Multiple
Geom File=g01
Flow File=f01
Subcritical Flow
K Sum by GR= 0
Std Step Tol= 0.01
Critical Tol= 0.01
Num of Std Step Trials= 20
Max Error Tol= 0.3
Flow Tol Ratio= 0.001
Split Flow NTrial= 30
Split Flow Tol= 0.02
Split Flow Ratio= 0.02
Log Output Level= 0
Friction Slope Method= 1
Unsteady Friction Slope Method= 2
Unsteady Bridges Friction Slope Method= 1
Parabolic Critical Depth
Global Vel Dist=  1 , 1 , 1
Global Log Level= 0
CheckData=True
Encroach Param= -1, 0, 0, 0
BEGIN DESCRIPTION:
Multiple Run
END DESCRIPTION:

--- UNT113 IN ROCK.f01 (steady flow) ---

Flow Title=Multiple
Number of Profiles=7
Profile Names=10-year,25-year,50-year,1pct_min,100-year,1pct_plu,500-year
River Rch & RM= UNT113 IN ROCK,Reach-1,1965
     158     196     225     191     258     349     338
Boundary for River Rch & Prof#=UNT113 IN ROCK,Reach-1,1
Up Type=0
Dn Type=3
Dn Slope=0.005
Boundary for River Rch & Prof#=UNT113 IN ROCK,Reach-1,2
Up Type=0
Dn Type=3
Dn Slope=0.005
Boundary for River Rch & Prof#=UNT113 IN ROCK,Reach-1,3
Up Type=0
Dn Type=3
Dn Slope=0.005
Boundary for River Rch & Prof#=UNT113 IN ROCK,Reach-1,4
Up Type=0
Dn Type=3
Dn Slope=0.005
Boundary for River Rch & Prof#=UNT113 IN ROCK,Reach-1,5
Up Type=0
Dn Type=3
Dn Slope=0.005
Boundary for River Rch & Prof#=UNT113 IN ROCK,Reach-1,6
Up Type=0
Dn Type=3
Dn Slope=0.005
Boundary for River Rch & Prof#=UNT113 IN ROCK,Reach-1,7
Up Type=0
Dn Type=3
Dn Slope=0.005

--- UNT113 IN ROCK.g01 (geometry) ---

Geom Title=Existing Conditions

River Reach=UNT113 IN ROCK,Reach-1
Reach XY= 30
      3654485.16     10171744.13      3654500.32     10171688.16
      3654505.30     10171636.49      3654500.43     10171570.52
      3654501.13     10171430.24      3654519.18     10171357.33
      3654493.49     10171245.52      3654503.91     10171201.77
      3654590.02     10171119.83      3654633.07     10171089.27
      3654679.53     10171030.50      3654724.35     10170920.90
      3654847.61     10170741.22      3654926.60     10170638.78
      3655024.69     10170525.07      3655051.60     10170485.14
      3655063.76     10170453.89      3655085.46     10170437.40
      3655107.16     10170406.15      3655164.45     10170363.61
      3655220.01     10170358.40      3655251.23     10170342.94
      3655309.46     10170295.96      3655339.42     10170278.13
      3655351.23     10170277.18      3655368.24     10170284.59
      3655507.19     10170291.32      3655615.28     10170241.54
      3655633.11     10170243.77      3655644.59     10170252.88

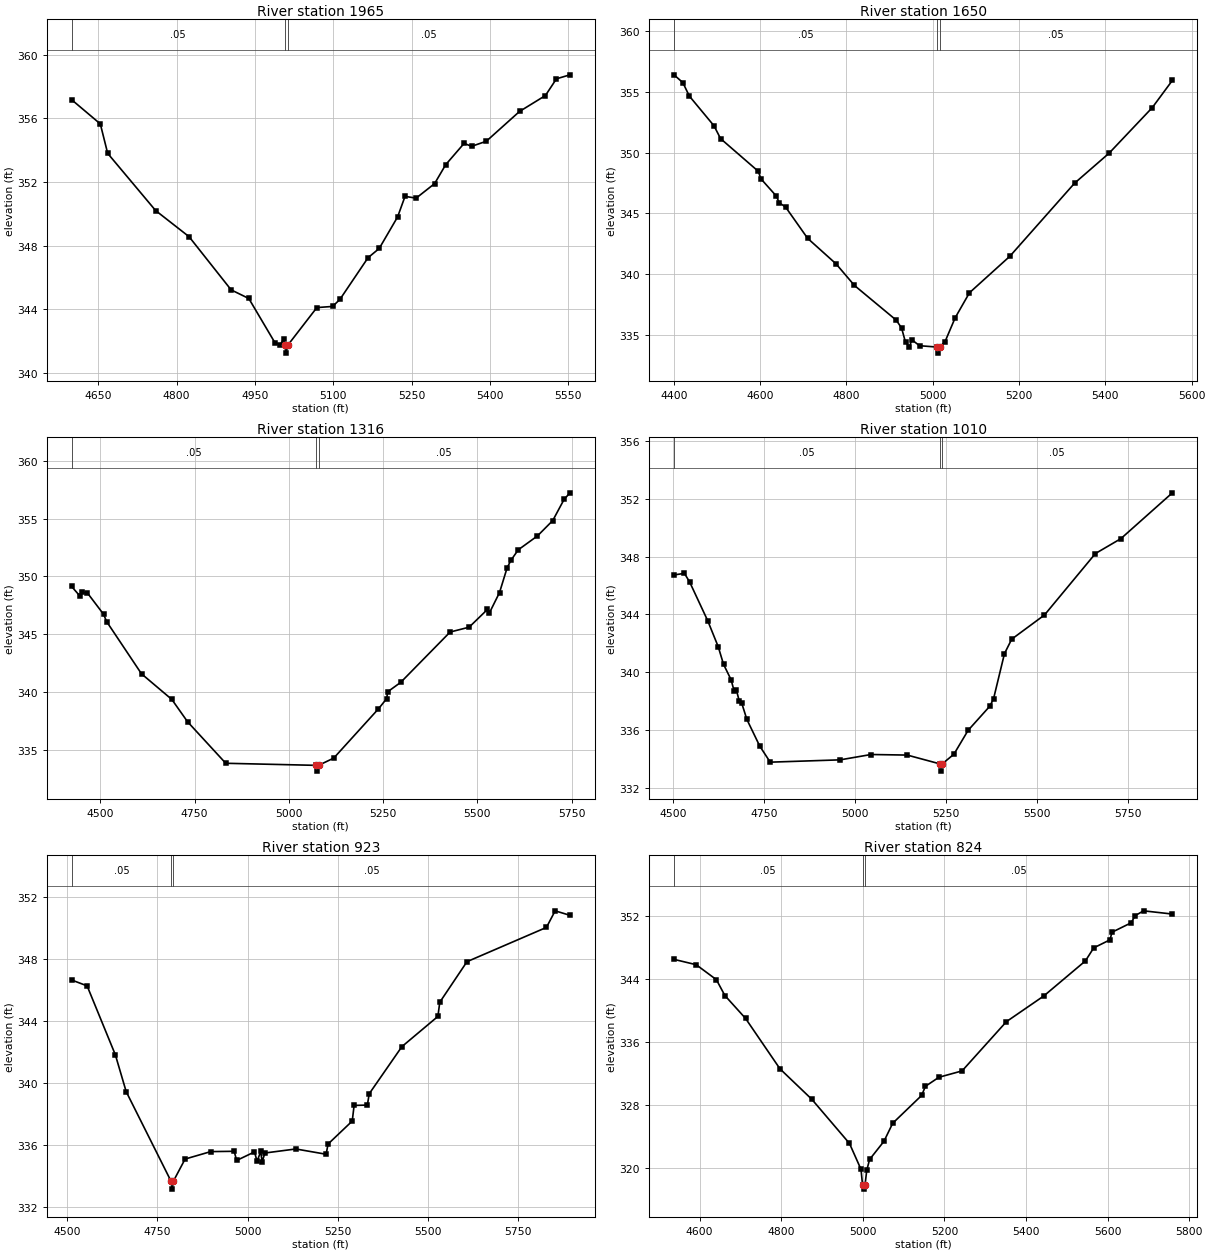
Type RM Length L Ch R = 1,1965,315,315,315
BEGIN DESCRIPTION:
UNT113 IN ROCK 38.0
END DESCRIPTION:
XS GIS Cut Line= 4
      3654817.08     10171774.36      3654593.14     10171562.57
      3654390.02     10171550.42      3654071.13     10171857.18
#Sta/Elev= 30
  4598.9  357.17  4653.9  355.65  4668.0  353.80  4759.8  350.21  4823.8  348.57
  4904.4  345.23  4938.2  344.69  4988.3  341.91  4998.3  341.78  5004.9  342.15
  5006.9  341.76  5009.6  341.26  5012.9  341.76  5068.5  344.12  5098.5  344.19
  5112.6  344.63  5166.5  347.25  5187.9  347.83  5223.1  349.81  5237.3  351.10
  5258.6  350.99  5293.9  351.90  5315.2  353.09  5350.5  354.43  5364.6  354.24
  5392.9  354.56  5456.5  356.43  5506.1  357.43  5527.2  358.48  5553.1  358.73
#Mann=3,-1,0
  4598.9    0.05       0  5006.9    0.03       0  5012.9    0.05       0
Bank Sta=5006.9,5012.9
Exp/Cntr=0.3,0.1

Type RM Length L Ch R = 1,1650,334,334,334
BEGIN DESCRIPTION:
Mapping XS 4dbfb1c5
END DESCRIPTION:
XS GIS Cut Line= 4
      3654867.31     10171695.35      3654602.57     10171292.80
      3654413.76     10171213.59      3653945.50     10171222.24
#Sta/Elev= 30
  4400.4  356.41  4420.9  355.77  4436.0  354.66  4493.2  352.21  4508.3  351.16
  4595.7  348.47  4601.6  347.86  4637.8  346.42  4644.2  345.88  4658.9  345.53
  4710.1  342.95  4775.9  340.85  4818.6  339.07  4915.2  336.22  4927.7  335.58
  4936.9  334.39  4946.1  334.02  4951.5  334.60  4969.5  334.11  5009.8  334.00
  5012.6  333.50  5015.8  334.00  5028.2  334.42  5052.0  336.41  5085.1  338.47
  5178.6  341.47  5328.7  347.49  5408.7  349.96  5508.7  353.71  5555.3  355.95
#Mann=3,-1,0
  4400.4    0.05       0  5009.8    0.03       0  5015.8    0.05       0
Bank Sta=5009.8,5015.8
Exp/Cntr=0.3,0.1

Type RM Length L Ch R = 1,1316,306,306,306
BEGIN DESCRIPTION:
Mapping XS 1b15c76a
END DESCRIPTION:
XS GIS Cut Line= 4
      3655090.86     10171391.56      3654891.19     10171102.92
      3654465.85     10170864.20      3653986.63     10170922.75
#Sta/Elev= 30
  4424.0  349.13  4445.2  348.33  4451.2  348.61  4466.1  348.56  4509.0  346.71
  4516.8  346.09  4609.4  341.56  4689.8  339.34  4731.7  337.40  4832.8  333.81
  5072.8  333.63  5075.6  333.13  5078.8  333.63  5119.2  334.26  5237.8  338.53
  5259.5  339.41  5262.0  340.00  5296.7  340.82  5427.7  345.18  5478.1  345.60
  5526.8  347.14  5531.8  346.83  5558.7  348.60  5578.8  350.74  5588.9  351.39
  5608.3  352.30  5659.4  353.51  5699.9  354.84  5729.9  356.67  5745.5  357.24
#Mann=3,-1,0
  4424.0    0.05       0  5072.8   0.033       0  5078.8    0.05       0
Bank Sta=5072.8,5078.8
Exp/Cntr=0.3,0.1

Type RM Length L Ch R = 1,1010,87,87,87
BEGIN DESCRIPTION:
Mapping XS 7e48b521
END DESCRIPTION:
XS GIS Cut Line= 3
      3655243.84     10171041.06      3654631.86     10170559.30
      3654040.53     10170563.64
#Sta/Elev= 30
  4503.1  346.73  4531.8  346.84  4546.2  346.24  4595.9  343.56  4624.8  341.76
  4639.3  340.55  4660.1  339.48  4668.2  338.72  4674.5  338.79  4682.6  338.00
  4689.0  337.89  4703.4  336.74  4738.7  334.90  4767.6  333.78  4960.0  333.94
  5045.0  334.31  5144.4  334.27  5234.4  333.66  5237.2  333.16  5240.4  333.66
  5272.7  334.33  5311.7  335.98  5371.7  337.66  5381.7  338.17  5411.7  341.29
  5431.7  342.29  5521.7  343.96  5661.7  348.21  5731.7  349.24  5873.3  352.41
#Mann=3,-1,0
  4503.1    0.05       0  5234.4   0.033       0  5240.4    0.05       0
Bank Sta=5234.4,5240.4
Exp/Cntr=0.3,0.1

Type RM Length L Ch R = 1,923,99,99,99
BEGIN DESCRIPTION:
Mapping XS af378448
END DESCRIPTION:
XS GIS Cut Line= 6
      3655267.68     10170984.62      3655075.66     10170854.44
      3654883.60     10170639.59      3654706.73     10170538.68
      3654572.18     10170506.13      3654056.91     10170485.52
#Sta/Elev= 30
  4512.7  346.66  4555.7  346.28  4634.0  341.83  4663.9  339.46  4788.4  333.67
  4791.2  333.17  4794.4  333.67  4827.1  335.11  4898.1  335.59  4963.0  335.61
  4970.0  335.02  5019.3  335.57  5026.6  334.96  5036.5  335.60  5040.5  334.94
  5048.3  335.50  5133.8  335.76  5217.7  335.42  5223.2  336.08  5290.1  337.56
  5295.3  338.57  5332.0  338.59  5337.1  339.32  5427.6  342.36  5527.4  344.31
  5532.5  345.22  5607.9  347.84  5828.0  350.05  5852.2  351.12  5893.2  350.83
#Mann=3,-1,0
  4512.7    0.05       0  4788.4   0.033       0  4794.4    0.05       0
Bank Sta=4788.4,4794.4
Exp/Cntr=0.3,0.1

Type RM Length L Ch R = 1,824,252,252,252
BEGIN DESCRIPTION:
Mapping XS 06109f1e
END DESCRIPTION:
XS GIS Cut Line= 4
      3655285.09     10170924.98      3655104.95     10170714.46
      3654856.47     10170483.34      3654262.94     10170368.32
#Sta/Elev= 30
  4537.3  346.55  4591.7  345.87  4641.1  343.97  4662.0  341.95  4712.5  339.05
  4797.0  332.63  4874.8  328.77  4967.2  323.15  4995.5  319.85  4999.3  317.84
  5002.1  317.34  5005.3  317.84  5009.5  319.72  5016.5  321.11  5051.7  323.42
  5073.2  325.72  5144.0  329.25  5153.3  330.41  5186.3  331.56  5243.1  332.37
  5351.7  338.63  5443.4  341.90  5545.2  346.35  5565.6  348.01  5605.4  349.03
  5610.4  350.00  5657.1  351.19  5667.5  352.12  5687.8  352.72  5758.3  352.31
#Mann=3,-1,0
  4537.3    0.05       0  4999.3    0.03       0  5005.3    0.05       0
Bank Sta=4999.3,5005.3
Exp/Cntr=0.3,0.1

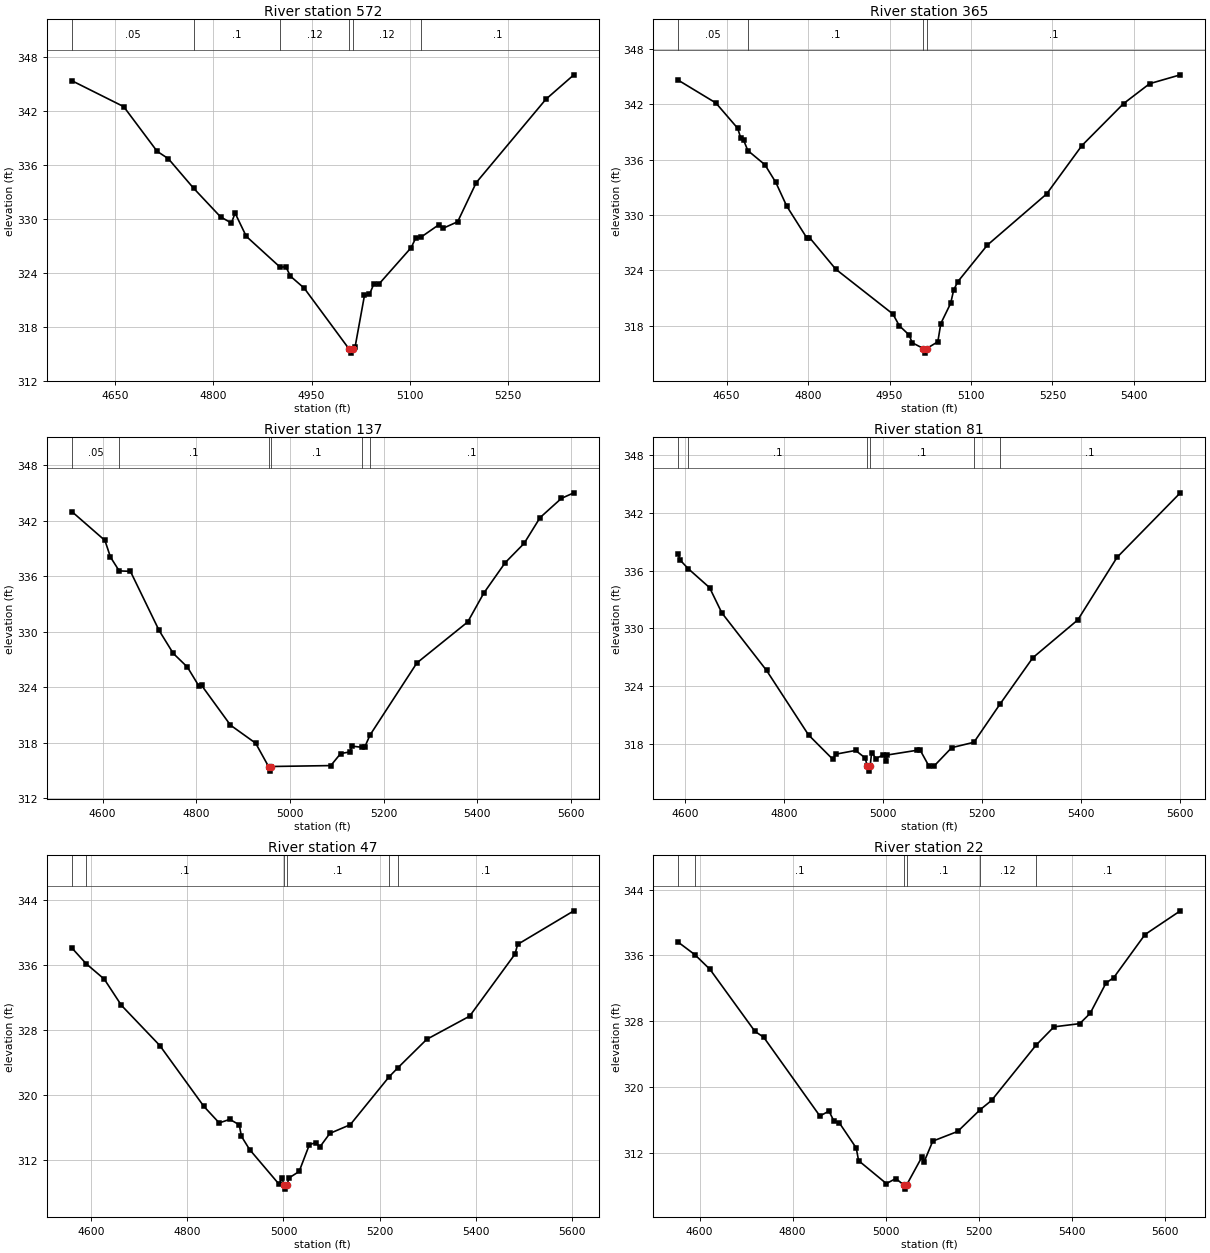
Type RM Length L Ch R = 1,572,207,207,207
BEGIN DESCRIPTION:
Mapping XS d3be5a7b
END DESCRIPTION:
XS GIS Cut Line= 3
      3655321.95     10170756.74      3655177.65     10170454.04
      3654892.28     10170130.70
#Sta/Elev= 30
  4583.9  345.37  4663.2  342.48  4714.2  337.51  4731.3  336.69  4769.8  333.41
  4811.1  330.21  4827.6  329.53  4833.3  330.63  4850.3  328.05  4902.1  324.61
  4910.8  324.66  4917.8  323.61  4938.8  322.28  5006.9  315.55  5009.7  315.05
  5012.9  315.55  5016.6  315.78  5030.8  321.47  5038.4  321.58  5045.1  322.75
  5052.6  322.71  5102.0  326.78  5109.2  327.87  5117.0  327.95  5144.6  329.35
  5151.3  328.96  5173.1  329.67  5201.5  334.03  5307.8  343.30  5350.5  346.02
#Mann=6,-1,0
  4583.9    0.05       0  4769.8     0.1       0  4902.1    0.12       0
  5006.9    0.07       0  5012.9    0.12       0  5117.0     0.1       0
Bank Sta=5006.9,5012.9
Exp/Cntr=0.3,0.1

Type RM Length L Ch R = 1,365,228,228,228
BEGIN DESCRIPTION:
Mapping XS f6ceab37
END DESCRIPTION:
XS GIS Cut Line= 4
      3655317.63     10170730.74      3655344.75     10170399.79
      3655236.25     10170144.80      3654944.38     10170025.45
#Sta/Elev= 30
  4560.9  344.62  4630.2  342.15  4670.4  339.40  4676.2  338.31  4681.2  338.13
  4689.0  336.99  4720.5  335.45  4740.6  333.53  4760.7  330.96  4797.6  327.52
  4802.6  327.55  4851.0  324.12  4956.2  319.26  4968.0  317.99  4986.2  316.98
  4991.6  316.15  5012.3  315.52  5015.0  315.02  5018.3  315.52  5038.9  316.25
  5044.4  318.23  5062.6  320.43  5068.0  321.85  5075.7  322.77  5130.0  326.73
  5239.2  332.28  5304.2  337.53  5380.9  342.08  5428.9  344.24  5485.4  345.20
#Mann=4,-1,0
  4560.9    0.05       0  4689.0     0.1       0  5012.3    0.07       0
  5018.3     0.1       0
Bank Sta=5012.3,5018.3
Exp/Cntr=0.3,0.1

Type RM Length L Ch R = 1,137,56,56,56
BEGIN DESCRIPTION:
Mapping XS dbb836ae
END DESCRIPTION:
XS GIS Cut Line= 5
      3655420.70     10170718.83      3655555.26     10170360.73
      3655493.41     10170226.18      3655374.05     10170189.29
      3654996.79     10170013.66
#Sta/Elev= 30
  4534.3  343.02  4605.1  339.89  4616.8  338.10  4635.5  336.60  4659.5  336.55
  4720.7  330.16  4750.9  327.68  4781.1  326.20  4806.0  324.12  4811.4  324.22
  4873.1  319.92  4926.8  317.97  4954.3  315.45  4957.1  314.95  4960.3  315.45
  5087.2  315.55  5108.2  316.85  5127.5  317.02  5132.7  317.65  5153.2  317.53
  5160.1  317.60  5170.8  318.84  5271.0  326.65  5379.5  331.08  5413.8  334.20
  5459.5  337.49  5499.8  339.57  5533.9  342.36  5579.4  344.44  5606.0  345.04
#Mann=6,-1,0
  4534.3    0.05       0  4635.5     0.1       0  4954.3    0.07       0
  4960.3     0.1       0  5153.2    0.12       0  5170.8     0.1       0
Bank Sta=4954.3,4960.3
Exp/Cntr=0.3,0.1

Type RM Length L Ch R = 1,81,34,34,34
BEGIN DESCRIPTION:
Mapping XS f1ce95fa
END DESCRIPTION:
XS GIS Cut Line= 6
      3655474.98     10170647.15      3655595.40     10170332.52
      3655588.89     10170288.03      3655521.62     10170208.82
      3655412.03     10170188.20      3655036.86     10170009.29
#Sta/Elev= 30
  4586.5  337.76  4589.7  337.13  4606.6  336.21  4649.8  334.23  4674.5  331.61
  4764.7  325.63  4849.5  318.92  4898.9  316.37  4904.2  316.92  4944.5  317.31
  4964.0  316.52  4967.8  315.66  4970.5  315.16  4973.8  315.66  4976.8  317.09
  4985.7  316.47  5000.4  316.85  5006.6  316.25  5008.7  316.84  5068.7  317.33
  5074.9  317.33  5092.5  315.68  5102.7  315.68  5138.4  317.60  5183.3  318.16
  5235.8  322.12  5302.2  326.95  5392.9  330.88  5472.1  337.38  5599.8  344.09
#Mann=6,-1,0
  4586.5    0.05       0  4606.6     0.1       0  4967.8    0.07       0
  4973.8     0.1       0  5183.3    0.12       0  5235.8     0.1       0
Bank Sta=4967.8,4973.8
Exp/Cntr=0.3,0.1

Type RM Length L Ch R = 1,47,25,25,25
BEGIN DESCRIPTION:
Mapping XS 3ad8ecb2
END DESCRIPTION:
XS GIS Cut Line= 5
      3655482.56     10170658.03      3655607.34     10170328.18
      3655616.02     10170260.90      3655463.03     10170108.99
      3655077.84     10169978.79
#Sta/Elev= 30
  4560.4  338.08  4590.2  336.13  4627.9  334.23  4663.5  331.01  4743.2  326.07
  4834.5  318.60  4866.6  316.55  4888.7  316.99  4908.2  316.32  4912.7  314.91
  4929.7  313.28  4990.2  309.06  4997.3  309.73  5001.3  308.91  5004.1  308.41
  5007.3  308.91  5011.4  309.78  5032.6  310.58  5053.9  313.88  5068.0  314.14
  5075.1  313.55  5096.3  315.26  5138.7  316.33  5219.7  322.24  5237.0  323.29
  5297.6  326.83  5386.7  329.68  5481.0  337.32  5486.3  338.50  5603.1  342.63
#Mann=6,-1,0
  4560.4    0.05       0  4590.2     0.1       0  5001.3    0.07       0
  5007.3     0.1       0  5219.7    0.12       0  5237.0     0.1       0
Bank Sta=5001.3,5007.3
Exp/Cntr=0.3,0.1

Type RM Length L Ch R = 1,22,0,0,0
BEGIN DESCRIPTION:
UNT113 IN ROCK 2.0
END DESCRIPTION:
XS GIS Cut Line= 4
      3655491.22     10170665.67      3655610.60     10170349.88
      3655640.98     10170139.37      3655169.01     10169902.85
#Sta/Elev= 30
  4554.3  337.61  4590.3  336.08  4622.5  334.31  4719.0  326.78  4737.8  326.07
  4858.5  316.50  4878.0  317.10  4888.3  315.92  4900.2  315.67  4936.5  312.62
  4941.6  311.08  5001.3  308.29  5021.5  308.91  5038.7  308.12  5041.4  307.62
  5044.7  308.12  5077.3  311.49  5082.3  310.93  5100.9  313.45  5154.5  314.63
  5202.3  317.25  5227.1  318.39  5322.3  325.08  5361.2  327.33  5416.5  327.72
  5438.9  328.97  5472.9  332.65  5489.7  333.32  5556.7  338.54  5632.5  341.42
#Mann=6,-1,0
  4554.3    0.05       0  4590.3     0.1       0  5038.7    0.07       0
  5044.7     0.1       0  5202.3    0.12       0  5322.3     0.1       0
Bank Sta=5038.7,5044.7
Exp/Cntr=0.3,0.1

Chan Stop Cuts=-1