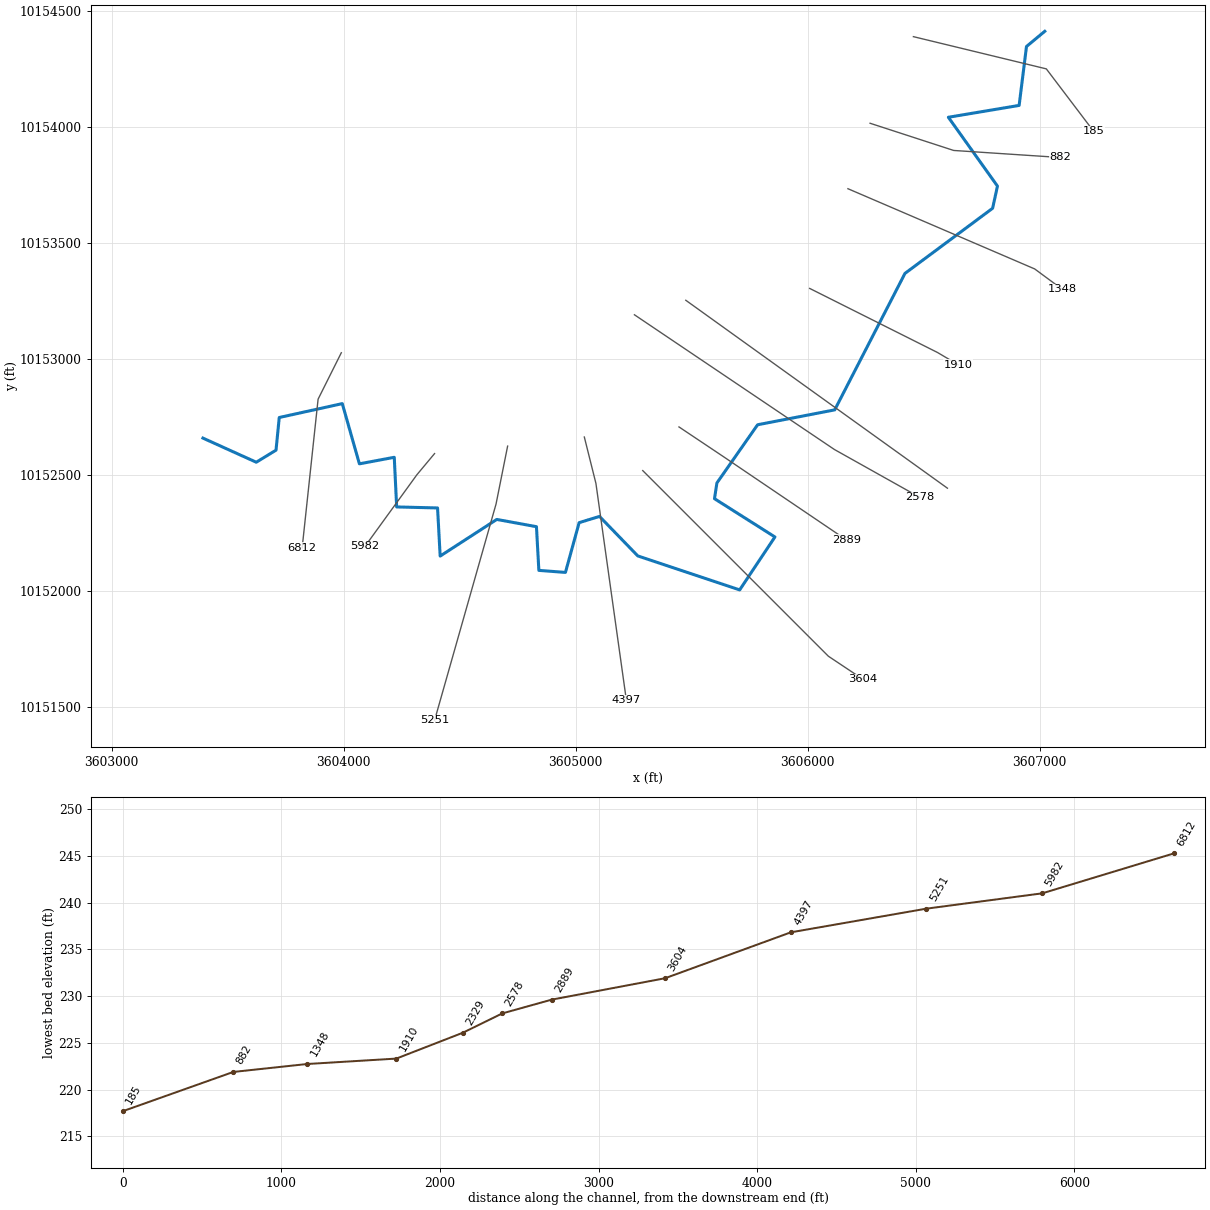
--- UPSHUR BRANCH.prj (project) ---

Proj Title=UPSHUR BRANCH Base Level Engineering
Current Plan=p01
Default Exp/Contr=0.3,0.1
English Units
Geom File=g01
Flow File=f01
Plan File=p01
Y Axis Title=Elevation
X Axis Title(PF)=Main Channel Distance
X Axis Title(XS)=Station
BEGIN DESCRIPTION:
UPSHUR BRANCH
END DESCRIPTION:
DSS Export Rating Curves= 0
DSS Export Rating Curve Sorted= 0
DSS Export Volume Flow Curves= 0
DXF OffsetX= 0
DXF OffsetY= 0
DXF ScaleX= 1
DXF ScaleY= 10

--- UPSHUR BRANCH.p01 (plan) ---

Plan Title=Multiple Run
Short Identifier=Multiple
Geom File=g01
Flow File=f01
Subcritical Flow
K Sum by GR= 0
Std Step Tol= 0.01
Critical Tol= 0.01
Num of Std Step Trials= 20
Max Error Tol= 0.3
Flow Tol Ratio= 0.001
Split Flow NTrial= 30
Split Flow Tol= 0.02
Split Flow Ratio= 0.02
Log Output Level= 0
Friction Slope Method= 1
Unsteady Friction Slope Method= 2
Unsteady Bridges Friction Slope Method= 1
Parabolic Critical Depth
Global Vel Dist=  1 , 1 , 1
Global Log Level= 0
CheckData=True
Encroach Param= -1, 0, 0, 0
BEGIN DESCRIPTION:
Multiple Run
END DESCRIPTION:

--- UPSHUR BRANCH.f01 (steady flow) ---

Flow Title=Multiple
Number of Profiles=7
Profile Names=10-year,25-year,50-year,1pct_min,100-year,1pct_plu,500-year
River Rch & RM= UPSHUR BRANCH,Reach-1,6812
     775    1053    1280    1140    1541    2084    2238
Boundary for River Rch & Prof#=UPSHUR BRANCH,Reach-1,1
Up Type=0
Dn Type=3
Dn Slope=0.005
Boundary for River Rch & Prof#=UPSHUR BRANCH,Reach-1,2
Up Type=0
Dn Type=3
Dn Slope=0.005
Boundary for River Rch & Prof#=UPSHUR BRANCH,Reach-1,3
Up Type=0
Dn Type=3
Dn Slope=0.005
Boundary for River Rch & Prof#=UPSHUR BRANCH,Reach-1,4
Up Type=0
Dn Type=3
Dn Slope=0.005
Boundary for River Rch & Prof#=UPSHUR BRANCH,Reach-1,5
Up Type=0
Dn Type=3
Dn Slope=0.005
Boundary for River Rch & Prof#=UPSHUR BRANCH,Reach-1,6
Up Type=0
Dn Type=3
Dn Slope=0.005
Boundary for River Rch & Prof#=UPSHUR BRANCH,Reach-1,7
Up Type=0
Dn Type=3
Dn Slope=0.005

--- UPSHUR BRANCH.g01 (geometry) ---

Geom Title=Existing Conditions
Program Version=4.10

River Reach=UPSHUR BRANCH   ,Reach-1
Reach XY= 30
      3603393.79      10152658.4      3603623.76     10152554.39
      3603708.83     10152606.47      3603722.72     10152747.09
      3603994.42     10152806.99      3604068.21     10152547.44
       3604218.4      10152575.6       3604228.8     10152361.68
      3604405.01     10152357.34       3604416.3     10152149.87
      3604660.22     10152307.86      3604831.23     10152276.61
      3604841.64     10152088.24      3604956.23     10152079.56
      3605015.25     10152293.97      3605102.93     10152320.88
      3605267.86     10152150.74      3605707.09     10152004.04
        3605859.     10152232.34      3605598.59     10152397.27
        3605609.     10152464.98      3605784.35     10152715.84
      3606116.81     10152780.07      3606419.49     10153368.17
      3606797.24     10153648.84      3606818.16     10153744.46
      3606606.54     10154041.11      3606911.56     10154092.19
      3606943.24     10154346.17      3607022.11     10154411.64

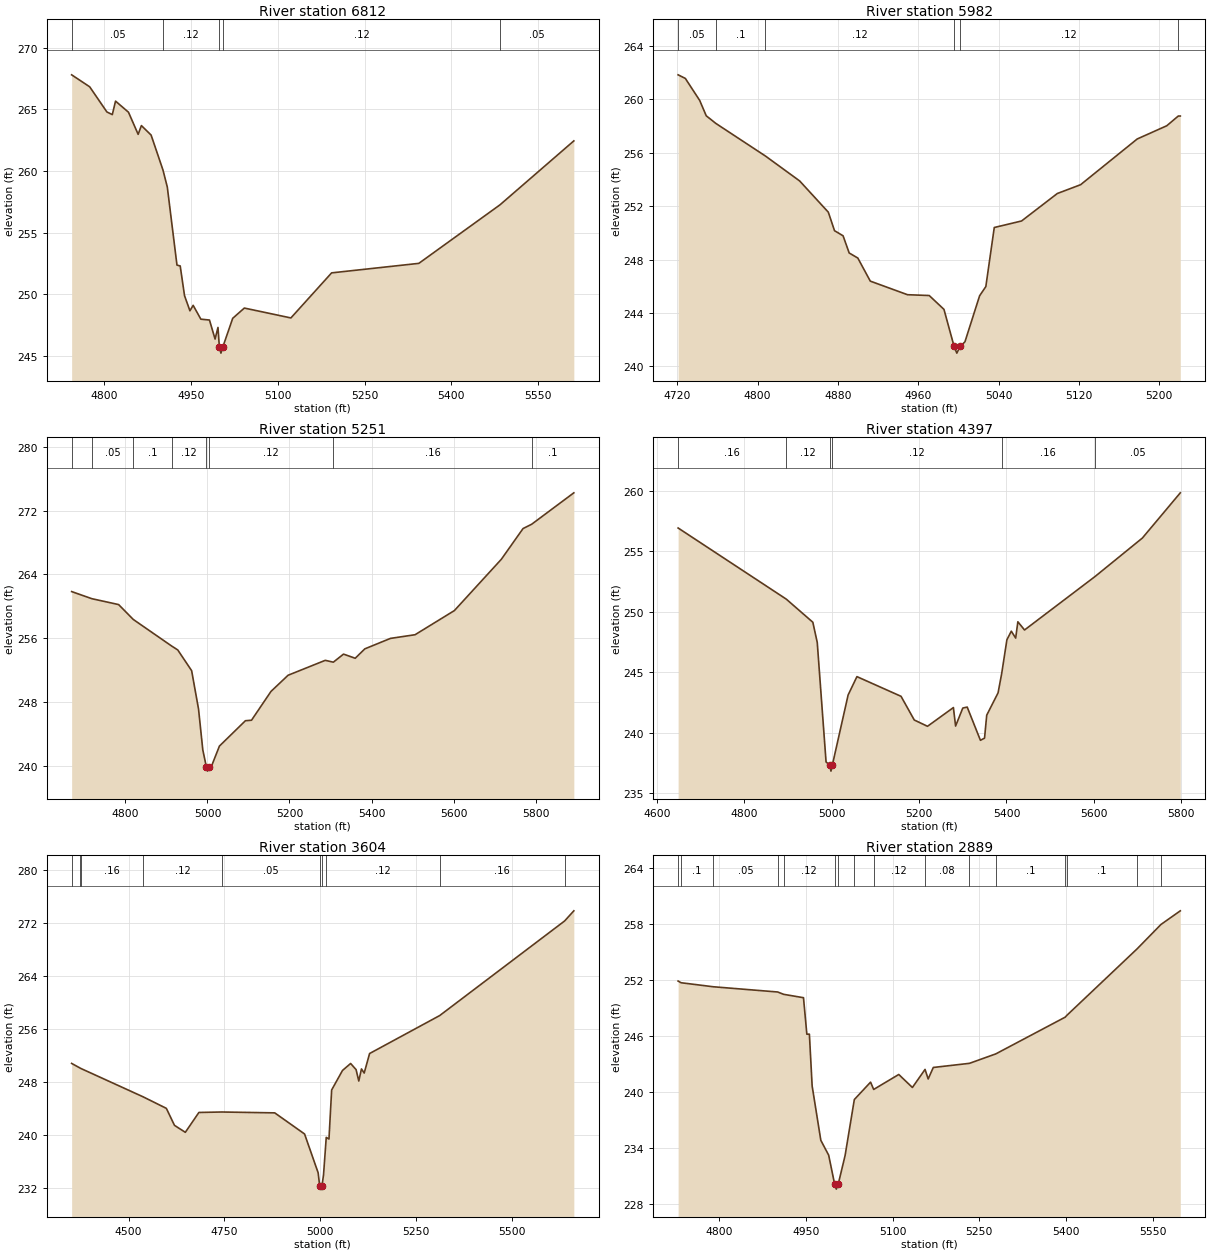
Type RM Length L Ch R = 1 ,6812    ,830,830,830
BEGIN DESCRIPTION:
UPSHUR BRANCH 14.0
END DESCRIPTION:
XS GIS Cut Line= 3
      3603990.21     10153026.22       3603890.2     10152826.19
      3603821.45     10152185.21
#Sta/Elev= 30
  4743.5  267.79  4774.7  266.82  4804.5  264.78  4813.8  264.57  4819.4  265.66
  4841.8  264.76  4858.5  262.97  4864.1  263.68  4880.9  262.91  4901.4  260.08
  4908.9   258.7  4925.6  252.38  4931.2  252.31  4938.7   249.9    4948  248.68
  4953.6  249.12  4966.9     248  4981.8  247.93  4991.5  246.39  4996.5  247.33
  4998.9  245.75  5001.6  245.25  5004.9  245.75    5022  248.07  5042.1   248.9
  5122.6   248.1    5193  251.75  5343.8  252.52  5484.1  257.26  5611.8  262.44
#Mann= 5 ,-1 , 0
  4743.5     .05       0  4901.4     .12       0  4998.9     .07       0
  5004.9     .12       0  5484.1     .05       0
Bank Sta=4998.9,5004.9
XS Rating Curve= 0 ,0
Exp/Cntr=0.3,0.1

Type RM Length L Ch R = 1 ,5982    ,731,731,731
BEGIN DESCRIPTION:
UPSHUR BRANCH 13.0
END DESCRIPTION:
XS GIS Cut Line= 3
       3604392.1     10152591.64      3604316.08     10152500.54
      3604092.11     10152191.65
#Sta/Elev= 30
  4720.8  261.85    4728  261.58  4742.3  259.93  4748.8  258.78  4758.3  258.21
  4807.8  255.76  4841.9  253.89  4870.4  251.55  4876.6  250.16  4885.1  249.78
  4891.2  248.49  4899.8  248.11  4912.2  246.38  4949.3  245.36  4970.9   245.3
  4985.6  244.26  4995.7  241.48  4998.4  240.98  5001.7  241.48  5006.5  241.83
  5021.1  245.28  5027.3  245.97  5035.7   250.4  5062.9  250.89  5098.5  252.95
  5121.7  253.61  5178.1  257.04  5207.5  258.03    5219  258.76    5221  258.76
#Mann= 6 ,-1 , 0
  4720.8     .05       0  4758.3      .1       0  4807.8     .12       0
  4995.7     .07       0  5001.7     .12       0    5219     .05       0
Bank Sta=4995.7,5001.7
XS Rating Curve= 0 ,0
Exp/Cntr=0.3,0.1

Type RM Length L Ch R = 1 ,5251    ,854,854,854
BEGIN DESCRIPTION:
UPSHUR BRANCH 12.0
END DESCRIPTION:
XS GIS Cut Line= 3
      3604707.03      10152623.9      3604657.04     10152373.93
      3604392.11     10151441.66
#Sta/Elev= 30
    4669  261.85  4718.1  260.96  4783.5  260.22  4819.1  258.36  4912.6  255.03
  4927.7  254.53  4961.5  251.93  4978.3  247.12  4988.7     242  4997.5  239.84
  5000.3  239.34  5003.5  239.84  5009.5  239.91  5029.2  242.48  5092.6  245.66
  5107.4  245.72    5155  249.34  5196.6  251.36  5287.2  253.23  5306.9     253
  5331.7  254.01  5360.2  253.49  5383.7  254.67  5446.1  255.98  5506.1  256.44
    5602  259.47  5716.4   265.9  5769.3  269.75  5790.3  270.29  5893.1  274.23
#Mann= 8 ,-1 , 0
    4669      .1       0  4718.1     .05       0  4819.1      .1       0
  4912.6     .12       0  4997.5     .07       0  5003.5     .12       0
  5306.9     .16       0  5790.3      .1       0
Bank Sta=4997.5,5003.5
XS Rating Curve= 0 ,0
Exp/Cntr=0.3,0.1

Type RM Length L Ch R = 1 ,4397    ,793,793,793
BEGIN DESCRIPTION:
UPSHUR BRANCH 10.0
END DESCRIPTION:
XS GIS Cut Line= 3
      3605037.58     10152663.04      3605087.59       10152463.
      3605218.85     10151528.37
#Sta/Elev= 30
  4648.1  256.93  4895.9  251.04  4956.6  249.13  4966.7  247.46  4986.9  237.57
  4995.3  237.31  4998.1  236.81  5001.3  237.31  5037.4  243.11  5057.6  244.63
  5158.6     243  5188.9  241.04  5219.2  240.52  5278.5  242.07  5283.5  240.54
    5300  242.03  5310.1  242.11  5340.4  239.36  5349.8  239.54  5354.8  241.44
  5380.8  243.29  5389.1  244.89    5401  247.68  5411.1  248.39  5421.1  247.82
  5426.1  249.17  5441.4  248.49  5602.7  252.91  5711.3   256.1  5798.1  259.84
#Mann= 6 ,-1 , 0
  4648.1     .16       0  4895.9     .12       0  4995.3     .07       0
  5001.3     .12       0  5389.1     .16       0  5602.7     .05       0
Bank Sta=4995.3,5001.3
XS Rating Curve= 0 ,0
Exp/Cntr=0.3,0.1

Type RM Length L Ch R = 1 ,3604    ,715,715,715
BEGIN DESCRIPTION:
UPSHUR BRANCH 8.0
END DESCRIPTION:
XS GIS Cut Line= 3
      3605289.35     10152518.35      3606089.33     10151718.38
      3606238.24     10151619.11
#Sta/Elev= 30
  4351.5  250.84  4374.2  250.12  4375.5  250.08  4538.2   245.8  4598.6  244.07
  4619.8  241.51  4648.1  240.46  4683.5  243.45  4742.9  243.52  4881.4  243.39
  4959.2  240.21  4994.6  234.37  4998.7   232.4  5001.4   231.9  5004.7   232.4
  5008.7  234.05  5014.5  238.67  5015.8   239.7  5022.9  239.45  5029.9  246.84
  5058.2  249.78  5079.4  250.83  5093.6  249.91  5100.7  248.19  5107.7  250.01
  5114.8  249.39  5128.9  252.33  5311.8  258.05  5637.7   272.3  5661.8  273.83
#Mann= 10 ,-1 , 0
  4351.5     .16       0  4374.2      .1       0  4375.5     .16       0
  4538.2     .12       0  4742.9     .05       0  4998.7     .03       0
  5004.7     .05       0  5014.5     .12       0  5311.8     .16       0
  5637.7      .1       0
Bank Sta=4998.7,5004.7
XS Rating Curve= 0 ,0
Exp/Cntr=0.3,0.1

Type RM Length L Ch R = 1 ,2889    ,311,311,311
BEGIN DESCRIPTION:
UPSHUR BRANCH 7.0
END DESCRIPTION:
XS GIS Cut Line= 3
      3605445.55     10152706.53      3605634.44     10152580.26
      3606166.09     10152220.39
#Sta/Elev= 30
  4728.6  251.86  4733.8  251.68  4789.4  251.25  4900.9  250.69  4911.3  250.44
  4945.6  250.08  4951.4  246.18  4955.8  246.18  4960.6  240.63  4975.6  234.83
  4989.2  233.24  4999.6  230.11  5002.4  229.61  5005.6  230.11  5017.6   233.2
  5033.6  239.19  5061.7  241.05  5067.1  240.27  5110.5  241.87  5134.1  240.48
    5156  242.41  5161.4  241.39  5170.3  242.62  5232.8  243.06  5278.4  244.07
  5398.6     248  5400.9  248.16  5523.3  255.32  5564.3  257.91  5597.8  259.37
#Mann= 16 ,-1 , 0
  4728.6     .05       0  4733.8      .1       0  4789.4     .05       0
  4900.9      .1       0  4911.3     .12       0  4999.6     .07       0
  5005.6     .12       0  5033.6     .08       0  5067.1     .12       0
    5156     .08       0  5232.8     .12       0  5278.4      .1       0
  5398.6     .12       0  5400.9      .1       0  5523.3     .08       0
  5564.3     .16       0
Bank Sta=4999.6,5005.6
XS Rating Curve= 0 ,0
Exp/Cntr=0.3,0.1

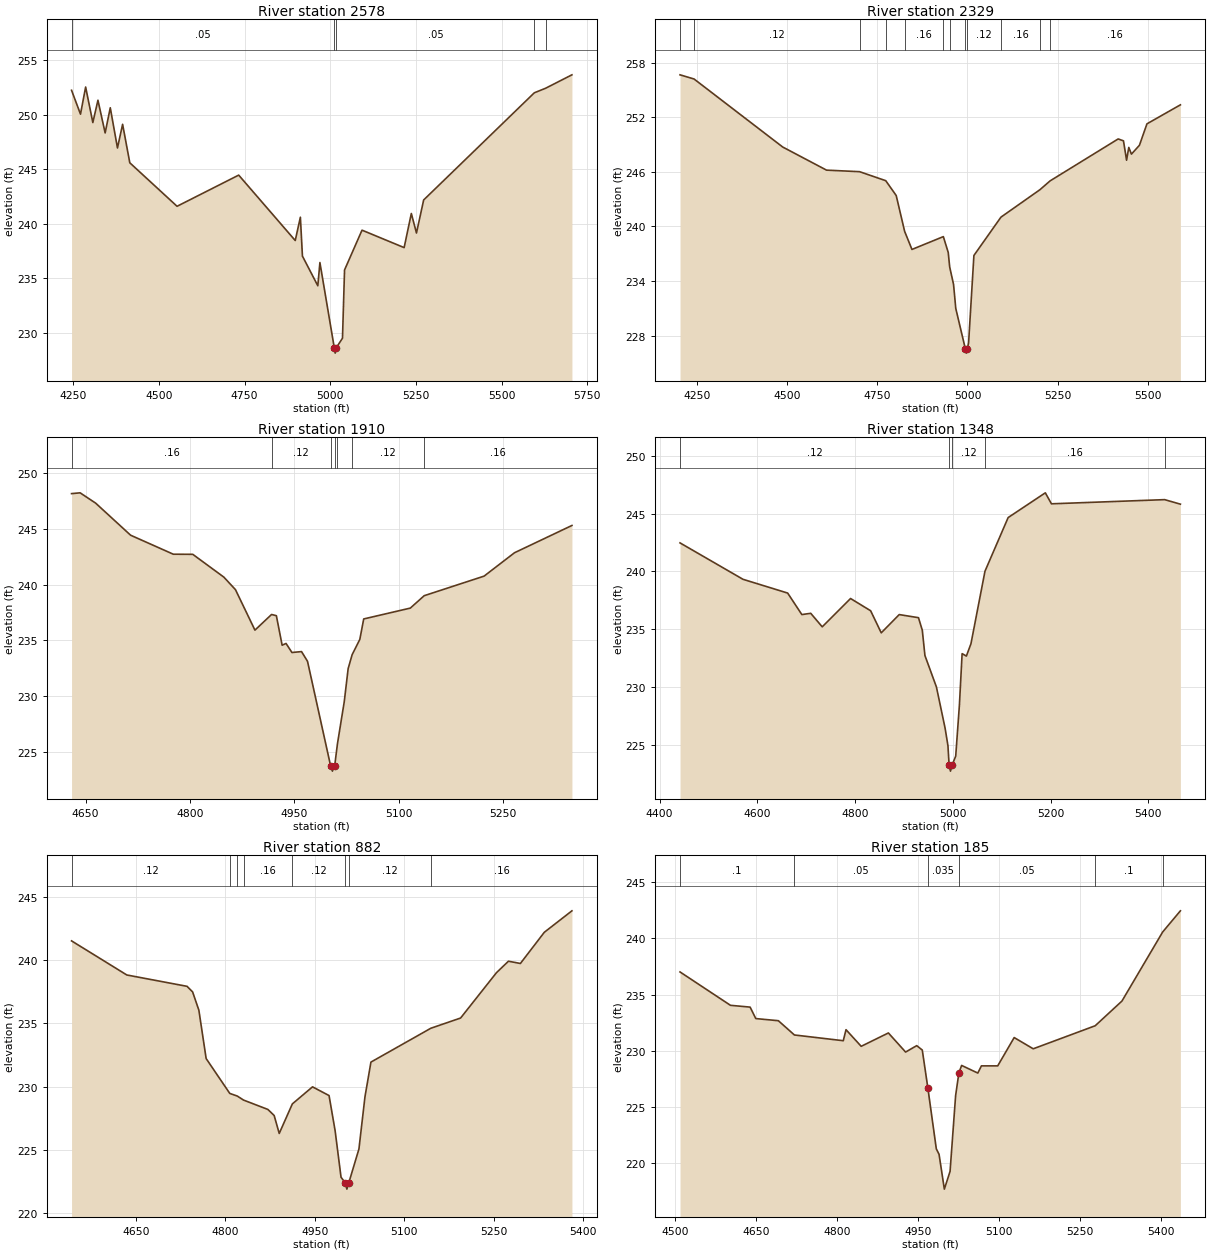
Type RM Length L Ch R = 1 ,2578    ,249,249,249
BEGIN DESCRIPTION:
UPSHUR BRANCH 6.0
END DESCRIPTION:
XS GIS Cut Line= 3
      3605253.54     10153189.91      3606115.56     10152609.15
      3606482.75     10152403.42
#Sta/Elev= 30
  4245.2  252.25  4271.3  250.06  4286.3  252.55  4307.3  249.29  4322.2  251.34
  4343.2  248.34  4358.2  250.65  4379.2  246.96  4394.2  249.13  4415.2   245.6
  4553.1  241.61    4733  244.47    4898  238.47    4913  240.61    4919  237.04
  4963.9  234.32    4970  236.45  5011.9  228.64  5014.6  228.14  5017.9  228.64
  5035.9  229.51  5041.9  235.77  5092.9  239.42  5215.8  237.82  5236.8  240.95
  5251.8  239.16  5272.8  242.19  5595.7  252.02  5628.8  252.44  5705.5  253.67
#Mann= 5 ,-1 , 0
  4245.2     .05       0  5011.9     .04       0  5017.9     .05       0
  5595.7     .16       0  5628.8     .05       0
Bank Sta=5011.9,5017.9
XS Rating Curve= 0 ,0
Exp/Cntr=0.3,0.1

Type RM Length L Ch R = 1 ,2329    ,419,419,419
BEGIN DESCRIPTION:
Mapping XS 1e6caf6f
END DESCRIPTION:
XS GIS Cut Line= 2
      3605474.93     10153252.39      3606602.52      10152442.5
#Sta/Elev= 30
  4202.4  256.67  4241.4  256.21  4487.4  248.73  4608.9  246.19  4700.6  246.02
  4773.2  245.03  4802.2   243.4  4825.6  239.46  4845.9  237.47    4933  238.88
  4946.6  237.13  4950.6  235.54  4961.3  233.63  4967.5  230.98  4993.9  226.57
  4996.7  226.07  4999.9  226.57  5003.1  227.22  5017.8  236.81  5092.8  241.02
  5200.7  244.03  5229.2  245.01  5418.1  249.62  5432.8  249.41  5441.4  247.28
  5447.5  248.69  5454.8  247.95    5477  248.92  5497.9  251.28  5590.7  253.37
#Mann= 12 ,-1 , 0
  4202.4     .16       0  4241.4     .12       0  4700.6     .16       0
  4773.2     .12       0  4825.6     .16       0    4933     .05       0
  4950.6     .12       0  4993.9     .07       0  4999.9     .12       0
  5092.8     .16       0  5200.7     .12       0  5229.2     .16       0
Bank Sta=4993.9,4999.9
XS Rating Curve= 0 ,0
Exp/Cntr=0.3,0.1

Type RM Length L Ch R = 1 ,1910    ,562,562,562
BEGIN DESCRIPTION:
UPSHUR BRANCH 5.0
END DESCRIPTION:
XS GIS Cut Line= 3
      3606008.81     10153303.49      3606559.64     10153027.41
      3606648.61     10152974.81
#Sta/Elev= 30
  4629.7  248.13    4642   248.2  4664.3  247.28  4714.6  244.41    4776  242.71
    4804   242.7  4848.7  240.66  4865.4  239.54  4893.4  235.92  4917.3  237.32
  4924.2  237.21  4932.5  234.57  4938.1  234.73  4946.6  233.92  4960.4     234
    4969  233.13  5002.1  223.81  5004.8  223.31  5008.1  223.81  5012.1  225.78
  5021.8  229.51  5027.4  232.47  5033.2  233.73  5044.2  235.09  5049.8  236.92
  5116.8  237.89  5136.8     239  5222.9  240.75  5266.6  242.84  5349.2  245.28
#Mann= 7 ,-1 , 0
  4629.7     .16       0  4917.3     .12       0  5002.1     .07       0
  5008.1     .12       0  5012.1     .16       0  5033.2     .12       0
  5136.8     .16       0
Bank Sta=5002.1,5008.1
XS Rating Curve= 0 ,0
Exp/Cntr=0.3,0.1

Type RM Length L Ch R = 1 ,1348    ,466,466,466
BEGIN DESCRIPTION:
UPSHUR BRANCH 3.0
END DESCRIPTION:
XS GIS Cut Line= 3
      3606173.69      10153733.2      3606978.56     10153387.48
      3607097.65     10153299.56
#Sta/Elev= 30
  4441.7  242.47  4570.6  239.32    4662  238.13    4691  236.27  4709.2  236.38
  4732.7  235.21  4790.7  237.66  4831.8   236.6  4853.5  234.69  4890.3  236.27
  4929.7     236  4937.5  234.92  4942.9  232.73  4966.4  230.01  4984.1  226.46
    4990  224.93  4992.4  223.23  4995.2  222.73  4998.4  223.23  5005.9  224.03
  5013.5  228.47    5019  232.89  5027.7  232.68  5037.1  233.75  5065.8  240.02
  5113.2  244.66  5189.3   246.8  5201.8  245.85  5433.5  246.21  5465.7  245.82
#Mann= 5 ,-1 , 0
  4441.7     .12       0  4992.4     .07       0  4998.4     .12       0
  5065.8     .16       0  5433.5     .12       0
Bank Sta=4992.4,4998.4
XS Rating Curve= 0 ,0
Exp/Cntr=0.3,0.1

Type RM Length L Ch R = 1 ,882     ,697,697,697
BEGIN DESCRIPTION:
UPSHUR BRANCH 2.0
END DESCRIPTION:
XS GIS Cut Line= 3
      3606269.17     10154015.31      3606629.45     10153898.11
      3607088.29     10153867.81
#Sta/Elev= 30
  4542.3  241.54  4634.9  238.84  4735.9  237.94  4745.2   237.5  4755.7  236.05
  4767.9  232.22  4807.5  229.46  4820.1  229.25  4830.7  228.93  4871.4  228.19
  4881.9  227.71  4890.4  226.29  4912.4  228.63  4946.2  229.98  4973.9  229.29
    4984  226.53    4994  222.82    5001  222.38  5003.8  221.88    5007  222.38
    5024  225.06  5034.1  229.19  5044.1  231.94  5144.5  234.62  5194.4  235.43
  5254.5  239.02  5274.6  239.93  5294.6  239.75  5334.7  242.22    5381  243.92
#Mann= 8 ,-1 , 0
  4542.3     .12       0  4807.5     .16       0  4820.1     .12       0
  4830.7     .16       0  4912.4     .12       0    5001     .07       0
    5007     .12       0  5144.5     .16       0
Bank Sta=5001,5007
XS Rating Curve= 0 ,0
Exp/Cntr=0.3,0.1

Type RM Length L Ch R = 1 ,185     ,0,0,0
BEGIN DESCRIPTION:
UPSHUR BRANCH 1.0
END DESCRIPTION:
XS GIS Cut Line= 3
      3606455.83     10154388.57      3607028.75     10154249.68
      3607232.75     10153980.58
#Sta/Elev= 30
  4508.9  237.01  4602.4  234.04  4638.8  233.88  4649.3  232.86  4691.1  232.67
  4720.9   231.4  4811.4  230.89  4816.5  231.87  4844.6  230.39    4895  231.58
  4926.9  229.88  4947.5  230.45  4957.8  230.06  4968.1   226.7  4983.8  221.27
  4988.9  220.78  4998.7  217.68  5009.3  219.26  5019.6  226.01  5025.6  228.01
  5030.7  228.69  5060.7  228.01  5067.4  228.65  5097.6  228.65  5128.1  231.17
  5163.4  230.17  5278.2  232.22  5327.8  234.42  5403.3  240.57  5436.1  242.45
#Mann= 6 ,-1 , 0
  4508.9      .1       0  4720.9     .05       0  4968.1    .035       0
  5025.6     .05       0  5278.2      .1       0  5403.3     .05       0
Bank Sta=4968.1,5025.6
XS Rating Curve= 0 ,0
Exp/Cntr=0.3,0.1

Chan Stop Cuts=-1
Use User Specified Reach Order=0
Composite Channel Slope=5