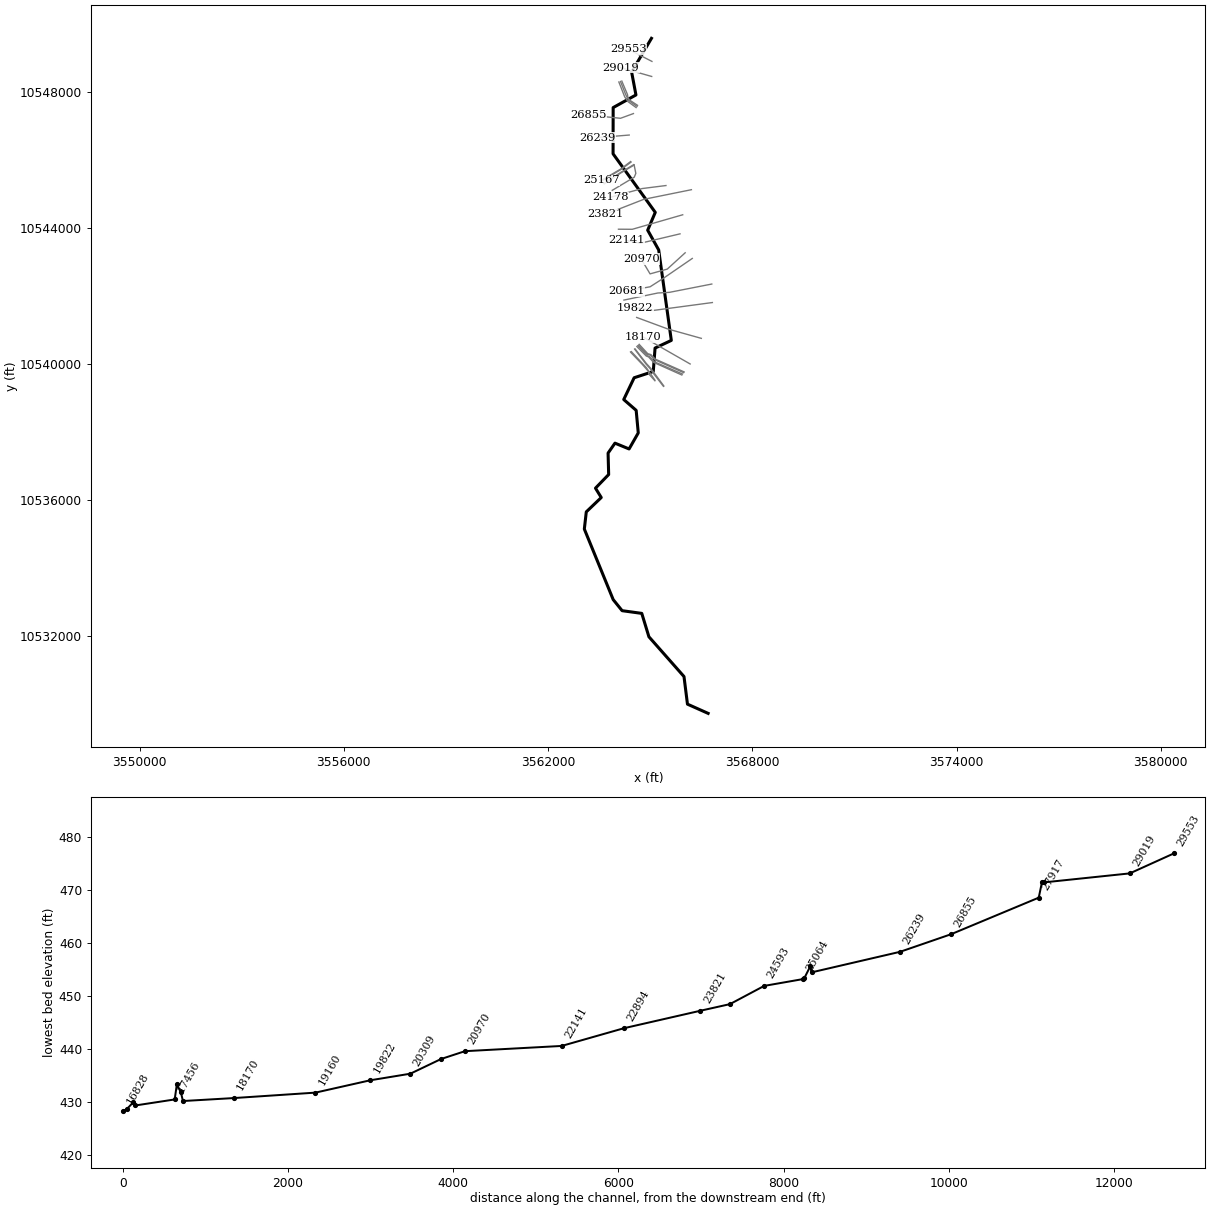
--- BEAR BRANCH.prj (project) ---

Proj Title=BEAR BRANCH Base Level Engineering
Current Plan=p01
Default Exp/Contr=0.3,0.1
English Units
Geom File=g01
Flow File=f01
Plan File=p01
Y Axis Title=Elevation
X Axis Title(PF)=Main Channel Distance
X Axis Title(XS)=Station
BEGIN DESCRIPTION:
BEAR BRANCH
END DESCRIPTION:
DSS Export Rating Curves= 0
DSS Export Rating Curve Sorted= 0
DSS Export Volume Flow Curves= 0
DXF OffsetX= 0
DXF OffsetY= 0
DXF ScaleX= 1
DXF ScaleY= 10

--- BEAR BRANCH.p01 (plan) ---

Plan Title=Multiple Run
Short Identifier=Multiple
Geom File=g01
Flow File=f01
Subcritical Flow
K Sum by GR= 0
Std Step Tol= 0.01
Critical Tol= 0.01
Num of Std Step Trials= 20
Max Error Tol= 0.3
Flow Tol Ratio= 0.001
Split Flow NTrial= 30
Split Flow Tol= 0.02
Split Flow Ratio= 0.02
Log Output Level= 0
Friction Slope Method= 1
Unsteady Friction Slope Method= 2
Unsteady Bridges Friction Slope Method= 1
Parabolic Critical Depth
Global Vel Dist=  1 , 1 , 1
Global Log Level= 0
CheckData=True
Encroach Param= -1, 0, 0, 0
BEGIN DESCRIPTION:
Multiple Run
END DESCRIPTION:

--- BEAR BRANCH.f01 (steady flow) ---

Flow Title=Multiple
Program Version=4.10
Number of Profiles= 7
Profile Names=10-year,25-year,50-year,1pct_min,100-year,1pct_plu,500-year
River Rch & RM=BEAR BRANCH,Reach-1         ,29553
     567     748     891     776    1050    1420    1450
River Rch & RM=BEAR BRANCH,Reach-1         ,24178
    1077    1475    1803    1606    2172    2937    3143
River Rch & RM=BEAR BRANCH,Reach-1         ,20681
    1652    2307    2854    2569    3474    4699    5139
River Rch & RM=BEAR BRANCH,Reach-1         ,16877
    2045    2879    3581    3239    4380    5923    6539
River Rch & RM=BEAR BRANCH,Reach-1         ,9280
    2200    3106    3871    3507    4743    6414    7107
River Rch & RM=BEAR BRANCH,Reach-1         ,7716
    2387    3382    4224    3834    5185    7012    7798
Boundary for River Rch & Prof#=BEAR BRANCH,Reach-1         , 1
Up Type= 0
Dn Type= 3
Dn Slope=0.005
Boundary for River Rch & Prof#=BEAR BRANCH,Reach-1         , 2
Up Type= 0
Dn Type= 3
Dn Slope=0.005
Boundary for River Rch & Prof#=BEAR BRANCH,Reach-1         , 3
Up Type= 0
Dn Type= 3
Dn Slope=0.005
Boundary for River Rch & Prof#=BEAR BRANCH,Reach-1         , 4
Up Type= 0
Dn Type= 3
Dn Slope=0.005
Boundary for River Rch & Prof#=BEAR BRANCH,Reach-1         , 5
Up Type= 0
Dn Type= 3
Dn Slope=0.005
Boundary for River Rch & Prof#=BEAR BRANCH,Reach-1         , 6
Up Type= 0
Dn Type= 3
Dn Slope=0.005
Boundary for River Rch & Prof#=BEAR BRANCH,Reach-1         , 7
Up Type= 0
Dn Type= 3
Dn Slope=0.005
DSS Import GetInterval= 0
DSS Import GetPeak= 0
DSS Import FillOption= 0

--- BEAR BRANCH.g01 (geometry) ---

Geom Title=Existing Conditions
Program Version=4.10

River Reach=BEAR BRANCH     ,Reach-1
Reach XY= 30
      3565037.11     10549576.64       3564454.4     10548585.59
      3564581.34     10547911.96      3563911.99     10547540.64
       3563909.3     10546182.04      3565149.12     10544460.75
      3564926.17     10543936.74      3565249.45      10543356.5
      3565620.29     10540696.31      3565143.21     10540471.31
      3565090.43     10539782.42      3564528.61     10539598.28
      3564222.68     10538958.15       3564587.9     10538640.18
      3564649.41     10537976.99      3564380.16     10537505.06
      3563965.17     10537675.87      3563762.78     10537384.62
       3563779.7     10536753.11      3563392.46     10536352.59
      3563562.24      10536077.2      3563122.41      10535655.5
      3563065.14     10535150.12      3563912.97     10533076.11
      3564174.79     10532750.52      3564752.57     10532671.36
      3564962.29     10531983.16      3565992.85     10530814.41
      3566094.93     10530002.61      3566702.11     10529731.64

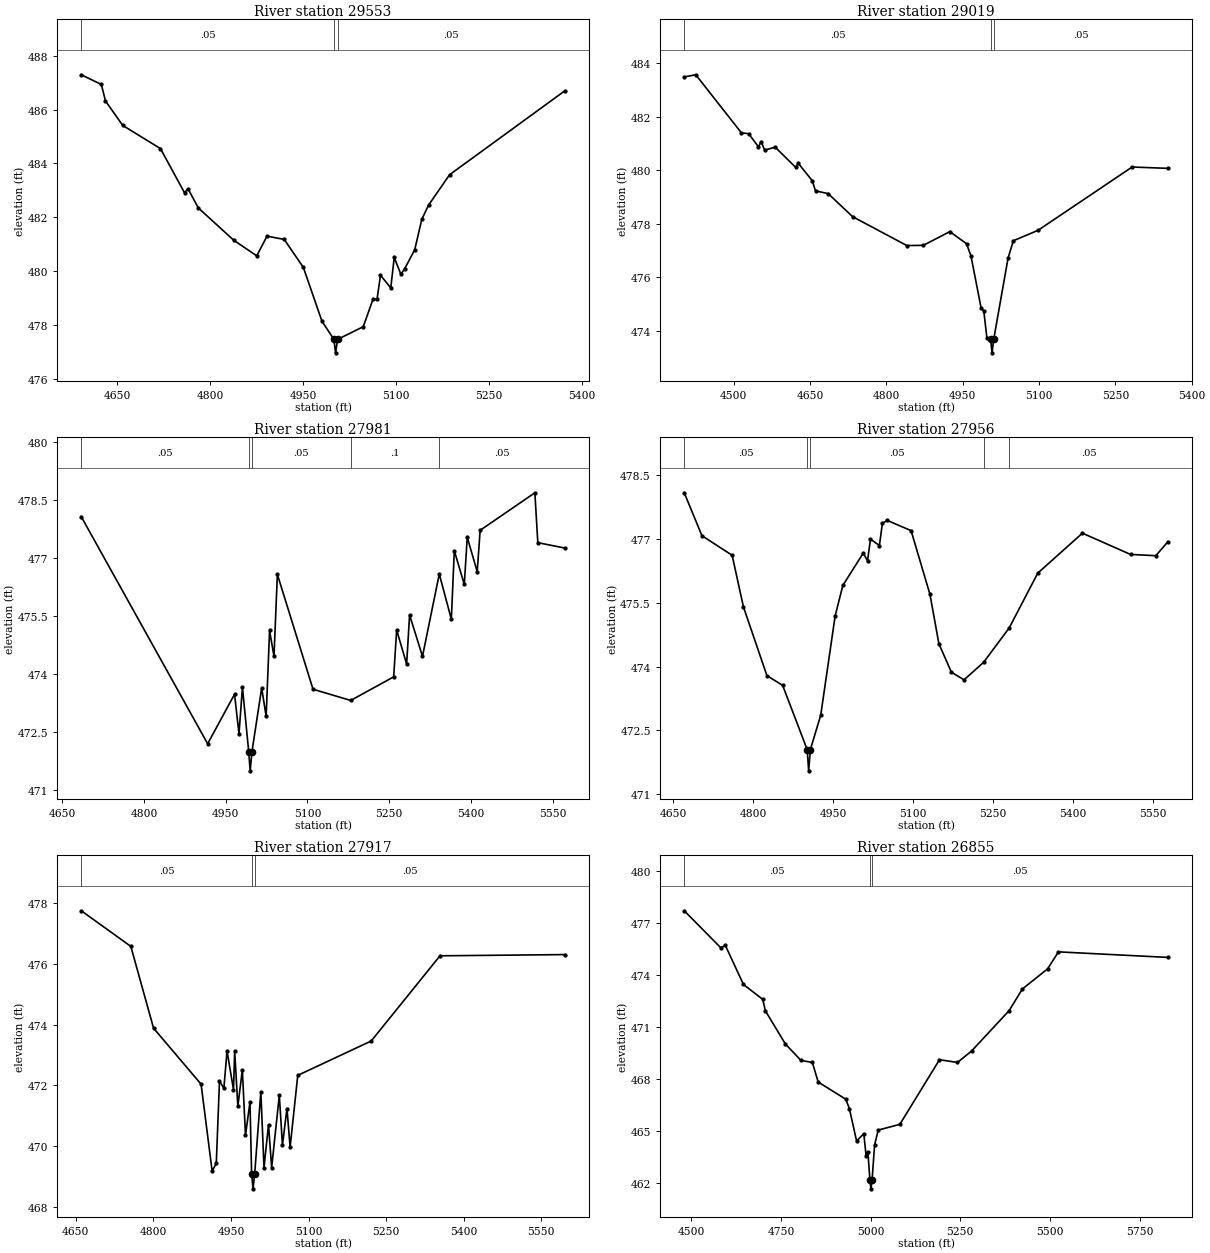
Type RM Length L Ch R = 1 ,29553   ,534,534,534
BEGIN DESCRIPTION:
BEAR BRANCH 55.0
END DESCRIPTION:
XS GIS Cut Line= 2
      3565050.96     10548898.36      3564356.36     10549254.77
#Sta/Elev= 30
  4592.3  487.29  4624.7  486.93  4631.3  486.32  4659.2  485.41  4720.1  484.55
  4758.9  482.91  4764.5  483.06  4781.1  482.35  4838.3  481.15  4875.5  480.57
    4892   481.3  4919.8  481.18  4950.7  480.14  4980.8  478.14    5000  477.47
  5002.7  476.97    5006  477.47  5047.4  477.94  5063.1  478.96  5069.6  478.95
  5075.2  479.85  5091.8  479.38  5097.4  480.51    5108  479.89    5114  480.08
  5130.5   480.8  5141.8  481.92  5152.7  482.45  5186.7  483.58    5373   486.7
#Mann= 3 ,-1 , 0
  4592.3     .05       0    5000     .03       0    5006     .05       0
Bank Sta=5000,5006
XS Rating Curve= 0 ,0
Exp/Cntr=0.3,0.1

Type RM Length L Ch R = 1 ,29019   ,1038,1038,1038
BEGIN DESCRIPTION:
BEAR BRANCH 53.0
END DESCRIPTION:
XS GIS Cut Line= 2
      3565043.97     10548455.67      3564129.94     10548716.08
#Sta/Elev= 30
  4402.9  483.48  4425.6  483.56    4515   481.4  4529.6  481.36  4548.8  480.87
    4554  481.07  4560.8  480.75  4581.6  480.86  4621.7  480.11  4626.9  480.26
  4654.4  479.61  4660.8  479.23  4685.6  479.13  4733.6  478.27  4840.4  477.19
  4872.7   477.2  4924.7  477.71  4957.5  477.26  4966.3   476.8  4986.2  474.86
  4991.4  474.76  4997.5  473.76  5004.9  473.69  5007.7  473.19  5010.9  473.69
  5039.1  476.72  5049.5  477.37  5098.1  477.76  5282.9  480.12  5353.3  480.07
#Mann= 3 ,-1 , 0
  4402.9     .05       0  5004.9     .03       0  5010.9     .05       0
Bank Sta=5004.9,5010.9
XS Rating Curve= 0 ,0
Exp/Cntr=0.3,0.1

Type RM Length L Ch R = 1 ,27981   ,25,25,25
BEGIN DESCRIPTION:
BEAR BRANCH 51.02
END DESCRIPTION:
XS GIS Cut Line= 5
      3564628.18     10547607.59      3564400.77     10547756.88
      3564346.95     10547826.32      3564333.07     10547923.54
      3564166.39     10548319.39
#Sta/Elev= 30
    4685  478.06  4916.9  472.19  4966.2  473.47  4974.4  472.45  4980.7  473.65
  4992.2  471.99  4994.9  471.49  4998.2  471.99    5016  473.63  5024.2   472.9
  5030.5  475.12  5038.6  474.45  5044.8  476.57  5110.2   473.6  5179.3  473.31
  5258.2  473.92  5263.7  475.13    5282  474.25  5287.4  475.52  5311.1  474.45
  5341.9  476.58    5364  475.41  5369.5  477.18  5387.8  476.31  5393.2  477.53
  5411.5  476.64  5416.9  477.71  5517.3  478.68  5522.7  477.39  5572.6  477.25
#Mann= 5 ,-1 , 0
    4685     .05       0  4992.2     .03       0  4998.2     .05       0
  5179.3      .1       0  5341.9     .05       0
Bank Sta=4992.2,4998.2
XS Rating Curve= 0 ,0
Exp/Cntr=0.3,0.1

Type RM Length L Ch R = 1 ,27956   ,39,39,39
BEGIN DESCRIPTION:
BEAR BRANCH 51.0
END DESCRIPTION:
XS GIS Cut Line= 4
      3564612.59     10547576.31      3564367.79     10547749.93
      3564282.72     10547918.34      3564128.33      10548306.9
#Sta/Elev= 30
  4670.7  478.09  4703.9  477.08  4760.5  476.62  4781.6  475.41  4825.7  473.79
  4855.2  473.56  4901.2  472.05    4904  471.55  4907.2  472.05  4926.6  472.86
  4953.6  475.19    4968  475.91  5006.3  476.67  5014.3  476.49  5019.9     477
  5036.6  476.85  5042.2  477.37  5051.2  477.44    5096   477.2  5131.4   475.7
  5148.1  474.54  5171.6  473.87  5195.3  473.69  5231.8   474.1  5279.9  474.91
  5333.5   476.2  5417.2  477.14  5507.4  476.64  5554.8  476.61  5577.6  476.94
#Mann= 5 ,-1 , 0
  4670.7     .05       0  4901.2     .03       0  4907.2     .05       0
  5231.8      .1       0  5279.9     .05       0
Bank Sta=4901.2,4907.2
XS Rating Curve= 0 ,0
Exp/Cntr=0.3,0.1

Type RM Length L Ch R = 1 ,27917   ,1062,1062,1062
BEGIN DESCRIPTION:
BEAR BRANCH 51.01
END DESCRIPTION:
XS GIS Cut Line= 4
       3564586.5     10547541.63      3564348.69     10547715.21
      3564251.47      10547854.1       3564079.6     10548293.31
#Sta/Elev= 30
  4660.5  477.74  4756.3  476.57  4800.3  473.88  4892.2  472.04  4913.6  469.18
  4921.6  469.44  4927.8  472.14  4936.3  471.91  4942.4  473.13  4954.9  471.86
  4957.2  473.12  4963.3  471.31    4972  472.51  4978.1  470.36  4986.8  471.46
  4989.9   469.1  4992.7   468.6  4995.9   469.1  5007.8  471.79  5013.9   469.3
  5022.6   470.7  5028.7   469.3  5043.5  471.67  5049.6  470.04  5058.3  471.24
  5064.4  469.97  5079.2  472.33  5221.3  473.46  5354.3  476.26  5596.1   476.3
#Mann= 3 ,-1 , 0
  4660.5     .05       0  4989.9     .03       0  4995.9     .05       0
Bank Sta=4989.9,4995.9
XS Rating Curve= 0 ,0
Exp/Cntr=0.3,0.1

Type RM Length L Ch R = 1 ,26855   ,616,616,616
BEGIN DESCRIPTION:
BEAR BRANCH 50.0
END DESCRIPTION:
XS GIS Cut Line= 3
       3564507.7     10547364.99      3564127.94     10547226.11
      3563188.24      10547321.6
#Sta/Elev= 30
  4480.4  477.72  4582.2  475.59  4595.1  475.72  4645.5  473.47  4699.3  472.61
  4706.6  471.95  4762.3  470.04  4805.8  469.09  4837.7  468.97  4853.9  467.84
  4930.8  466.85  4940.9  466.31    4961  464.44  4981.1  464.86  4987.5   463.6
  4992.5  463.82  4998.2  462.18  5000.9  461.68  5004.2  462.18  5011.2  464.21
  5021.3  465.07  5081.6   465.4  5192.2  469.13  5242.4  468.97  5281.6  469.63
  5386.4  471.96  5423.4  473.21  5493.7  474.37  5523.9  475.35  5829.3  475.03
#Mann= 3 ,-1 , 0
  4480.4     .05       0  4998.2     .03       0  5004.2     .05       0
Bank Sta=4998.2,5004.2
XS Rating Curve= 0 ,0
Exp/Cntr=0.3,0.1

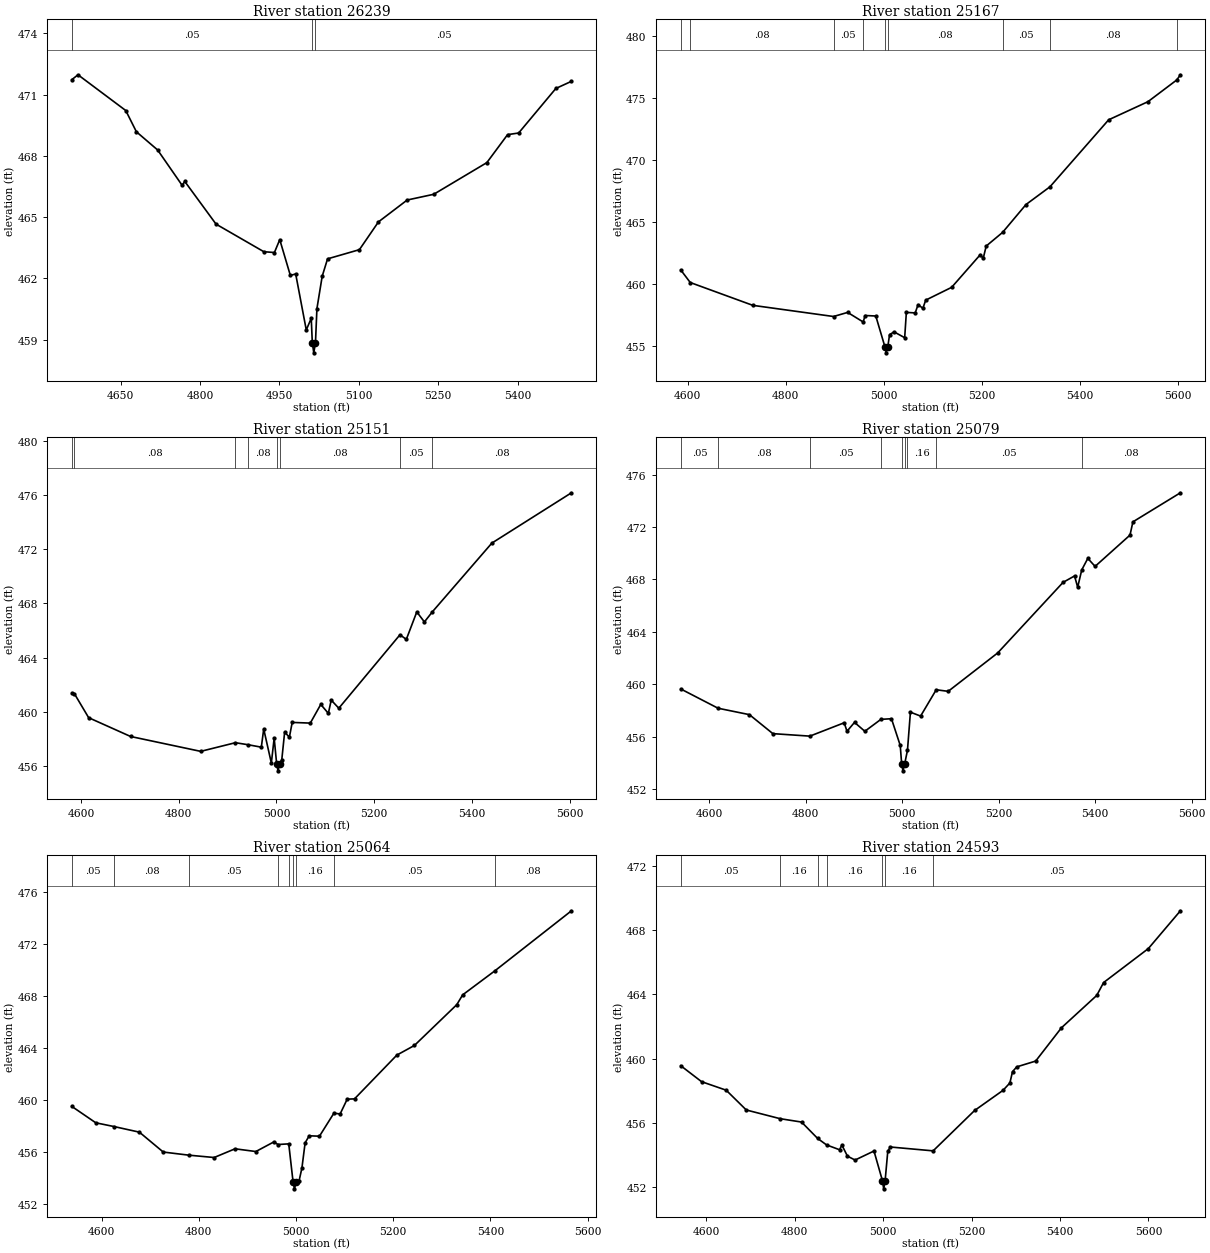
Type RM Length L Ch R = 1 ,26239   ,1072,1072,1072
BEGIN DESCRIPTION:
BEAR BRANCH 48.0
END DESCRIPTION:
XS GIS Cut Line= 2
      3564383.69      10546733.6      3563442.68     10546657.21
#Sta/Elev= 30
  4557.7  471.73  4569.3  471.97  4659.6  470.22  4679.7  469.18  4719.8  468.29
  4766.1  466.56  4771.1  466.75  4830.2  464.66  4920.5  463.31  4940.5  463.27
  4950.6   463.9  4970.6  462.15  4980.7  462.22  5000.7  459.48  5010.1  460.05
  5012.1  458.86  5014.9  458.36  5018.1  458.86  5020.8  460.52  5030.8  462.11
  5040.9  462.96  5101.1  463.41  5137.1  464.77  5191.4  465.84  5241.5  466.12
  5341.9  467.67  5381.1  469.04    5402  469.12  5472.3   471.3  5501.8  471.65
#Mann= 3 ,-1 , 0
  4557.7     .05       0  5012.1     .03       0  5018.1     .05       0
Bank Sta=5012.1,5018.1
XS Rating Curve= 0 ,0
Exp/Cntr=0.3,0.1

Type RM Length L Ch R = 1 ,25167   ,16,16,16
BEGIN DESCRIPTION:
BEAR BRANCH 46.01
END DESCRIPTION:
XS GIS Cut Line= 4
      3564424.91     10545954.73      3564128.06     10545729.49
      3564051.24     10545685.22      3563570.76     10545402.66
#Sta/Elev= 30
  4585.9  461.15  4605.2  460.14  4732.7   458.3  4897.3   457.4  4926.1  457.73
  4957.7  456.96  4961.9  457.48  4983.5  457.44    5002  454.97  5004.8  454.47
    5008  454.97  5011.6  455.94  5020.8  456.16  5042.4  455.69  5045.8  457.73
  5063.9  457.69  5069.7  458.36  5079.5  458.06  5085.3  458.72  5138.1  459.75
  5196.7  462.39  5202.5  462.08  5208.6  463.08    5242  464.18  5289.8  466.43
  5338.7  467.86  5458.3  473.26  5538.4  474.72  5597.1  476.47  5604.6  476.89
#Mann= 9 ,-1 , 0
  4585.9     .05       0  4605.2     .08       0  4897.3     .05       0
  4957.7     .08       0    5002     .07       0    5008     .08       0
    5242     .05       0  5338.7     .08       0  5597.1     .05       0
Bank Sta=5002,5008
XS Rating Curve= 0 ,0
Exp/Cntr=0.3,0.1

Type RM Length L Ch R = 1 ,25151   ,72,72,72
BEGIN DESCRIPTION:
BEAR BRANCH 46.0
END DESCRIPTION:
XS GIS Cut Line= 3
      3564435.37     10545936.53      3564125.46     10545711.26
      3563577.29     10545383.14
#Sta/Elev= 30
  4581.4  461.34  4586.7  461.32  4615.8  459.55  4701.6  458.16    4845  457.06
    4916   457.7    4942  457.55    4969  457.37  4973.9  458.71  4989.5   456.2
  4995.3  458.04  5000.4  456.12  5003.2  455.62  5006.4  456.12  5010.8  456.42
  5016.7  458.48  5026.4  458.11  5032.2   459.2  5069.2  459.15  5090.6  460.53
  5106.1  459.87    5112  460.85  5127.5  460.25  5252.6  465.68  5265.6  465.34
    5287  467.37  5302.6  466.63  5318.7  467.37  5440.6  472.46  5603.4  476.18
#Mann= 8 ,-1 , 0
  4581.4     .05       0  4586.7     .08       0    4916     .05       0
    4942     .08       0  5000.4     .07       0  5006.4     .08       0
  5252.6     .05       0  5318.7     .08       0
Bank Sta=5000.4,5006.4
XS Rating Curve= 0 ,0
Exp/Cntr=0.3,0.1

Type RM Length L Ch R = 1 ,25079   ,15,15,15
BEGIN DESCRIPTION:
BEAR BRANCH 46.02
END DESCRIPTION:
XS GIS Cut Line= 3
      3564514.75     10545862.29      3564139.78     10545638.34
      3563638.47     10545310.22
#Sta/Elev= 30
  4540.9  459.63  4618.2  458.16  4683.2  457.67  4731.8  456.22  4808.5  456.03
  4879.7  457.05  4885.5   456.4  4901.1  457.08  4922.5   456.4  4955.8  457.31
  4977.7  457.36  4995.9  455.32  4998.9  453.88  5001.6  453.38  5004.9  453.88
  5010.9  454.95    5017  457.86  5038.1  457.56  5070.5  459.57  5095.3  459.45
  5197.9  462.38  5333.5  467.77  5357.3  468.26  5363.8   467.4  5372.2  468.72
  5384.8   469.6  5399.9  468.99  5472.3  471.38  5478.3  472.39  5576.8  474.61
#Mann= 9 ,-1 , 0
  4540.9     .05       0  4618.2     .08       0  4808.5     .05       0
  4955.8     .08       0  4998.9     .07       0  5004.9     .08       0
  5010.9     .16       0  5070.5     .05       0  5372.2     .08       0
Bank Sta=4998.9,5004.9
XS Rating Curve= 0 ,0
Exp/Cntr=0.3,0.1

Type RM Length L Ch R = 1 ,25064   ,471,471,471
BEGIN DESCRIPTION:
BEAR BRANCH 46.03
END DESCRIPTION:
XS GIS Cut Line= 3
      3564523.86     10545849.26      3564142.38     10545622.72
      3563655.59     10545299.49
#Sta/Elev= 30
  4538.7  459.54    4588  458.28  4625.7  457.99  4677.7  457.56  4726.8  456.03
  4779.5  455.79  4831.5  455.61  4874.5  456.28  4917.3  456.07  4954.4  456.81
  4962.8  456.61    4985  456.66    4994   453.7  4996.8   453.2    5000   453.7
  5006.1  453.79  5012.1   454.8  5018.7  456.74  5027.1  457.28  5048.2  457.25
  5077.9  459.02  5090.7  458.96  5105.3   460.1  5120.3  460.12  5207.5  463.49
  5243.6  464.23  5330.8  467.37  5342.8  468.12  5409.1  469.97  5566.7  474.59
#Mann= 9 ,-1 , 0
  4538.7     .05       0  4625.7     .08       0  4779.5     .05       0
  4962.8     .08       0    4985     .16       0    4994     .07       0
    5000     .16       0  5077.9     .05       0  5409.1     .08       0
Bank Sta=4994,5000
XS Rating Curve= 0 ,0
Exp/Cntr=0.3,0.1

Type RM Length L Ch R = 1 ,24593   ,415,415,415
BEGIN DESCRIPTION:
BEAR BRANCH 45.0
END DESCRIPTION:
XS GIS Cut Line= 4
      3564526.86     10545858.42      3564577.97     10545607.27
      3564531.59     10545494.34      3563885.98     10545108.71
#Sta/Elev= 30
  4541.9  459.56  4588.9  458.57  4644.6  458.04  4690.1  456.81  4766.6  456.27
  4815.1  456.06  4851.6  455.04  4871.7  454.64    4901  454.34  4906.4  454.63
    4919  453.94  4936.2   453.7    4979  454.26  4998.2  452.41    5001  451.91
  5004.2  452.41  5010.2  454.24    5016  454.51  5112.8  454.27  5206.7  456.78
  5270.9  458.03  5286.5  458.49  5292.4  459.19    5302  459.49  5344.8  459.85
  5403.2  461.92    5483  463.93  5498.5  464.73  5599.7  466.84  5672.3  469.19
#Mann= 7 ,-1 , 0
  4541.9     .05       0  4766.6     .16       0  4851.6     .05       0
  4871.7     .16       0  4998.2     .07       0  5004.2     .16       0
  5112.8     .05       0
Bank Sta=4998.2,5004.2
XS Rating Curve= 0 ,0
Exp/Cntr=0.3,0.1

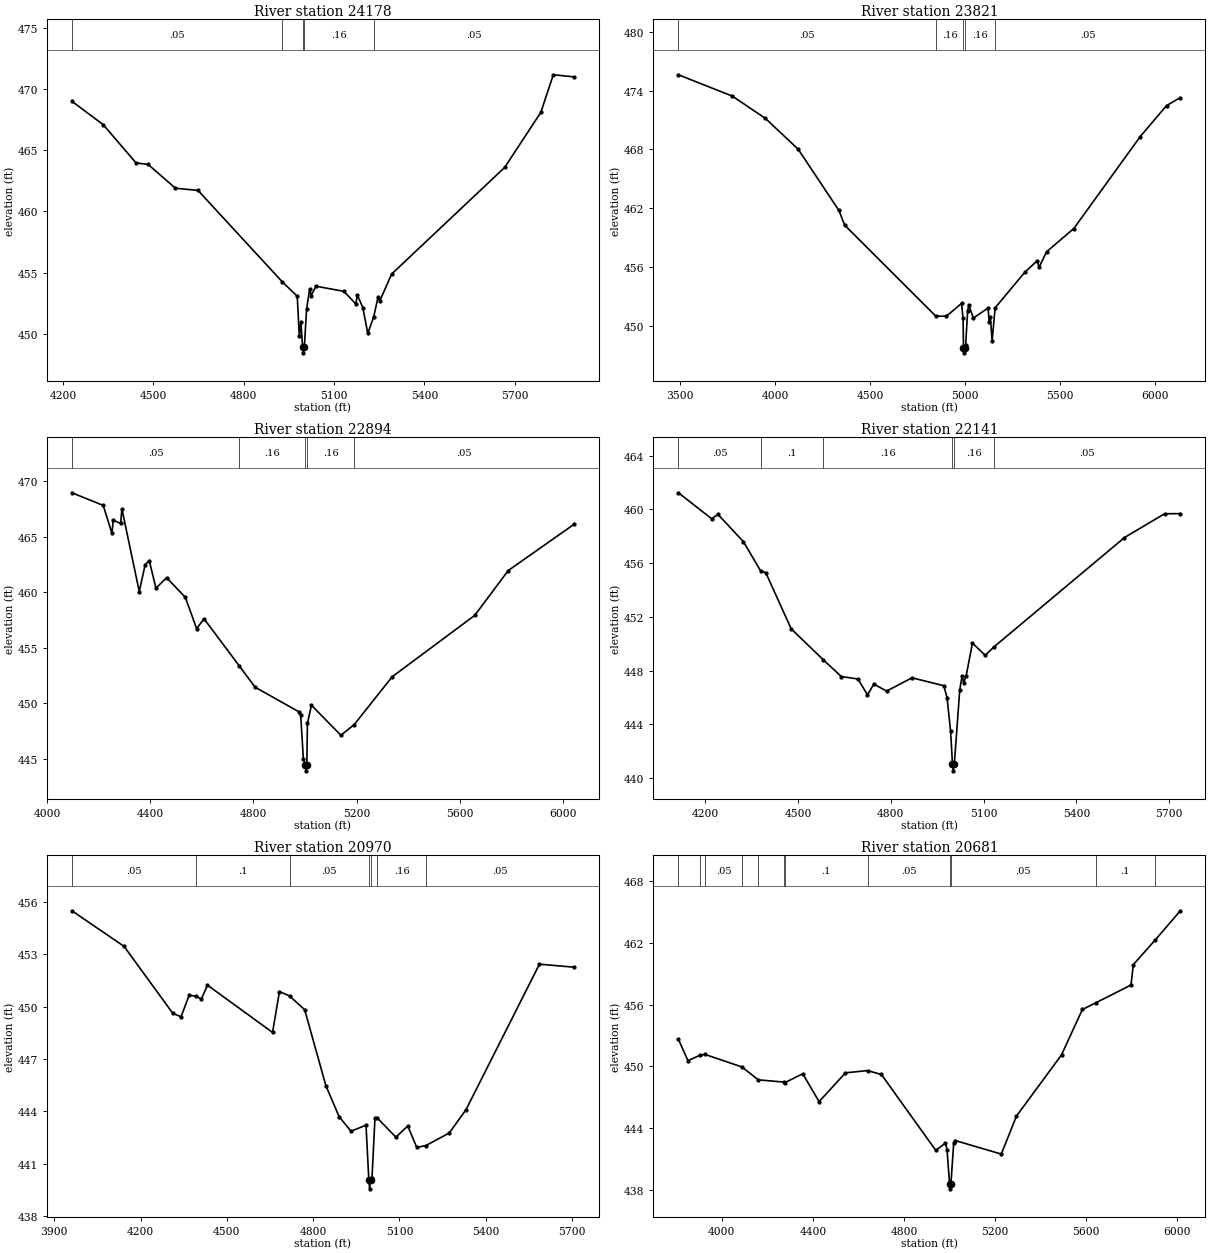
Type RM Length L Ch R = 1 ,24178   ,357,357,357
BEGIN DESCRIPTION:
BEAR BRANCH 44.0
END DESCRIPTION:
XS GIS Cut Line= 3
      3565463.12     10545249.22      3564765.21     10545160.68
      3563836.28     10544905.68
#Sta/Elev= 30
  4229.7  468.99  4333.1   467.1  4442.4  463.97  4482.7  463.84  4573.4   461.9
  4648.3  461.72  4927.3  454.28  4977.9  453.08  4984.7  449.81  4989.9  450.98
  4995.6  448.96  4998.4  448.46  5001.6  448.96    5009  452.05  5019.1  453.66
  5024.3  453.14  5040.1   453.9  5132.8  453.48  5172.4  452.45  5177.6  453.17
  5195.7  452.15  5212.1  450.05  5231.5  451.37  5246.5  453.04  5251.7  452.68
  5291.3  454.89  5666.9   463.6  5786.8  468.09  5828.2  471.16  5896.5  470.99
#Mann= 5 ,-1 , 0
  4229.7     .05       0  4927.3     .16       0  4995.6     .07       0
  5001.6     .16       0  5231.5     .05       0
Bank Sta=4995.6,5001.6
XS Rating Curve= 0 ,0
Exp/Cntr=0.3,0.1

Type RM Length L Ch R = 1 ,23821   ,927,927,927
BEGIN DESCRIPTION:
BEAR BRANCH 42.0
END DESCRIPTION:
XS GIS Cut Line= 3
      3566210.47     10545126.82      3564809.48     10544842.97
      3563679.25     10544400.26
#Sta/Elev= 30
  3491.4  475.62  3775.4  473.44  3949.8  471.16  4122.3  468.01  4336.6  461.76
  4367.2  460.25  4846.9  450.96  4902.6  450.95  4982.5  452.26  4990.5  450.72
  4992.8  447.71  4995.6  447.21  4998.8  447.71    5004     448  5014.7   451.5
  5020.3  452.12  5044.7  450.76  5122.1  451.79  5128.8  450.31  5134.2  450.85
  5143.6  448.45  5159.4  451.81  5315.4  455.44  5381.1  456.62  5390.6  455.94
    5430  457.53  5573.7  459.91  5923.7  469.31  6062.1  472.47  6134.7  473.29
#Mann= 5 ,-1 , 0
  3491.4     .05       0  4846.9     .16       0  4992.8     .07       0
  4998.8     .16       0  5159.4     .05       0
Bank Sta=4992.8,4998.8
XS Rating Curve= 0 ,0
Exp/Cntr=0.3,0.1

Type RM Length L Ch R = 1 ,22894   ,753,753,753
BEGIN DESCRIPTION:
BEAR BRANCH 41.0
END DESCRIPTION:
XS GIS Cut Line= 3
      3565955.31     10544389.85      3564473.54     10543962.77
      3564067.34     10543965.37
#Sta/Elev= 30
  4095.4  468.96  4216.9  467.82  4250.5  465.31  4255.7  466.48  4284.2   466.2
  4289.4  467.49  4356.7  460.06  4379.7  462.49  4395.6  462.85  4421.4  460.36
  4462.9  461.31  4535.4  459.54  4579.5  456.71    4608  457.61  4745.5  453.34
  4806.4  451.44  4975.8  449.23  4983.3   448.9  4993.7     445  5001.1   444.4
  5003.9   443.9  5007.1   444.4  5009.5  448.17    5025  449.81  5139.4  447.11
  5190.8  448.06  5338.5  452.38  5658.9  457.91  5788.9  461.95  6043.7  466.11
#Mann= 5 ,-1 , 0
  4095.4     .05       0  4745.5     .16       0  5001.1     .07       0
  5007.1     .16       0  5190.8     .05       0
Bank Sta=5001.1,5007.1
XS Rating Curve= 0 ,0
Exp/Cntr=0.3,0.1

Type RM Length L Ch R = 1 ,22141   ,1171,1171,1171
BEGIN DESCRIPTION:
BEAR BRANCH 40.0
END DESCRIPTION:
XS GIS Cut Line= 3
      3565876.59     10543829.14      3564715.13      10543553.1
      3564295.15     10543636.06
#Sta/Elev= 30
  4113.9  461.23  4221.3   459.3  4241.8  459.62  4324.1  457.59  4380.6  455.38
    4396   455.3  4478.3  451.11    4582  448.81  4640.6  447.56  4694.1  447.38
  4724.9   446.2  4745.5     447  4786.6  446.48  4868.8  447.47  4971.6  446.88
  4981.9     446  4993.5  443.49  4999.5  441.05  5002.2  440.55  5005.5  441.05
    5023  446.57  5030.5   447.6  5035.7  447.11  5043.6   447.6  5064.1  450.05
  5105.2  449.14  5134.2  449.78  5555.4   457.9    5685  459.67  5735.8  459.68
#Mann= 6 ,-1 , 0
  4113.9     .05       0  4380.6      .1       0    4582     .16       0
  4999.5     .07       0  5005.5     .16       0  5134.2     .05       0
Bank Sta=4999.5,5005.5
XS Rating Curve= 0 ,0
Exp/Cntr=0.3,0.1

Type RM Length L Ch R = 1 ,20970   ,289,289,289
BEGIN DESCRIPTION:
BEAR BRANCH 39.0
END DESCRIPTION:
XS GIS Cut Line= 4
      3566027.66     10543271.88      3565501.58     10542792.68
      3564996.38     10542652.06      3564735.94     10543089.59
#Sta/Elev= 30
  3961.4  455.49  4142.7  453.45  4312.3  449.61  4340.7  449.42    4369  450.65
  4391.5   450.6  4411.6  450.44  4432.6  451.23  4658.9  448.52  4682.8  450.86
    4718  450.61  4770.6  449.82  4844.2  445.48  4890.4  443.69    4932  442.86
  4983.9  443.21  4993.7  440.06  4996.4  439.56  4999.7  440.06  5004.6  440.16
    5015   443.6  5022.6  443.63  5087.7  442.52  5129.2  443.16  5160.3  441.93
  5192.1  442.04  5273.4  442.76  5331.8   444.1  5586.9  452.43  5706.6  452.26
#Mann= 7 ,-1 , 0
  3961.4     .05       0  4391.5      .1       0    4718     .05       0
  4993.7     .03       0  4999.7     .05       0  5022.6     .16       0
  5192.1     .05       0
Bank Sta=4993.7,4999.7
XS Rating Curve= 0 ,0
Exp/Cntr=0.3,0.1

Type RM Length L Ch R = 1 ,20681   ,372,372,372
BEGIN DESCRIPTION:
BEAR BRANCH 38.0
END DESCRIPTION:
XS GIS Cut Line= 4
      3566236.58     10543106.01       3565387.6     10542522.66
      3564996.98     10542272.66      3564299.09     10542145.06
#Sta/Elev= 30
  3809.6  452.63  3851.4  450.54    3905  451.08  3926.5  451.15  4088.8  449.93
  4160.1  448.68  4272.5  448.46    4277  448.41  4355.4  449.27  4427.1  446.56
    4543  449.36    4640  449.58  4700.7   449.2  4939.4  441.82  4981.7  442.53
  4988.7   441.9  4999.9  438.58  5002.6  438.08  5005.9  438.58  5018.1  442.54
  5024.3  442.78    5227  441.46  5293.7  445.16  5491.4  451.11  5582.9  455.52
    5641  456.16  5796.4   457.9  5806.5  459.88  5900.7  462.23  6012.9  465.12
#Mann= 12 ,-1 , 0
  3809.6     .05       0    3905     .16       0  3926.5     .05       0
  4088.8     .16       0  4160.1      .1       0  4272.5     .05       0
    4277      .1       0    4640     .05       0  4999.9     .03       0
  5005.9     .05       0    5641      .1       0  5900.7     .05       0
Bank Sta=4999.9,5005.9
XS Rating Curve= 0 ,0
Exp/Cntr=0.3,0.1

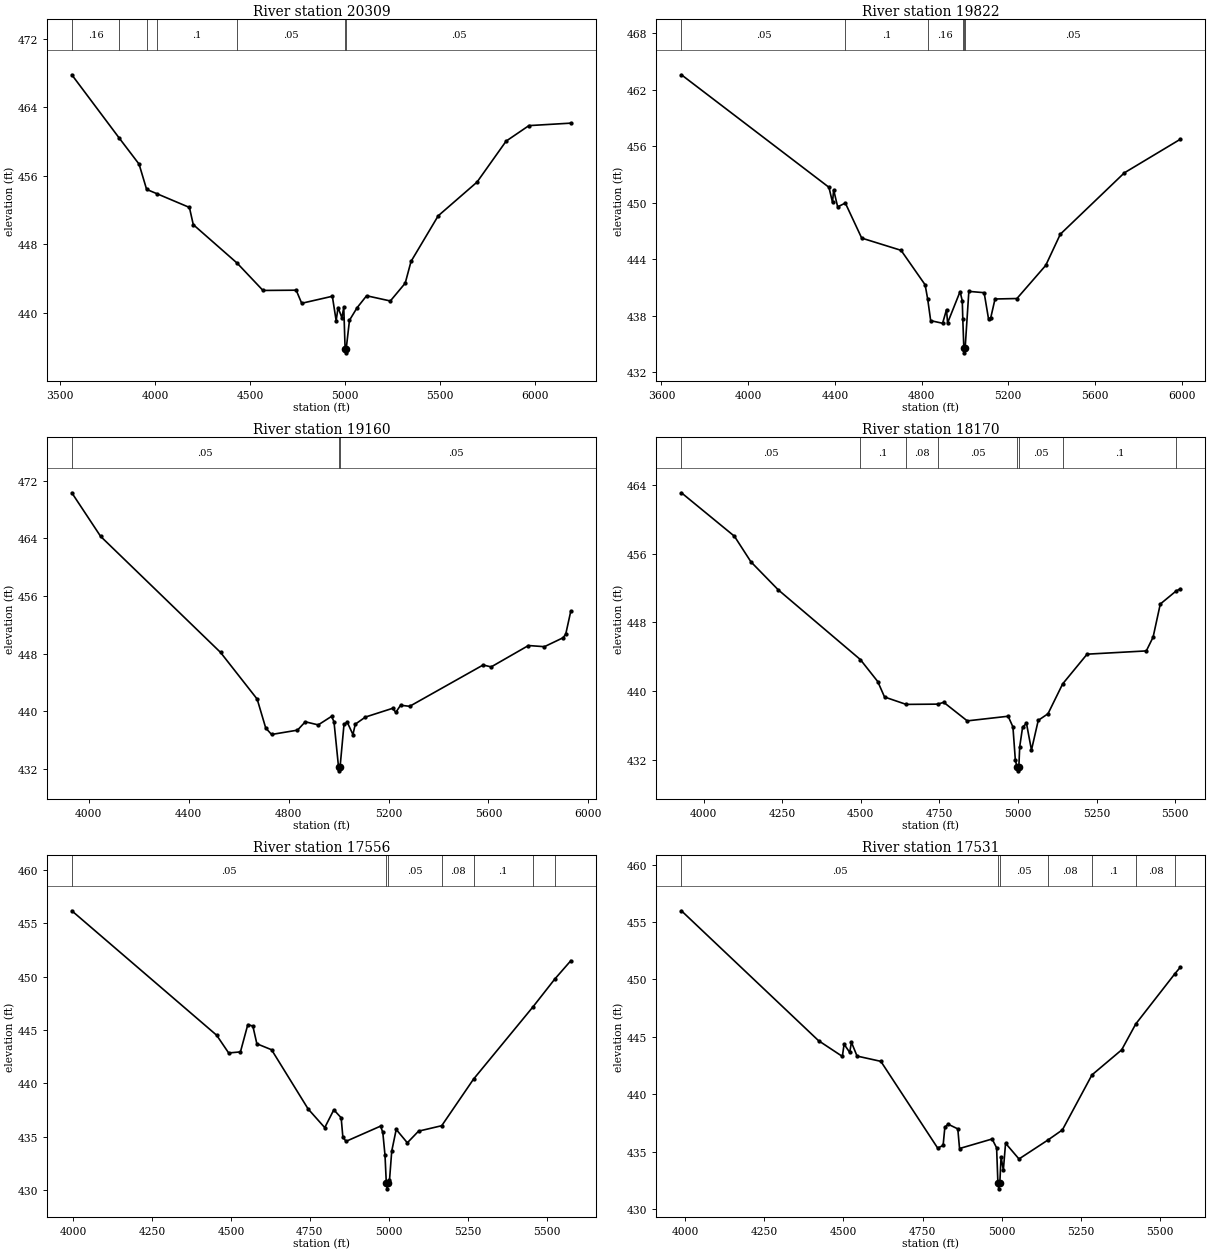
Type RM Length L Ch R = 1 ,20309   ,487,487,487
BEGIN DESCRIPTION:
BEAR BRANCH 37.0
END DESCRIPTION:
XS GIS Cut Line= 4
      3566809.49     10542353.39      3565562.08      10542108.6
      3565226.14     10542090.37       3564228.7     10541882.03
#Sta/Elev= 30
  3562.2  467.79  3811.6   460.4  3916.2  457.35  3955.9   454.4  4011.6  453.88
  4181.2  452.29  4201.5  450.28  4432.5  445.78  4568.4  442.59  4743.2  442.62
  4772.2  441.09  4933.5  441.91  4953.5  439.06  4963.6  440.59  4983.6  439.41
  4993.6  440.61  5000.6   435.8  5003.4   435.3  5006.6   435.8  5023.7  439.11
  5063.7  440.57  5113.8  441.97  5238.7  441.36    5317  443.44  5347.6  445.98
  5490.6  451.31    5695  455.25  5848.2  460.04  5968.1  461.85  6188.8  462.14
#Mann= 7 ,-1 , 0
  3562.2     .16       0  3811.6      .1       0  3955.9     .05       0
  4011.6      .1       0  4432.5     .05       0  5000.6     .03       0
  5006.6     .05       0
Bank Sta=5000.6,5006.6
XS Rating Curve= 0 ,0
Exp/Cntr=0.3,0.1

Type RM Length L Ch R = 1 ,19822   ,662,662,662
BEGIN DESCRIPTION:
BEAR BRANCH 36.0
END DESCRIPTION:
XS GIS Cut Line= 3
      3566826.63     10541809.48      3565090.51     10541576.84
      3564546.21     10541663.51
#Sta/Elev= 30
  3692.1  463.59  4372.7  451.64  4389.4  450.03  4394.5  451.37    4413  449.56
  4448.5  449.96    4524  446.24  4705.6  444.94  4816.6  441.28  4828.6  439.74
  4842.3  437.47  4897.3  437.19  4915.3  438.64  4920.3  437.23    4978  440.56
  4988.1  439.56  4990.5  437.65  4995.3  434.55  4998.1  434.05  5001.3  434.55
  5018.4  440.58    5089  440.44  5109.2  437.66  5119.3  437.76  5139.2  439.77
  5240.3  439.82  5373.2  443.34  5440.4  446.65  5735.8  453.17  5994.9  456.75
#Mann= 6 ,-1 , 0
  3692.1     .05       0  4448.5      .1       0  4828.6     .16       0
  4990.5     .05       0  4995.3     .03       0  5001.3     .05       0
Bank Sta=4995.3,5001.3
XS Rating Curve= 0 ,0
Exp/Cntr=0.3,0.1

Type RM Length L Ch R = 1 ,19160   ,990,990,990
BEGIN DESCRIPTION:
BEAR BRANCH 35.0
END DESCRIPTION:
XS GIS Cut Line= 3
      3566502.16      10540756.7      3565516.07     10541032.73
       3564602.9     10541371.26
#Sta/Elev= 30
  3932.1  470.33  4047.4  464.28  4527.4  448.17  4674.2  441.68  4708.4  437.67
  4731.8  436.77  4835.6  437.37  4866.8  438.53  4918.7   438.1  4971.8  439.28
  4981.7  438.55    5000  432.22  5002.7  431.72    5006  432.22  5021.9   438.2
    5035  438.46  5057.6  436.76    5067   438.2  5107.7  439.19  5216.3   440.4
  5229.3  439.84  5248.3  440.83  5284.7  440.68  5578.9  446.42  5610.9  446.15
  5760.2  449.12  5824.2  448.96  5898.9   450.2  5909.5   450.7    5930  453.93
#Mann= 3 ,-1 , 0
  3932.1     .05       0    5000     .03       0    5006     .05       0
Bank Sta=5000,5006
XS Rating Curve= 0 ,0
Exp/Cntr=0.3,0.1

Type RM Length L Ch R = 1 ,18170   ,614,614,614
BEGIN DESCRIPTION:
BEAR BRANCH 33.0
END DESCRIPTION:
XS GIS Cut Line= 2
       3566174.1      10540003.2      3564796.38      10540792.7
#Sta/Elev= 30
  3929.2  463.08  4097.8  458.02  4150.5  455.03  4237.4  451.77  4498.6  443.65
  4553.9  441.09  4575.5  439.29  4644.3  438.43  4744.9  438.46  4763.9  438.67
  4838.7  436.51  4968.8  437.05    4984  435.81  4991.8   431.9  4996.9  431.19
  4999.6  430.69  5002.9  431.19  5005.6   433.5  5014.9   435.8  5027.2  436.21
    5043  433.11  5064.6  436.57  5095.6  437.34  5142.3  440.82    5220  444.28
  5408.4  444.66    5430  446.26  5452.9  450.12    5504  451.66  5517.1  451.89
#Mann= 8 ,-1 , 0
  3929.2     .05       0  4498.6      .1       0  4644.3     .08       0
  4744.9     .05       0  4996.9     .03       0  5002.9     .05       0
  5142.3      .1       0    5504     .05       0
Bank Sta=4996.9,5002.9
XS Rating Curve= 0 ,0
Exp/Cntr=0.3,0.1

Type RM Length L Ch R = 1 ,17556   ,25,25,25
BEGIN DESCRIPTION:
BEAR BRANCH 32.03
END DESCRIPTION:
XS GIS Cut Line= 5
      3565996.14     10539770.51      3565150.66      10540145.5
      3565020.46     10540279.18      3564928.44     10540305.22
      3564676.06     10540580.08
#Sta/Elev= 30
  3996.2  456.16  4454.9  444.51  4492.9  442.85  4530.2  442.95  4553.5   445.5
  4569.5  445.37  4582.2  443.71  4628.8  443.15  4744.5  437.61  4797.2  435.86
  4825.9  437.53  4849.2  436.78  4854.6  434.95  4864.8  434.58  4973.9     436
    4981  435.42    4988  433.27  4992.2  430.63  4994.9  430.13  4998.2  430.63
  5002.2  430.92  5009.3  433.66  5023.5  435.69  5058.7  434.44  5094.2  435.53
  5167.6  436.04  5268.3   440.4  5456.4  447.16  5525.4  449.76  5576.5  451.49
#Mann= 7 ,-1 , 0
  3996.2     .05       0  4992.2     .03       0  4998.2     .05       0
  5167.6     .08       0  5268.3      .1       0  5456.4     .08       0
  5525.4     .05       0
Bank Sta=4992.2,4998.2
XS Rating Curve= 0 ,0
Exp/Cntr=0.3,0.1

Type RM Length L Ch R = 1 ,17531   ,49,49,49
BEGIN DESCRIPTION:
BEAR BRANCH 32.02
END DESCRIPTION:
XS GIS Cut Line= 5
      3565981.37      10539749.5      3565135.04      10540127.1
      3564997.02     10540267.72       3564921.5     10540282.65
      3564661.07     10540553.49
#Sta/Elev= 30
  3988.4  455.98  4421.6  444.67  4496.8   443.3  4502.3  444.36    4520  443.65
  4525.5  444.53  4543.2  443.33  4618.4  442.87  4797.9  435.32  4815.1  435.55
  4820.6  437.13  4830.8   437.4  4861.5  436.99    4867  435.28  4969.9  436.11
  4984.1  435.34  4988.2  432.27    4991  431.77  4994.2  432.27  4998.2  434.54
  5005.4  433.41  5012.4  435.74  5054.8  434.37  5146.2  436.02  5191.9   436.9
  5285.3  441.69  5379.1  443.87  5423.8  446.13  5547.6  450.51  5564.9  451.08
#Mann= 7 ,-1 , 0
  3988.4     .05       0  4988.2     .03       0  4994.2     .05       0
  5146.2     .08       0  5285.3      .1       0  5423.8     .08       0
  5547.6     .05       0
Bank Sta=4988.2,4994.2
XS Rating Curve= 0 ,0
Exp/Cntr=0.3,0.1

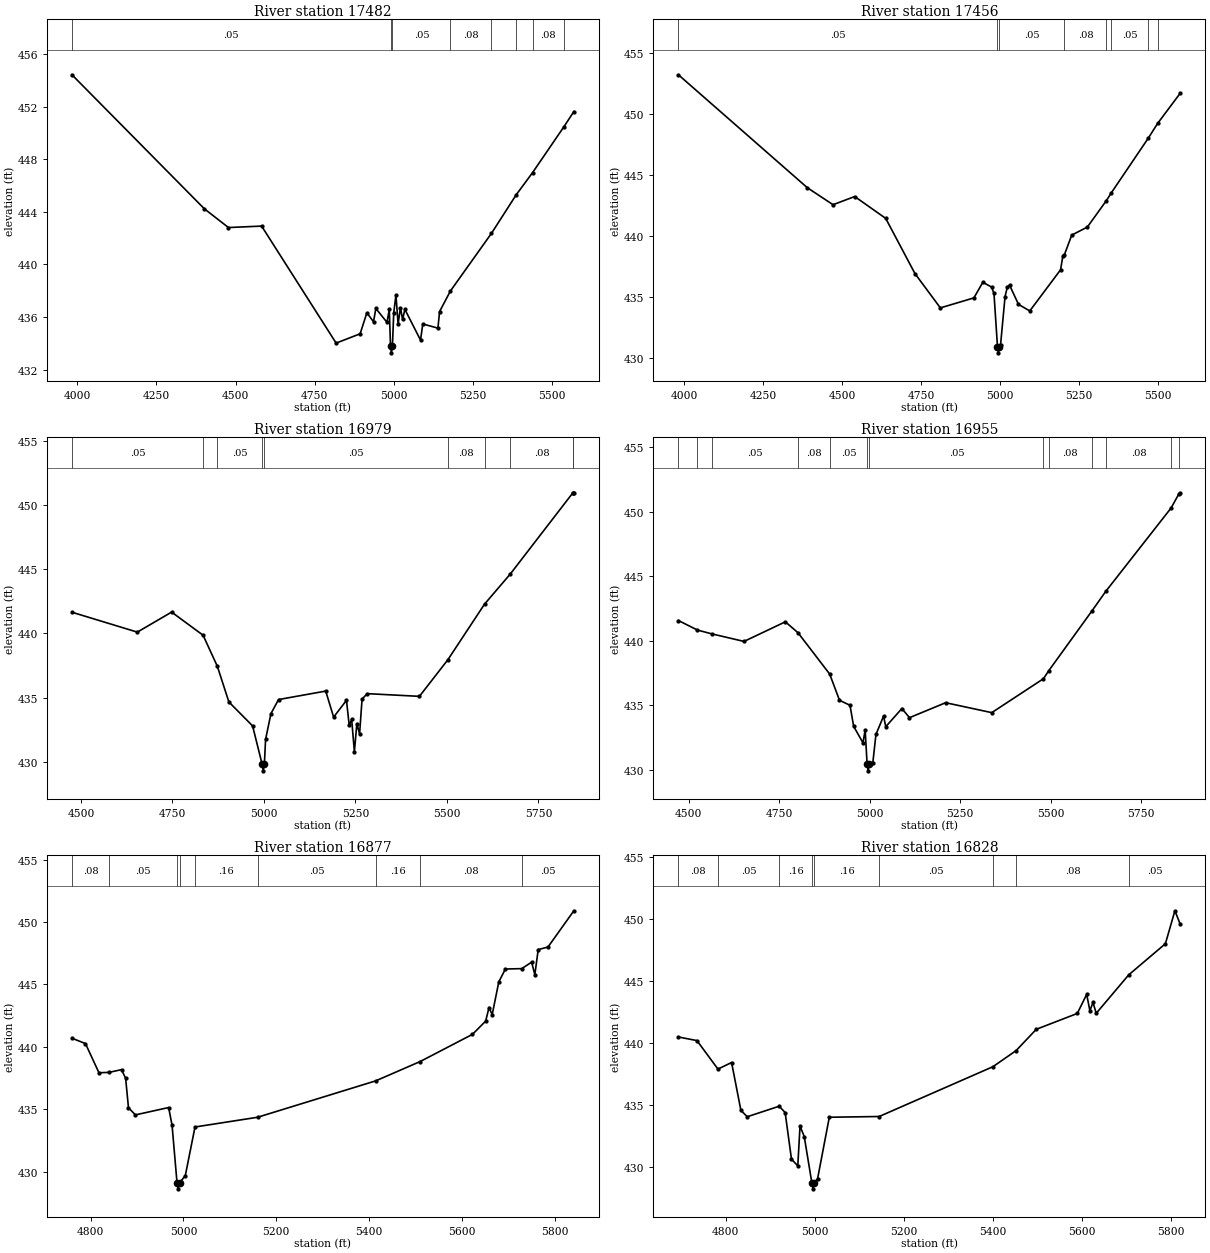
Type RM Length L Ch R = 1 ,17482   ,26,26,26
BEGIN DESCRIPTION:
BEAR BRANCH 32.0
END DESCRIPTION:
XS GIS Cut Line= 5
      3565948.18     10539708.77      3565123.06     10540066.42
      3564970.72     10540226.58      3564916.29     10540241.68
      3564636.04     10540540.09
#Sta/Elev= 30
  3983.1  454.44  4401.8  444.23  4477.7  442.81  4582.5  442.92    4818  434.01
  4893.8  434.72  4915.2  436.32  4936.2  435.63  4943.5  436.65  4978.7  435.59
    4986  436.58  4989.9  433.77  4992.6  433.27  4995.9  433.77    5000  436.29
    5007  437.67  5013.9  435.46  5021.2   436.7  5028.1  435.81  5035.3  436.58
  5084.7  434.24  5091.9  435.47  5139.7  435.15  5144.9  436.41  5179.2  437.98
    5309  442.37  5387.3  445.31  5438.8  446.99  5538.1  450.49  5569.3  451.64
#Mann= 8 ,-1 , 0
  3983.1     .05       0  4989.9     .03       0  4995.9     .05       0
  5179.2     .08       0    5309      .1       0  5387.3     .05       0
  5438.8     .08       0  5538.1     .05       0
Bank Sta=4989.9,4995.9
XS Rating Curve= 0 ,0
Exp/Cntr=0.3,0.1

Type RM Length L Ch R = 1 ,17456   ,477,477,477
BEGIN DESCRIPTION:
BEAR BRANCH 32.01
END DESCRIPTION:
XS GIS Cut Line= 5
      3565929.27      10539679.2      3565098.58     10540051.58
      3564952.75     10540210.43      3564882.44     10540239.08
      3564608.96     10540515.15
#Sta/Elev= 30
  3981.5   453.2  4390.1  443.95  4471.5  442.56  4540.2  443.23  4638.4  441.44
  4731.1  436.92  4811.6  434.11  4917.9  434.93  4946.2  436.21  4974.1  435.81
  4981.5  435.29  4992.6  430.93  4995.4  430.43  4998.6  430.93  5002.4   431.1
  5016.6  435.04    5024  435.83  5030.8  435.98  5059.1   434.4  5094.9  433.86
  5192.5  437.23  5199.6  438.33  5204.9  438.48  5227.9  440.07  5277.4  440.73
  5337.8   442.9  5353.8  443.55  5470.7  448.02  5500.2  449.22    5572   451.7
#Mann= 8 ,-1 , 0
  3981.5     .05       0  4992.6     .03       0  4998.6     .05       0
  5204.9     .08       0  5337.8      .1       0  5353.8     .05       0
  5470.7     .08       0  5500.2     .05       0
Bank Sta=4992.6,4998.6
XS Rating Curve= 0 ,0
Exp/Cntr=0.3,0.1

Type RM Length L Ch R = 1 ,16979   ,24,24,24
BEGIN DESCRIPTION:
BEAR BRANCH 30.02
END DESCRIPTION:
XS GIS Cut Line= 4
      3565399.38     10539358.15      3565015.25     10539876.84
      3564885.04     10540020.06      3564559.51     10540441.08
#Sta/Elev= 30
  4475.4  441.64    4654  440.09  4747.7  441.65  4833.6  439.85  4872.6  437.43
  4904.2  434.65  4968.9  432.79  4995.1  429.79  4997.9  429.29  5001.1  429.79
  5004.4  431.74    5019  433.74  5039.8  434.84  5168.7   435.5  5190.3  433.47
  5225.4  434.78  5232.9  432.83  5239.6  433.29    5247  430.78  5253.8  432.97
  5261.2  432.16    5268  434.88  5282.2   435.3  5424.7  435.09  5502.4  437.94
  5602.6  442.27  5672.8  444.61  5843.2  450.91  5843.3  450.92  5846.6  450.94
#Mann= 10 ,-1 , 0
  4475.4     .05       0  4833.6     .08       0  4872.6     .05       0
  4995.1     .03       0  5001.1     .05       0  5502.4     .08       0
  5602.6     .05       0  5672.8     .08       0  5843.2     .05       0
  5843.3     .08       0
Bank Sta=4995.1,5001.1
XS Rating Curve= 0 ,0
Exp/Cntr=0.3,0.1

Type RM Length L Ch R = 1 ,16955   ,78,78,78
BEGIN DESCRIPTION:
BEAR BRANCH 31.0
END DESCRIPTION:
XS GIS Cut Line= 5
      3565389.35     10539345.22      3565092.46     10539730.65
      3565003.92     10539859.12      3564871.98     10540008.43
      3564542.11     10540441.64
#Sta/Elev= 30
  4472.1  441.56  4524.7  440.82    4565  440.52  4653.3  439.94  4767.5  441.46
  4802.5  440.61  4889.9  437.41    4917  435.38    4946  434.99  4956.1  433.36
  4981.9  432.08  4987.9  433.08  4993.3  430.41    4996  429.91  4999.3  430.41
  5008.9   430.5  5017.7  432.73  5038.7  434.15  5044.8  433.33  5089.4  434.74
  5110.3  434.03  5210.2  435.19  5337.6  434.42  5480.4  437.05  5494.5  437.65
  5614.2   442.3  5652.5  443.82  5832.9  450.28  5853.6  451.33  5858.4  451.46
#Mann= 13 ,-1 , 0
  4472.1     .05       0  4524.7     .08       0    4565     .05       0
  4802.5     .08       0  4889.9     .05       0  4993.3     .04       0
  4999.3     .05       0  5480.4     .16       0  5494.5     .08       0
  5614.2     .05       0  5652.5     .08       0  5832.9     .05       0
  5853.6     .08       0
Bank Sta=4993.3,4999.3
XS Rating Curve= 0 ,0
Exp/Cntr=0.3,0.1

Type RM Length L Ch R = 1 ,16877   ,49,49,49
BEGIN DESCRIPTION:
BEAR BRANCH 30.0
END DESCRIPTION:
XS GIS Cut Line= 3
      3565134.23     10539533.66      3564887.69     10539893.06
      3564446.88     10540365.11
#Sta/Elev= 30
  4759.6  440.69  4788.7  440.26  4817.8  437.92  4839.4  437.95  4866.5  438.17
  4875.3  437.47  4881.4  435.12  4896.3  434.54    4968  435.13  4975.4   433.7
    4986  429.11  4988.7  428.61    4992  429.11  5003.9  429.67  5024.8  433.57
  5159.6  434.35  5414.3  437.27  5510.1  438.82  5622.8     441  5651.2  442.06
  5658.5  443.15  5665.3  442.58  5679.5   445.2  5693.7  446.24    5729  446.27
  5750.3  446.79  5757.2  445.79  5764.5   447.8  5785.5     448  5841.3  450.91
#Mann= 9 ,-1 , 0
  4759.6     .08       0  4839.4     .05       0    4986     .04       0
    4992     .05       0  5024.8     .16       0  5159.6     .05       0
  5414.3     .16       0  5510.1     .08       0    5729     .05       0
Bank Sta=4986,4992
XS Rating Curve= 0 ,0
Exp/Cntr=0.3,0.1

Type RM Length L Ch R = 1 ,16828   ,213,213,213
BEGIN DESCRIPTION:
BEAR BRANCH 30.01
END DESCRIPTION:
XS GIS Cut Line= 6
      3565138.95     10539510.08      3564954.48     10539714.08
      3564954.48     10539779.18      3564770.02     10539989.68
      3564420.63     10540354.27      3564420.63     10540356.48
#Sta/Elev= 30
  4694.1  440.46  4735.7  440.17  4782.9  437.87  4813.5   438.4  4834.4  434.54
  4848.6  434.02  4920.4  434.87  4933.8  434.36    4948   430.6  4962.2  430.05
  4967.2  433.27  4976.7  432.42  4993.7   428.7  4996.4   428.2  4999.7   428.7
  5006.7  429.03    5033  433.98    5145  434.04  5400.4  438.06  5452.5  439.36
  5497.8  441.08  5589.9  442.36    5611   443.9  5618.2  442.58  5625.2  443.25
  5632.4  442.37  5705.5  445.48  5787.8  447.99  5809.1  450.65  5821.3  449.55
#Mann= 9 ,-1 , 0
  4694.1     .08       0  4782.9     .05       0  4920.4     .16       0
  4993.7     .07       0  4999.7     .16       0    5145     .05       0
  5400.4     .16       0  5452.5     .08       0  5705.5     .05       0
Bank Sta=4993.7,4999.7
XS Rating Curve= 0 ,0
Exp/Cntr=0.3,0.1