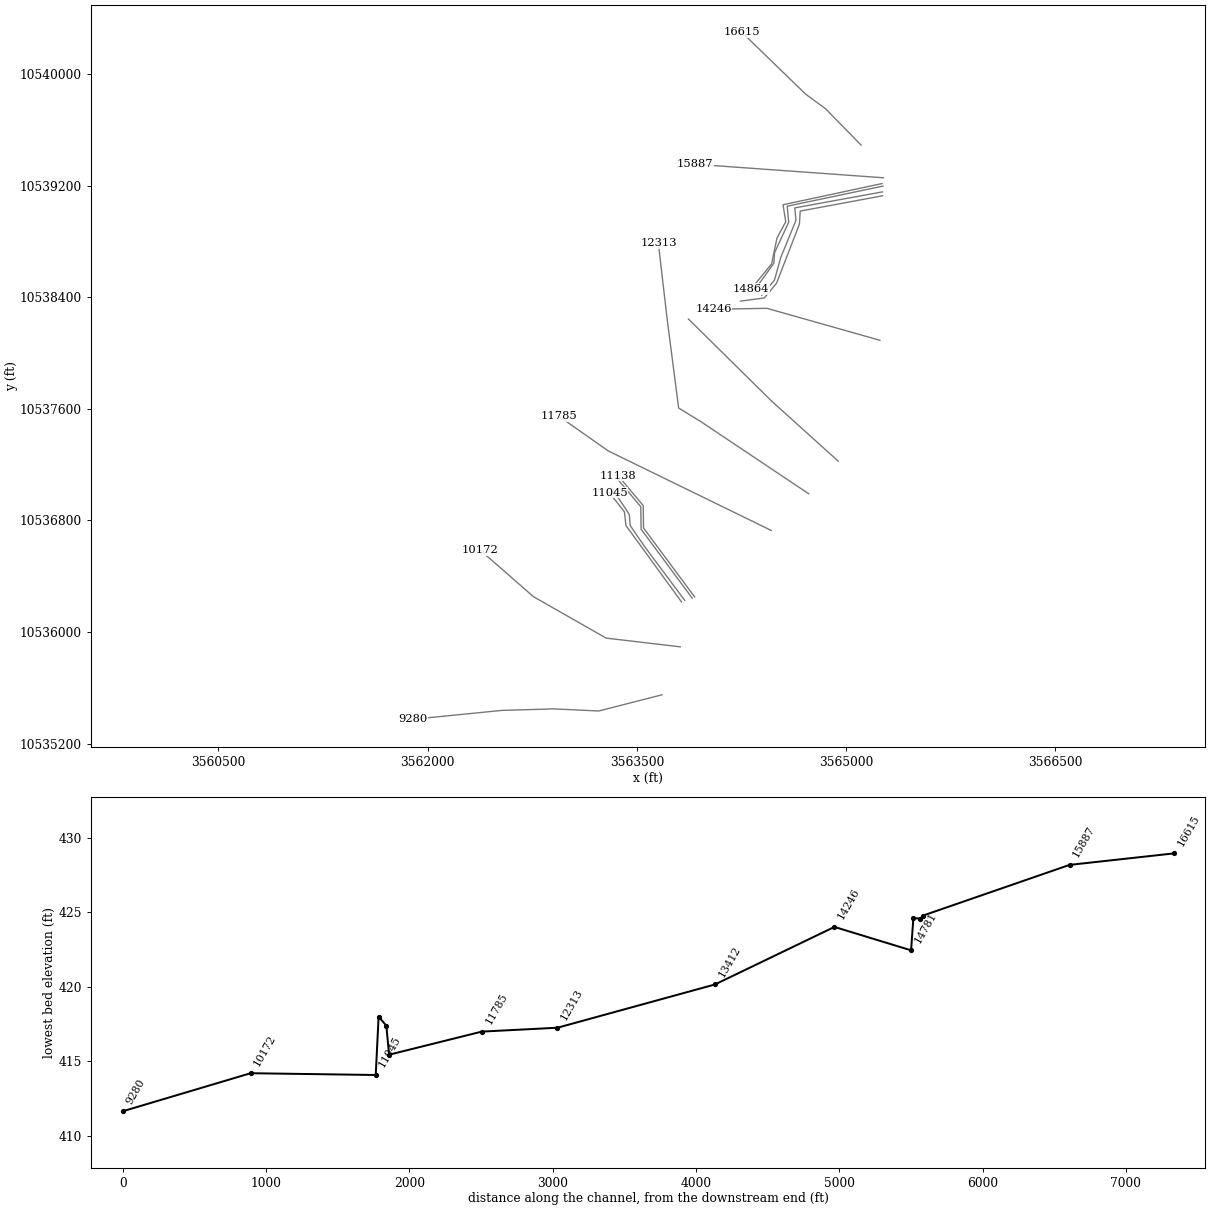
HEC-RAS study BEAR BRANCH.prj: BEAR BRANCH Base Level Engineering

--- BEAR BRANCH.g01 (geometry) --- (continued)

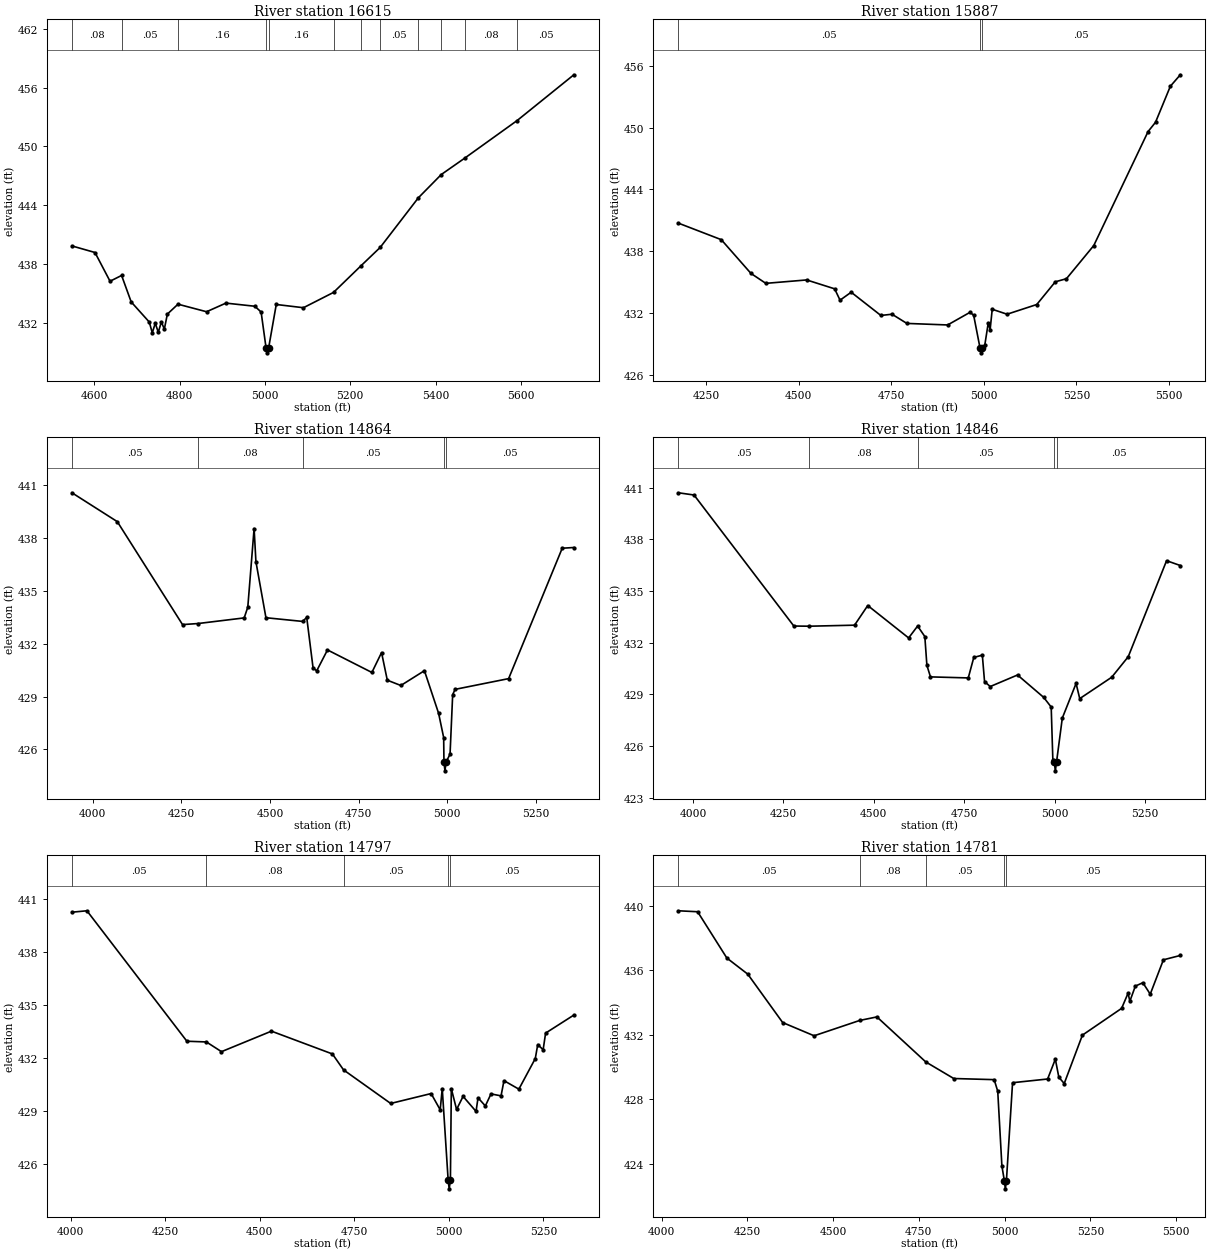
Type RM Length L Ch R = 1 ,16615   ,728,728,728
BEGIN DESCRIPTION:
BEAR BRANCH 29.0
END DESCRIPTION:
XS GIS Cut Line= 4
      3565107.38     10539490.62      3564852.97      10539750.7
      3564708.87      10539856.6      3564253.66     10540297.96
#Sta/Elev= 30
  4547.4  439.85  4601.4  439.18  4636.7  436.25  4663.8  436.84  4686.3  434.14
  4728.7  432.09  4735.7  430.99  4742.8  431.97  4749.8  431.04    4757   432.1
    4764  431.37  4771.1   432.9    4796  433.91    4863  433.14  4908.4  434.02
  4976.2   433.7  4990.9  433.11  5002.5  429.45  5005.3  428.95  5008.5  429.45
  5026.4  433.88  5090.1  433.55  5160.6  435.11  5224.2  437.79  5270.1   439.7
  5359.6  444.76  5413.3  447.13  5468.9  448.82    5591  452.63  5724.1   457.3
#Mann= 12 ,-1 , 0
  4547.4     .08       0  4663.8     .05       0    4796     .16       0
  5002.5     .07       0  5008.5     .16       0  5160.6     .05       0
  5224.2     .16       0  5270.1     .05       0  5359.6     .16       0
  5413.3     .05       0  5468.9     .08       0    5591     .05       0
Bank Sta=5002.5,5008.5
XS Rating Curve= 0 ,0
Exp/Cntr=0.3,0.1

Type RM Length L Ch R = 1 ,15887   ,1023,1023,1023
BEGIN DESCRIPTION:
BEAR BRANCH 28.0
END DESCRIPTION:
XS GIS Cut Line= 2
      3565267.58     10539256.39      3563915.26     10539353.48
#Sta/Elev= 30
  4174.7  440.74  4290.5  439.14  4370.7  435.87  4410.8  434.91  4521.1  435.24
  4596.7  434.38  4611.3  433.28  4641.4  434.05  4721.6   431.8  4751.7  431.92
  4791.8  431.03    4902  430.88  4962.2   432.1  4972.2  431.83  4989.3  428.68
    4992  428.18  4995.3  428.68  5002.3  428.93  5011.7  431.08  5016.7  430.41
  5022.4   432.4  5062.5  431.92  5142.7  432.86  5192.8  435.06  5222.9  435.36
  5296.7  438.57  5443.4  449.61  5463.5  450.51  5503.6     454  5530.5  455.11
#Mann= 3 ,-1 , 0
  4174.7     .05       0  4989.3     .03       0  4995.3     .05       0
Bank Sta=4989.3,4995.3
XS Rating Curve= 0 ,0
Exp/Cntr=0.3,0.1

Type RM Length L Ch R = 1 ,14864   ,18,18,18
BEGIN DESCRIPTION:
BEAR BRANCH 27.01
END DESCRIPTION:
XS GIS Cut Line= 6
      3565257.14     10539214.72      3564547.55     10539062.82
      3564567.08     10538941.29      3564504.14      10538824.1
      3564465.81     10538638.92      3564318.23     10538458.79
#Sta/Elev= 30
  3941.7  440.58  4069.6  438.94  4253.6  433.09  4297.3  433.15  4427.5  433.47
  4437.7  434.08  4455.5  438.55  4460.6  436.67  4488.9  433.48  4592.4  433.27
  4603.9   433.5  4621.8  430.63    4632  430.46  4662.5  431.65  4787.7  430.37
    4815   431.5  4831.2  429.93  4869.4  429.63  4935.9  430.47  4975.9  428.05
  4990.2  426.67    4991  425.28  4993.8  424.78    4997  425.28  5008.2  425.73
  5015.6  429.11  5022.4  429.41  5173.4  430.02  5324.6  437.43  5357.4  437.47
#Mann= 5 ,-1 , 0
  3941.7     .05       0  4297.3     .08       0  4592.4     .05       0
    4991     .03       0    4997     .05       0
Bank Sta=4991,4997
XS Rating Curve= 0 ,0
Exp/Cntr=0.3,0.1

Type RM Length L Ch R = 1 ,14846   ,49,49,49
BEGIN DESCRIPTION:
BEAR BRANCH 27.0
END DESCRIPTION:
XS GIS Cut Line= 6
      3565264.38     10539196.71      3564577.75     10539052.33
      3564588.16     10538937.74      3564487.14     10538719.65
      3564481.72     10538643.69       3564337.4     10538442.95
#Sta/Elev= 30
  3959.8   440.7    4003  440.57  4278.9  432.97  4321.8  432.96  4446.8  433.02
  4483.3  434.16  4596.3  432.28  4621.2  432.97  4641.1  432.36  4646.8  430.69
  4656.7  430.02  4761.2  429.96  4776.5  431.15  4800.1  431.28  4806.2  429.75
  4821.9  429.46  4897.4  430.13  4969.8  428.83  4990.5  428.27  4995.1  425.18
  4999.2  425.07  5001.9  424.57  5005.2  425.07  5021.2  427.63  5059.3  429.64
  5069.4  428.76  5157.8     430  5203.5  431.19  5309.5  436.76  5347.5  436.48
#Mann= 5 ,-1 , 0
  3959.8     .05       0  4321.8     .08       0  4621.2     .05       0
  4999.2     .03       0  5005.2     .05       0
Bank Sta=4999.2,5005.2
XS Rating Curve= 0 ,0
Exp/Cntr=0.3,0.1

Type RM Length L Ch R = 1 ,14797   ,16,16,16
BEGIN DESCRIPTION:
BEAR BRANCH 27.02
END DESCRIPTION:
XS GIS Cut Line= 6
      3565261.02     10539155.33      3564631.64      10539040.3
      3564640.32     10538951.33      3564530.73     10538683.31
      3564486.24     10538522.72      3564395.09     10538414.21
#Sta/Elev= 30
  4003.3  440.27  4042.9  440.35  4307.2  432.97  4358.7  432.93  4398.7  432.38
  4530.8  433.54    4692  432.25  4721.4  431.35  4846.1  429.45    4953  430.01
    4977  429.09  4982.4  430.29    4998  425.12  5000.8  424.62    5004  425.12
  5006.4  430.29  5020.3  429.11  5037.5  429.85  5071.8     429    5077  429.77
  5096.4  429.31  5111.3  429.99  5137.9  429.88  5145.6  430.74    5185  430.26
  5228.4  431.99  5234.9  432.78  5249.2  432.49  5255.7  433.43  5330.4  434.45
#Mann= 5 ,-1 , 0
  4003.3     .05       0  4358.7     .08       0  4721.4     .05       0
    4998    .035       0    5004     .05       0
Bank Sta=4998,5004
XS Rating Curve= 0 ,0
Exp/Cntr=0.3,0.1

Type RM Length L Ch R = 1 ,14781   ,535,535,535
BEGIN DESCRIPTION:
BEAR BRANCH 27.03
END DESCRIPTION:
XS GIS Cut Line= 6
      3565260.94      10539127.1       3564670.7     10539017.51
      3564665.28      10538924.2      3564501.43     10538501.02
      3564413.54     10538394.68      3564242.85     10538372.17
#Sta/Elev= 30
  4049.2  439.69  4105.2  439.63  4190.4  436.76  4251.4  435.76  4353.1  432.76
  4444.7  431.94  4577.5  432.89  4627.8  433.11  4770.1  430.32  4851.8  429.29
  4969.6  429.22    4980   428.5  4992.1  423.87  4999.3  422.95  5002.1  422.45
  5005.3  422.95  5023.2  429.03  5125.4  429.26  5147.9  430.49  5158.1  429.37
  5173.8  428.98  5226.8  431.98  5341.1  433.64  5359.9  434.58  5365.1  434.08
  5381.1  435.02    5403  435.23  5424.5  434.52  5462.9  436.65  5512.2  436.92
#Mann= 5 ,-1 , 0
  4049.2     .05       0  4577.5     .08       0  4770.1     .05       0
  4999.3    .035       0  5005.3     .05       0
Bank Sta=4999.3,5005.3
XS Rating Curve= 0 ,0
Exp/Cntr=0.3,0.1

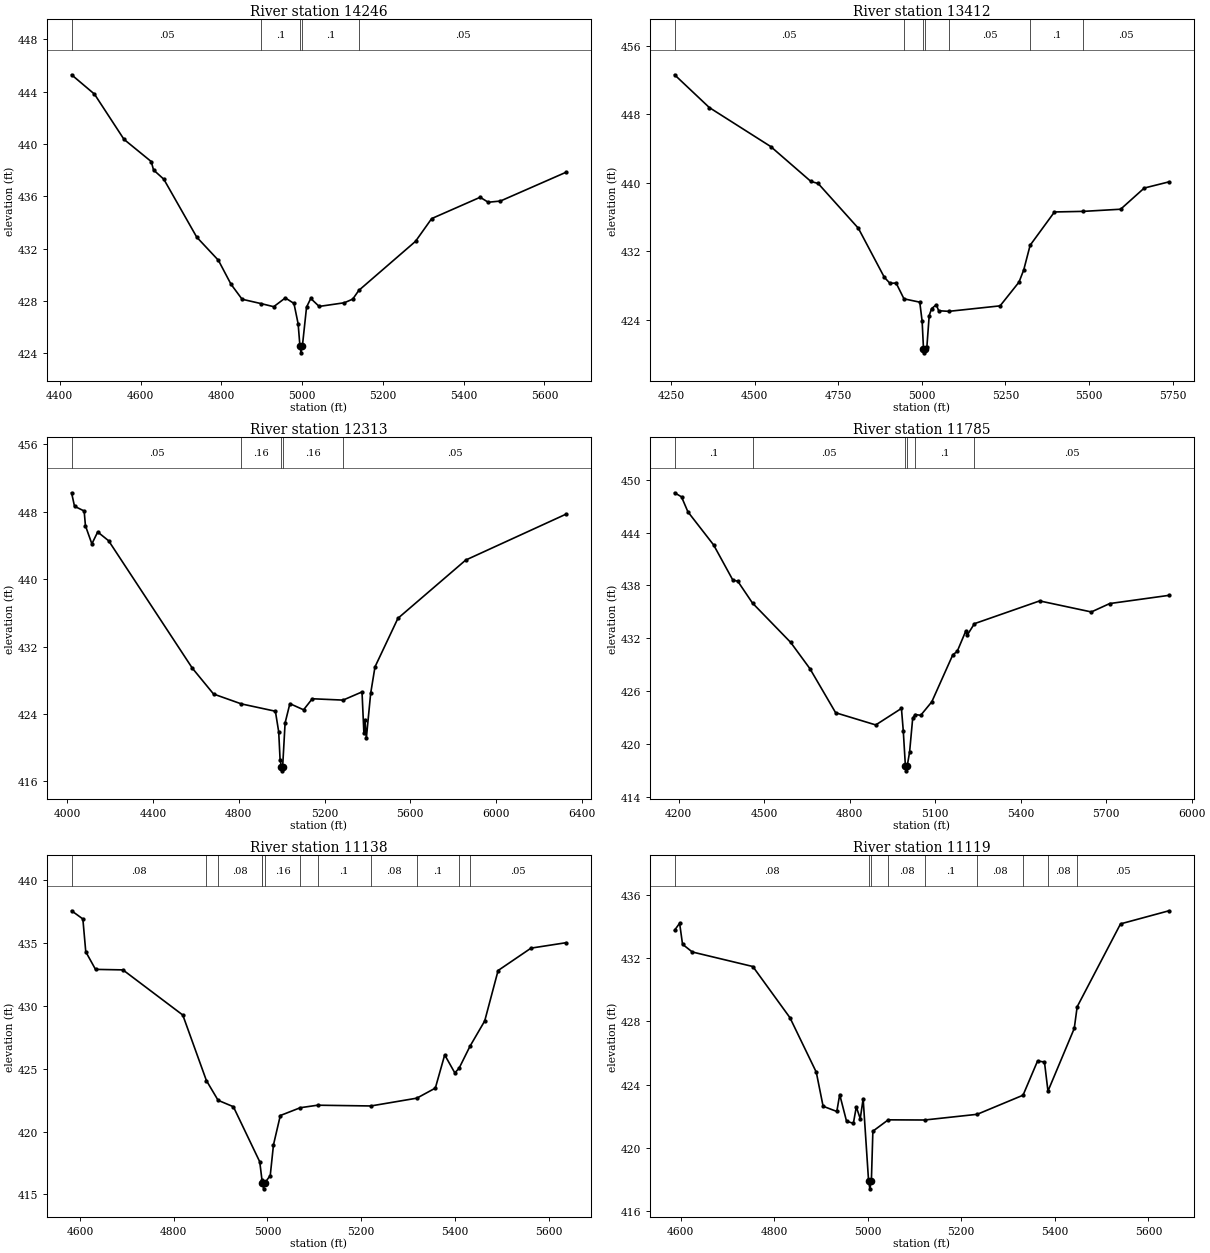
Type RM Length L Ch R = 1 ,14246   ,834,834,834
BEGIN DESCRIPTION:
BEAR BRANCH 26.0
END DESCRIPTION:
XS GIS Cut Line= 3
      3565241.91     10538091.29      3564431.99     10538320.47
      3564049.77     10538313.58
#Sta/Elev= 30
  4429.3  445.29    4486  443.81  4559.1  440.35  4626.6  438.65  4632.2  438.01
  4657.7   437.3  4739.2  432.87  4792.8   431.1    4824  429.27  4851.5  428.12
  4899.3  427.78  4929.8  427.55  4958.5  428.22  4979.9   427.8  4990.3  426.23
  4994.7  424.52  4997.4  424.02  5000.7  424.52  5011.1  427.52  5021.5  428.18
  5042.3  427.57  5104.6  427.85  5125.4  428.13  5140.6   428.8  5280.9  432.55
  5320.9  434.29  5440.9  435.92  5460.9  435.54  5490.9  435.63  5653.3  437.83
#Mann= 5 ,-1 , 0
  4429.3     .05       0  4899.3      .1       0  4994.7     .07       0
  5000.7      .1       0  5140.6     .05       0
Bank Sta=4994.7,5000.7
XS Rating Curve= 0 ,0
Exp/Cntr=0.3,0.1

Type RM Length L Ch R = 1 ,13412   ,1099,1099,1099
BEGIN DESCRIPTION:
BEAR BRANCH 24.0
END DESCRIPTION:
XS GIS Cut Line= 3
      3564942.38      10537225.4      3564463.21      10537657.7
      3563869.49     10538243.61
#Sta/Elev= 30
  4259.8  452.59  4363.7  448.77  4547.5  444.22  4667.8  440.15  4689.5  439.91
  4809.8  434.69  4887.5  428.97  4904.4  428.27  4922.8   428.3  4946.3  426.46
  4993.6  426.07  5000.7  423.83  5004.7  420.66  5007.4  420.16  5010.7  420.66
  5014.8  420.83  5021.8   424.5    5029  425.32  5043.1  425.77  5050.1  425.07
  5080.6     425    5234  425.64  5290.6  428.41  5304.7  429.83  5323.9  432.71
  5396.7  436.59  5483.5  436.66  5594.7  436.91  5665.4  439.38  5739.3   440.1
#Mann= 7 ,-1 , 0
  4259.8     .05       0  4946.3     .16       0  5004.7     .07       0
  5010.7     .16       0  5080.6     .05       0  5323.9      .1       0
  5483.5     .05       0
Bank Sta=5004.7,5010.7
XS Rating Curve= 0 ,0
Exp/Cntr=0.3,0.1

Type RM Length L Ch R = 1 ,12313   ,528,528,528
BEGIN DESCRIPTION:
BEAR BRANCH 22.0
END DESCRIPTION:
XS GIS Cut Line= 5
      3564731.45     10536991.03       3563960.6     10537506.66
      3563799.15     10537605.62      3563715.81     10538251.45
      3563653.87     10538785.91
#Sta/Elev= 30
  4020.1  450.24  4033.8  448.64  4078.8  448.08  4084.8  446.33  4114.8  444.18
  4141.9  445.59  4192.9  444.55  4583.3  429.44  4682.4  426.37    4812   425.2
  4970.8  424.33  4986.3  421.88  4992.7   418.6  4998.7  417.76  5001.4  417.26
  5004.7  417.76  5016.1  422.94  5038.4  425.23  5102.3   424.5  5142.9  425.81
  5286.4  425.65  5374.9  426.62  5383.6  421.77  5388.6  423.33    5395  421.12
  5415.2  426.44  5435.4  429.59  5542.4  435.35  5858.7  442.26  6326.1   447.7
#Mann= 5 ,-1 , 0
  4020.1     .05       0    4812     .16       0  4998.7     .07       0
  5004.7     .16       0  5286.4     .05       0
Bank Sta=4998.7,5004.7
XS Rating Curve= 0 ,0
Exp/Cntr=0.3,0.1

Type RM Length L Ch R = 1 ,11785   ,647,647,647
BEGIN DESCRIPTION:
BEAR BRANCH 21.0
END DESCRIPTION:
XS GIS Cut Line= 3
      3564463.16     10536728.04      3563293.94     10537298.33
      3562939.38     10537547.76
#Sta/Elev= 30
  4185.9   448.5  4210.2  448.04  4232.7  446.34  4322.9  442.59  4390.5   438.6
  4407.4  438.49  4459.4     436  4593.2  431.55  4660.8  428.57    4751  423.58
  4891.7   422.2  4981.8  424.07  4988.2  421.55  4995.8   417.5  4998.6     417
  5001.8   417.5  5010.4  419.13  5021.3  422.96  5030.1  423.38  5049.4  423.29
  5088.3  424.82  5162.1  430.15  5177.3  430.52  5207.2  432.81  5212.7  432.38
  5237.8  433.67  5466.6  436.25    5648     435  5712.5  435.95  5920.3  436.88
#Mann= 6 ,-1 , 0
  4185.9      .1       0  4459.4     .05       0  4995.8     .03       0
  5001.8     .05       0  5030.1      .1       0  5237.8     .05       0
Bank Sta=4995.8,5001.8
XS Rating Curve= 0 ,0
Exp/Cntr=0.3,0.1

Type RM Length L Ch R = 1 ,11138   ,19,19,19
BEGIN DESCRIPTION:
BEAR BRANCH 19.03
END DESCRIPTION:
XS GIS Cut Line= 4
      3563914.12     10536250.95      3563547.37     10536745.74
       3563545.2     10536906.33      3563366.08     10537119.98
#Sta/Elev= 30
  4581.8  437.56  4605.9  436.91  4612.1   434.3  4632.9   432.9  4691.4  432.86
  4819.2  429.27  4869.6  424.06  4894.6  422.49  4927.2  421.98  4983.5   417.6
  4988.2  416.16  4988.9  415.95  4991.7  415.45  4994.9  415.95  5005.9  416.51
  5012.8  418.95  5027.4  421.28    5070   421.9  5106.9   422.1  5220.7  422.04
  5318.8  422.66  5358.3  423.46  5378.3   426.1  5399.9  424.67    5409  425.04
  5432.3  426.79  5463.7   428.8  5492.3  432.81  5562.6  434.59  5637.1  435.02
#Mann= 12 ,-1 , 0
  4581.8     .08       0  4869.6     .05       0  4894.6     .08       0
  4988.2     .16       0  4988.9     .07       0  4994.9     .16       0
    5070     .08       0  5106.9      .1       0  5220.7     .08       0
  5318.8      .1       0    5409     .08       0  5432.3     .05       0
Bank Sta=4988.9,4994.9
XS Rating Curve= 0 ,0
Exp/Cntr=0.3,0.1

Type RM Length L Ch R = 1 ,11119   ,54,54,54
BEGIN DESCRIPTION:
BEAR BRANCH 19.02
END DESCRIPTION:
XS GIS Cut Line= 4
      3563896.74     10536242.29      3563530.01     10536737.06
      3563527.84     10536897.65      3563347.74     10537112.47
#Sta/Elev= 30
  4587.1  433.78  4597.9  434.22  4604.1  432.89    4625   432.4  4754.4  431.48
  4833.7  428.24    4890  424.79  4904.6  422.63  4933.9   422.3  4940.1  423.37
  4954.7  421.68  4969.3  421.55  4975.6  422.59    4984  421.84  4990.2  423.11
  5001.8   417.9  5004.6   417.4  5007.8   417.9    5011  421.05  5043.8  421.77
  5121.8  421.76    5234  422.12    5332  423.33  5363.1   425.5  5377.8  425.43
  5385.3  423.59  5441.5  427.56  5447.7  428.93  5540.4  434.18  5643.9  435.01
#Mann= 9 ,-1 , 0
  4587.1     .08       0  5001.8     .07       0  5007.8     .08       0
  5043.8     .08       0  5121.8      .1       0    5234     .08       0
    5332      .1       0  5385.3     .08       0  5447.7     .05       0
Bank Sta=5001.8,5007.8
XS Rating Curve= 0 ,0
Exp/Cntr=0.3,0.1

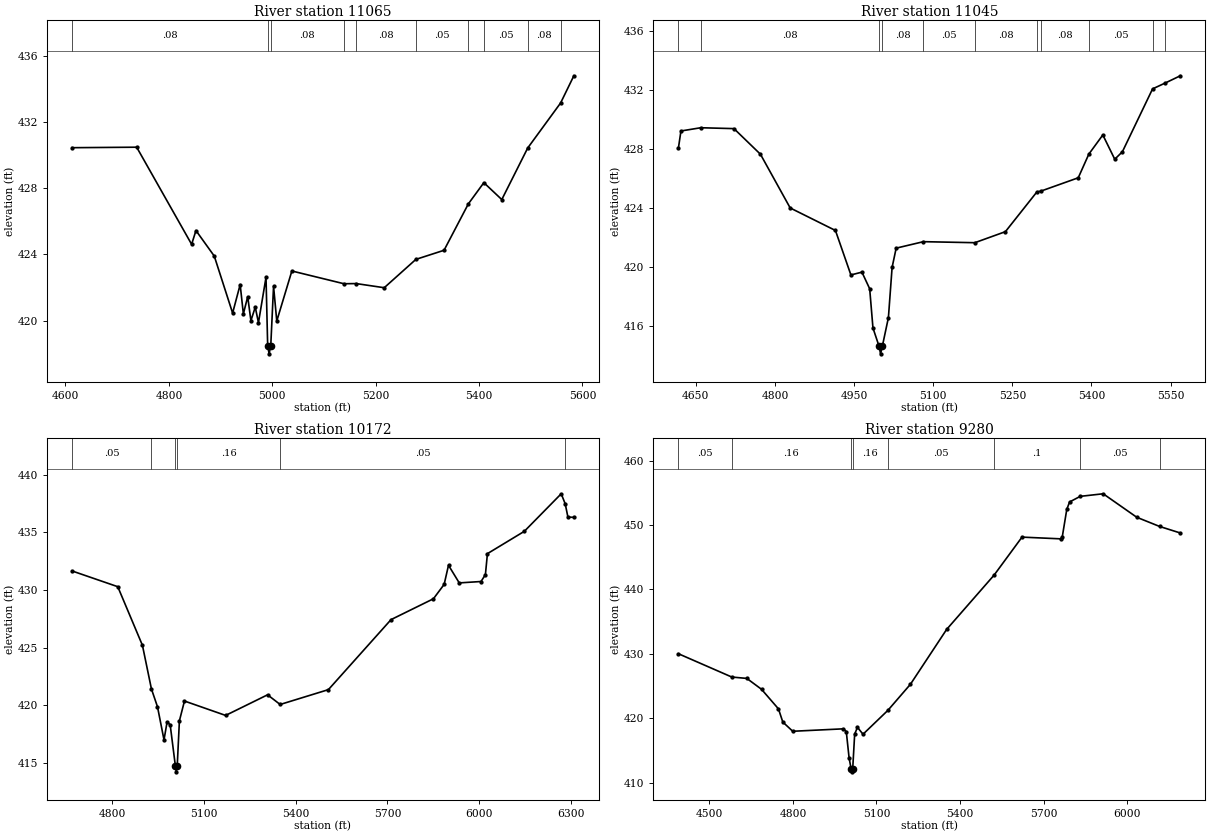
Type RM Length L Ch R = 1 ,11065   ,20,20,20
BEGIN DESCRIPTION:
BEAR BRANCH 19.0
END DESCRIPTION:
XS GIS Cut Line= 5
      3563842.53     10536227.05      3563556.05     10536611.19
      3563451.88      10536763.1      3563445.37      10536843.4
      3563319.49     10537032.22
#Sta/Elev= 30
  4612.5  430.44  4737.7  430.47    4844  424.61  4852.4  425.44  4887.8   423.9
  4923.3  420.46  4937.9  422.18  4944.1  420.41  4952.5  421.45  4958.7     420
  4967.1  420.82  4973.3  419.88  4987.9  422.62  4991.1   418.5  4993.9     418
  4997.1   418.5  5002.5  422.08  5008.7  419.98  5037.9     423  5138.7  422.23
  5162.3  422.24  5216.6  421.99  5277.8   423.7  5332.3  424.25  5379.3  427.05
  5409.3  428.33    5444  427.31  5494.1  430.42  5557.8  433.14  5583.4  434.78
#Mann= 10 ,-1 , 0
  4612.5     .08       0  4991.1     .07       0  4997.1     .08       0
  5138.7     .05       0  5162.3     .08       0  5277.8     .05       0
  5379.3     .08       0  5409.3     .05       0  5494.1     .08       0
  5557.8     .05       0
Bank Sta=4991.1,4997.1
XS Rating Curve= 0 ,0
Exp/Cntr=0.3,0.1

Type RM Length L Ch R = 1 ,11045   ,873,873,873
BEGIN DESCRIPTION:
BEAR BRANCH 19.01
END DESCRIPTION:
XS GIS Cut Line= 4
      3563820.83     10536214.02       3563421.5      10536763.1
      3563410.65     10536860.76      3563303.34     10536998.12
#Sta/Elev= 30
    4617  428.07  4621.8  429.23  4659.4  429.45  4722.3  429.39  4772.5  427.65
  4828.9     424  4914.7  422.47    4944  419.45  4964.9  419.64  4979.6  418.51
  4985.8  415.85  4997.5  414.59  5000.2  414.09  5003.5  414.59  5015.1  416.55
  5022.1  419.96  5029.8  421.27  5081.5  421.71  5178.9  421.64  5236.9  422.39
  5296.6  425.09  5303.8  425.14    5375  426.05  5395.1  427.66  5421.6  428.96
  5444.2  427.31  5458.7  427.82  5515.9  432.09  5539.4  432.48  5568.5  432.98
#Mann= 11 ,-1 , 0
    4617     .05       0  4659.4     .08       0  4997.5     .07       0
  5003.5     .08       0  5081.5     .05       0  5178.9     .08       0
  5296.6     .05       0  5303.8     .08       0  5395.1     .05       0
  5515.9     .08       0  5539.4     .05       0
Bank Sta=4997.5,5003.5
XS Rating Curve= 0 ,0
Exp/Cntr=0.3,0.1

Type RM Length L Ch R = 1 ,10172   ,892,892,892
BEGIN DESCRIPTION:
BEAR BRANCH 18.0
END DESCRIPTION:
XS GIS Cut Line= 4
      3563810.82     10535893.53      3563279.57     10535956.03
      3562758.74      10536252.9      3562377.84     10536585.37
#Sta/Elev= 30
  4669.3  431.66    4819  430.29  4899.6   425.2    4929  421.41  4948.8  419.86
  4970.1  416.99  4980.1  418.53  4990.2  418.31  5007.3  414.71  5010.1  414.21
  5013.3  414.71  5020.4  418.64  5036.9  420.36  5171.4  419.11  5308.5   420.9
  5349.6  420.06  5507.3  421.35  5711.9  427.43  5850.4  429.24  5885.5  430.49
  5899.7  432.15  5934.8  430.62    6006  430.74  6020.3  431.34  6026.9  433.16
  6147.5   435.1    6268  438.36    6281  437.49  6289.9  436.34  6309.3  436.31
#Mann= 6 ,-1 , 0
  4669.3     .05       0    4929     .16       0  5007.3     .07       0
  5013.3     .16       0  5349.6     .05       0    6281      .1       0
Bank Sta=5007.3,5013.3
XS Rating Curve= 0 ,0
Exp/Cntr=0.3,0.1

Type RM Length L Ch R = 1 ,9280    ,827,827,827
BEGIN DESCRIPTION:
BEAR BRANCH 17.0
END DESCRIPTION:
XS GIS Cut Line= 5
      3563679.97     10535549.62      3563226.45     10535433.53
      3562904.18     10535448.72        3562532.     10535437.87
      3561896.56      10535374.5
#Sta/Elev= 30
  4389.1     430  4580.8  426.38  4634.6  426.17  4687.4  424.48  4748.2  421.44
  4763.9  419.39  4799.5  417.96  4981.7  418.34  4991.7  417.91  5001.7  413.86
  5008.8  412.16  5011.5  411.66  5014.8  412.16  5021.8  417.52  5031.8  418.57
  5051.8   417.5  5141.1  421.21    5222  425.26    5352  433.78  5522.3  442.21
  5622.5  448.11  5762.1  447.84  5767.1  448.16  5783.2  452.41  5793.3  453.57
  5831.5  454.44  5913.9  454.84  6034.5  451.19  6116.2  449.77  6190.8  448.75
#Mann= 8 ,-1 , 0
  4389.1     .05       0  4580.8     .16       0  5008.8     .07       0
  5014.8     .16       0  5141.1     .05       0  5522.3      .1       0
  5831.5     .05       0  6116.2      .1       0
Bank Sta=5008.8,5014.8
XS Rating Curve= 0 ,0
Exp/Cntr=0.3,0.1