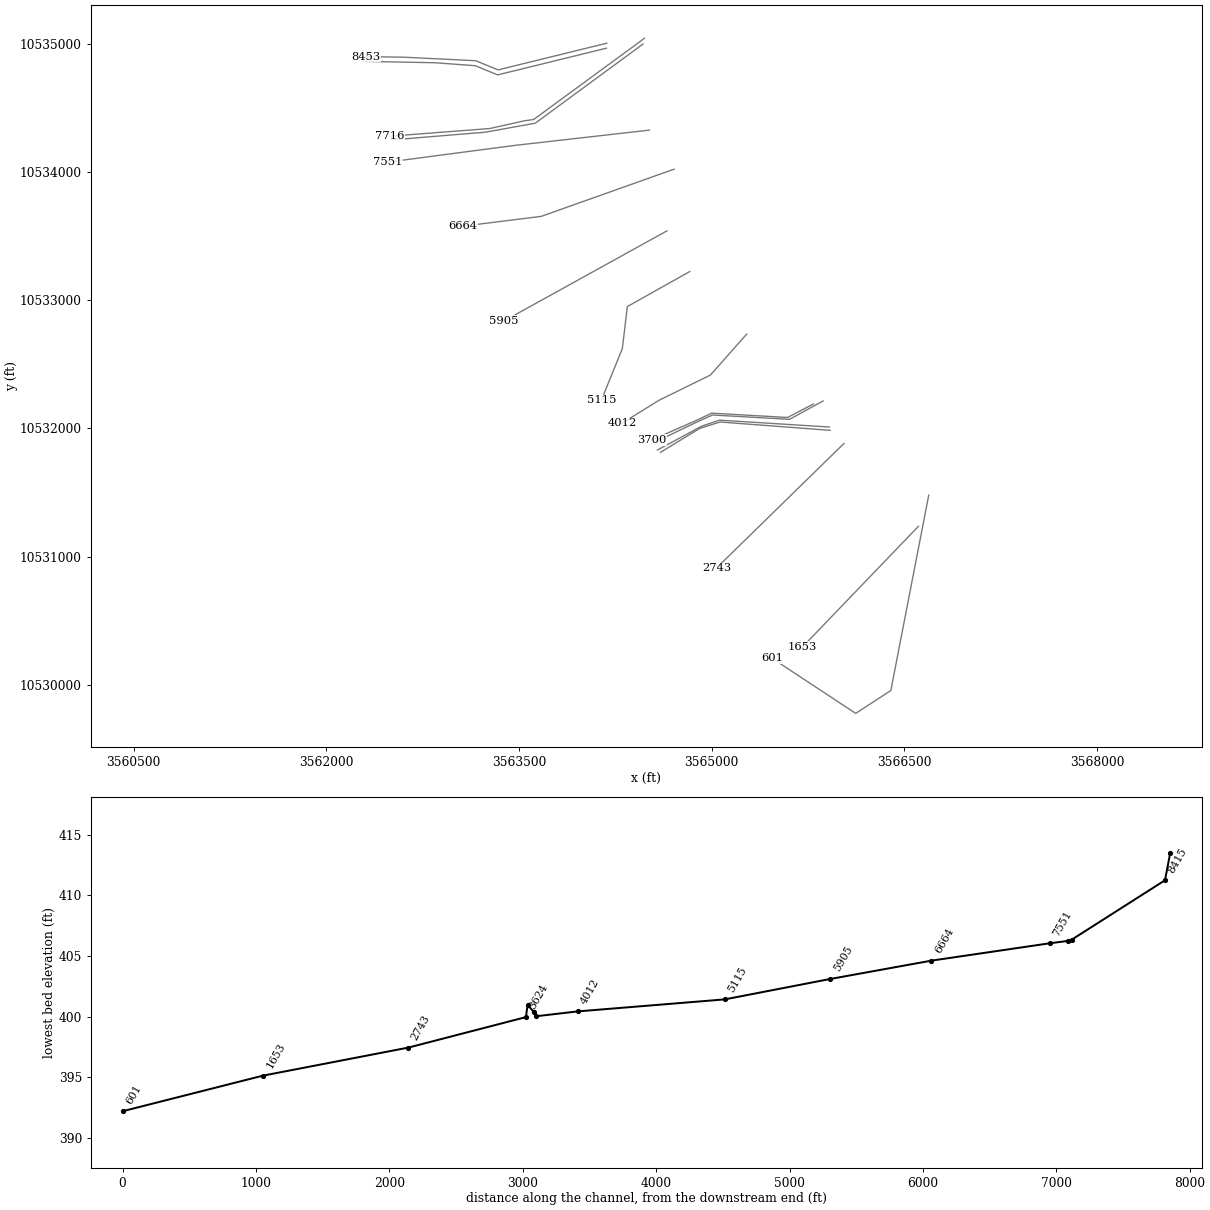
HEC-RAS study BEAR BRANCH.prj: BEAR BRANCH Base Level Engineering

--- BEAR BRANCH.g01 (geometry) --- (continued)

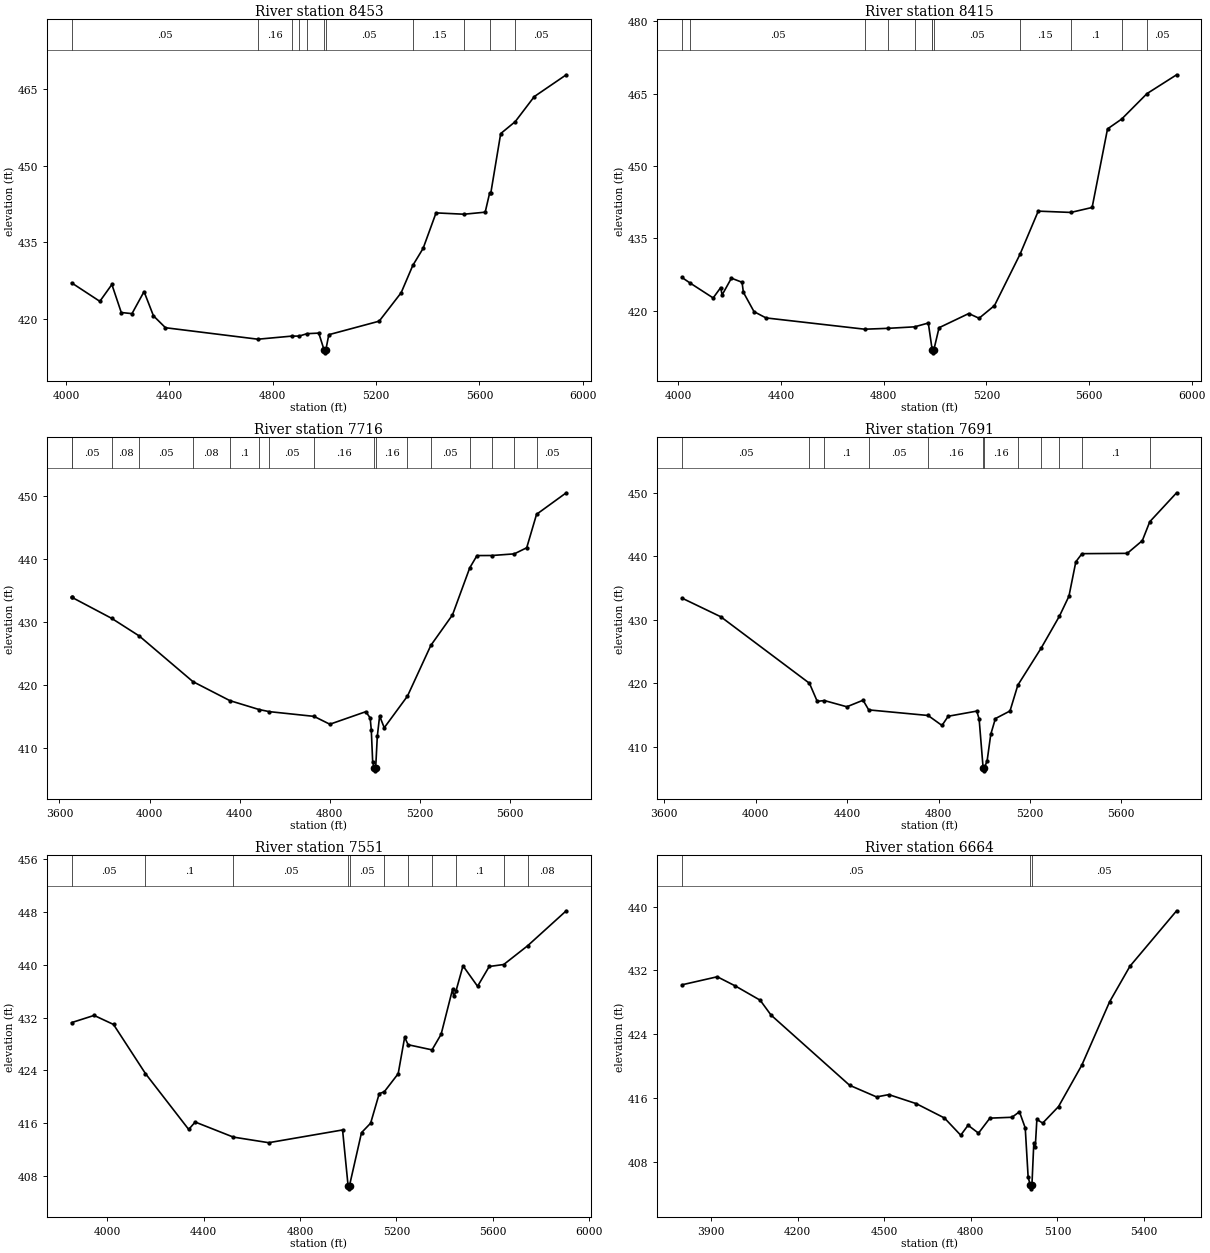
Type RM Length L Ch R = 1 ,8453    ,38,38,38
BEGIN DESCRIPTION:
BEAR BRANCH 16.1
END DESCRIPTION:
XS GIS Cut Line= 5
      3564183.46     10535002.75      3563337.12     10534794.42
      3563163.51     10534866.04      3562603.35     10534893.49
      3562308.22     10534897.83
#Sta/Elev= 30
    4021  427.11  4130.4   423.5    4177  426.79  4213.4  421.32  4254.9   421.1
  4301.6   425.4    4338  420.67  4384.6  418.35  4742.5  416.11  4872.7  416.71
  4902.1  416.72  4932.6  417.19  4978.1   417.3  4999.1  413.95  5001.8  413.45
  5005.1  413.95    5017  416.99    5212  419.63  5297.1  425.18  5342.3  430.52
  5382.2  433.84  5432.2  440.76  5540.7   440.5  5622.5   440.9  5639.9  444.68
  5644.4  444.68  5682.5  456.23  5738.9  458.57  5812.5  463.45  5936.4  467.71
#Mann= 11 ,-1 , 0
    4021     .05       0  4742.5     .16       0  4872.7     .05       0
  4902.1     .16       0  4932.6     .05       0  4999.1     .04       0
  5005.1     .05       0  5342.3     .15       0  5540.7      .1       0
  5639.9     .08       0  5738.9     .05       0
Bank Sta=4999.1,5005.1
XS Rating Curve= 0 ,0
Exp/Cntr=0.3,0.1

Type RM Length L Ch R = 1 ,8415    ,699,699,699
BEGIN DESCRIPTION:
BEAR BRANCH 16.0
END DESCRIPTION:
XS GIS Cut Line= 5
      3564180.26      10534963.7      3563333.87     10534755.36
      3563160.26     10534826.97      3562848.57     10534850.09
      3562292.97     10534860.94
#Sta/Elev= 30
  4013.7  426.87  4045.3  425.72  4135.4  422.62  4164.9  424.78  4170.1  423.23
  4206.5  426.72    4248  425.87  4253.1   423.8  4294.6  419.78  4341.3  418.48
    4726  416.14  4816.7  416.32  4920.1  416.63  4973.8  417.42  4988.1  412.16
  4988.8  411.74  4991.6  411.24  4994.8  411.74  5015.7  416.45  5131.5  419.39
  5171.6  418.41  5231.7  421.04  5330.9  431.64  5402.2  440.62  5529.2  440.35
  5612.2  441.38  5672.2  457.67  5727.1   459.7  5826.1  464.99  5941.4  468.89
#Mann= 12 ,-1 , 0
  4013.7     .08       0  4045.3     .05       0    4726     .16       0
  4816.7     .05       0  4920.1     .16       0  4988.1     .05       0
  4988.8     .04       0  4994.8     .05       0  5330.9     .15       0
  5529.2      .1       0  5727.1     .08       0  5826.1     .05       0
Bank Sta=4988.8,4994.8
XS Rating Curve= 0 ,0
Exp/Cntr=0.3,0.1

Type RM Length L Ch R = 1 ,7716    ,25,25,25
BEGIN DESCRIPTION:
BEAR BRANCH 15.0
END DESCRIPTION:
XS GIS Cut Line= 5
       3564476.2     10535040.54       3563614.2     10534407.71
      3563541.28     10534397.29      3563273.05      10534337.4
      3562497.01      10534277.5
#Sta/Elev= 30
  3653.9  433.89  3655.8  433.89    3832  430.56  3954.4  427.76  4192.4  420.52
  4356.5   417.5  4486.7  416.08  4531.7  415.75  4729.9     415  4800.5  413.75
    4960  415.74  4979.4  414.76  4984.5  412.85  4990.7  407.73    4998  406.85
  5000.7  406.35    5004  406.85  5011.2  411.82  5021.5  415.06    5042  413.19
  5145.2  418.22  5248.9  426.27    5345  431.11  5421.6  438.58  5453.8  440.53
  5520.4  440.54  5619.3   440.8  5674.5  441.77  5718.2  447.08  5850.1   450.5
#Mann= 17 ,-1 , 0
  3653.9     .08       0  3655.8     .05       0    3832     .08       0
  3954.4     .05       0  4192.4     .08       0  4356.5      .1       0
  4486.7     .08       0  4531.7     .05       0  4729.9     .16       0
    4998     .07       0    5004     .16       0  5145.2      .1       0
  5248.9     .05       0  5421.6     .08       0  5520.4      .1       0
  5619.3     .08       0  5718.2     .05       0
Bank Sta=4998,5004
XS Rating Curve= 0 ,0
Exp/Cntr=0.3,0.1

Type RM Length L Ch R = 1 ,7691    ,140,140,140
BEGIN DESCRIPTION:
BEAR BRANCH 14.0
END DESCRIPTION:
XS GIS Cut Line= 4
      3564465.79     10534996.27      3563627.22     10534379.06
       3563239.2     10534308.75      3562512.63     10534248.85
#Sta/Elev= 30
  3677.1  433.43  3847.2  430.49    4235  420.03  4269.2  417.18  4300.3  417.31
  4398.8  416.33  4469.7  417.36  4494.4  415.84  4754.2  414.96    4815  413.39
  4842.2  414.84  4967.4  415.65  4977.6   414.4  4994.9  406.75  4997.7  406.25
  5000.9  406.75  5012.7  407.85  5028.4  411.98  5048.7  414.47  5112.7  415.67
    5147  419.74  5249.5  425.59  5328.7  430.57  5370.6  433.73  5400.7  439.14
  5427.6  440.42  5625.8  440.47  5691.7  442.47  5724.2  445.44  5841.7     450
#Mann= 12 ,-1 , 0
  3677.1     .05       0    4235     .08       0  4300.3      .1       0
  4494.4     .05       0  4754.2     .16       0  4994.9     .07       0
  5000.9     .16       0    5147      .1       0  5249.5     .05       0
  5328.7     .08       0  5427.6      .1       0  5724.2     .05       0
Bank Sta=4994.9,5000.9
XS Rating Curve= 0 ,0
Exp/Cntr=0.3,0.1

Type RM Length L Ch R = 1 ,7551    ,887,887,887
BEGIN DESCRIPTION:
BEAR BRANCH 13.0
END DESCRIPTION:
XS GIS Cut Line= 3
        3564515.     10534324.77      3563464.62     10534205.41
      3562477.21      10534075.2
#Sta/Elev= 30
  3852.2  431.23  3945.7  432.32  4026.2  430.95  4158.6  423.52  4338.2  415.05
  4365.2  416.17  4523.3  413.89  4670.3  413.04  4976.9  414.97  4999.7  406.55
  5002.4  406.05  5005.7  406.55  5055.5  414.56  5093.4     416  5129.1  420.48
  5149.7  420.74  5207.7  423.49  5234.6  429.01  5248.9  427.88  5348.2   427.1
  5385.9  429.46  5433.3  436.27  5438.4  435.19  5447.4  435.99  5476.7  439.83
  5537.2  436.73  5585.5  439.73  5645.8  440.03    5745  442.87  5905.3  448.17
#Mann= 11 ,-1 , 0
  3852.2     .05       0  4158.6      .1       0  4523.3     .05       0
  4999.7     .03       0  5005.7     .05       0  5149.7      .1       0
  5248.9     .05       0  5348.2     .08       0  5447.4      .1       0
  5645.8     .05       0    5745     .08       0
Bank Sta=4999.7,5005.7
XS Rating Curve= 0 ,0
Exp/Cntr=0.3,0.1

Type RM Length L Ch R = 1 ,6664    ,759,759,759
BEGIN DESCRIPTION:
BEAR BRANCH 12.0
END DESCRIPTION:
XS GIS Cut Line= 3
      3564707.52     10534020.26       3563672.8     10533652.21
      3563061.68     10533575.82
#Sta/Elev= 30
  3798.9  430.19  3921.4   431.2  3984.3  430.04    4070  428.26  4107.6   426.4
  4379.9   417.6  4473.3  416.14  4515.8  416.43  4610.7   415.3  4708.5   413.5
  4764.9  411.34  4790.4  412.59  4826.5   411.6    4866  413.48  4942.6  413.59
  4968.4  414.28  4988.5  412.25  4998.6  406.06  5005.7  405.12  5008.4  404.62
  5011.7  405.12  5018.2  410.38  5023.2  409.81  5028.8  413.32    5049  412.86
  5103.8  414.93  5184.5  420.12  5280.8  428.06  5351.3  432.52    5513  439.47
#Mann= 3 ,-1 , 0
  3798.9     .05       0  5005.7     .03       0  5011.7     .05       0
Bank Sta=5005.7,5011.7
XS Rating Curve= 0 ,0
Exp/Cntr=0.3,0.1

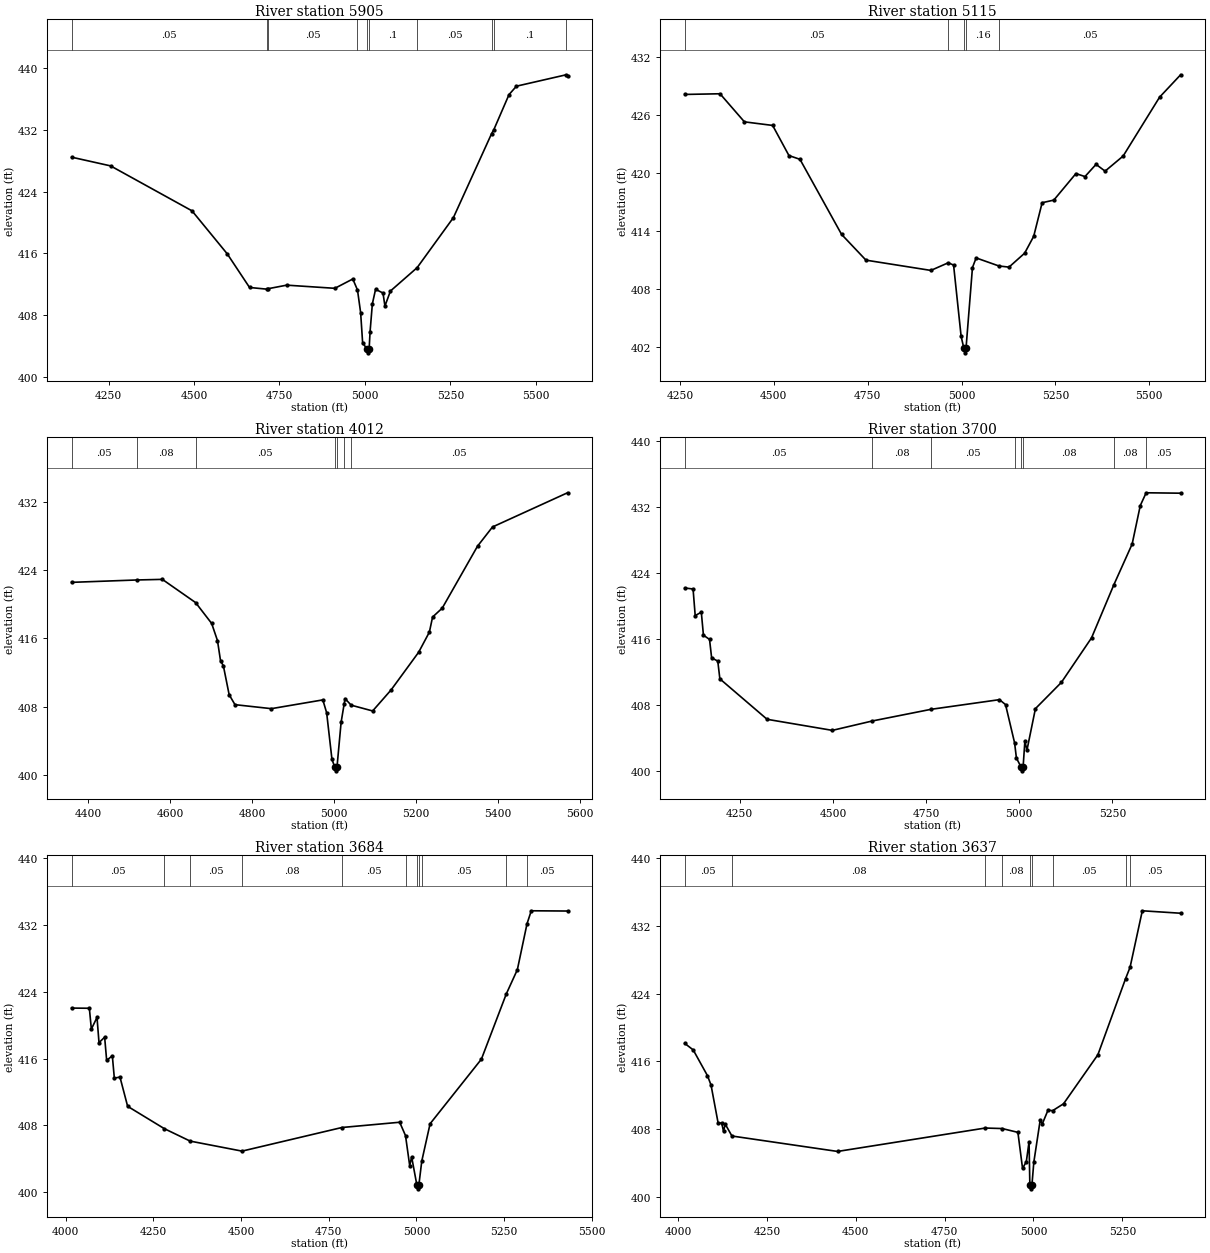
Type RM Length L Ch R = 1 ,5905    ,790,790,790
BEGIN DESCRIPTION:
BEAR BRANCH 11.0
END DESCRIPTION:
XS GIS Cut Line= 2
      3564651.66     10533539.16      3563382.69     10532836.35
#Sta/Elev= 30
    4142  428.49    4256  427.36  4494.1  421.53  4597.2  415.95  4662.4  411.59
  4713.3  411.37  4716.8  411.43  4771.2  411.89    4912  411.48  4964.5  412.69
  4978.2  411.26  4987.4  408.33  4993.3  404.38  5006.3  403.61  5009.1  403.11
  5012.3  403.61    5015  405.84  5021.7  409.46  5031.1  411.35  5052.8  410.87
  5058.5  409.18  5074.6  411.13  5152.7  414.16  5258.9  420.66  5370.7  431.56
  5376.7  432.02  5421.5  436.61  5443.2   437.7  5588.7  439.18  5592.6  439.03
#Mann= 10 ,-1 , 0
    4142     .05       0  4713.3      .1       0  4716.8     .05       0
  4978.2      .1       0  5006.3     .07       0  5012.3      .1       0
  5152.7     .05       0  5370.7     .08       0  5376.7      .1       0
  5588.7     .08       0
Bank Sta=5006.3,5012.3
XS Rating Curve= 0 ,0
Exp/Cntr=0.3,0.1

Type RM Length L Ch R = 1 ,5115    ,1103,1103,1103
BEGIN DESCRIPTION:
BEAR BRANCH 9.0
END DESCRIPTION:
XS GIS Cut Line= 4
       3564829.6     10533222.32      3564343.53      10532948.9
      3564304.46     10532621.21      3564141.71     10532219.76
#Sta/Elev= 30
  4262.8  428.11  4356.7  428.18  4421.7  425.28  4496.9  424.91  4540.3   421.8
  4569.7  421.41  4680.5  413.66  4745.5     411  4918.4  409.94  4964.8  410.73
  4978.9  410.49    4999  403.13  5006.1  401.93  5008.8  401.43  5012.1  401.93
  5029.2  410.24    5039  411.23  5099.5   410.4  5126.5  410.28  5168.2  411.72
  5192.3  413.46  5214.8  416.93  5245.9   417.2  5304.8  419.94  5328.9  419.63
  5358.4  420.89  5382.5  420.19  5430.6  421.75  5527.7  427.83  5583.7  430.14
#Mann= 5 ,-1 , 0
  4262.8     .05       0  4964.8     .16       0  5006.1     .07       0
  5012.1     .16       0  5099.5     .05       0
Bank Sta=5006.1,5012.1
XS Rating Curve= 0 ,0
Exp/Cntr=0.3,0.1

Type RM Length L Ch R = 1 ,4012    ,312,312,312
BEGIN DESCRIPTION:
BEAR BRANCH 7.0
END DESCRIPTION:
XS GIS Cut Line= 4
      3565272.35     10532734.06      3564990.23     10532415.05
      3564588.75     10532217.56      3564302.31     10532039.62
#Sta/Elev= 30
  4359.7   422.6  4519.4  422.88  4581.1  422.95  4662.3  420.22  4701.5  417.77
  4715.7  415.75  4723.3  413.34    4730  412.81  4744.2  409.39  4758.4  408.22
  4847.3  407.75  4972.9  408.78  4982.2  407.27  4995.2  401.78  5001.6  400.94
  5004.4  400.44  5007.6  400.94  5017.5  406.14    5025  408.32  5027.1  408.93
  5042.1  408.16  5094.5  407.48  5139.5  409.95  5206.9  414.39    5233  416.75
  5240.8  418.52  5264.4  419.57  5350.5  426.85  5387.1  429.11  5570.2  433.13
#Mann= 7 ,-1 , 0
  4359.7     .05       0  4519.4     .08       0  4662.3     .05       0
  5001.6     .03       0  5007.6     .05       0    5025     .16       0
  5042.1     .05       0
Bank Sta=5001.6,5007.6
XS Rating Curve= 0 ,0
Exp/Cntr=0.3,0.1

Type RM Length L Ch R = 1 ,3700    ,16,16,16
BEGIN DESCRIPTION:
BEAR BRANCH 5.03
END DESCRIPTION:
XS GIS Cut Line= 5
      3565792.05     10532189.52      3565590.25     10532084.07
       3565000.4     10532117.92      3564879.31     10532060.63
        3564533.      10531908.3
#Sta/Elev= 30
  4102.4  422.18  4124.7  422.06  4130.4  418.84  4146.8  419.25  4152.5  416.47
  4168.9  415.95  4174.5  413.72    4191  413.33  4196.6  411.18  4323.4  406.28
  4498.5  404.94    4606  406.08  4763.4  407.49    4947  408.66  4963.3  408.06
  4987.6  403.43  4992.5  401.59  5004.5  400.54  5007.3  400.04  5010.5  400.54
  5015.2  403.62  5020.8  402.55  5043.5  407.57  5113.2  410.75  5194.1  416.14
  5253.9  422.56  5303.1   427.5  5324.9  432.16  5340.7  433.71  5433.2  433.66
#Mann= 8 ,-1 , 0
  4102.4     .05       0    4606     .08       0  4763.4     .05       0
  4987.6     .08       0  5004.5     .07       0  5010.5     .08       0
  5253.9     .08       0  5340.7     .05       0
Bank Sta=5004.5,5010.5
XS Rating Curve= 0 ,0
Exp/Cntr=0.3,0.1

Type RM Length L Ch R = 1 ,3684    ,47,47,47
BEGIN DESCRIPTION:
BEAR BRANCH 5.02
END DESCRIPTION:
XS GIS Cut Line= 6
       3565867.6     10532212.98      3565605.87     10532069.74
      3565049.88     10532100.99      3565006.91      10532103.6
      3564891.03     10532051.51      3564540.75     10531883.54
#Sta/Elev= 30
  4016.8  422.05  4067.3  422.03    4073  419.53  4089.1  420.93  4094.8  417.91
  4110.9  418.56  4116.6  415.79  4132.8  416.33  4138.5  413.66  4154.6  413.78
  4176.4  410.28  4281.1   407.6  4354.7  406.11  4502.6  404.91  4787.4  407.74
  4952.1  408.37  4968.7  406.77  4980.7  403.16  4986.2  404.21  5000.9  400.89
  5003.6  400.39  5006.9  400.89  5015.1  403.72  5038.8  408.19  5185.1  415.93
  5256.2  423.76  5287.6  426.65  5315.2  432.16  5327.3  433.71  5430.6  433.68
#Mann= 11 ,-1 , 0
  4016.8     .05       0  4281.1     .08       0  4354.7     .05       0
  4502.6     .08       0  4787.4     .05       0  4968.7     .08       0
  5000.9     .07       0  5006.9     .08       0  5015.1     .05       0
  5256.2     .08       0  5315.2     .05       0
Bank Sta=5000.9,5006.9
XS Rating Curve= 0 ,0
Exp/Cntr=0.3,0.1

Type RM Length L Ch R = 1 ,3637    ,13,13,13
BEGIN DESCRIPTION:
BEAR BRANCH 5.0
END DESCRIPTION:
XS GIS Cut Line= 4
      3565915.82     10532009.85       3565060.3     10532063.23
      3564922.28     10532016.36      3564577.26     10531830.17
#Sta/Elev= 30
    4019  418.12  4042.8  417.35  4082.8  414.32  4092.9  413.21  4112.9  408.72
  4122.9  408.74    4128  407.76    4133  408.59  4151.7   407.2  4448.9  405.38
  4864.3  408.14    4912  408.08  4956.2  407.63  4969.3  403.38  4979.9  404.17
  4987.6  406.52  4989.8  401.47  4992.6  400.97  4995.8  401.47    5001  404.11
    5019  409.09  5024.9  408.63  5040.8  410.24    5054  410.19  5084.6     411
  5181.2  416.78  5259.1  425.75  5271.8   427.1  5306.2  433.76    5414  433.47
#Mann= 9 ,-1 , 0
    4019     .05       0  4151.7     .08       0  4864.3     .05       0
    4912     .08       0  4989.8     .07       0  4995.8     .08       0
    5054     .05       0  5259.1     .08       0  5271.8     .05       0
Bank Sta=4989.8,4995.8
XS Rating Curve= 0 ,0
Exp/Cntr=0.3,0.1

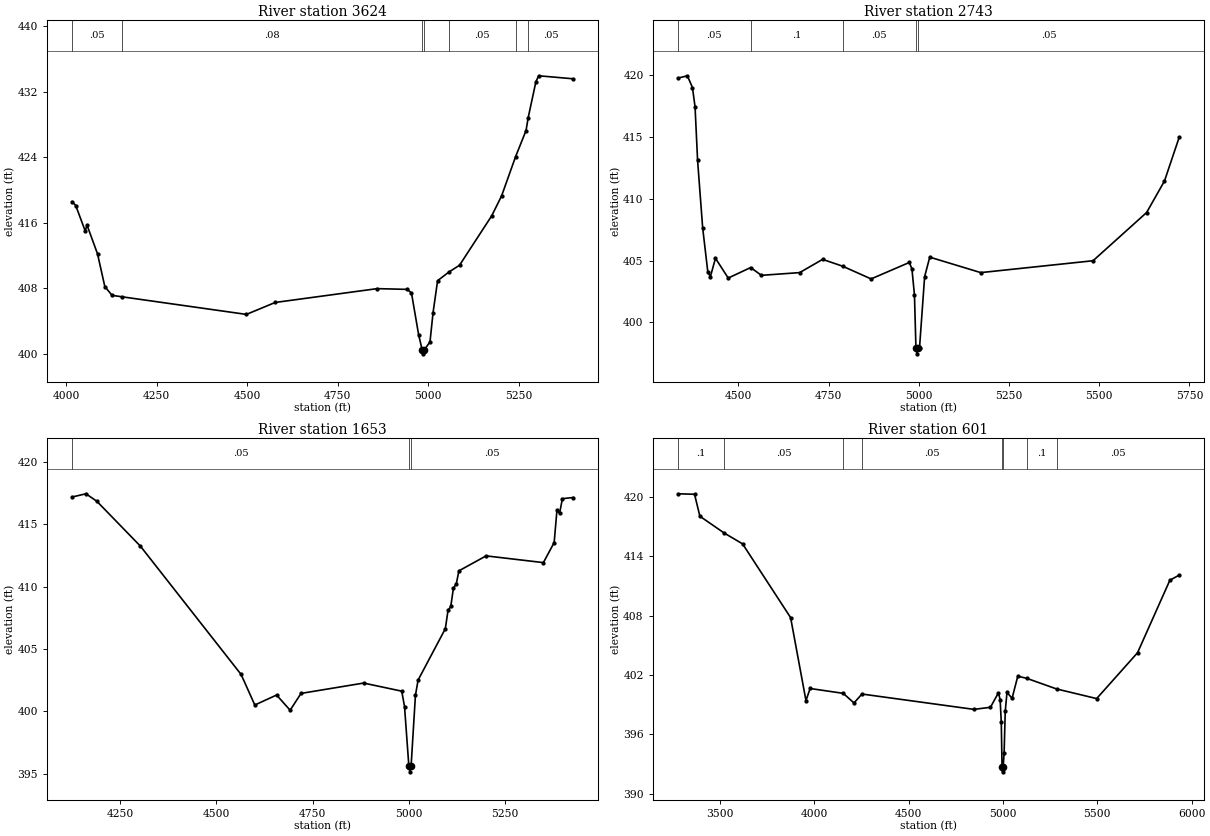
Type RM Length L Ch R = 1 ,3624    ,881,881,881
BEGIN DESCRIPTION:
BEAR BRANCH 5.01
END DESCRIPTION:
XS GIS Cut Line= 4
      3565922.32      10531983.8      3565065.51     10532048.91
      3564907.96     10531999.43      3564600.66     10531811.93
#Sta/Elev= 30
  4016.1  418.58  4026.3   418.1  4052.5  414.99  4057.5   415.7  4086.5  412.19
  4106.6   408.2  4126.6  407.12  4154.5  406.94  4497.7  404.79  4577.2  406.25
  4858.7  407.94  4941.8  407.85  4953.6  407.41  4973.3  402.31    4983  400.47
  4985.8  399.97    4989  400.47  5004.7  401.42  5013.2  405.01  5025.7  408.91
  5056.3  409.95  5086.3   410.8  5175.3  416.85  5202.5  419.28  5241.1  424.07
    5270  427.27    5276  428.86  5297.3  433.25  5305.1  433.96  5400.5  433.59
#Mann= 7 ,-1 , 0
  4016.1     .05       0  4154.5     .08       0    4983     .07       0
    4989     .08       0  5056.3     .05       0  5241.1     .08       0
    5276     .05       0
Bank Sta=4983,4989
XS Rating Curve= 0 ,0
Exp/Cntr=0.3,0.1

Type RM Length L Ch R = 1 ,2743    ,1090,1090,1090
BEGIN DESCRIPTION:
BEAR BRANCH 3.0
END DESCRIPTION:
XS GIS Cut Line= 2
      3566029.58      10531881.3      3565036.84     10530909.38
#Sta/Elev= 30
  4332.1  419.76  4358.3  419.95  4372.4     419  4379.6  417.44  4386.6  413.11
  4400.7  407.65  4414.9   404.1    4422  403.69  4436.2  405.19  4471.5  403.59
  4533.8  404.44  4563.5  403.81  4669.5  404.03  4733.2   405.1  4788.5  404.55
  4867.5  403.52  4973.5  404.85  4980.7  404.33  4987.7  402.23  4991.8  397.96
  4994.6  397.46  4997.8  397.96  5001.8  397.97  5015.9   403.7  5030.1  405.28
  5171.5  404.03  5482.7  404.99  5631.2  408.89  5680.7  411.44  5721.4  414.97
#Mann= 5 ,-1 , 0
  4332.1     .05       0  4533.8      .1       0  4788.5     .05       0
  4991.8     .03       0  4997.8     .05       0
Bank Sta=4991.8,4997.8
XS Rating Curve= 0 ,0
Exp/Cntr=0.3,0.1

Type RM Length L Ch R = 1 ,1653    ,1052,1052,1052
BEGIN DESCRIPTION:
BEAR BRANCH 2.0
END DESCRIPTION:
XS GIS Cut Line= 2
      3566609.41     10531235.44      3565707.89     10530295.77
#Sta/Elev= 30
    4125  417.19  4161.1  417.45  4189.4  416.85  4302.6  413.25  4564.2  402.96
  4599.8  400.51  4656.4  401.31  4691.6  400.09  4719.9  401.44  4882.5  402.27
  4981.5  401.62  4988.8  400.38  4999.9  395.65  5002.7  395.15  5005.9  395.65
  5017.1  401.29    5024  402.51  5094.8  406.63  5101.7  408.09  5108.9  408.41
  5115.8  409.89  5123.1   410.2    5130  411.27  5200.7  412.47  5349.5  411.93
  5377.5  413.54  5384.7  416.11  5391.6  415.89  5398.9  417.06  5427.2  417.15
#Mann= 3 ,-1 , 0
    4125     .05       0  4999.9     .03       0  5005.9     .05       0
Bank Sta=4999.9,5005.9
XS Rating Curve= 0 ,0
Exp/Cntr=0.3,0.1

Type RM Length L Ch R = 1 ,601     ,0,0,0
BEGIN DESCRIPTION:
BEAR BRANCH 1.0
END DESCRIPTION:
XS GIS Cut Line= 4
       3566689.8     10531478.25      3566394.67     10529954.83
      3566121.23     10529776.88      3565470.23     10530206.54
#Sta/Elev= 30
  3275.9  420.31  3364.1  420.26  3392.4  418.04  3520.9  416.35  3618.8  415.25
  3873.5   407.8  3954.9  399.42    3977  400.64  4152.5  400.15  4209.6  399.18
  4251.7  400.08  4845.6  398.53  4933.2  398.74  4975.4   400.2  4984.6  399.51
  4990.6  397.22  4994.7  392.72  4997.5  392.22  5000.7  392.72  5005.7  394.16
  5011.6  398.32  5020.8  400.24  5047.9  399.65  5078.1  401.88    5125  401.67
  5284.3  400.59  5496.4  399.62  5713.1  404.25  5884.7  411.58  5933.9  412.09
#Mann= 8 ,-1 , 0
  3275.9      .1       0  3520.9     .05       0  4152.5     .16       0
  4251.7     .05       0  4994.7     .03       0  5000.7     .05       0
    5125      .1       0  5284.3     .05       0
Bank Sta=4994.7,5000.7
XS Rating Curve= 0 ,0
Exp/Cntr=0.3,0.1

Chan Stop Cuts=-1
Use User Specified Reach Order=0
Composite Channel Slope=5