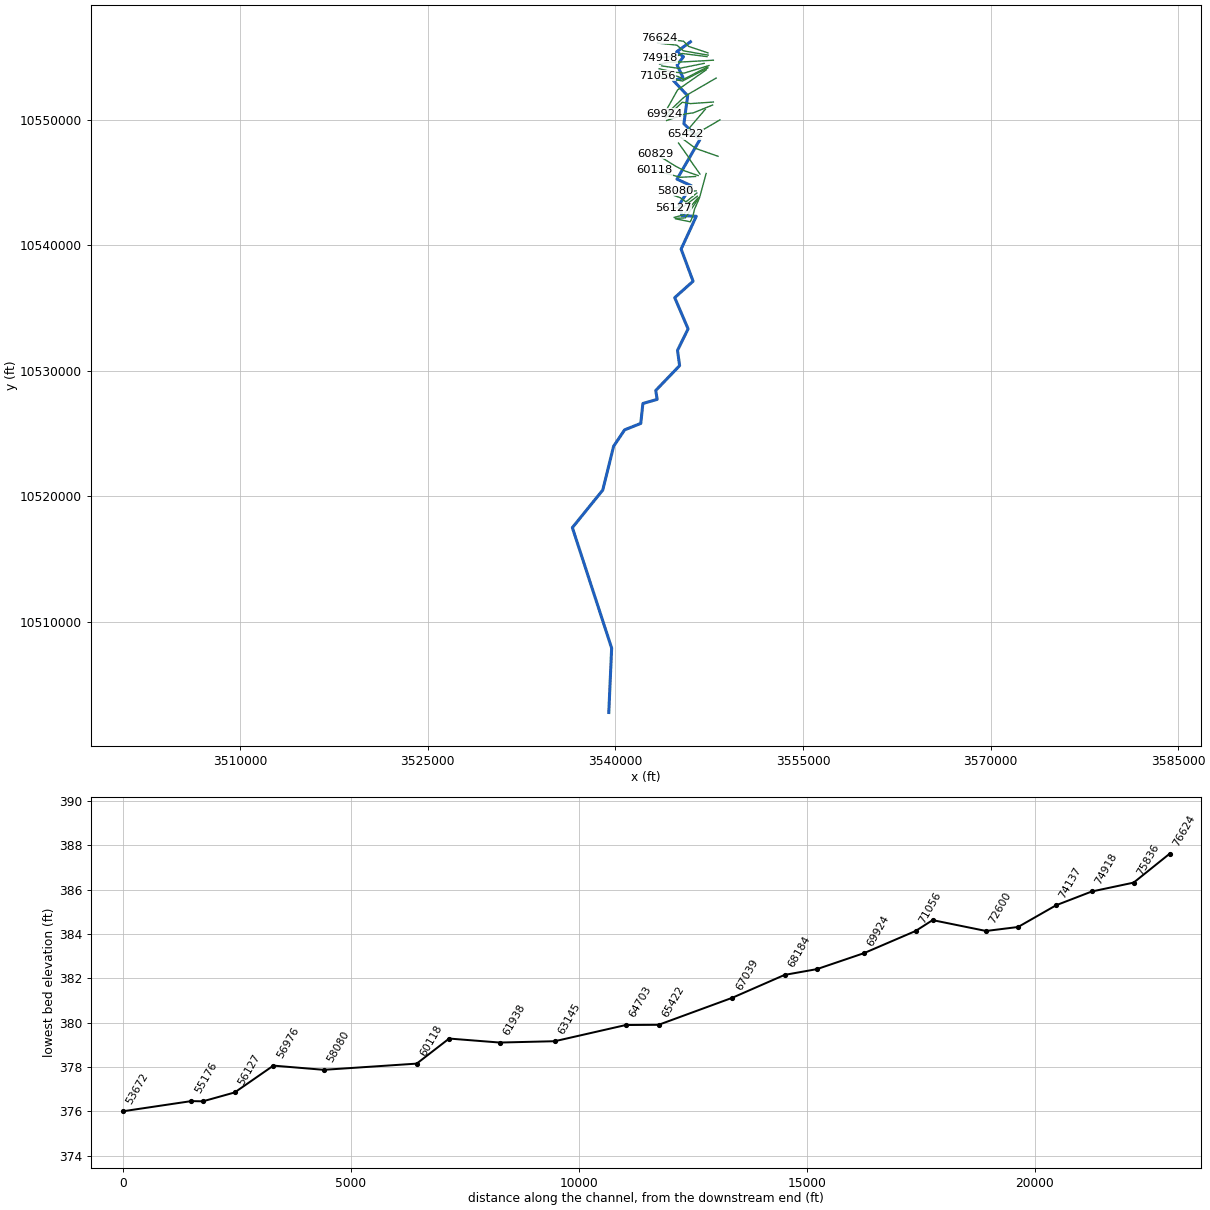
--- BIGELMCREEK.prj (project) ---

Proj Title=BIG ELM CREEK Base Level Engineering
Current Plan=p01
Default Exp/Contr=0.3,0.1
English Units
Geom File=g01
Flow File=f01
Plan File=p01
Y Axis Title=Elevation
X Axis Title(PF)=Main Channel Distance
X Axis Title(XS)=Station
BEGIN DESCRIPTION:
BIG CREEK
END DESCRIPTION:
DSS Export Rating Curves= 0
DSS Export Rating Curve Sorted= 0
DSS Export Volume Flow Curves= 0
DXF Filename=BIG CREEK.
DXF OffsetX= 0
DXF OffsetY= 0
DXF ScaleX= 1
DXF ScaleY= 10

--- BIGELMCREEK.p01 (plan) ---

Plan Title=Multiple Run
Short Identifier=Multiple
Geom File=g01
Flow File=f01
Subcritical Flow
K Sum by GR= 0
Std Step Tol= 0.01
Critical Tol= 0.01
Num of Std Step Trials= 20
Max Error Tol= 0.3
Flow Tol Ratio= 0.001
Split Flow NTrial= 30
Split Flow Tol= 0.02
Split Flow Ratio= 0.02
Log Output Level= 0
Friction Slope Method= 1
Unsteady Friction Slope Method= 2
Unsteady Bridges Friction Slope Method= 1
Parabolic Critical Depth
Global Vel Dist=  1 , 1 , 1
Global Log Level= 0
CheckData=True
Encroach Param= -1, 0, 0, 0
BEGIN DESCRIPTION:
Multiple Run
END DESCRIPTION:

--- BIGELMCREEK.f01 (steady flow) ---

Flow Title=Multiple
Program Version=4.10
Number of Profiles= 7
Profile Names=10-year,25-year,50-year,1pct_min,100-year,1pct_plu,500-year
River Rch & RM=BIG CREEK,Reach-1         ,76624
   12393   18202   23300   21573   29175   39456   45605
River Rch & RM=BIG CREEK,Reach-1         ,69924
   13032   19137   24496   22677   30668   41474   47919
River Rch & RM=BIG CREEK,Reach-1         ,60118
   12831   18807   24041   22225   30056   40648   46833
River Rch & RM=BIG CREEK,Reach-1         ,52930
   13609   19938   25481   23548   31846   43068   49582
River Rch & RM=BIG CREEK,Reach-1         ,50317
   14127   20731   26527   24543   33192   44888   51797
River Rch & RM=BIG CREEK,Reach-1         ,46768
   14152   20749   26533   24533   33178   44869   51705
River Rch & RM=BIG CREEK,Reach-1         ,44833
   14565   21371   27342   25294   34207   46261   53361
River Rch & RM=BIG CREEK,Reach-1         ,41361
   14507   21275   27210   25162   34029   46020   53043
River Rch & RM=BIG CREEK,Reach-1         ,39006
   14327   20968   26781   24730   33444   45230   51982
River Rch & RM=BIG CREEK,Reach-1         ,36912
   14578   21362   27308   25239   34133   46161   53148
River Rch & RM=BIG CREEK,Reach-1         ,34354
   14570   21333   27255   25174   34046   46043   52945
River Rch & RM=BIG CREEK,Reach-1         ,29416
   14618   21365   27263   25150   34013   45998   52756
River Rch & RM=BIG CREEK,Reach-1         ,24167
   14598   21329   27212   25097   33941   45901   52622
River Rch & RM=BIG CREEK,Reach-1         ,21731
   14605   21325   27193   25067   33901   45847   52506
River Rch & RM=BIG CREEK,Reach-1         ,17689
   14676   21402   27267   25111   33960   45927   52496
River Rch & RM=BIG CREEK,Reach-1         ,12478
   14577   21228   27020   24860   33620   45467   51868
River Rch & RM=BIG CREEK,Reach-1         ,7438
   14591   21231   27008   24833   33583   45418   51746
River Rch & RM=BIG ELM CREEK,Reach-1         ,76624
   12393   18202   23300   21573   29175   39456   45605
River Rch & RM=BIG ELM CREEK,Reach-1         ,69924
   13032   19137   24496   22677   30668   41474   47919
River Rch & RM=BIG ELM CREEK,Reach-1         ,60118
   12831   18807   24041   22225   30056   40648   46833
River Rch & RM=BIG ELM CREEK,Reach-1         ,52930
   13609   19938   25481   23548   31846   43068   49582
River Rch & RM=BIG ELM CREEK,Reach-1         ,50317
   14127   20731   26527   24543   33192   44888   51797
River Rch & RM=BIG ELM CREEK,Reach-1         ,46768
   14152   20749   26533   24533   33178   44869   51705
River Rch & RM=BIG ELM CREEK,Reach-1         ,44833
   14565   21371   27342   25294   34207   46261   53361
River Rch & RM=BIG ELM CREEK,Reach-1         ,41361
   14507   21275   27210   25162   34029   46020   53043
River Rch & RM=BIG ELM CREEK,Reach-1         ,39006
   14327   20968   26781   24730   33444   45230   51982
River Rch & RM=BIG ELM CREEK,Reach-1         ,36912
   14578   21362   27308   25239   34133   46161   53148
River Rch & RM=BIG ELM CREEK,Reach-1         ,34354
   14570   21333   27255   25174   34046   46043   52945
River Rch & RM=BIG ELM CREEK,Reach-1         ,29416
   14618   21365   27263   25150   34013   45998   52756
River Rch & RM=BIG ELM CREEK,Reach-1         ,24167
   14598   21329   27212   25097   33941   45901   52622
River Rch & RM=BIG ELM CREEK,Reach-1         ,21731
   14605   21325   27193   25067   33901   45847   52506
River Rch & RM=BIG ELM CREEK,Reach-1         ,17689
   14676   21402   27267   25111   33960   45927   52496
River Rch & RM=BIG ELM CREEK,Reach-1         ,12478
   14577   21228   27020   24860   33620   45467   51868
River Rch & RM=BIG ELM CREEK,Reach-1         ,7438
   14591   21231   27008   24833   33583   45418   51746
Boundary for River Rch & Prof#=BIG ELM CREEK,Reach-1         , 1
Up Type= 0
Dn Type= 3
Dn Slope=0.001
Boundary for River Rch & Prof#=BIG ELM CREEK,Reach-1         , 2
Up Type= 0
Dn Type= 3
Dn Slope=0.001
Boundary for River Rch & Prof#=BIG ELM CREEK,Reach-1         , 3
Up Type= 0
Dn Type= 3
Dn Slope=0.001
Boundary for River Rch & Prof#=BIG ELM CREEK,Reach-1         , 4
Up Type= 0
Dn Type= 3
Dn Slope=0.001
Boundary for River Rch & Prof#=BIG ELM CREEK,Reach-1         , 5
Up Type= 0
Dn Type= 3
Dn Slope=0.001
Boundary for River Rch & Prof#=BIG ELM CREEK,Reach-1         , 6
Up Type= 0
Dn Type= 3
Dn Slope=0.001
Boundary for River Rch & Prof#=BIG ELM CREEK,Reach-1         , 7
Up Type= 0
Dn Type= 3
Dn Slope=0.001
DSS Import GetInterval= 0
DSS Import GetPeak= 0
DSS Import FillOption= 0

--- BIGELMCREEK.g01 (geometry) ---

Geom Title=Existing Conditions
Program Version=4.10

River Reach=BIG ELM CREEK   ,Reach-1
Reach XY= 30
      3546002.11     10556211.64      3544892.11     10555411.64
      3545439.51     10555020.44      3544931.52     10554361.84
      3545401.95     10553366.25      3544643.08     10553111.07
      3545775.02     10551916.31      3545475.63     10549683.08
      3546752.64      10548421.5      3544923.58     10545271.33
      3546071.68     10544746.46      3545114.07     10543256.46
      3545318.03     10542369.11      3546462.49     10542314.14
      3545252.61     10539701.59      3546209.43     10537142.78
      3544742.03     10535836.25      3545810.28     10533345.87
       3544963.5     10531636.08      3545130.16     10530417.03
      3543222.77     10528440.37      3543338.95     10527733.98
      3542194.42     10527404.55      3542026.97     10525818.77
      3540731.86     10525304.98      3539853.68     10524000.26
      3538984.72     10520509.65      3536556.35     10517520.12
       3539697.1     10507922.17      3539467.95     10502795.31

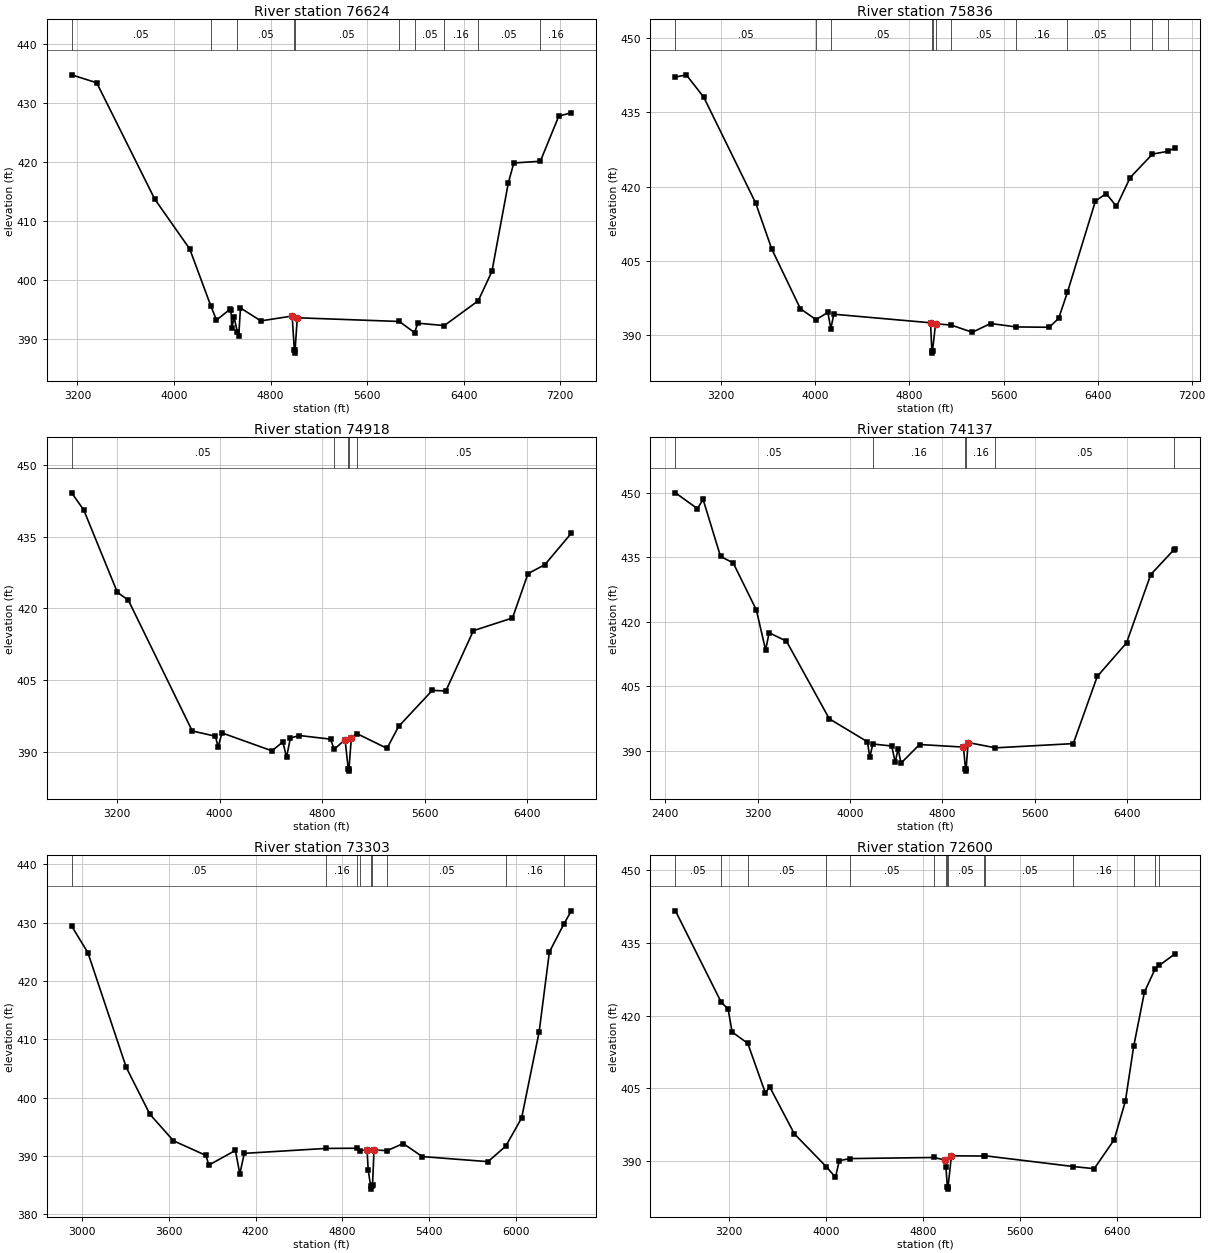
Type RM Length L Ch R = 1 ,76624   ,788,788,788
BEGIN DESCRIPTION:
BIG CREEK 50.0
END DESCRIPTION:
XS GIS Cut Line= 4
      3547399.17     10555328.41      3545852.29     10555844.04
      3545446.04      10556255.5      3543529.39     10556489.87
#Sta/Elev= 30
  3152.2  434.75  3359.9   433.4  3840.9  413.69  4130.8  405.24  4305.6  395.59
  4352.2  393.21  4466.7  395.07  4473.4  394.84  4478.6  391.82  4498.3  393.69
  4525.4  391.14  4536.6  390.52    4551  395.26  4719.7  393.07  4979.2  393.89
  4997.4  388.11  5000.2  387.61  5003.4  388.11  5021.6   393.6  5867.1  392.97
  5993.9  391.07  6019.8  392.68  6239.9  392.28  6520.5  396.47  6634.3  401.45
  6770.6  416.49  6815.7  419.82  7035.5  420.11  7188.4  427.76  7291.9  428.32
#Mann= 10 ,-1 , 0
  3152.2     .05       0  4305.6     .16       0  4525.4     .05       0
  4997.4     .03       0  5003.4     .05       0  5867.1     .16       0
  5993.9     .05       0  6239.9     .16       0  6520.5     .05       0
  7035.5     .16       0
Bank Sta=4979.2,5021.6
XS Rating Curve= 0 ,0
Exp/Cntr=0.3,0.1

Type RM Length L Ch R = 1 ,75836   ,918,918,918
BEGIN DESCRIPTION:
BIG CREEK 49.1
END DESCRIPTION:
XS GIS Cut Line= 4
      3547409.57     10555151.34      3545435.62     10555489.88
      3544914.79       10555943.      3543367.86     10556109.67
#Sta/Elev= 30
  2809.6  442.16  2901.8  442.61  3050.5  438.08  3491.8  416.68  3628.9  407.36
  3872.4  395.28  4005.1  393.09  4105.7  394.54  4131.2  391.28  4156.4  394.18
  4978.9  392.45  4990.1  386.81  4992.9  386.31  4996.1  386.81  5021.6  392.26
  5024.6  392.24  5154.3  391.99    5334  390.53  5489.7   392.3  5706.9  391.61
  5988.2  391.54  6068.7  393.35    6143  398.62  6381.2  417.08  6473.1  418.58
    6560  415.98  6676.7  421.82    6866  426.58  6998.2  427.13  7058.6  427.86
#Mann= 12 ,-1 , 0
  2809.6     .05       0  4005.1     .16       0  4131.2     .05       0
  4990.1     .03       0  4996.1     .05       0  5024.6     .16       0
  5154.3     .05       0  5706.9     .16       0    6143     .05       0
  6676.7     .16       0    6866      .1       0  6998.2     .05       0
Bank Sta=4978.9,5021.6
XS Rating Curve= 0 ,0
Exp/Cntr=0.3,0.1

Type RM Length L Ch R = 1 ,74918   ,781,781,781
BEGIN DESCRIPTION:
BIG CREEK 49.0
END DESCRIPTION:
XS GIS Cut Line= 4
      3547315.86     10555031.54      3545326.24     10555281.54
      3545060.62      10555130.5      3543487.68     10554911.75
#Sta/Elev= 30
  2846.1  444.24  2940.6  440.64  3202.6   423.4  3288.2  421.75  3787.2  394.33
  3968.6  393.22  3988.8  390.91    4019  393.92    4409  390.16  4494.5  392.03
  4522.9  388.81  4553.2  392.86  4623.7  393.37  4867.6  392.61  4893.5  390.46
  4979.8  392.51  5004.2  386.41  5006.9  385.91  5010.2  386.41  5028.8  392.94
  5070.6  393.79  5306.9  390.69  5397.7  395.28  5660.2  402.83    5766  402.71
  5980.9  415.35  6286.2  418.01  6407.4  427.31  6538.6  429.18    6745  435.76
#Mann= 5 ,-1 , 0
  2846.1     .05       0  4893.5     .16       0  5004.2     .07       0
  5010.2     .16       0  5070.6     .05       0
Bank Sta=4979.8,5028.8
XS Rating Curve= 0 ,0
Exp/Cntr=0.3,0.1

Type RM Length L Ch R = 1 ,74137   ,834,834,834
BEGIN DESCRIPTION:
BIG CREEK 48.3
END DESCRIPTION:
XS GIS Cut Line= 4
      3547831.44     10554745.08      3545430.41     10554609.67
      3544242.91     10554578.42      3543525.68     10554432.89
#Sta/Elev= 30
  2489.2  450.02  2678.8  446.35  2728.9  448.47  2879.2  435.24  2989.3  433.71
  3189.6  422.77  3269.8  413.44  3299.8  417.48  3450.1  415.51  3820.6  397.47
  4151.2  392.11  4171.2  388.46  4197.5   391.6  4361.5  391.13  4391.6  387.31
  4415.8  390.52  4441.6  387.14  4601.9  391.48  4982.4  390.88  4999.4  385.79
  5002.1  385.29  5005.4  385.79  5022.4  391.94  5259.2  390.71  5932.7  391.69
    6140  407.31  6393.3  415.11  6603.2  431.02  6800.2  436.68  6813.8  436.95
#Mann= 6 ,-1 , 0
  2489.2     .05       0  4197.5     .16       0  4999.4     .07       0
  5005.4     .16       0  5259.2     .05       0  6800.2      .1       0
Bank Sta=4982.4,5022.4
XS Rating Curve= 0 ,0
Exp/Cntr=0.3,0.1

Type RM Length L Ch R = 1 ,73303   ,703,703,703
BEGIN DESCRIPTION:
BIG CREEK 48.0
END DESCRIPTION:
XS GIS Cut Line= 3
      3547092.08     10554491.64      3545092.11     10554091.64
       3543692.1     10554291.64
#Sta/Elev= 30
  2928.5  429.41  3040.7  424.85  3305.8  405.19    3469  397.16  3632.1   392.6
  3856.5  390.09  3876.9  388.43  4060.5  390.95    4091   386.9  4121.6  390.44
  4687.4  391.29  4899.4  391.32  4924.8  390.91  4970.6  391.07  4978.2  387.64
  4995.4  384.81  4998.1  384.31  5001.4  384.81  5008.5   385.1  5018.6  391.04
  5108.8   390.9  5220.6  392.13  5351.9  389.89  5806.5  389.02  5929.2  391.68
  6038.8  396.49  6160.1  411.27  6230.8  424.96  6331.1  429.76  6382.3  432.02
#Mann= 9 ,-1 , 0
  2928.5     .05       0  4687.4     .16       0  4899.4     .05       0
  4924.8     .16       0  4995.4     .07       0  5001.4     .16       0
  5108.8     .05       0  5929.2     .16       0  6331.1      .1       0
Bank Sta=4970.6,5018.6
XS Rating Curve= 0 ,0
Exp/Cntr=0.3,0.1

Type RM Length L Ch R = 1 ,72600   ,1171,1171,1171
BEGIN DESCRIPTION:
BIG CREEK 48.2
END DESCRIPTION:
XS GIS Cut Line= 4
      3547482.47      10554323.2       3545487.7     10553713.83
       3544636.6     10553802.98      3543492.87      10554062.8
#Sta/Elev= 30
  2761.2  441.63    3137   422.8    3195  421.33  3227.8   416.6  3356.9  414.24
  3500.6  404.07  3538.6   405.2  3740.6  395.54  4002.2  388.79  4079.1  386.59
  4110.4  390.01  4198.5  390.44  4888.5  390.67  4983.3  390.14  4988.4  388.67
  5000.4  384.63  5003.2  384.13  5006.4  384.63  5033.6  391.01  5298.3  390.97
  5313.5  391.01    6037   388.8  6209.8  388.35  6373.9  394.34  6466.2   402.3
  6534.6  413.62  6623.6  424.88  6710.3  429.57  6745.3  430.34  6875.6  432.76
#Mann= 15 ,-1 , 0
  2761.2     .05       0    3137      .1       0  3356.9     .05       0
  4002.2     .16       0  4198.5     .05       0  4888.5     .16       0
  4988.4     .05       0  5000.4     .03       0  5006.4     .05       0
  5298.3     .16       0  5313.5     .05       0    6037     .16       0
  6534.6     .05       0  6710.3      .1       0  6745.3     .05       0
Bank Sta=4983.3,5033.6
XS Rating Curve= 0 ,0
Exp/Cntr=0.3,0.1

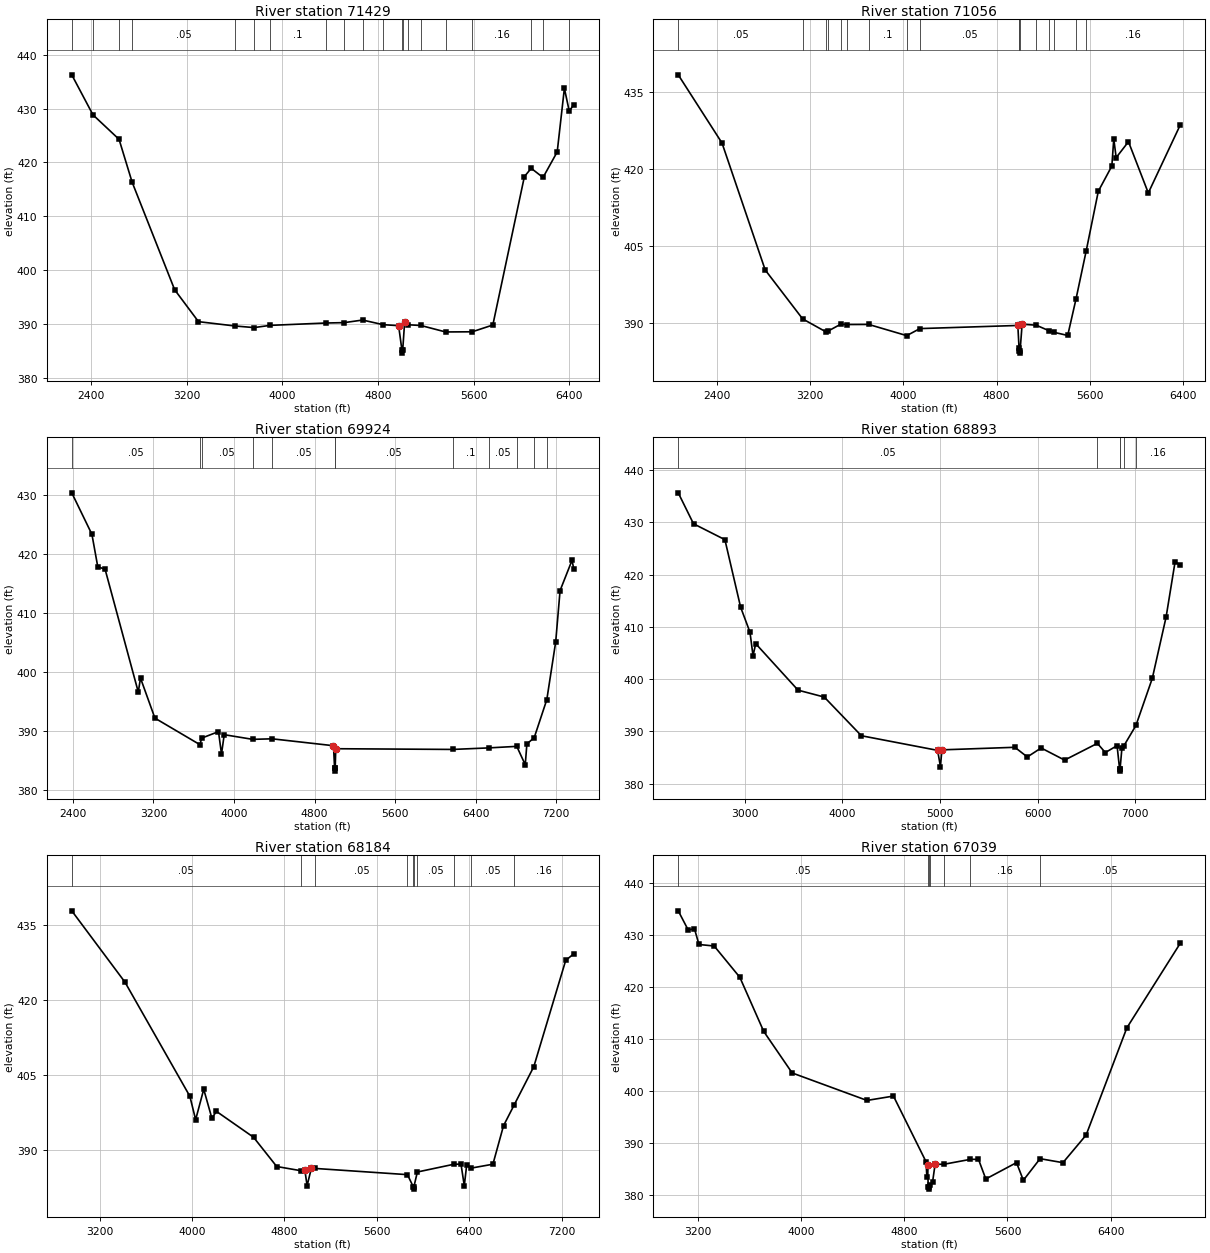
Type RM Length L Ch R = 1 ,71429   ,373,373,373
BEGIN DESCRIPTION:
BIG CREEK 48.1
END DESCRIPTION:
XS GIS Cut Line= 4
      3547367.95     10554213.85      3545419.99     10553208.63
      3545023.83     10553440.68      3543525.63     10553843.65
#Sta/Elev= 30
  2236.2  436.27  2413.8  428.84    2632   424.3    2741  416.37  3097.4  396.38
  3296.8  390.46  3601.4  389.66  3762.1  389.36  3895.2  389.77  4364.2  390.21
    4517  390.28  4670.8  390.76  4842.4   389.9    4972  389.72  5000.1  385.12
  5002.8  384.62  5006.1  385.12  5022.2  390.31  5054.7  389.88  5158.2  389.75
  5365.2  388.55  5588.2  388.58  5760.7  389.84  6024.9  417.39    6082  418.92
  6180.8  417.22  6299.5  421.96  6359.6  433.76  6400.3  429.53  6438.8  430.76
#Mann= 20 ,-1 , 0
  2236.2     .05       0  2413.8      .1       0    2632      .1       0
    2741     .05       0  3601.4     .16       0  3762.1     .08       0
  3895.2      .1       0  4364.2     .05       0    4517     .16       0
  4670.8     .05       0  4842.4      .1       0  5000.1     .07       0
  5006.1     .16       0  5054.7     .05       0  5158.2     .08       0
  5365.2     .05       0  5588.2     .16       0    6082     .05       0
  6180.8     .16       0  6400.3      .1       0
Bank Sta=4972,5022.2
XS Rating Curve= 0 ,0
Exp/Cntr=0.3,0.1

Type RM Length L Ch R = 1 ,71056   ,1132,1132,1132
BEGIN DESCRIPTION:
BIG CREEK 47.0
END DESCRIPTION:
XS GIS Cut Line= 3
       3547388.7     10554130.48      3545357.49     10553083.63
      3543373.14      10553510.7
#Sta/Elev= 30
  2064.6  438.35  2440.9  425.06    2812  400.33  3133.7   390.8  3332.7  388.29
  3351.8  388.42  3460.8  389.76  3510.8   389.7  3701.3  389.72  4028.3  387.54
  4141.5  388.91  4983.1  389.52  4993.6  385.11  4996.6  384.63  4999.4  384.13
  5002.6  384.63  5020.1  389.77  5141.4  389.57  5252.4  388.48  5289.9  388.21
  5411.8  387.57  5482.4   394.6  5570.7  404.05  5674.8  415.67  5791.1  420.58
  5807.7  425.86  5828.2  422.22    5934  425.32  6104.4  415.33  6379.5  428.61
#Mann= 17 ,-1 , 0
  2064.6     .05       0  3133.7     .08       0  3332.7     .16       0
  3351.8     .08       0  3460.8     .16       0  3510.8     .08       0
  3701.3      .1       0  4028.3     .16       0  4141.5     .05       0
  4993.6      .1       0  4996.6     .07       0  5002.6      .1       0
  5141.4     .05       0  5252.4      .1       0  5289.9     .08       0
  5482.4     .05       0  5570.7     .16       0
Bank Sta=4983.1,5020.1
XS Rating Curve= 0 ,0
Exp/Cntr=0.3,0.1

Type RM Length L Ch R = 1 ,69924   ,1031,1031,1031
BEGIN DESCRIPTION:
BIG CREEK 46.0
END DESCRIPTION:
XS GIS Cut Line= 4
      3547263.72     10553979.44      3545263.74     10552583.63
      3544972.08      10552380.5      3543899.17     10550469.06
#Sta/Elev= 30
  2389.3  430.33  2589.4  423.29  2647.4   417.8  2720.3  417.36  3049.8  396.54
  3071.9  398.91  3214.9  392.12  3662.9  387.61  3678.3  388.72  3846.5  389.83
  3876.2  386.03  3903.4  389.31  4185.8  388.52    4379  388.61  4988.6  387.44
  4999.4  383.63  5002.1  383.13  5005.4  383.63  5011.1  386.93  6174.5  386.81
  6530.2  387.07  6808.7  387.33  6893.1  384.21  6909.1  387.74  6982.1  388.81
  7107.2  395.26  7195.4  405.06  7238.8  413.75  7357.4  418.88  7375.6  417.37
#Mann= 12 ,-1 , 0
  2389.3     .05       0  3662.9     .16       0  3678.3     .05       0
  4185.8      .1       0    4379     .05       0  4999.4     .03       0
  5005.4     .05       0  6174.5      .1       0  6530.2     .05       0
  6808.7     .16       0  6982.1     .05       0  7107.2     .16       0
Bank Sta=4988.6,5011.1
XS Rating Curve= 0 ,0
Exp/Cntr=0.3,0.1

Type RM Length L Ch R = 1 ,68893   ,709,709,709
BEGIN DESCRIPTION:
BIG CREEK 45.0
END DESCRIPTION:
XS GIS Cut Line= 4
      3548055.43     10553323.22      3545883.54       10552068.
       3545425.2     10551745.08      3543919.97     10550317.98
#Sta/Elev= 30
  2318.5  435.65  2474.9  429.73  2796.5  426.69  2957.6  413.77  3053.4  408.99
  3084.6  404.49  3112.3  406.79  3545.8   397.9  3814.3  396.58  4194.7  389.18
  4975.6  386.38  5004.6  383.28  5019.4  386.48  5767.1  386.97  5894.5  385.12
  6036.1  386.84  6276.4  384.52  6612.2  387.72  6693.8  385.96    6814  387.29
  6839.3  382.91  6842.1  382.41  6845.3  382.91  6863.7  386.82  6880.8  387.16
  7007.1  391.14  7174.8  400.15  7316.4   411.9  7408.2  422.44  7461.9  421.82
#Mann= 6 ,-1 , 0
  2318.5     .05       0  6612.2     .16       0  6839.3     .03       0
  6845.3     .16       0  6880.8     .05       0  7007.1     .16       0
Bank Sta=4975.6,5019.4
XS Rating Curve= 0 ,0
Exp/Cntr=0.3,0.1

Type RM Length L Ch R = 1 ,68184   ,1145,1145,1145
BEGIN DESCRIPTION:
BIG CREEK 44.0
END DESCRIPTION:
XS GIS Cut Line= 4
      3547831.46     10551413.49      3545999.86     10551287.62
      3545344.47     10551396.13      3543992.14     10550141.68
#Sta/Elev= 30
  2959.3   437.9  3419.7  423.61  3981.1  400.76  4031.2  396.06  4101.3  402.15
  4171.5  396.37  4211.6  397.72  4532.4  392.54  4732.8  386.68  4939.6  385.85
  4976.7   385.9  4995.7  382.85  5032.6  386.31  5068.2  386.29  5864.1  385.05
  5914.1  382.65  5916.9  382.15  5920.1  382.65  5949.9  385.58  6265.4  387.13
  6327.6  387.16    6356  382.83  6376.9  387.01  6412.7  386.35  6603.7  387.14
  6695.5  394.85  6789.3  399.09  6957.5  406.68  7233.6  427.97  7304.1   429.3
#Mann= 10 ,-1 , 0
  2959.3     .05       0  4939.6     .16       0  5068.2     .05       0
  5864.1     .16       0  5914.1     .07       0  5920.1     .16       0
  5949.9     .05       0  6265.4     .16       0  6412.7     .05       0
  6789.3     .16       0
Bank Sta=4976.7,5032.6
XS Rating Curve= 0 ,0
Exp/Cntr=0.3,0.1

Type RM Length L Ch R = 1 ,67039   ,1617,1617,1617
BEGIN DESCRIPTION:
BIG CREEK 43.0
END DESCRIPTION:
XS GIS Cut Line= 4
      3547770.69     10551174.77      3546216.87     10550549.77
      3545617.91     10550471.65      3544092.08     10549941.63
#Sta/Elev= 30
  3046.6  434.68  3123.9  430.99  3172.3  431.24  3207.3   428.2  3325.3  427.91
  3524.3  421.89  3709.7  411.47  3930.1  403.48  4510.5  398.19  4715.8  399.03
  4968.2  386.41  4975.4  383.36  4980.5  385.68  4985.4  381.62  4988.2  381.12
  4991.4  381.62  4998.1  381.87  5018.7  382.41  5038.8  385.89  5108.6  385.91
  5312.5  386.85  5375.2  386.86  5432.1  383.07  5670.3  386.22  5723.3  382.82
    5853  386.98  6030.3  386.21  6210.2  391.53  6525.9  412.15  6940.7  428.45
#Mann= 7 ,-1 , 0
  3046.6     .05       0  4985.4     .07       0  4991.4     .05       0
  4998.1     .16       0  5108.6      .1       0  5312.5     .16       0
    5853     .05       0
Bank Sta=4980.5,5038.8
XS Rating Curve= 0 ,0
Exp/Cntr=0.3,0.1

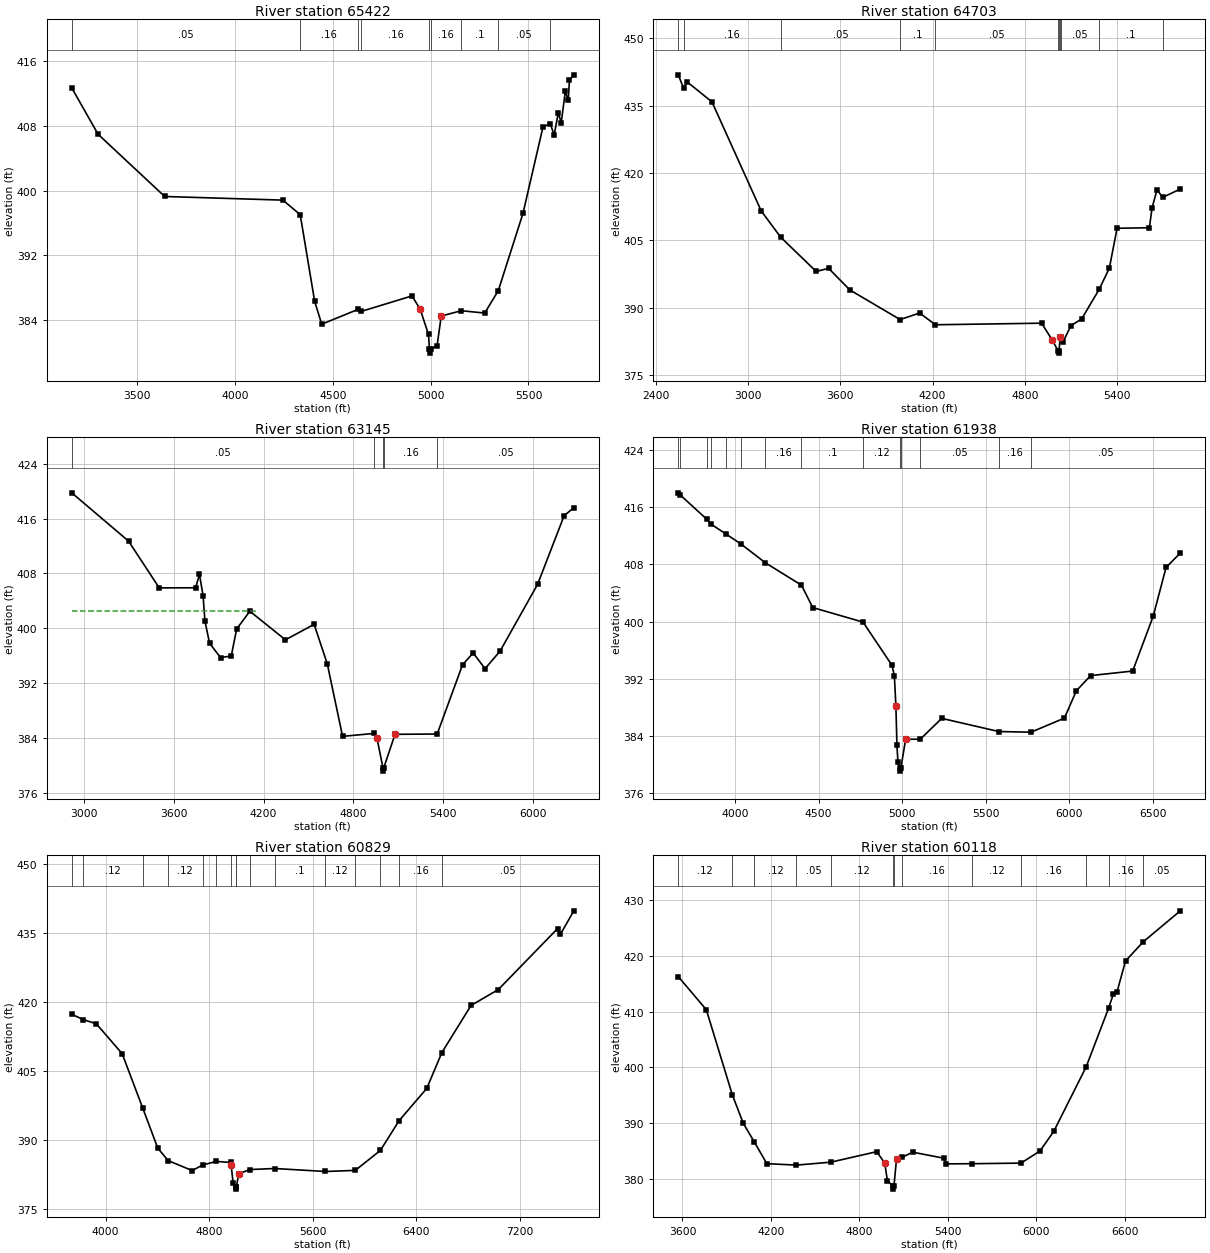
Type RM Length L Ch R = 1 ,65422   ,719,719,719
BEGIN DESCRIPTION:
BIG CREEK 42.0
END DESCRIPTION:
XS GIS Cut Line= 3
      3547192.11     10550841.64      3545992.11     10549441.64
      3545592.12     10548841.66
#Sta/Elev= 30
  3166.9  412.73  3301.4  406.99  3641.6  399.29  4245.3  398.84    4334  397.04
  4407.7  386.32  4443.9  383.48  4630.9  385.33  4646.3  385.07  4904.9  386.98
  4946.6  385.35  4989.4  382.21  4994.1   380.4  4996.8   379.9  5000.1   380.4
  5033.3  380.84  5054.4  384.49  5156.7  385.15  5276.7  384.86  5346.1  387.65
    5472   397.2  5574.2  407.89  5611.4  408.32  5631.3  406.88  5652.3  409.65
  5667.3  408.42  5688.4   412.3  5703.4   411.2  5709.4  413.68  5731.9  414.35
#Mann= 9 ,-1 , 0
  3166.9     .05       0    4334     .16       0  4630.9     .05       0
  4646.3     .16       0  4994.1     .07       0  5000.1     .16       0
  5156.7      .1       0  5346.1     .05       0  5611.4      .1       0
Bank Sta=4946.6,5054.4
XS Rating Curve= 0 ,0
Exp/Cntr=0.3,0.1

Type RM Length L Ch R = 1 ,64703   ,1558,1558,1558
BEGIN DESCRIPTION:
BIG CREEK 41.0
END DESCRIPTION:
XS GIS Cut Line= 3
      3548352.33      10549989.9      3546351.42     10548822.34
      3545400.93     10548765.92
#Sta/Elev= 30
  2544.2   441.9  2578.7  438.96  2602.3  440.32  2763.8  435.87  3084.6  411.56
  3211.3  405.72  3442.6  398.08  3522.9  398.79  3661.8  393.96  3988.8  387.37
  4115.7  388.83  4218.6  386.21  4910.2  386.56  4980.4  382.73  5017.4  380.39
  5020.2  379.89  5023.4  380.39  5031.2  383.51  5033.9  383.39  5050.5  382.43
  5100.6  386.01  5170.7   387.5  5284.9  394.12    5351  398.82  5401.1  407.71
  5611.5  407.83  5629.3  412.29  5661.6  416.31  5697.9  414.58    5813  416.46
#Mann= 11 ,-1 , 0
  2544.2      .1       0  2578.7     .16       0  3211.3     .05       0
  3988.8      .1       0  4218.6     .05       0  5017.4     .03       0
  5023.4     .05       0  5031.2     .16       0  5033.9     .05       0
  5284.9      .1       0  5697.9     .05       0
Bank Sta=4980.4,5031.2
XS Rating Curve= 0 ,0
Exp/Cntr=0.3,0.1

Type RM Length L Ch R = 1 ,63145   ,1207,1207,1207
BEGIN DESCRIPTION:
BIG CREEK 40.0
END DESCRIPTION:
XS GIS Cut Line= 3
      3548200.37     10547094.91      3546420.86     10547715.57
      3545237.45     10548586.87
#Sta/Elev= 30
  2918.9  419.75  3298.3  412.71    3503  405.89  3746.2   405.9    3772  407.85
  3796.1  404.75  3808.4  401.06  3839.4  397.82  3912.6  395.73  3984.2  395.94
  4020.5  399.89  4108.5  402.48  4346.4  398.31  4538.1  400.57    4626  394.79
  4728.1  384.23  4939.4  384.66  4957.2  384.04  4997.7  379.66  5000.4  379.16
  5003.7  379.66  5078.3  384.53    5360  384.57  5529.5  394.67  5600.5   396.4
  5679.9   394.1  5780.2  396.66  6030.9   406.4  6208.3  416.42  6273.1  417.58
#Mann= 5 ,-1 , 0
  2918.9     .05       0  4939.4     .16       0  4997.7     .07       0
  5003.7     .16       0    5360     .05       0
#XS Ineff= 2 , 0
         4139.99  402.49
Permanent Ineff=
       F       F
Bank Sta=4957.2,5078.3
XS Rating Curve= 0 ,0
Exp/Cntr=0.3,0.1

Type RM Length L Ch R = 1 ,61938   ,1109,1109,1109
BEGIN DESCRIPTION:
BIG CREEK 38.0
END DESCRIPTION:
XS GIS Cut Line= 4
      3546759.38     10545675.68      3546044.22     10546687.41
       3545778.5     10547116.61      3545046.07     10548143.75
#Sta/Elev= 30
  3659.4  417.98  3671.3  417.68  3830.6  414.28  3852.7  413.65  3947.5  412.19
  4034.2  410.84  4181.3   408.2  4397.1  405.08  4464.5  401.95  4765.6  399.92
  4938.6  393.89  4953.1  392.45  4962.2  388.25  4968.5   382.7  4974.3  380.43
  4986.7   379.6  4989.5   379.1  4992.7   379.6  5020.5  383.55  5108.4  383.56
  5236.7  386.47  5578.6  384.63  5771.2  384.54  5971.1  386.51  6042.4  390.33
  6128.4  392.45  6379.6  393.08  6502.1  400.72  6579.5  407.56  6664.7  409.57
#Mann= 14 ,-1 , 0
  3659.4      .1       0  3671.3     .16       0  3830.6      .1       0
  3852.7     .12       0  3947.5     .16       0  4034.2     .12       0
  4181.3     .16       0  4397.1      .1       0  4765.6     .12       0
  4986.7     .07       0  4992.7     .12       0  5108.4     .05       0
  5578.6     .16       0  5771.2     .05       0
Bank Sta=4962.2,5020.5
XS Rating Curve= 0 ,0
Exp/Cntr=0.3,0.1

Type RM Length L Ch R = 1 ,60829   ,711,711,711
BEGIN DESCRIPTION:
BIG CREEK 37.0
END DESCRIPTION:
XS GIS Cut Line= 4
       3546611.8     10545558.46      3545518.08     10545936.06
       3544819.3     10546300.64      3543169.99     10547311.93
#Sta/Elev= 30
  3738.4  417.34  3825.5   416.2  3928.5  415.26  4127.7  408.77  4286.7  396.93
  4403.1   388.2    4483  385.49    4669  383.32  4748.8  384.52  4854.9  385.31
  4965.7  385.09  4969.9  384.55    4985  380.63  5004.1  379.78  5006.8  379.28
  5010.1  379.78  5029.2  382.66  5118.7  383.55  5307.4  383.77  5698.4  383.12
  5929.4  383.36  6123.1   387.7  6268.1  394.19  6481.7  401.21  6598.6  409.01
  6823.9  419.27  7034.7  422.72    7493  436.01  7514.3  434.75  7618.3  439.86
#Mann= 16 ,-1 , 0
  3738.4     .16       0  3825.5     .12       0  4286.7     .16       0
    4483     .12       0  4748.8      .1       0  4854.9     .05       0
  4965.7     .16       0  5004.1     .07       0  5010.1     .16       0
  5118.7     .05       0  5307.4      .1       0  5698.4     .12       0
  5929.4     .16       0  6123.1     .12       0  6268.1     .16       0
  6598.6     .05       0
Bank Sta=4969.9,5029.2
XS Rating Curve= 0 ,0
Exp/Cntr=0.3,0.1

Type RM Length L Ch R = 1 ,60118   ,2038,2038,2038
BEGIN DESCRIPTION:
BIG CREEK 36.0
END DESCRIPTION:
XS GIS Cut Line= 3
       3546412.2     10545484.67       3545196.9     10545419.56
      3543083.18     10545988.14
#Sta/Elev= 30
  3571.1  416.29  3761.5  410.35  3937.9  395.08  4011.8  389.99  4088.2  386.57
  4172.1  382.72  4372.9  382.46  4606.6  382.99  4917.4  384.87  4971.9  382.83
  4989.9  379.68  5028.3  378.65    5031  378.15  5034.3  378.65    5052  383.61
  5090.8  383.87  5161.3  384.78    5373   383.7  5390.7  382.68  5562.7  382.71
  5896.4  382.82  6025.4     385  6118.6  388.52  6338.3  400.09  6490.3  410.61
  6522.5  413.14  6548.1  413.59  6605.3  419.09  6724.6  422.51    6977  428.09
#Mann= 13 ,-1 , 0
  3571.1     .12       0  3937.9     .16       0  4088.2     .12       0
  4372.9     .05       0  4606.6     .12       0  5028.3     .07       0
  5034.3     .12       0  5090.8     .16       0  5562.7     .12       0
  5896.4     .16       0  6338.3     .05       0  6490.3     .16       0
  6724.6     .05       0
Bank Sta=4971.9,5052
XS Rating Curve= 0 ,0
Exp/Cntr=0.3,0.1

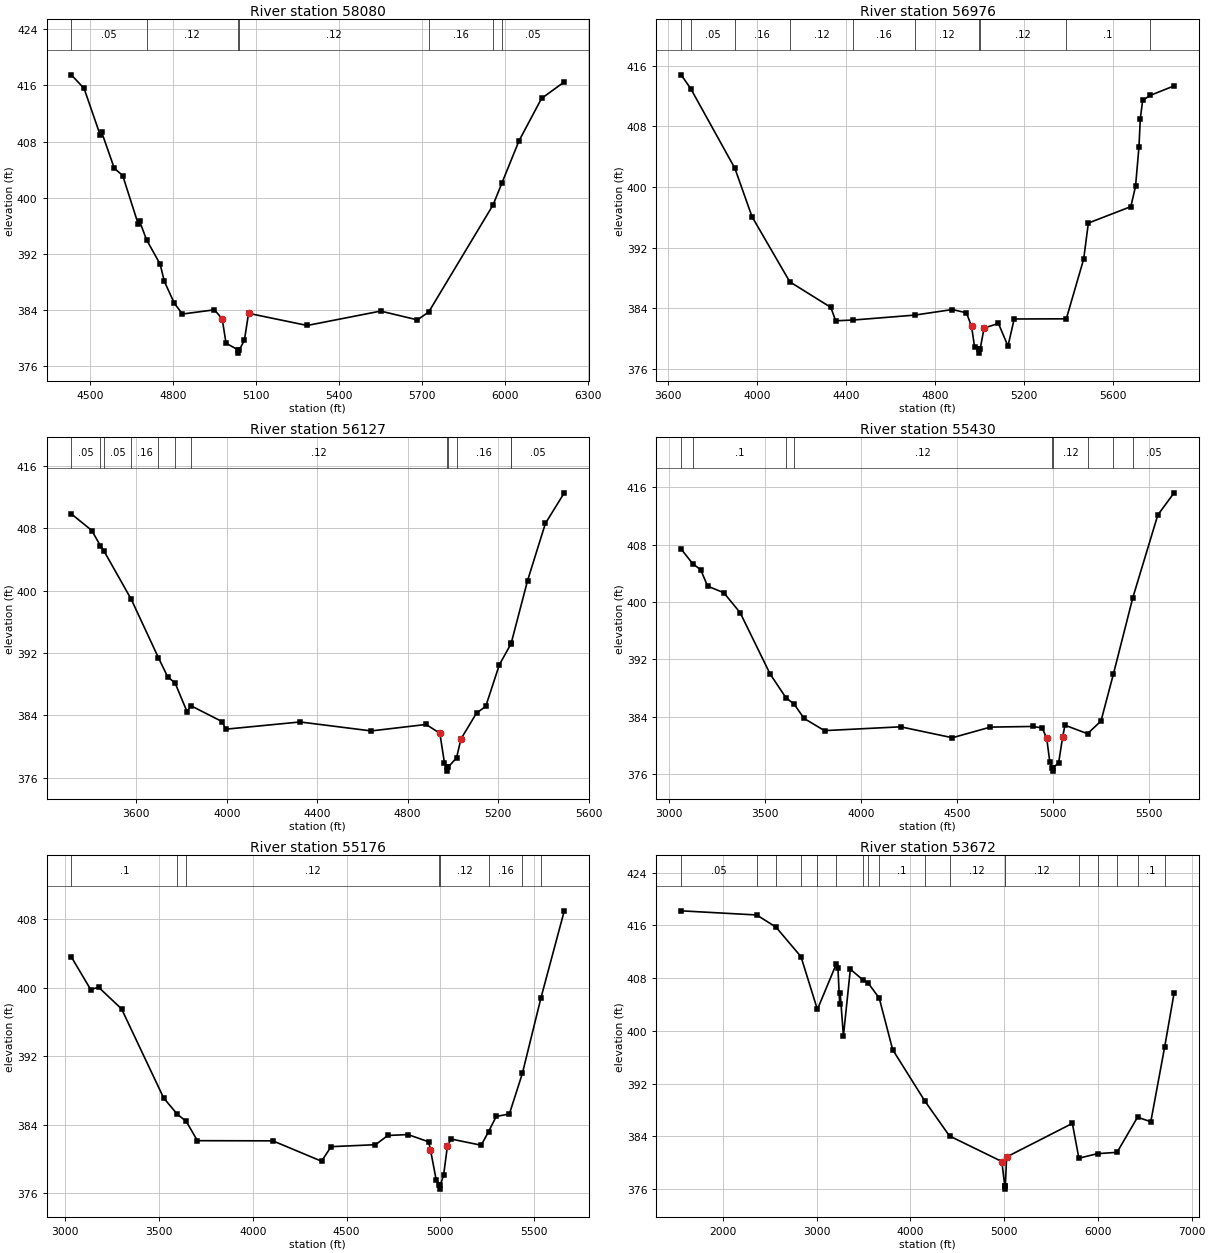
Type RM Length L Ch R = 1 ,58080   ,1104,1104,1104
BEGIN DESCRIPTION:
BIG CREEK 33.0
END DESCRIPTION:
XS GIS Cut Line= 4
      3546455.57     10544343.17      3546143.08     10544295.43
      3545774.16     10544538.49      3544771.55     10544338.83
#Sta/Elev= 30
  4433.1  417.52  4479.2  415.58  4537.6  408.92  4542.7  409.35  4588.3  404.21
  4618.7  403.17  4674.7  396.25  4679.7  396.66  4704.9  394.01  4753.9  390.54
    4769  388.09  4805.1  384.98  4834.2  383.44  4949.7  384.04  4977.9  382.76
  4991.8  379.28    5034  378.37  5036.8  377.87    5040  378.37  5058.1  379.69
  5073.2  383.54  5284.9  381.81    5550  383.86  5682.5  382.61  5723.6  383.72
  5956.2  398.99  5987.5  402.05  6049.6   408.1  6131.2  414.16  6213.3  416.51
#Mann= 7 ,-1 , 0
  4433.1     .05       0  4704.9     .12       0    5034     .07       0
    5040     .12       0  5723.6     .16       0  5956.2      .1       0
  5987.5     .05       0
Bank Sta=4977.9,5073.2
XS Rating Curve= 0 ,0
Exp/Cntr=0.3,0.1

Type RM Length L Ch R = 1 ,56976   ,849,849,849
BEGIN DESCRIPTION:
BIG CREEK 31.2
END DESCRIPTION:
XS GIS Cut Line= 4
      3546511.75     10544169.59      3545634.98     10543457.76
      3545187.93     10543791.96      3544688.82      10543969.9
#Sta/Elev= 30
  3658.5  414.82    3702  412.98  3900.4  402.46  3977.1   396.1  4147.2  387.48
  4331.9   384.1  4353.6  382.33  4432.2  382.43  4708.9  383.08  4878.8  383.82
  4941.9  383.38  4964.9  381.58  4978.7  378.82  4997.3  378.56    5000  378.06
  5003.3  378.56  5021.1  381.37  5085.7  381.98  5128.6  378.99  5156.6  382.57
    5391  382.59    5469  390.47  5490.2  395.24  5681.3  397.41  5702.5  400.11
  5717.9  405.31  5723.8  409.02  5734.4  411.45  5768.3   412.1  5875.9  413.36
#Mann= 10 ,-1 , 0
  3658.5     .16       0    3702     .05       0  3900.4     .16       0
  4147.2     .12       0  4432.2     .16       0  4708.9     .12       0
  4997.3     .07       0  5003.3     .12       0    5391      .1       0
  5768.3     .05       0
Bank Sta=4964.9,5021.1
XS Rating Curve= 0 ,0
Exp/Cntr=0.3,0.1

Type RM Length L Ch R = 1 ,56127   ,697,697,697
BEGIN DESCRIPTION:
BIG CREEK 31.0
END DESCRIPTION:
XS GIS Cut Line= 3
      3546546.47     10543913.51      3545457.03     10543097.51
      3544649.74     10542958.63
#Sta/Elev= 30
  3312.4  409.87  3403.2  407.73  3441.4  405.75  3457.4  405.07  3577.4  398.91
  3697.4  391.42  3738.6  388.95  3771.4  388.16  3824.1  384.49  3841.7  385.24
  3980.3  383.19  3994.9  382.23  4324.2  383.16  4638.8  382.01  4881.5  382.84
  4942.4  381.71  4962.7   377.9  4972.7  377.35  4975.5  376.85  4978.7  377.35
  5016.2  378.56  5035.7  380.98  5104.7  384.31  5145.3  385.16  5205.3  390.49
  5257.3  393.21  5258.2   393.3  5330.2   401.3  5409.1  408.64  5492.7  412.57
#Mann= 12 ,-1 , 0
  3312.4     .05       0  3441.4      .1       0  3457.4     .05       0
  3577.4     .16       0  3697.4     .12       0  3771.4     .16       0
  3841.7     .12       0  4972.7     .07       0  4978.7     .12       0
  5016.2     .16       0  5257.3      .1       0  5258.2     .05       0
Bank Sta=4942.4,5035.7
XS Rating Curve= 0 ,0
Exp/Cntr=0.3,0.1

Type RM Length L Ch R = 1 ,55430   ,254,254,254
BEGIN DESCRIPTION:
BIG CREEK 31.3
END DESCRIPTION:
XS GIS Cut Line= 3
      3546620.03     10543798.11      3545415.23      10542421.2
      3544701.79     10542225.11
#Sta/Elev= 30
  3063.4  407.37  3123.4  405.34  3165.3  404.49  3201.4  402.21  3285.8  401.29
    3371  398.51  3526.9  389.99  3610.3  386.64  3651.6  385.81  3704.4  383.78
  3810.7  382.09  4207.4  382.62    4477   381.1  4675.4  382.58  4897.2  382.67
  4945.4  382.46  4968.8  381.04    4985  377.73  4996.9  376.95  4999.7  376.45
  5002.9  376.95  5031.1   377.6  5051.8   381.2  5064.2  382.84  5181.7  381.66
  5251.9  383.43  5316.4  389.96  5417.8  400.61    5548  412.12  5632.9   415.2
#Mann= 9 ,-1 , 0
  3063.4     .05       0  3123.4      .1       0  3610.3     .16       0
  3651.6     .12       0  4996.9     .07       0  5002.9     .12       0
  5181.7     .16       0  5316.4      .1       0  5417.8     .05       0
Bank Sta=4968.8,5051.8
XS Rating Curve= 0 ,0
Exp/Cntr=0.3,0.1

Type RM Length L Ch R = 1 ,55176   ,1504,1504,1504
BEGIN DESCRIPTION:
BIG CREEK 31.1
END DESCRIPTION:
XS GIS Cut Line= 3
      3546615.88     10543700.81      3545591.18     10542189.87
      3544789.79     10542146.55
#Sta/Elev= 30
  3032.6  403.59  3135.8  399.77  3177.8  400.05  3300.6  397.51  3525.1   387.1
    3598   385.2  3645.2  384.38  3704.8  382.12    4107   382.1  4366.7  379.72
  4417.6  381.42  4654.2  381.65  4720.1  382.73  4827.9  382.83  4937.4  381.99
  4947.4  381.05  4977.5  377.58  4994.5  376.96  4997.3  376.46  5000.5  376.96
  5017.5  378.12  5037.6  381.46  5057.6  382.31  5217.8  381.59  5256.8  383.17
    5298  384.95  5368.1  385.24  5437.3  389.98  5536.2  398.78  5660.8  408.97
#Mann= 8 ,-1 , 0
  3032.6      .1       0    3598     .16       0  3645.2     .12       0
  4994.5     .07       0  5000.5     .12       0  5256.8     .16       0
  5437.3      .1       0  5536.2     .05       0
Bank Sta=4947.4,5037.6
XS Rating Curve= 0 ,0
Exp/Cntr=0.3,0.1

Type RM Length L Ch R = 1 ,53672   ,742,742,742
BEGIN DESCRIPTION:
BIG CREEK 30.0
END DESCRIPTION:
XS GIS Cut Line= 6
       3547253.8     10545725.48      3546728.83     10543805.04
      3546327.24     10542887.07      3546183.47     10542302.15
      3545986.55     10541873.56      3544818.56     10542111.76
#Sta/Elev= 30
  1553.9  418.21  2360.3  417.58  2564.8  415.75  2832.4  411.26  3007.4  403.25
    3207  410.07    3227  409.48  3245.2  404.06  3250.4   405.8  3284.9  399.22
  3359.1  409.35  3491.2  407.76  3546.9   407.3  3667.3  404.97  3810.5  397.15
  4153.9  389.36    4417  384.06  4974.6  380.19  5006.4   376.5  5009.1     376
  5012.4   376.5  5026.1  380.88  5727.4  385.97    5797  380.69  5995.8  381.38
  6203.9  381.58  6422.9  386.91  6564.2  386.22  6712.7  397.61  6812.8  405.76
#Mann= 18 ,-1 , 0
  1553.9     .05       0  2360.3     .16       0  2564.8     .12       0
  2832.4      .1       0  3007.4     .16       0    3207     .05       0
  3491.2     .16       0  3546.9     .05       0  3667.3      .1       0
  4153.9     .16       0    4417     .12       0  5006.4     .07       0
  5012.4     .12       0    5797     .16       0  5995.8     .12       0
  6203.9     .16       0  6422.9      .1       0  6712.7     .05       0
Bank Sta=4974.6,5026.1
XS Rating Curve= 0 ,0
Exp/Cntr=0.3,0.1