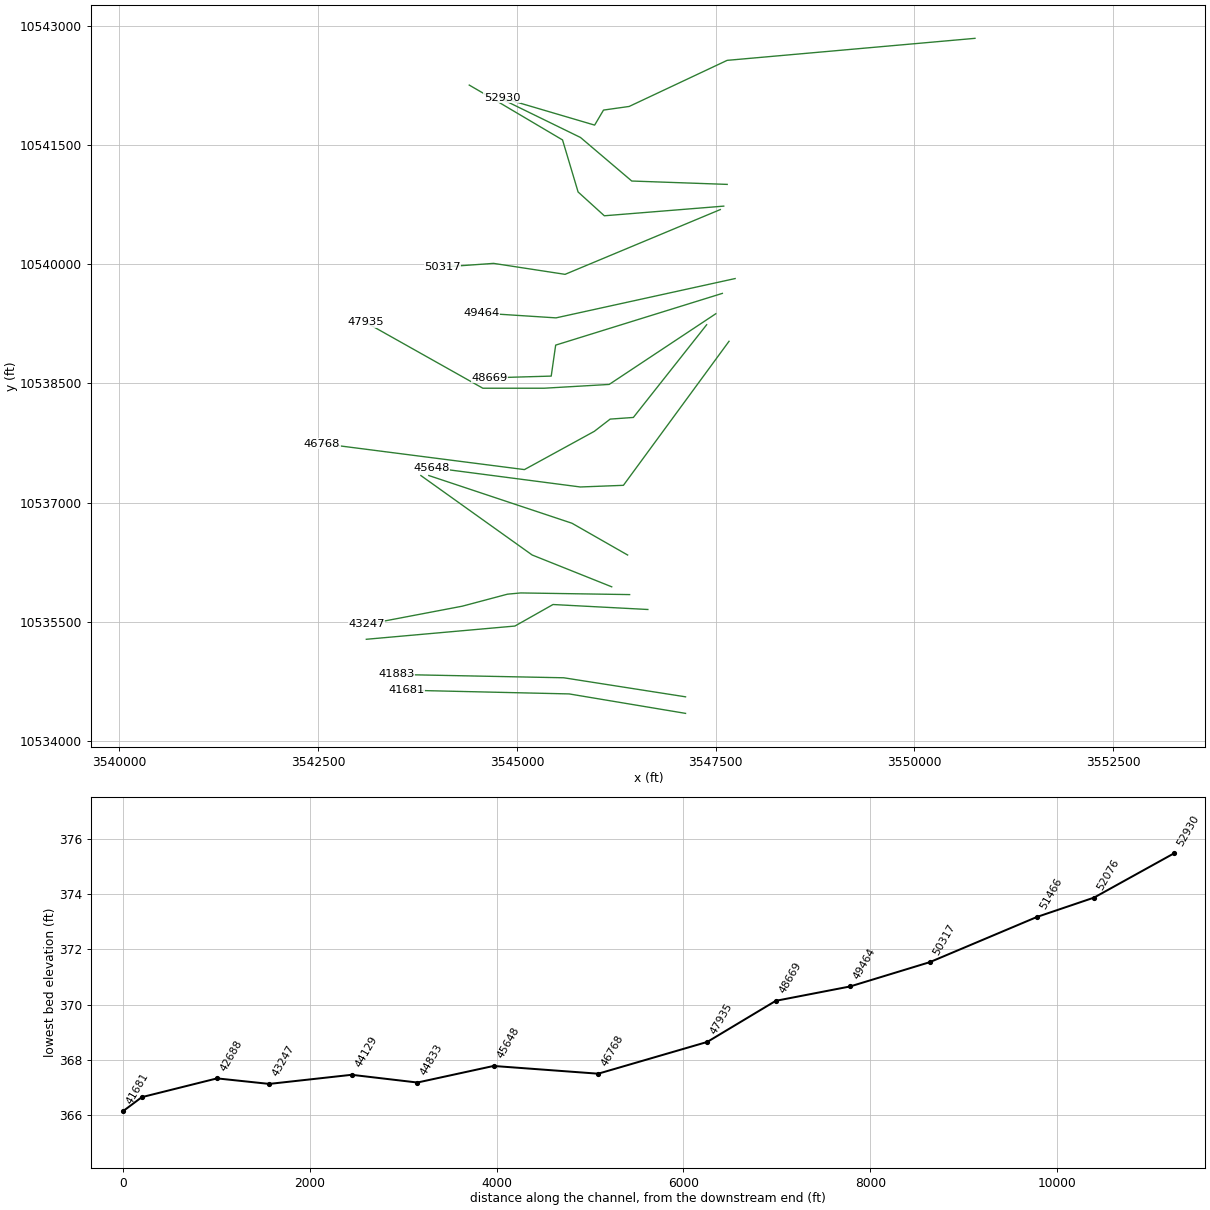
HEC-RAS study BIGELMCREEK.prj: BIG ELM CREEK Base Level Engineering

--- BIGELMCREEK.g01 (geometry) --- (continued)

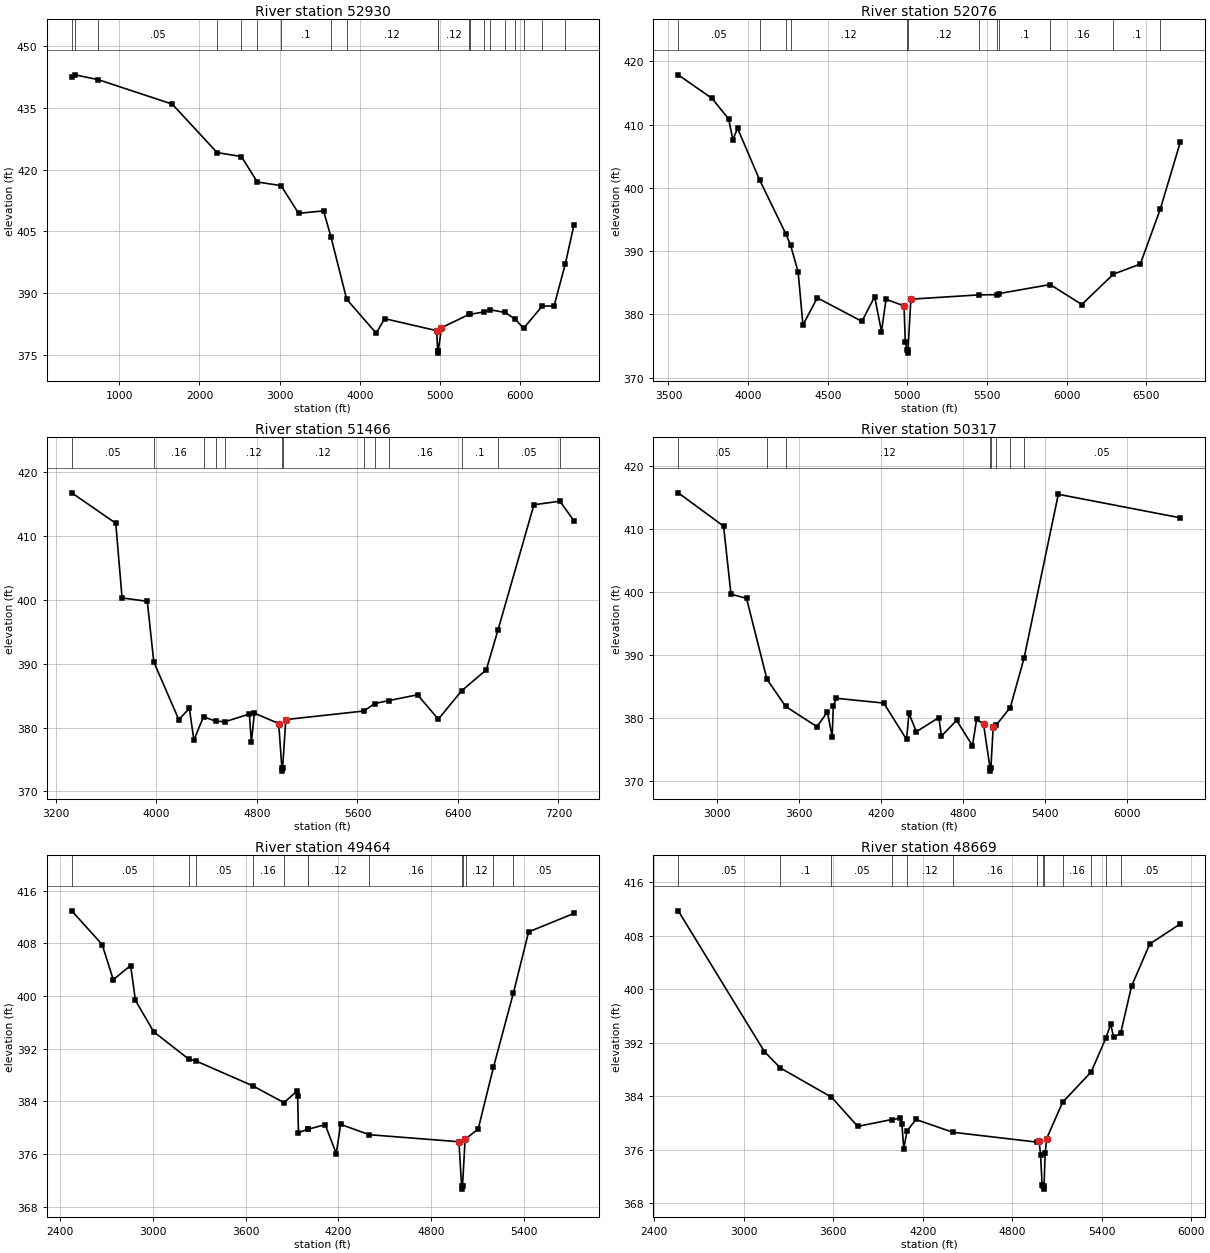
Type RM Length L Ch R = 1 ,52930   ,854,854,854
BEGIN DESCRIPTION:
BIG CREEK 29.2
END DESCRIPTION:
XS GIS Cut Line= 6
      3550760.76      10542843.5      3547643.79     10542566.34
      3546411.89      10541986.4      3546089.03     10541940.73
      3545977.46     10541751.51      3544815.66     10542093.98
#Sta/Elev= 30
     407  442.48   446.4  442.97   735.5  441.81  1660.6  435.87  2219.8  424.12
  2523.9  423.15  2721.8  416.98  3018.6   416.1  3236.8  409.39  3548.9  409.97
  3640.9  403.68    3837  388.54  4205.5  380.32  4311.3  383.84  4959.4  380.93
  4973.7  375.98  4976.4  375.48  4979.7  375.98    5020  381.65    5366  384.88
    5370  384.87  5553.3  385.47  5626.4     386  5813.1  385.34  5939.4  383.76
  6043.7  381.49  6276.7  386.87  6425.2  386.94  6565.2  397.12  6671.7  406.45
#Mann= 20 ,-1 , 0
     407     .08       0   446.4      .1       0   735.5     .05       0
  2219.8      .1       0  2523.9     .05       0  2721.8     .16       0
  3018.6      .1       0  3640.9     .05       0    3837     .12       0
  4973.7     .07       0  4979.7     .12       0    5366     .16       0
    5370     .12       0  5553.3     .16       0  5626.4      .1       0
  5813.1     .16       0  5939.4     .12       0  6043.7     .16       0
  6276.7      .1       0  6565.2     .05       0
Bank Sta=4959.4,5020
XS Rating Curve= 0 ,0
Exp/Cntr=0.3,0.1

Type RM Length L Ch R = 1 ,52076   ,610,610,610
BEGIN DESCRIPTION:
BIG CREEK 29.3
END DESCRIPTION:
XS GIS Cut Line= 4
      3547644.58      10541005.5       3546444.4     10541047.88
      3545799.91     10541595.78      3544806.39     10542080.98
#Sta/Elev= 30
  3561.4  417.87    3774  414.13  3878.1  410.88  3904.1  407.63  3934.1  409.41
  4071.9  401.28  4238.7  392.64    4267  390.92  4314.3  386.71  4344.4  378.32
  4434.4  382.62  4714.6   378.9  4794.7   382.8  4837.6  377.29  4866.1   382.4
  4979.2  381.34    4987  375.65  4998.2  374.38    5001  373.88  5004.2  374.38
  5022.1  382.41  5450.3  383.09  5564.5  383.12  5572.4  383.28    5897  384.72
  6095.5  381.56  6293.3  386.36  6462.7  387.96  6588.3  396.65  6713.9  407.25
#Mann= 12 ,-1 , 0
  3561.4     .05       0  4071.9     .12       0  4238.7     .16       0
    4267     .12       0  4998.2     .07       0  5004.2     .12       0
  5450.3     .16       0  5564.5     .12       0  5572.4      .1       0
    5897     .16       0  6293.3      .1       0  6588.3     .05       0
Bank Sta=4979.2,5022.1
XS Rating Curve= 0 ,0
Exp/Cntr=0.3,0.1

Type RM Length L Ch R = 1 ,51466   ,1149,1149,1149
BEGIN DESCRIPTION:
BIG CREEK 28.3
END DESCRIPTION:
XS GIS Cut Line= 6
      3547601.17     10540732.07      3546099.39     10540610.54
      3545769.53     10540910.01      3545573.82     10541564.87
      3544744.82     10542055.32      3544400.54      10542255.2
#Sta/Elev= 30
  3325.8  416.74    3676  411.98  3726.2  400.29  3926.8  399.76  3978.9  390.26
  4177.6  381.25  4261.9     383    4298  378.05  4374.5  381.68  4473.3  380.99
  4546.5  380.92  4739.5  382.11  4755.7  377.72  4779.6  382.26  4973.1  380.63
  4998.4  373.68  5001.2  373.18  5004.4  373.68  5029.8  381.25  5651.4  382.59
  5736.6  383.75  5849.4  384.22  6078.3  385.13    6244  381.31  6429.3  385.75
  6625.8  389.03  6718.5  395.24    7005  414.87  7211.2  415.43  7322.8  412.39
#Mann= 13 ,-1 , 0
  3325.8     .05       0  3978.9     .16       0  4374.5     .12       0
  4473.3     .16       0  4546.5     .12       0  4998.4     .07       0
  5004.4     .12       0  5651.4     .16       0  5736.6      .1       0
  5849.4     .16       0  6429.3      .1       0  6718.5     .05       0
  7211.2     .16       0
Bank Sta=4973.1,5029.8
XS Rating Curve= 0 ,0
Exp/Cntr=0.3,0.1

Type RM Length L Ch R = 1 ,50317   ,853,853,853
BEGIN DESCRIPTION:
BIG CREEK 29.1
END DESCRIPTION:
XS GIS Cut Line= 4
      3547557.71     10540688.65      3545605.56     10539873.59
      3544706.16     10540011.58       3544065.4     10539965.52
#Sta/Elev= 30
  2719.7  415.75  3050.9  410.46  3105.1  399.64  3218.4     399  3367.7  386.14
  3504.5  381.81  3732.7   378.6  3809.4  380.93  3844.2  376.99  3852.8   381.9
  3874.5  383.11  4221.2  382.35  4387.6  376.57  4405.4  380.72    4459   377.8
  4623.6  380.05    4642   377.1  4753.5   379.6    4869  375.58  4899.4  379.75
  4949.9  379.02  4997.5  372.04  5000.3  371.54  5003.5  372.04  5020.8  378.57
  5044.6  378.92  5145.2  381.64  5245.9  389.48  5496.3  415.52  6387.5  411.78
#Mann= 8 ,-1 , 0
  2719.7     .05       0  3367.7     .16       0  3504.5     .12       0
  4997.5     .07       0  5003.5     .12       0  5044.6     .16       0
  5145.2      .1       0  5245.9     .05       0
Bank Sta=4949.9,5020.8
XS Rating Curve= 0 ,0
Exp/Cntr=0.3,0.1

Type RM Length L Ch R = 1 ,49464   ,795,795,795
BEGIN DESCRIPTION:
BIG CREEK 28.2
END DESCRIPTION:
XS GIS Cut Line= 3
      3547744.33      10539820.6      3545491.75     10539325.81
      3544549.89     10539386.58
#Sta/Elev= 30
  2474.5  412.95  2671.3  407.82    2743  402.49  2855.6  404.64  2886.3  399.36
  3004.9  394.57  3232.4   390.4  3277.1  390.15  3645.1  386.37  3848.4   383.8
  3930.6  385.53  3936.8  384.81  3941.9  379.22  4004.1  379.81  4005.9  379.78
  4114.9  380.45  4186.6  376.07  4214.9   380.5  4400.4  378.93  4980.8  377.86
  4997.9  371.16  5000.6  370.66  5003.9  371.16  5020.9  378.26  5024.5  378.32
  5105.2  379.78    5204  389.16  5332.8  400.42  5431.8  409.75  5724.6  412.55
#Mann= 13 ,-1 , 0
  2474.5     .05       0  3232.4      .1       0  3277.1     .05       0
  3645.1     .16       0  3848.4     .12       0  4004.1     .16       0
  4005.9     .12       0  4400.4     .16       0  4997.9     .07       0
  5003.9     .16       0  5024.5     .12       0    5204     .16       0
  5332.8     .05       0
Bank Sta=4980.8,5020.9
XS Rating Curve= 0 ,0
Exp/Cntr=0.3,0.1

Type RM Length L Ch R = 1 ,48669   ,734,734,734
BEGIN DESCRIPTION:
BIG CREEK 27.3
END DESCRIPTION:
XS GIS Cut Line= 4
      3547583.73     10539633.96      3545487.41     10538982.93
      3545431.46     10538593.11      3544655.59     10538570.65
#Sta/Elev= 30
  2560.4  411.74    3138   390.7  3244.9  388.25  3587.5  383.89  3763.1  379.52
  3991.3  380.54    4049  380.74  4059.5  379.89  4071.9  376.13  4093.6  378.83
  4153.7  380.55  4400.5  378.64  4963.9  377.17    4979   377.3  4989.1  375.31
  4999.2  370.72  5006.3  370.64  5009.1  370.14  5012.3  370.64  5019.5  375.48
  5029.6   377.7  5136.6  383.12    5328  387.66  5426.8  392.73  5458.8  394.81
  5478.8  392.82  5525.6  393.44  5598.8  400.49  5721.1  406.79  5925.5  409.79
#Mann= 13 ,-1 , 0
  2560.4     .05       0  3244.9      .1       0  3587.5     .05       0
  3991.3     .16       0  4093.6     .12       0  4400.5     .16       0
  4963.9     .12       0  5006.3     .07       0  5012.3     .12       0
  5136.6     .16       0    5328     .12       0  5426.8     .16       0
  5525.6     .05       0
Bank Sta=4979,5029.6
XS Rating Curve= 0 ,0
Exp/Cntr=0.3,0.1

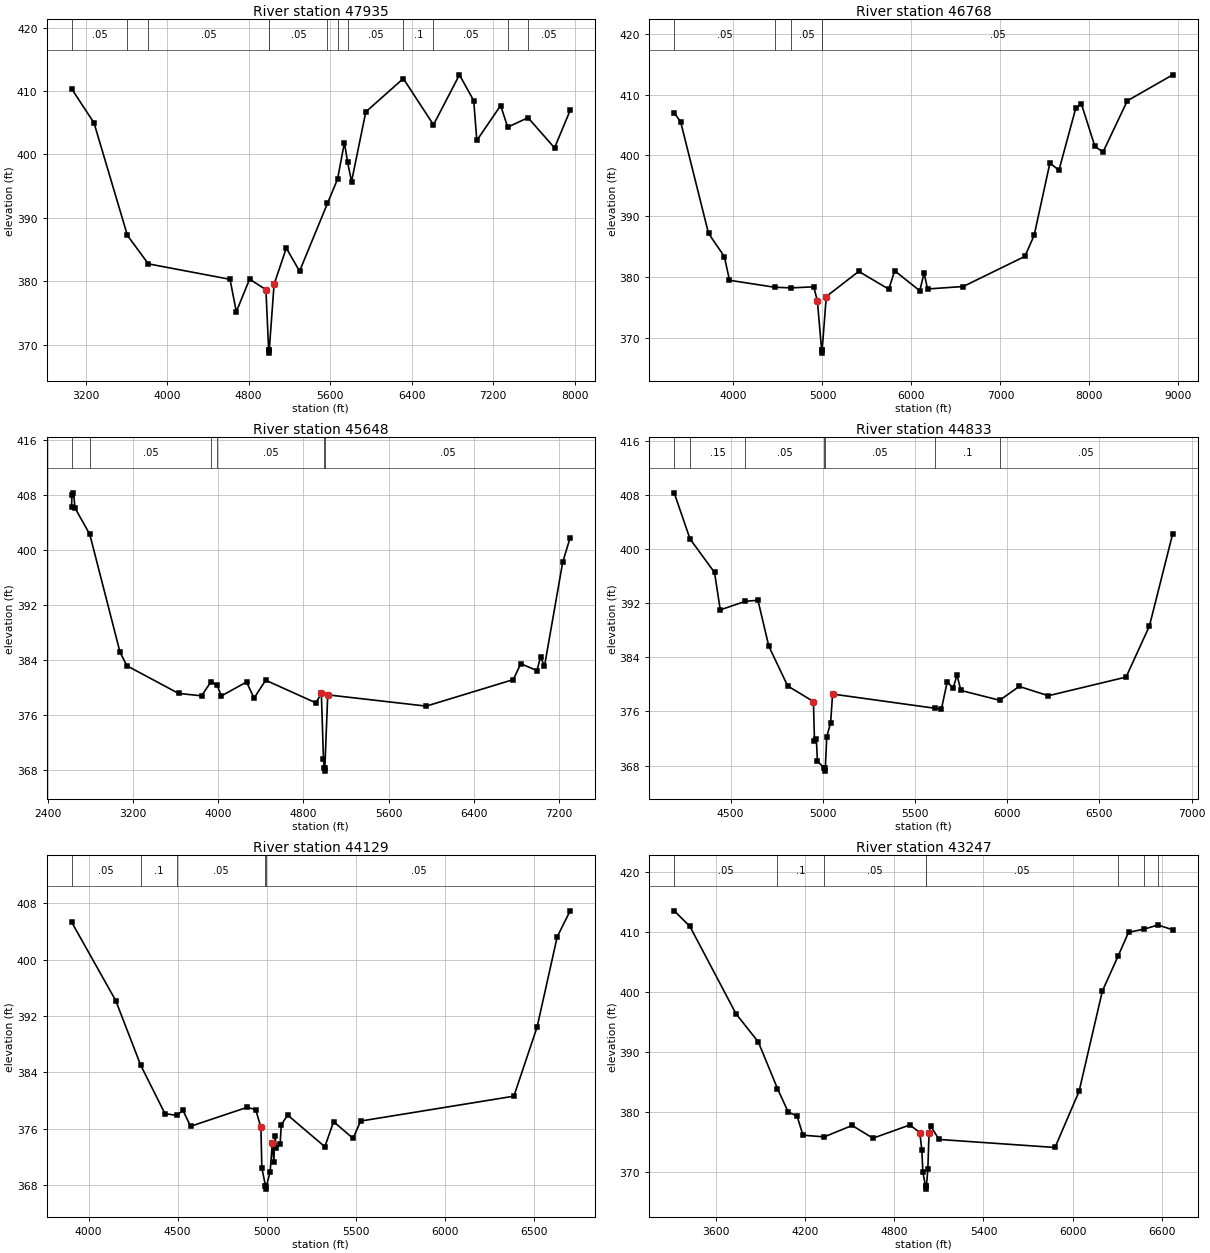
Type RM Length L Ch R = 1 ,47935   ,1167,1167,1167
BEGIN DESCRIPTION:
BIG CREEK 29.0
END DESCRIPTION:
XS GIS Cut Line= 5
      3547501.28     10539377.88      3546160.16     10538488.14
      3545339.84      10538440.4      3544571.61      10538440.4
      3543093.39      10539271.7
#Sta/Elev= 30
  3061.5  410.35  3281.7  404.95  3609.8  387.21  3814.5  382.73    4617  380.29
    4679  375.18  4809.2  380.32  4969.5  378.66  4996.5  369.15  4999.3  368.65
  5002.5  369.15  5049.6   379.5  5169.8  385.21    5300  381.57  5573.8  392.26
  5672.7  396.08  5740.4  401.85  5771.6  398.75  5810.4  395.71  5950.4   406.7
  6318.6  411.95    6615  404.66  6869.7  412.54  7009.9  408.47  7040.4  402.19
  7274.4   407.7  7343.5  404.29  7543.2  405.78  7803.5  401.02  7956.8  406.93
#Mann= 12 ,-1 , 0
  3061.5     .05       0  3609.8      .1       0  3814.5     .05       0
  4996.5     .03       0  5002.5     .05       0  5573.8     .16       0
  5672.7     .12       0  5771.6     .05       0  6318.6      .1       0
    6615     .05       0  7343.5      .1       0  7543.2     .05       0
Bank Sta=4969.5,5049.6
XS Rating Curve= 0 ,0
Exp/Cntr=0.3,0.1

Type RM Length L Ch R = 1 ,46768   ,1120,1120,1120
BEGIN DESCRIPTION:
BIG CREEK 28.1
END DESCRIPTION:
XS GIS Cut Line= 6
      3547386.27     10539239.42      3546464.41     10538072.78
      3546172.74     10538051.94      3545973.36     10537897.89
      3545094.62     10537416.53      3542546.81      10537743.9
#Sta/Elev= 30
  3333.9  407.03  3407.2  405.49  3719.7  387.19  3897.7  383.38  3955.4  379.48
  4463.9  378.33  4650.5  378.23  4902.6   378.4  4943.4  376.04  4990.6     368
  4993.3   367.5  4996.6     368    5043  376.81    5408  380.94  5745.5  378.01
  5811.3  381.04  6093.5  377.76  6142.8  380.67  6180.7  378.05  6580.9  378.45
  7275.1  383.41  7378.8  386.87    7556  398.75  7657.6  397.57  7846.7  407.78
  7910.2  408.46  8061.8  401.48  8152.8  400.56  8425.6  408.99  8936.3  413.26
#Mann= 5 ,-1 , 0
  3333.9     .05       0  4463.9      .1       0  4650.5     .05       0
  4990.6     .03       0  4996.6     .05       0
Bank Sta=4943.4,5043
XS Rating Curve= 0 ,0
Exp/Cntr=0.3,0.1

Type RM Length L Ch R = 1 ,45648   ,815,815,815
BEGIN DESCRIPTION:
BIG CREEK 27.2
END DESCRIPTION:
XS GIS Cut Line= 4
      3547667.52     10539031.09      3546339.41     10537218.61
      3545797.74     10537197.78      3543922.71     10537442.57
#Sta/Elev= 30
    2625  406.28  2628.1  408.03  2642.8  408.28  2657.4  406.06  2795.7  402.24
  3079.7  385.08  3144.5  383.11  3629.3  379.09  3844.6  378.74  3932.3  380.75
  3989.5  380.34  4030.7  378.72  4266.9  380.75  4337.9  378.41  4446.7  381.01
  4918.7  377.71  4969.4   379.1  4989.4  369.56  4996.4  368.28  4999.1  367.78
  5002.4  368.28  5029.4  378.88  5954.2  377.24  6771.1   381.1  6841.7  383.42
    6993  382.41  7027.9  384.42  7063.6  383.01    7235  398.17    7305  401.74
#Mann= 6 ,-1 , 0
    2625     .08       0  2795.7     .05       0  3932.3      .1       0
  3989.5     .05       0  4996.4     .03       0  5002.4     .05       0
Bank Sta=4969.4,5029.4
XS Rating Curve= 0 ,0
Exp/Cntr=0.3,0.1

Type RM Length L Ch R = 1 ,44833   ,704,704,704
BEGIN DESCRIPTION:
BIG CREEK 28.0
END DESCRIPTION:
XS GIS Cut Line= 3
      3546392.12     10536341.63      3545692.11     10536741.64
      3543892.11     10537341.64
#Sta/Elev= 30
  4193.8  408.34  4279.6  401.52  4412.6  396.56  4443.6  391.03  4579.4  392.29
    4648  392.45  4707.1  385.64  4809.3  379.78  4948.9  377.47  4954.7  371.59
  4964.8  371.98  4970.5  368.62  5007.6  367.68  5010.3  367.18  5013.6  367.68
  5021.1  372.25  5042.2  374.34  5052.7  378.58  5607.5  376.48    5643  376.36
  5674.7  380.42  5706.3  379.41  5727.4   381.4  5748.4  379.11  5959.3  377.66
  6064.7  379.71  6222.8  378.33  6644.4  381.09  6770.9  388.64  6897.4  402.32
#Mann= 7 ,-1 , 0
  4193.8     .05       0  4279.6     .15       0  4579.4     .05       0
  5007.6     .03       0  5013.6     .05       0  5607.5      .1       0
  5959.3     .05       0
Bank Sta=4948.9,5052.7
XS Rating Curve= 0 ,0
Exp/Cntr=0.3,0.1

Type RM Length L Ch R = 1 ,44129   ,882,882,882
BEGIN DESCRIPTION:
BIG CREEK 27.0
END DESCRIPTION:
XS GIS Cut Line= 3
      3546192.11     10535941.64      3545192.11     10536341.64
      3543792.11     10537341.64
#Sta/Elev= 30
  3904.7  405.33  4152.4  394.19  4292.8  385.01  4428.4  378.17  4494.9  377.91
  4529.4  378.63  4572.5  376.37  4888.8  379.05  4937.3  378.75  4966.9  376.24
  4972.3  370.47  4992.3  367.96    4995  367.46  4998.3  367.96  5018.6  369.86
  5030.9  373.96  5039.5  371.32  5045.6  375.03  5054.2  373.31  5075.1  373.92
  5081.3  376.58  5116.9  377.96  5325.8  373.47    5375  377.03  5484.4  374.64
  5526.1  377.11  6386.4  380.64  6516.6  390.43  6629.7  403.24  6702.2  406.92
#Mann= 5 ,-1 , 0
  3904.7     .05       0  4292.8      .1       0  4494.9     .05       0
  4992.3     .03       0  4998.3     .05       0
Bank Sta=4966.9,5030.9
XS Rating Curve= 0 ,0
Exp/Cntr=0.3,0.1

Type RM Length L Ch R = 1 ,43247   ,559,559,559
BEGIN DESCRIPTION:
BIG CREEK 27.1
END DESCRIPTION:
XS GIS Cut Line= 5
      3546417.52     10535843.61      3545047.74     10535864.44
      3544881.08     10535848.82      3544313.37     10535697.78
      3543110.29     10535468.62
#Sta/Elev= 30
  3322.2  413.57  3427.6  410.98  3737.7  396.38  3887.7  391.68  4015.9  383.92
  4087.7  380.02  4147.7  379.32  4187.7  376.13    4330  375.85  4517.8  377.75
  4657.8  375.63    4906  377.84  4972.3  376.56  4986.2  373.63    4993  369.96
  5010.7  367.63  5013.4  367.13  5016.7  367.63  5026.4  370.45  5034.4   376.5
  5044.7  377.68  5101.5  375.42  5880.8  374.08  6042.4  383.44  6198.9  400.19
  6305.4  406.06  6374.6  409.98  6480.5  410.52  6572.4  411.21  6671.7   410.4
#Mann= 8 ,-1 , 0
  3322.2     .05       0  4015.9      .1       0    4330     .05       0
  5010.7     .03       0  5016.7     .05       0  6305.4     .08       0
  6480.5      .1       0  6572.4     .05       0
Bank Sta=4972.3,5034.4
XS Rating Curve= 0 ,0
Exp/Cntr=0.3,0.1

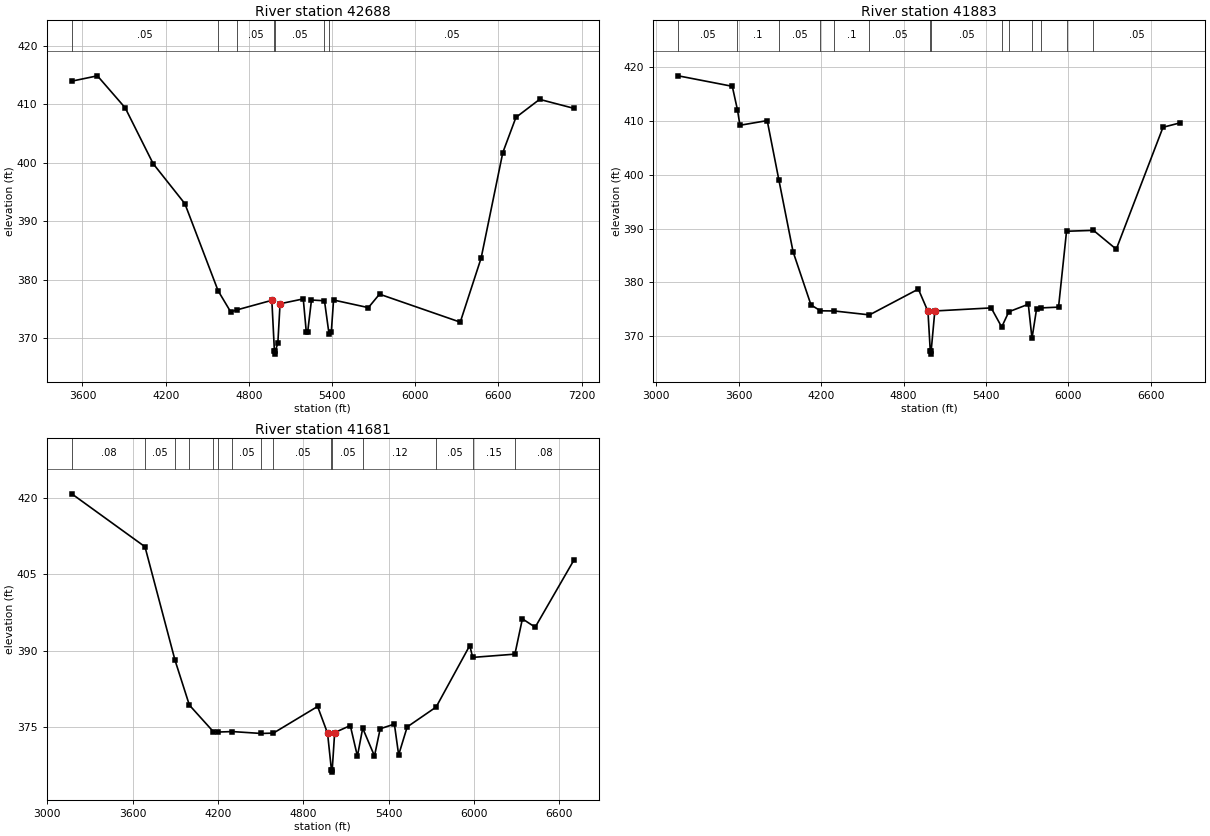
Type RM Length L Ch R = 1 ,42688   ,805,805,805
BEGIN DESCRIPTION:
BIG CREEK 26.0
END DESCRIPTION:
XS GIS Cut Line= 4
      3546646.71     10535656.11      3545453.99     10535718.61
      3544974.83     10535447.78       3543106.1      10535281.2
#Sta/Elev= 30
  3522.9  413.94  3707.8  414.85    3908  409.39  4109.8  399.85  4338.6  393.02
  4578.4  378.14  4669.1  374.54  4713.3  374.88  4965.8  376.52  4984.4  367.83
  4987.2  367.33  4990.4  367.83  5009.1  369.21    5025  375.93  5192.4  376.76
    5214  371.16  5224.2  371.11  5251.6  376.57  5345.4  376.44    5378  370.81
  5394.5  371.06  5410.9  376.57  5661.9  375.27  5742.3  377.57  6324.6  372.79
  6475.2  383.74  6631.4  401.74  6726.1  407.75  6896.8  410.83  7143.8   409.3
#Mann= 7 ,-1 , 0
  3522.9     .05       0  4578.4      .1       0  4713.3     .05       0
  4984.4     .03       0  4990.4     .05       0  5345.4     .12       0
    5378     .05       0
Bank Sta=4965.8,5025
XS Rating Curve= 0 ,0
Exp/Cntr=0.3,0.1

Type RM Length L Ch R = 1 ,41883   ,202,202,202
BEGIN DESCRIPTION:
BIG CREEK 25.0
END DESCRIPTION:
XS GIS Cut Line= 3
      3547120.65     10534557.15      3545589.41     10534796.73
      3543486.19     10534838.38
#Sta/Elev= 30
  3160.7  418.43    3554  416.48  3591.6   412.1  3609.9  409.23  3808.2   410.1
  3893.7  398.97  3996.3   385.7  4126.8   375.8  4195.8  374.71  4296.5  374.68
  4552.4  373.95  4907.9  378.75  4977.9  374.59  4994.9  367.15  4997.7  366.65
  5000.9  367.15  5027.9  374.68    5438  375.25  5514.5  371.69  5566.1  374.53
  5708.1  375.93  5734.9  369.58  5768.1  375.04  5799.7  375.25  5928.1  375.39
  5986.3  389.51  6182.2  389.68  6348.2  386.17  6688.3  408.86  6814.2  409.69
#Mann= 14 ,-1 , 0
  3160.7     .05       0  3591.6      .1       0  3893.7     .05       0
  4195.8     .16       0  4296.5      .1       0  4552.4     .05       0
  4994.9     .03       0  5000.9     .05       0  5514.5     .12       0
  5566.1     .05       0  5734.9     .12       0  5799.7     .05       0
  5986.3     .15       0  6182.2     .05       0
Bank Sta=4977.9,5027.9
XS Rating Curve= 0 ,0
Exp/Cntr=0.3,0.1

Type RM Length L Ch R = 1 ,41681   ,320,320,320
BEGIN DESCRIPTION:
BIG CREEK 24.0
END DESCRIPTION:
XS GIS Cut Line= 3
      3547120.69     10534348.81      3545657.12     10534593.61
      3543610.25     10534640.48
#Sta/Elev= 30
  3171.3  420.77  3686.2  410.38  3897.5   388.1  3998.4   379.3  4167.4  374.07
  4200.3  374.01  4301.2   374.1  4503.1  373.73  4589.4   373.8  4900.3  379.03
  4970.3  373.78  4997.3  366.64  5000.1  366.14  5003.3  366.64  5020.3   373.9
  5130.3  375.28  5180.3  369.27  5217.5  374.76  5300.4  369.31  5340.4  374.65
  5440.4  375.57  5470.4  369.52  5530.4  375.01  5734.1  378.92  5970.6  390.99
    5991  388.66    6288   389.3  6340.7  396.23  6430.7  394.59  6702.6  407.74
#Mann= 15 ,-1 , 0
  3171.3     .08       0  3686.2     .05       0  3897.5     .16       0
  3998.4     .08       0  4167.4     .16       0  4200.3      .1       0
  4301.2     .05       0  4503.1      .1       0  4589.4     .05       0
  4997.3     .03       0  5003.3     .05       0  5217.5     .12       0
  5734.1     .05       0    5991     .15       0    6288     .08       0
Bank Sta=4970.3,5020.3
XS Rating Curve= 0 ,0
Exp/Cntr=0.3,0.1