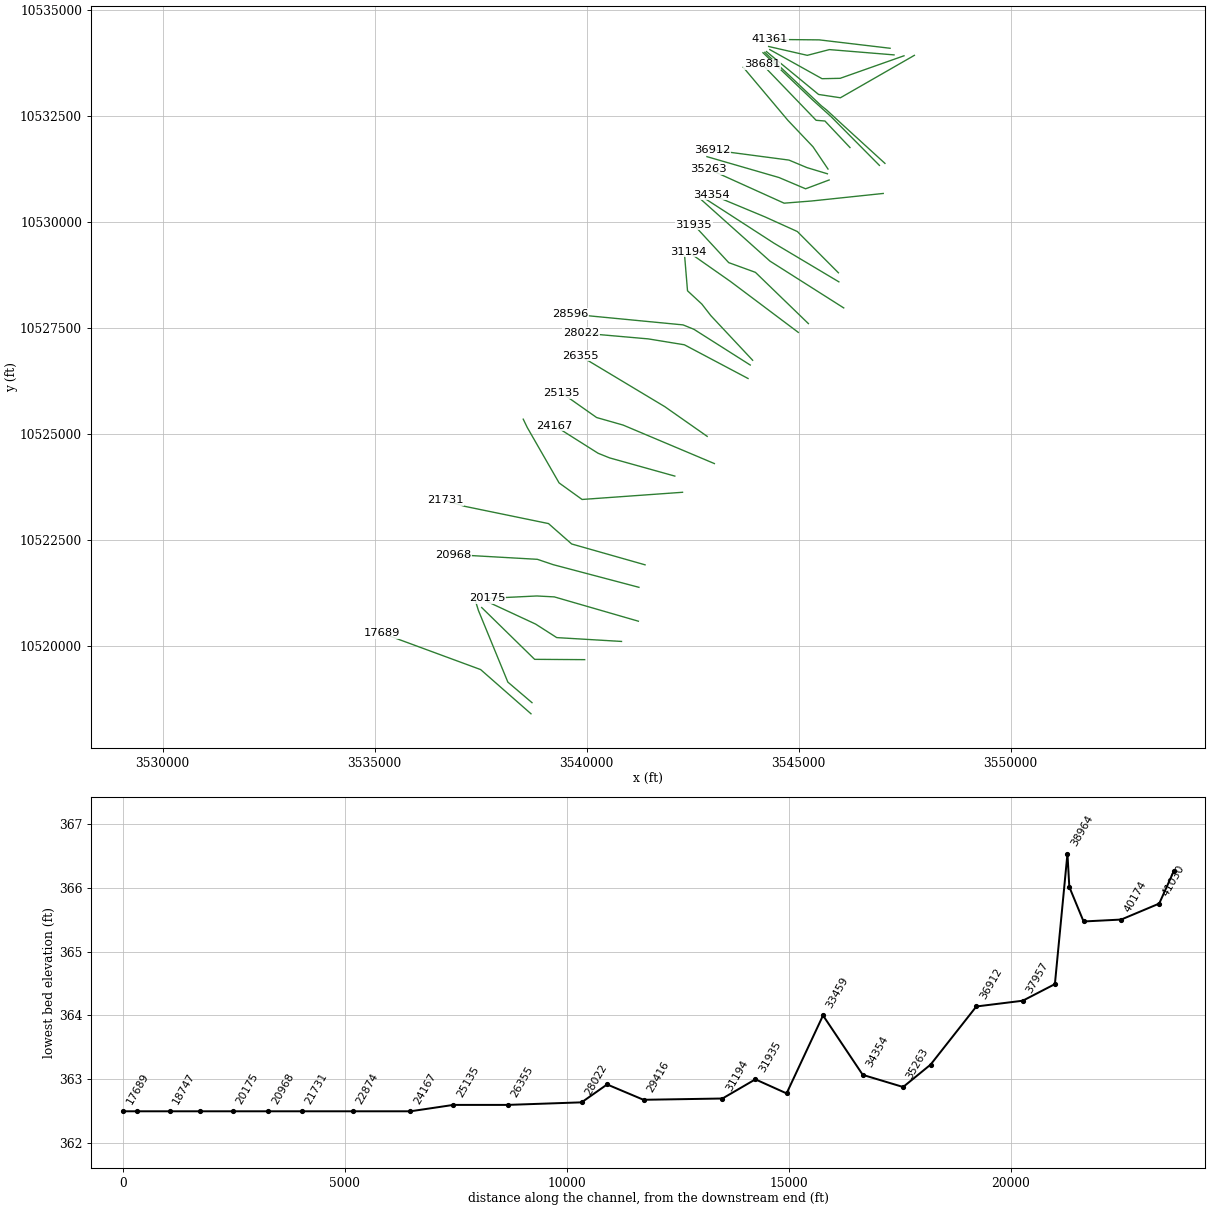
HEC-RAS study BIGELMCREEK.prj: BIG ELM CREEK Base Level Engineering

--- BIGELMCREEK.g01 (geometry) --- (continued)

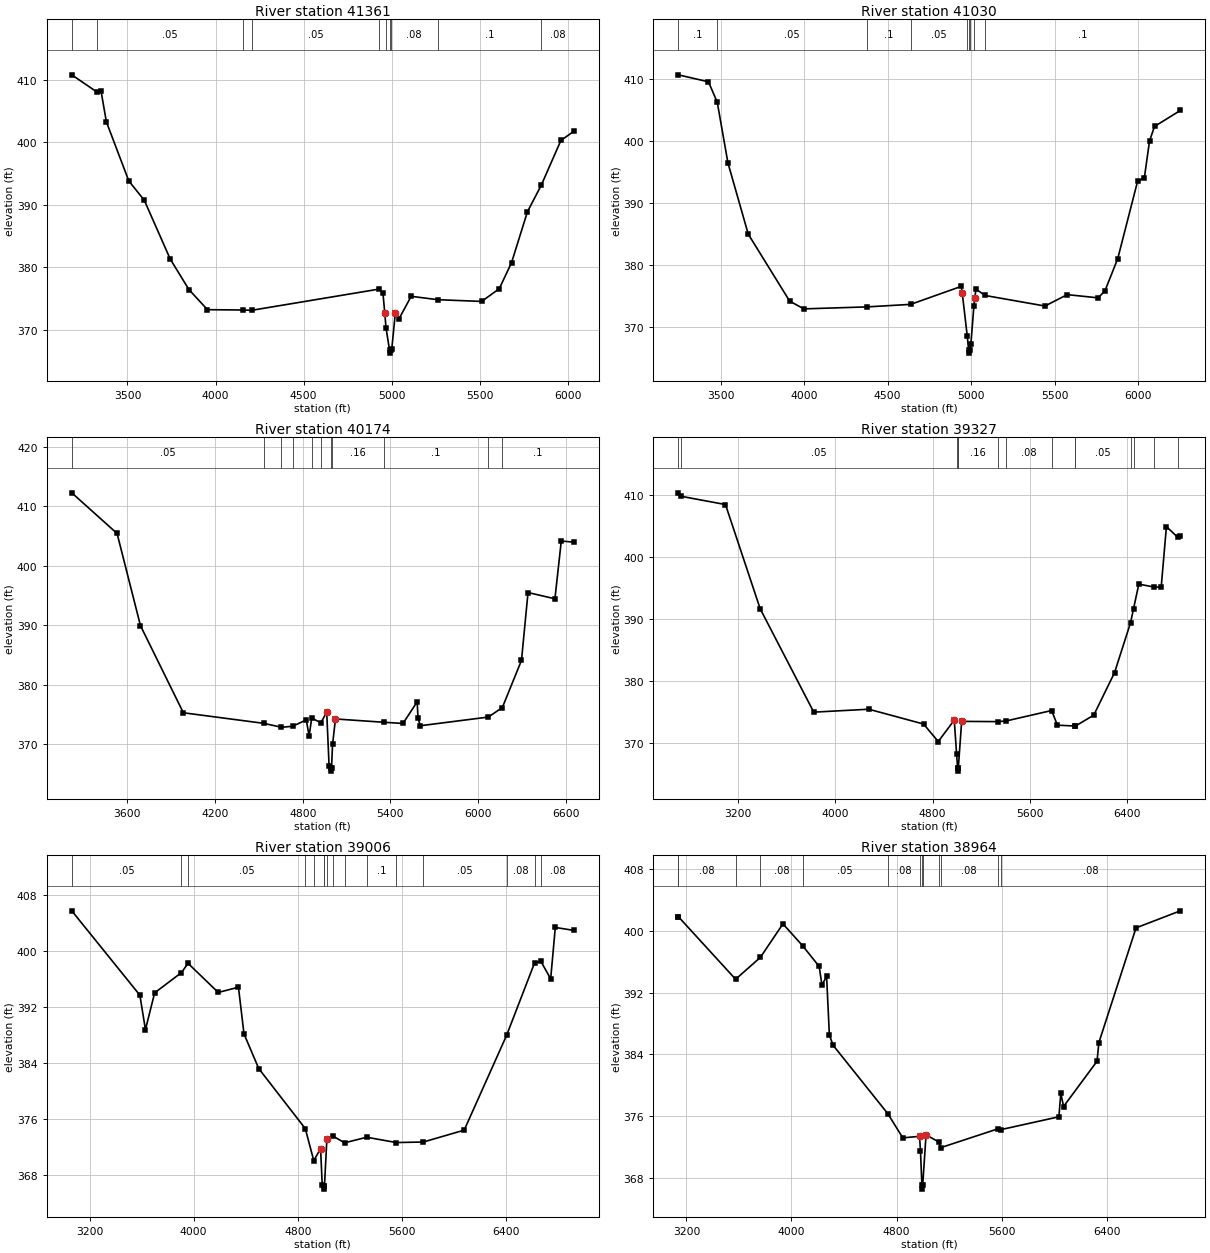
Type RM Length L Ch R = 1 ,41361   ,331,331,331
BEGIN DESCRIPTION:
BIG CREEK 23.0
END DESCRIPTION:
XS GIS Cut Line= 3
       3547157.1      10534088.4      3545485.24     10534286.32
      3544318.62     10534296.73
#Sta/Elev= 30
    3184  410.78    3330  407.97  3350.1   408.2  3380.4  403.27  3507.8   393.8
  3595.6  390.72  3742.9  381.31  3849.1  376.43  3954.3  373.21  4155.5  373.16
  4205.4  373.11    4930  376.51  4950.7  375.82  4960.7  372.71    4968   370.3
  4987.7  366.76  4990.4  366.26  4993.7  366.76  5000.7  366.92  5020.7  372.67
  5040.7   371.7  5110.7  375.35  5260.8  374.81  5510.7  374.53  5610.7  376.56
  5680.7  380.75  5770.7  388.87  5849.2  393.12  5960.7  400.28  6034.2  401.75
#Mann= 10 ,-1 , 0
    3184      .1       0    3330     .05       0  4155.5      .1       0
  4205.4     .05       0    4930     .12       0    4968     .08       0
  4987.7     .07       0  4993.7     .08       0  5260.8      .1       0
  5849.2     .08       0
Bank Sta=4960.7,5020.7
XS Rating Curve= 0 ,0
Exp/Cntr=0.3,0.1

Type RM Length L Ch R = 1 ,41030   ,856,856,856
BEGIN DESCRIPTION:
BIG CREEK 22.0
END DESCRIPTION:
XS GIS Cut Line= 4
      3547250.89     10533932.15      3545724.83     10534057.15
      3545203.99     10533921.73      3544292.53     10534130.07
#Sta/Elev= 30
  3246.7  410.66  3427.7  409.53  3480.2  406.23  3544.1  396.45  3665.6  384.95
  3913.5  374.14    3998  372.89    4376  373.21  4637.6  373.62  4939.9  376.52
    4946  375.49  4976.4  368.44  4984.3  366.25  4987.1  365.75  4990.3  366.25
  4997.7  367.19  5016.1  373.42  5020.9  374.72  5028.7  376.06  5083.4  375.05
  5441.1  373.35  5574.4  375.19  5759.1  374.67  5800.1   375.8  5876.8  381.02
    5995  393.45    6036  394.07  6066.8  399.99  6096.7  402.33    6251  404.91
#Mann= 9 ,-1 , 0
  3246.7      .1       0  3480.2     .05       0    4376      .1       0
  4637.6     .05       0  4976.4     .12       0  4984.3     .07       0
  4990.3     .12       0  5016.1     .16       0  5083.4      .1       0
Bank Sta=4946,5020.9
XS Rating Curve= 0 ,0
Exp/Cntr=0.3,0.1

Type RM Length L Ch R = 1 ,40174   ,847,847,847
BEGIN DESCRIPTION:
BIG CREEK 21.1
END DESCRIPTION:
XS GIS Cut Line= 4
      3547485.24     10533911.32      3545980.03     10533380.07
      3545551.93     10533371.23      3544319.07     10534056.88
#Sta/Elev= 30
  3219.9  412.28  3529.9  405.45  3689.9  389.95  3983.3  375.31  4534.1  373.53
  4654.8  372.87  4730.8  373.04    4824  374.11    4844  371.44  4861.5  374.42
    4924  373.62  4964.1  375.42  4980.5  366.35  4991.1     366  4993.8   365.5
  4997.1     366  5004.1  369.99  5024.1  374.27  5356.8  373.71  5485.9  373.51
  5583.1  377.15  5588.9  374.38  5604.9  373.13  6070.1  374.59  6165.8  376.19
  6296.8  384.12  6341.4  395.52  6525.5  394.47    6569  404.18    6655  403.99
#Mann= 11 ,-1 , 0
  3219.9     .05       0  4534.1      .1       0  4654.8     .05       0
  4730.8     .16       0  4861.5     .05       0    4924     .16       0
  4991.1     .07       0  4997.1     .16       0  5356.8      .1       0
  6070.1     .05       0  6165.8      .1       0
Bank Sta=4964.1,5024.1
XS Rating Curve= 0 ,0
Exp/Cntr=0.3,0.1

Type RM Length L Ch R = 1 ,39327   ,321,321,321
BEGIN DESCRIPTION:
BIG CREEK 21.0
END DESCRIPTION:
XS GIS Cut Line= 4
      3547730.03     10533921.73      3545985.24     10532921.73
      3545469.62     10532999.86      3544240.46     10534010.27
#Sta/Elev= 30
  2711.3  410.34  2732.2  409.79  3099.3  408.45  3384.2  391.65  3824.4  374.98
  4276.4  375.45  4726.5  373.06  4846.9  370.24  4978.4   373.7  4997.6  368.21
  5005.7  365.97  5008.5  365.47  5011.7  365.97  5039.1  373.49  5335.8  373.45
  5404.4  373.56    5778  375.24  5825.5  372.88  5971.3  372.74  5973.4  372.74
    6124  374.49  6294.8  381.35  6426.7  389.43  6451.2  391.69  6494.2  395.62
  6616.9  395.16  6677.9  395.12  6720.9  404.89    6813  403.19    6835  403.42
#Mann= 14 ,-1 , 0
  2711.3     .08       0  2732.2     .05       0  4997.6     .16       0
  5005.7     .07       0  5011.7     .16       0  5335.8      .1       0
  5404.4     .08       0    5778     .05       0  5971.3      .1       0
  5973.4     .05       0  6426.7     .08       0  6451.2      .1       0
  6616.9     .08       0    6813      .1       0
Bank Sta=4978.4,5039.1
XS Rating Curve= 0 ,0
Exp/Cntr=0.3,0.1

Type RM Length L Ch R = 1 ,39006   ,42,42,42
BEGIN DESCRIPTION:
BIG CREEK 20.02
END DESCRIPTION:
XS GIS Cut Line= 5
      3547035.46     10531375.25      3546050.23     10532273.68
      3545663.95     10532629.58      3545533.74     10532733.74
      3544201.28     10533992.42
#Sta/Elev= 30
  3063.7  405.69  3587.2  393.66  3629.8  388.75  3700.7     394  3905.8  396.87
  3957.6   398.2  4189.2  394.05  4344.6   394.8  4387.2  388.14  4500.6   383.2
  4858.4  374.63  4923.6  370.06  4975.6   371.8  4988.7  366.53  4999.8  366.51
  5002.5  366.01  5005.8  366.51  5023.9   373.1  5073.3  373.55    5160  372.61
  5330.1  373.41  5557.5  372.65  5765.6  372.73  6079.2  374.42  6404.9  387.92
    6620  398.26  6669.3  398.47  6743.9  395.99  6779.5  403.32    6922   402.9
#Mann= 16 ,-1 , 0
  3063.7     .05       0  3905.8     .08       0  3957.6     .05       0
  4858.4     .08       0  4923.6     .16       0  4999.8     .07       0
  5005.8     .16       0  5023.9     .08       0  5073.3      .1       0
    5160     .08       0  5330.1      .1       0  5557.5     .08       0
  5765.6     .05       0  6404.9     .08       0    6620      .1       0
  6669.3     .08       0
Bank Sta=4975.6,5023.9
XS Rating Curve= 0 ,0
Exp/Cntr=0.3,0.1

Type RM Length L Ch R = 1 ,38964   ,283,283,283
BEGIN DESCRIPTION:
BIG CREEK 20.01
END DESCRIPTION:
XS GIS Cut Line= 4
      3546905.28     10531327.48      3545759.43     10532482.01
      3545316.72     10532881.31      3544157.85     10533983.77
#Sta/Elev= 30
  3137.9  401.86  3138.4  401.86  3574.6  393.74  3763.1  396.57    3935  400.92
  4084.6  398.09  4210.8   395.4    4232  392.98  4267.4  394.12  4288.6  386.49
  4316.9  385.18  4733.9   376.3  4847.3  373.18  4975.1  373.37  4982.2  371.43
    4993  367.03  4995.7  366.53    4999  367.03  5024.4  373.57  5122.6  372.63
  5135.1   371.9  5570.3  374.34  5593.4  374.24  6036.2  375.91  6050.3  378.96
  6071.4  377.24  6326.2  383.11  6340.3  385.53  6623.1   400.4  6960.2  402.61
#Mann= 13 ,-1 , 0
  3137.9     .05       0  3138.4     .08       0  3574.6     .05       0
  3763.1     .08       0  4084.6     .05       0  4733.9     .08       0
  4982.2     .16       0    4993     .07       0    4999     .16       0
  5122.6      .1       0  5135.1     .08       0  5570.3      .1       0
  5593.4     .08       0
Bank Sta=4975.1,5024.4
XS Rating Curve= 0 ,0
Exp/Cntr=0.3,0.1

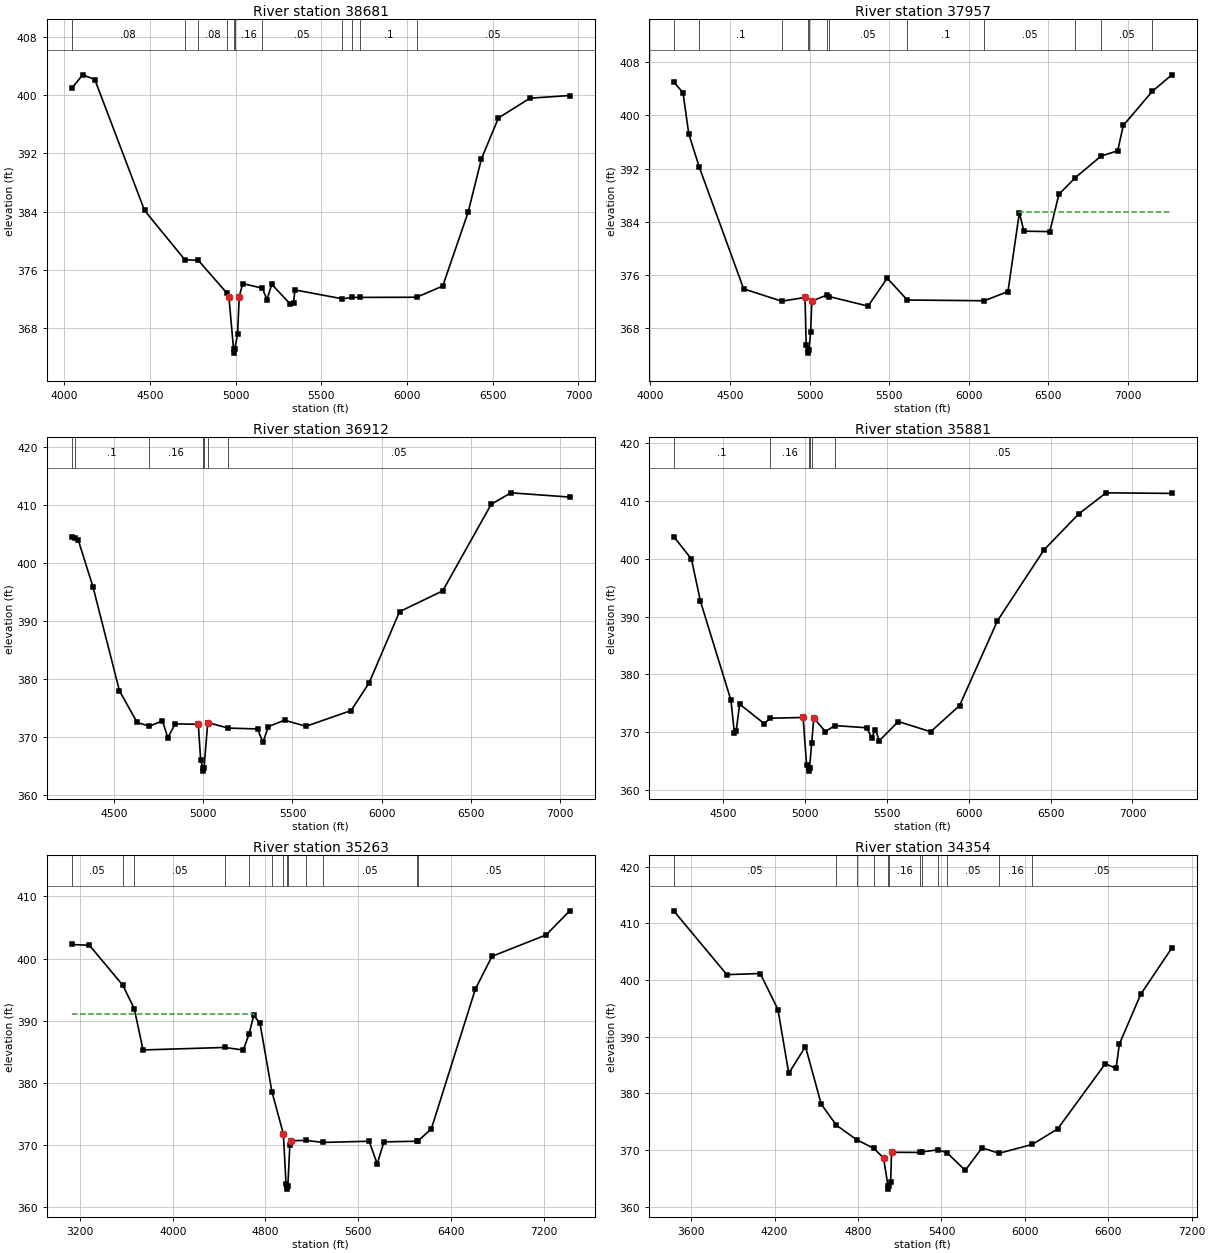
Type RM Length L Ch R = 1 ,38681   ,724,724,724
BEGIN DESCRIPTION:
BIG CREEK 20.0
END DESCRIPTION:
XS GIS Cut Line= 4
      3546210.82      10531748.5      3545620.54      10532373.5
      3545412.21     10532390.86      3544136.65     10533714.14
#Sta/Elev= 30
  4042.2  400.96  4107.1  402.84  4177.9  402.19    4468  384.15  4702.7  377.37
    4782  377.27  4948.4  372.76  4960.5  372.16  4987.6  364.99  4990.4  364.49
  4993.6  364.99  5010.7   367.1  5020.7  372.28  5040.8  374.08  5155.7  373.44
  5182.2  371.86  5210.5  373.98  5316.7  371.28  5337.8   371.4    5345   373.2
  5621.5  371.98  5680.8  372.16  5725.4  372.17  6055.3  372.19  6207.9  373.73
  6356.3  383.92    6434  391.27    6533   396.9    6717  399.62  6948.9  399.99
#Mann= 11 ,-1 , 0
  4042.2     .08       0  4702.7      .1       0    4782     .08       0
  4948.4     .16       0  4987.6     .07       0  4993.6     .16       0
  5155.7     .05       0  5621.5      .1       0  5680.8     .05       0
  5725.4      .1       0  6055.3     .05       0
Bank Sta=4960.5,5020.7
XS Rating Curve= 0 ,0
Exp/Cntr=0.3,0.1

Type RM Length L Ch R = 1 ,37957   ,1045,1045,1045
BEGIN DESCRIPTION:
BIG CREEK 19.0
END DESCRIPTION:
XS GIS Cut Line= 4
      3545692.12     10531241.63      3545339.41     10531765.48
      3544745.66     10532390.48      3543692.08     10533641.68
#Sta/Elev= 30
  4146.5  405.02    4205  403.42    4241  397.23    4307  392.22  4585.9   373.9
  4825.3  372.04  4971.4  372.61  4978.7  365.48  4989.8  364.73  4992.6  364.23
  4995.8  364.73    5007  367.43  5013.9  372.05  5108.9  372.97  5123.2  372.74
  5367.4   371.3  5487.9  375.51  5613.9  372.22  6098.1  372.11  6246.4   373.5
  6317.9  385.36  6346.5  382.58  6509.1  382.51  6566.3  388.12  6670.2  390.65
  6831.3  393.88  6935.6  394.67  6970.8  398.48  7153.4  403.62  7275.8   406.1
#Mann= 12 ,-1 , 0
  4146.5     .05       0    4307      .1       0  4825.3     .16       0
  4989.8     .07       0  4995.8     .16       0  5108.9      .1       0
  5123.2     .05       0  5613.9      .1       0  6098.1     .05       0
  6670.2      .1       0  6831.3     .05       0  7153.4      .1       0
#XS Ineff= 2 , 0
                         6318.75          385.47
Permanent Ineff=
       F       F
Bank Sta=4971.4,5013.9
XS Rating Curve= 0 ,0
Exp/Cntr=0.3,0.1

Type RM Length L Ch R = 1 ,36912   ,1031,1031,1031
BEGIN DESCRIPTION:
BIG CREEK 18.1
END DESCRIPTION:
XS GIS Cut Line= 4
      3545677.95     10531130.07      3545195.24     10531275.75
       3544771.7     10531452.98      3542955.55     10531692.36
#Sta/Elev= 30
  4260.5  404.36  4278.4   404.2  4297.9  403.91  4381.5  395.76  4529.2  377.96
  4628.2  372.52    4697  371.87  4770.3  372.79  4800.6  369.88  4841.7  372.27
  4971.5  372.21  4984.9  366.05  4997.7  364.64  5000.4  364.14  5003.7  364.64
  5024.5  372.47  5027.3  372.49  5137.9  371.55  5304.1   371.4  5334.4   369.1
  5364.6   371.8  5455.4   372.9  5576.5  371.86  5828.6  374.56  5929.5  379.29
    6101  391.58    6343  395.16  6615.4  410.07  6726.3  412.03  7055.7   411.3
#Mann= 7 ,-1 , 0
  4260.5     .05       0  4278.4      .1       0    4697     .16       0
  4997.7     .07       0  5003.7     .16       0  5027.3      .1       0
  5137.9     .05       0
Bank Sta=4971.5,5024.5
XS Rating Curve= 0 ,0
Exp/Cntr=0.3,0.1

Type RM Length L Ch R = 1 ,35881   ,618,618,618
BEGIN DESCRIPTION:
BIG CREEK 18.2
END DESCRIPTION:
XS GIS Cut Line= 4
      3545719.66     10530984.25      3545163.96     10530776.14
      3544537.33     10531041.53      3542835.97     10531533.97
#Sta/Elev= 30
  4195.6  403.86    4304  399.96  4359.2  392.63  4545.4  375.52  4566.7  369.84
  4577.4  370.17  4598.8  374.83  4748.3  371.47    4787   372.4  4986.5  372.52
  5008.2  364.25  5019.8  363.73  5022.5  363.23  5025.8  363.73  5039.1  368.09
  5051.9  372.42  5122.9  370.08  5180.2  371.12    5376  370.74  5405.1  369.04
  5428.8   370.4  5452.5   368.5  5568.6  371.82  5766.4  370.05  5943.4  374.59
  6174.5  389.26  6458.9  401.54  6670.9  407.76  6838.7  411.43  7240.7  411.33
#Mann= 6 ,-1 , 0
  4195.6      .1       0    4787     .16       0  5019.8     .07       0
  5025.8     .16       0  5039.1      .1       0  5180.2     .05       0
Bank Sta=4986.5,5051.9
XS Rating Curve= 0 ,0
Exp/Cntr=0.3,0.1

Type RM Length L Ch R = 1 ,35263   ,909,909,909
BEGIN DESCRIPTION:
BIG CREEK 18.0
END DESCRIPTION:
XS GIS Cut Line= 4
      3546995.66     10530666.53      3545307.27     10530488.96
      3544657.12     10530437.36      3542881.04     10531239.46
#Sta/Elev= 30
  3126.9  402.27  3281.3  402.14  3568.6  395.71  3667.6  391.96  3743.8  385.29
    4447  385.69  4608.6  385.28  4657.8  387.82  4699.1  390.85  4752.8  389.59
  4855.7  378.59  4954.6  371.76  4977.8  363.64  4987.3  363.38    4990  362.88
  4993.3  363.38  5010.4  370.03  5020.4  370.68  5153.9  370.72  5295.1   370.4
    5695  370.59  5764.4  366.94  5822.4  370.49  6110.4  370.59  6118.1  370.67
  6231.1  372.56    6612  395.11  6755.1  400.36  7222.9  403.82  7425.6  407.69
#Mann= 13 ,-1 , 0
  3126.9     .05       0  3568.6      .1       0  3667.6     .05       0
    4447      .1       0  4657.8     .05       0  4855.7      .1       0
  4954.6     .16       0  4987.3     .07       0  4993.3     .16       0
  5153.9      .1       0  5295.1     .05       0  6110.4     .16       0
  6118.1     .05       0
#XS Ineff= 2 , 0
         4704.55  391.04
Permanent Ineff=
       F       F
Bank Sta=4954.6,5020.4
XS Rating Curve= 0 ,0
Exp/Cntr=0.3,0.1

Type RM Length L Ch R = 1 ,34354   ,895,895,895
BEGIN DESCRIPTION:
BIG CREEK 17.0
END DESCRIPTION:
XS GIS Cut Line= 4
      3545937.53      10528796.7      3544969.62     10529768.96
      3544201.39     10530116.18      3542938.39     10530641.34
#Sta/Elev= 30
  3474.2  412.18  3856.3  400.92  4096.7  401.12    4224  394.76  4301.8  383.51
    4422  388.22  4535.1  378.07  4643.6  374.36  4789.6   371.8  4913.8  370.26
  4983.4  368.57    5016  363.57  5018.7  363.07    5022  363.57  5035.1  364.41
  5040.9  369.57  5245.3  369.54  5259.7  369.63  5371.6     370  5438.2  369.53
    5571  366.38  5692.1  370.36  5813.9   369.4  6054.7  370.97  6236.3  373.71
  6578.9  385.21  6655.9  384.36  6679.7  388.67  6833.7  397.47    7057  405.62
#Mann= 12 ,-1 , 0
  3474.2     .05       0  4643.6     .16       0  4789.6     .05       0
  4913.8     .16       0    5016     .07       0    5022     .16       0
  5245.3      .1       0  5259.7     .05       0  5371.6      .1       0
  5438.2     .05       0  5813.9     .16       0  6054.7     .05       0
Bank Sta=4983.4,5040.9
XS Rating Curve= 0 ,0
Exp/Cntr=0.3,0.1

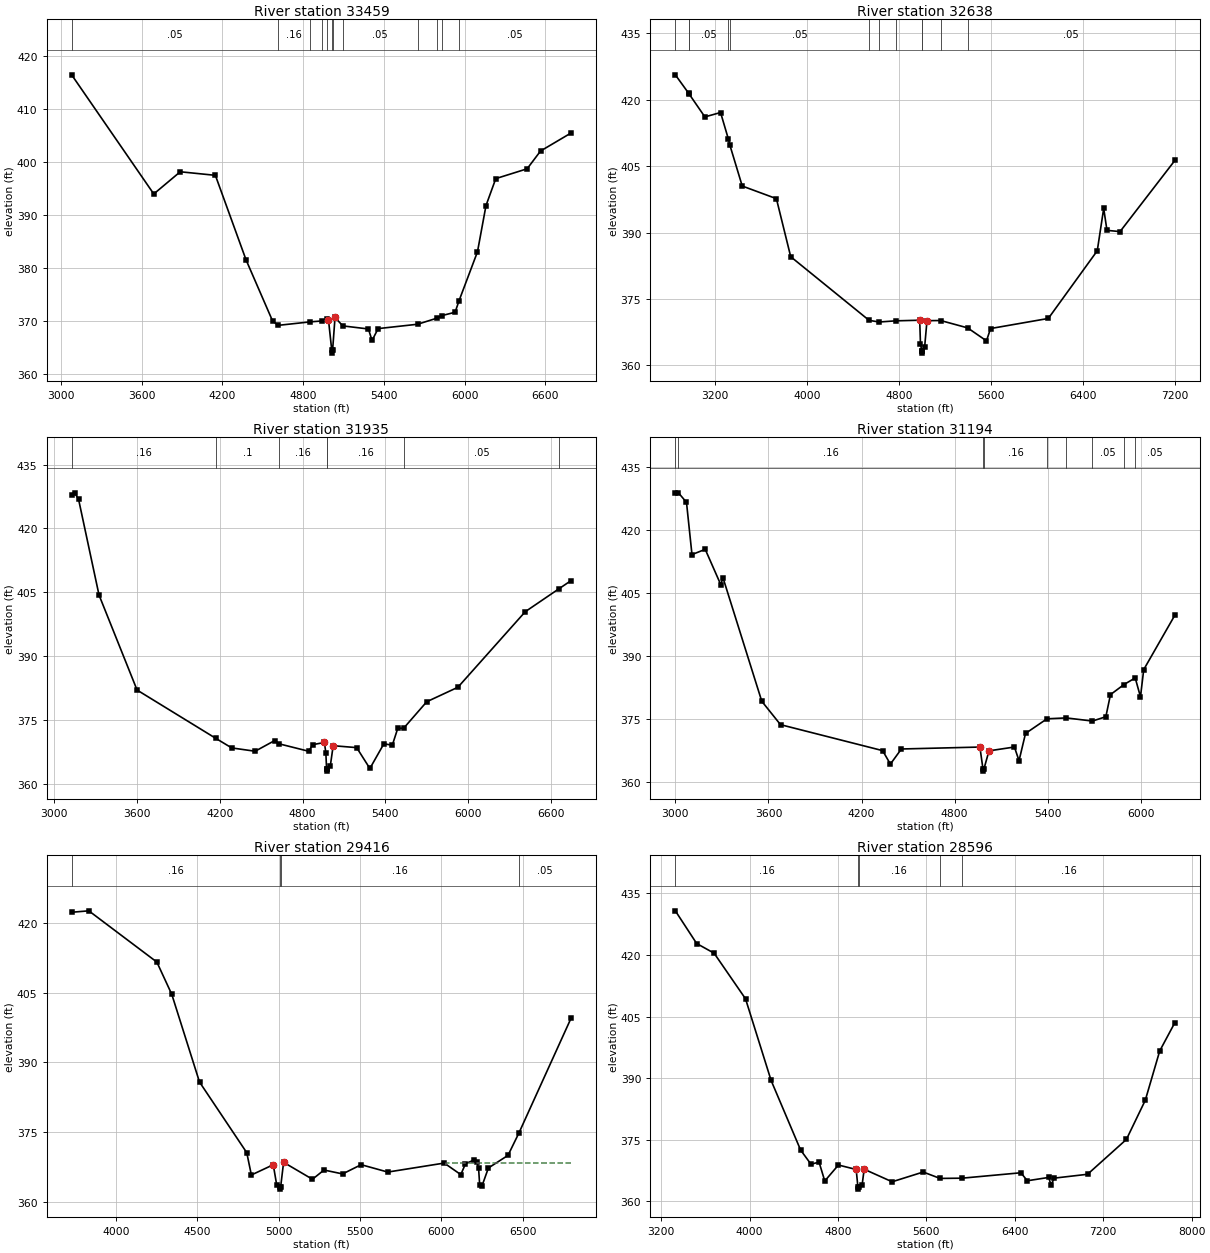
Type RM Length L Ch R = 1 ,33459   ,821,821,821
BEGIN DESCRIPTION:
BIG CREEK 16.0
END DESCRIPTION:
XS GIS Cut Line= 3
       3545948.8     10528583.18      3544417.53     10529494.65
      3542797.78      10530541.5
#Sta/Elev= 30
  3080.4  416.42  3690.4  393.98  3887.1  398.16    4148  397.49  4375.8  381.57
  4572.5  370.08  4613.9  369.23  4852.9  369.89  4941.1  370.06  4973.5  370.37
  4987.9  370.33  5012.6   364.5  5015.3     364  5018.6   364.5  5036.7  370.72
  5094.4  369.13  5284.7  368.55  5311.8  366.38    5357  368.62  5650.2  369.44
  5792.8  370.58  5830.8  371.07  5928.6   371.7  5958.2  373.89  6094.9  383.09
  6158.2   391.8  6230.8  396.87  6463.6  398.72  6563.3  402.07    6791  405.48
#Mann= 12 ,-1 , 0
  3080.4     .05       0  4613.9     .16       0  4852.9     .05       0
  4941.1     .16       0  4973.5      .1       0  5012.6     .07       0
  5018.6      .1       0  5094.4     .05       0  5650.2     .16       0
  5792.8     .05       0  5830.8     .16       0  5958.2     .05       0
Bank Sta=4987.9,5036.7
XS Rating Curve= 0 ,0
Exp/Cntr=0.3,0.1

Type RM Length L Ch R = 1 ,32638   ,703,703,703
BEGIN DESCRIPTION:
BIG CREEK 16.1
END DESCRIPTION:
XS GIS Cut Line= 3
      3546063.33     10527968.63      3544321.56     10529073.18
      3542620.63     10530593.63
#Sta/Elev= 30
  2854.5  425.62  2969.1   421.5  2971.5   421.4  3111.4  416.12  3247.8  417.11
  3316.4  411.06  3329.4  409.69  3436.2  400.51  3733.3  397.66  3857.8  384.55
  4539.9  370.17  4628.7  369.81  4770.5  370.07  4979.4  370.21  4986.1  364.91
  4997.3  363.28  5000.1  362.78  5003.3  363.28    5022  364.09  5042.9  370.11
  5161.8  370.14  5396.3  368.48  5560.1  365.55  5595.5  368.33  6097.9  370.61
  6523.4  385.89  6579.4  395.45  6607.8   390.5  6721.5  390.22  7198.4  406.29
#Mann= 12 ,-1 , 0
  2854.5     .05       0  2969.1      .1       0  2971.5     .05       0
  3316.4      .1       0  3329.4     .05       0  4539.9     .16       0
  4628.7     .05       0  4770.5     .16       0  4997.3     .07       0
  5003.3     .16       0  5161.8      .1       0  5396.3     .05       0
Bank Sta=4979.4,5042.9
XS Rating Curve= 0 ,0
Exp/Cntr=0.3,0.1

Type RM Length L Ch R = 1 ,31935   ,741,741,741
BEGIN DESCRIPTION:
BIG CREEK 15.0
END DESCRIPTION:
XS GIS Cut Line= 4
      3545230.03     10527598.82      3543980.03     10528807.15
      3543349.83     10529036.32      3542527.14     10529926.69
#Sta/Elev= 30
  3125.3  427.76  3147.1  428.35  3175.4  426.84  3323.8  404.35  3599.6  382.04
  4171.1  370.68  4285.7  368.45  4455.5  367.67  4596.7  370.17  4627.9  369.42
  4844.4  367.66  4872.3  369.21  4957.4  369.73  4968.1   367.3  4973.4   363.5
  4976.1     363  4979.4   363.5    5000  364.13  5021.3  368.97  5191.5  368.52
  5287.3  363.62  5388.7  369.42  5449.9  369.09  5489.4  373.05  5532.6  373.09
  5699.4  379.29  5925.6   382.7  6413.8  400.44  6658.9  405.84  6746.7  407.76
#Mann= 7 ,-1 , 0
  3125.3     .16       0  4171.1      .1       0  4627.9     .16       0
  4973.4     .07       0  4979.4     .16       0  5532.6     .05       0
  6658.9     .16       0
Bank Sta=4957.4,5021.3
XS Rating Curve= 0 ,0
Exp/Cntr=0.3,0.1

Type RM Length L Ch R = 1 ,31194   ,1778,1778,1778
BEGIN DESCRIPTION:
BIG CREEK 14.0
END DESCRIPTION:
XS GIS Cut Line= 3
       3544992.1     10527391.65      3543392.11     10528591.64
      3542392.14     10529291.62
#Sta/Elev= 30
  2999.7  428.85  3019.7  428.95  3071.6  426.69    3107  414.25  3192.4   415.5
  3292.4  407.11    3307  408.73    3557  379.33  3677.8  373.76  4336.1  367.58
  4386.1  364.37    4457  367.97  4963.2  368.43  4983.1   363.2  4985.9   362.7
  4989.1   363.2  5021.9  367.53  5185.8  368.44  5215.5  365.18  5257.3  371.67
  5395.5  375.15  5519.6  375.37  5688.6  374.62  5775.2  375.65  5804.9  380.91
  5892.1  383.31  5964.6  384.89  5998.4  380.38  6019.4  386.87  6220.3  399.83
#Mann= 9 ,-1 , 0
  2999.7      .1       0  3019.7     .16       0  4983.1     .07       0
  4989.1     .16       0  5395.5     .05       0  5519.6      .1       0
  5688.6     .05       0  5892.1     .16       0  5964.6     .05       0
Bank Sta=4963.2,5021.9
XS Rating Curve= 0 ,0
Exp/Cntr=0.3,0.1

Type RM Length L Ch R = 1 ,29416   ,820,820,820
BEGIN DESCRIPTION:
BIG CREEK 13.2
END DESCRIPTION:
XS GIS Cut Line= 5
      3543914.92     10526735.12      3542929.69     10527785.45
      3542717.01     10528058.89      3542378.46      10528372.3
      3542310.89     10529188.35
#Sta/Elev= 30
  3729.5  422.39  3834.9   422.7  4252.6  411.65  4344.4  404.67  4514.4  385.78
  4804.5  370.54  4832.8  365.73  4967.2  367.94  4988.2  363.61  5006.6  363.18
  5009.4  362.68  5012.6  363.18  5030.7  368.46  5207.7  364.81  5278.8   366.8
  5392.8  365.96  5506.8  367.95  5670.2  366.36  6016.8   368.3  6118.6  365.81
  6147.3  368.16  6197.5  368.93  6217.5  368.56  6227.6  367.18  6234.3  363.64
  6247.6  363.26  6287.8  367.24  6408.2  369.96    6476  374.84  6796.2  399.61
#Mann= 4 ,-1 , 0
  3729.5     .16       0  5006.6     .07       0  5012.6     .16       0
    6476     .05       0
#XS Ineff= 2 , 0
                         6029.55          368.32
Permanent Ineff=
       F       F
Bank Sta=4967.2,5030.7
XS Rating Curve= 0 ,0
Exp/Cntr=0.3,0.1

Type RM Length L Ch R = 1 ,28596   ,574,574,574
BEGIN DESCRIPTION:
BIG CREEK 13.1
END DESCRIPTION:
XS GIS Cut Line= 4
      3543858.47     10526622.28      3542530.38     10527464.27
      3542274.31     10527568.43      3539615.44     10527824.35
#Sta/Elev= 30
  3328.2  430.77  3521.2   422.8  3679.1  420.44  3963.3  409.32  4194.8  389.41
  4461.7  372.45  4555.7  368.99  4628.6  369.51  4680.3   364.9  4803.9   368.8
  4964.5  367.71  4980.2  363.42    4983  362.92  4986.2  363.42  5018.1  363.89
  5036.7  367.77  5289.9  364.71    5571  367.09  5723.1  365.53  5922.6  365.59
  6455.2  366.91  6512.9  364.96  6706.4  365.77  6727.8  363.93  6756.6   365.6
    7058  366.54  7409.6  375.04  7580.4  384.58    7711  396.61  7848.3  403.52
#Mann= 5 ,-1 , 0
  3328.2     .16       0  4980.2     .07       0  4986.2     .16       0
  5723.1     .12       0  5922.6     .16       0
Bank Sta=4964.5,5036.7
XS Rating Curve= 0 ,0
Exp/Cntr=0.3,0.1

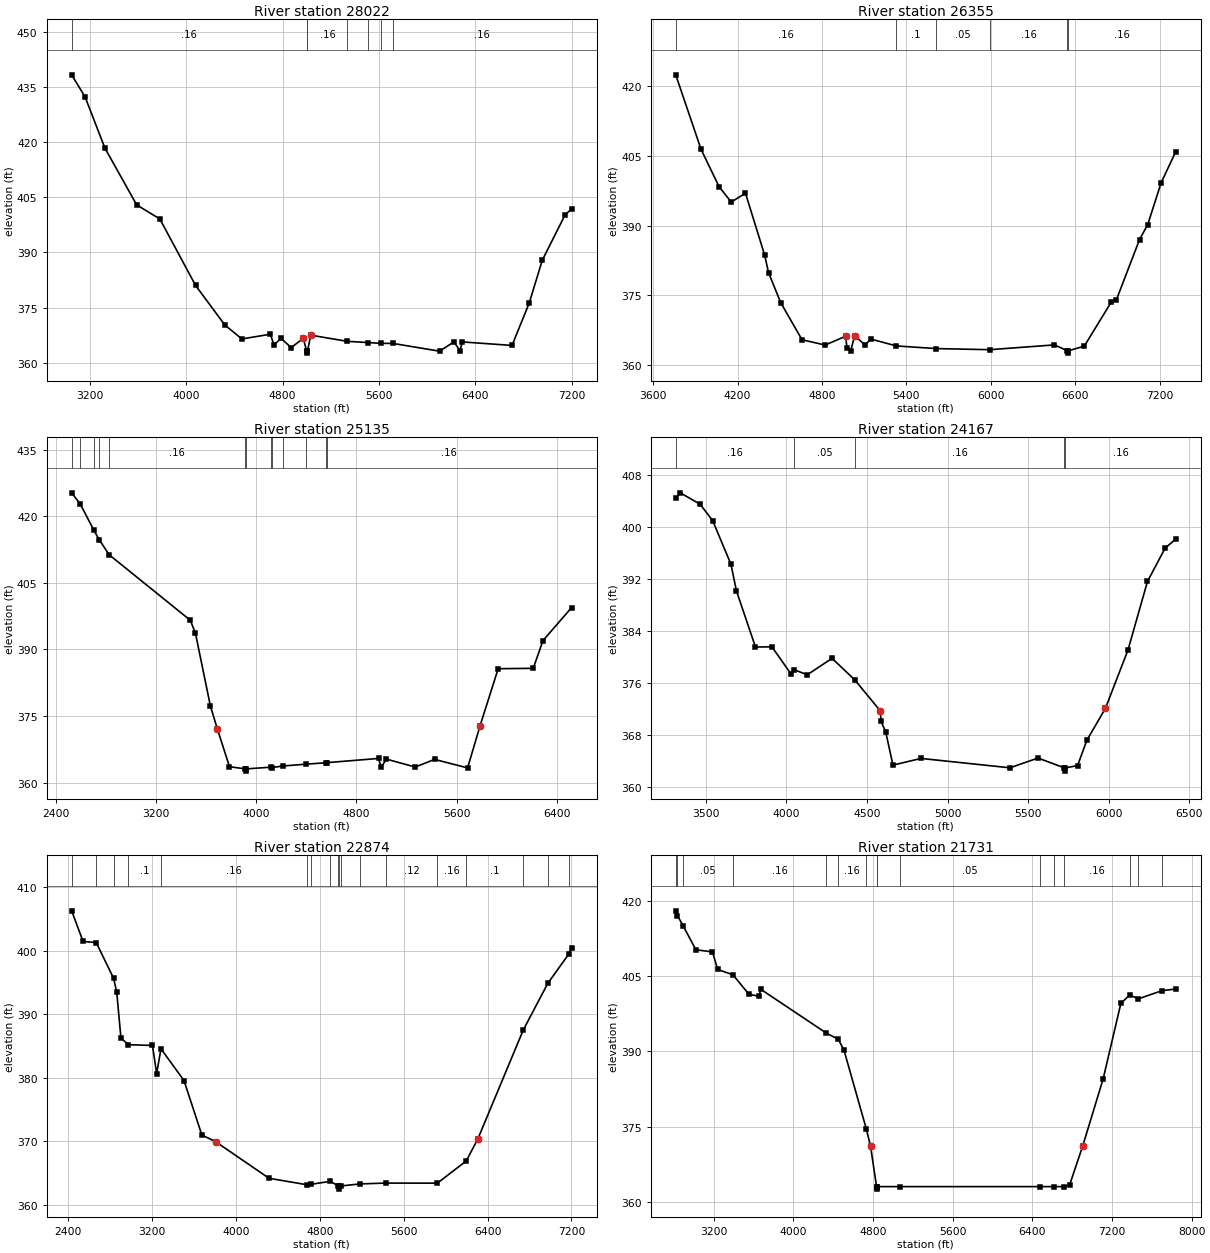
Type RM Length L Ch R = 1 ,28022   ,1667,1667,1667
BEGIN DESCRIPTION:
BIG CREEK 13.0
END DESCRIPTION:
XS GIS Cut Line= 4
      3543806.45      10526305.4      3542304.69     10527099.68
      3541453.99     10527238.57      3539869.81     10527377.46
#Sta/Elev= 30
  3048.6  438.27  3159.6   432.3  3324.3  418.39  3588.4  402.93  3780.8   399.1
  4077.6  381.03  4320.5  370.28  4462.4  366.49  4698.8  367.78  4727.8   364.9
  4788.1  366.62  4871.7  364.15  4972.4  366.66  5000.4  363.14  5003.2  362.64
  5006.4  363.14  5033.8  367.52  5338.1  365.84  5513.4  365.51  5614.2  365.29
  5713.8  365.29  6103.2  363.17  6223.7   365.7  6271.6  363.33  6293.9  365.68
  6705.5  364.73  6848.9  376.33  6956.4  387.87  7147.2  400.31  7199.7  401.77
#Mann= 7 ,-1 , 0
  3048.6     .16       0  5000.4     .07       0  5006.4     .16       0
  5338.1      .1       0  5513.4     .16       0  5614.2      .1       0
  5713.8     .16       0
Bank Sta=4972.4,5033.8
XS Rating Curve= 0 ,0
Exp/Cntr=0.3,0.1

Type RM Length L Ch R = 1 ,26355   ,1220,1220,1220
BEGIN DESCRIPTION:
BIG CREEK 11.0
END DESCRIPTION:
XS GIS Cut Line= 3
      3542842.09     10524941.65      3541842.11     10525641.64
      3539842.12     10526841.63
#Sta/Elev= 30
  3760.4  422.48  3940.4  406.45  4068.6   398.4  4154.9  395.11  4256.1  397.01
  4392.9  383.64    4420  379.92  4506.3  373.47    4658  365.48  4822.4  364.34
  4967.5  366.23    4978   363.7  5004.4  363.13  5031.6  366.36  5105.4  364.37
  5148.2  365.62  5327.8  364.15  5611.1  363.58  5990.9  363.34  6452.4  364.37
  6544.6   363.1  6547.4   362.6  6550.6   363.1  6664.2   364.1  6854.7  373.53
  6891.6  374.01  7056.9  387.04  7115.2  390.26  7210.4  399.27  7313.4   405.9
#Mann= 6 ,-1 , 0
  3760.4     .16       0  5327.8      .1       0  5611.1     .05       0
  5990.9     .16       0  6544.6     .07       0  6550.6     .16       0
Bank Sta=4967.5,5031.6
XS Rating Curve= 0 ,0
Exp/Cntr=0.3,0.1

Type RM Length L Ch R = 1 ,25135   ,968,968,968
BEGIN DESCRIPTION:
BIG CREEK 10.0
END DESCRIPTION:
XS GIS Cut Line= 4
      3543012.13     10524300.21      3540859.38     10525207.32
      3540234.38     10525385.28      3539415.59     10525961.45
#Sta/Elev= 30
  2528.5  425.28  2597.4  422.74  2706.5  416.81  2747.8  414.74  2827.6  411.33
  3475.1  396.57    3516  393.62  3635.4  377.22  3689.6  372.18  3787.3   363.6
  3914.5   363.1  3917.3   362.6  3920.5   363.1  4117.4  363.49  4128.5  363.41
  4214.7  363.76  4400.9  364.17  4556.4  364.49  4565.1  364.51  4976.5  365.46
  4996.9  363.42  5038.5  365.31  5268.1  363.52  5423.2  365.24  5686.4  363.33
  5786.2  372.85  5930.3  385.67  6209.9  385.75  6287.5  391.99  6515.6  399.43
#Mann= 13 ,-1 , 0
  2528.5      .1       0  2597.4     .05       0  2706.5     .16       0
  2747.8     .05       0  2827.6     .16       0  3914.5     .07       0
  3920.5     .16       0  4117.4     .12       0  4128.5     .16       0
  4214.7     .12       0  4400.9     .16       0  4556.4     .12       0
  4565.1     .16       0
Bank Sta=3689.6,5786.2
XS Rating Curve= 0 ,0
Exp/Cntr=0.3,0.1

Type RM Length L Ch R = 1 ,24167   ,1293,1293,1293
BEGIN DESCRIPTION:
BIG CREEK 9.0
END DESCRIPTION:
XS GIS Cut Line= 4
      3542079.04     10524005.05      3540538.19     10524434.75
       3540269.1     10524543.26      3539242.13     10525191.63
#Sta/Elev= 30
  3312.2   404.4  3340.2  405.21  3463.3  403.47    3542  400.92    3655  394.25
  3689.2  390.16  3807.3  381.55  3909.9  381.57    4028  377.41  4046.7  378.07
  4129.2  377.29  4282.9  379.81  4424.3   376.5  4582.3  371.75  4587.5  370.14
  4616.5  368.49    4661  363.42  4835.1  364.45  5387.7  363.01  5561.7  364.51
  5725.8     363  5728.5   362.5  5731.8     363  5807.6  363.35  5865.3  367.24
  5980.6  372.14  6120.6  381.09  6241.8  391.62  6351.2  396.72  6416.5   398.1
#Mann= 5 ,-1 , 0
  3312.2     .16       0  4046.7     .05       0  4424.3     .16       0
  5725.8     .07       0  5731.8     .16       0
Bank Sta=4582.3,5980.6
XS Rating Curve= 0 ,0
Exp/Cntr=0.3,0.1

Type RM Length L Ch R = 1 ,22874   ,1143,1143,1143
BEGIN DESCRIPTION:
BIG CREEK 7.0
END DESCRIPTION:
XS GIS Cut Line= 5
      3542260.77     10523623.51      3539891.49     10523453.85
      3539348.96     10523844.48      3538598.09      10525150.9
      3538503.45     10525346.72
#Sta/Elev= 30
    2433  406.26  2541.9  401.44  2667.5  401.27  2833.4  395.63  2862.8  393.49
  2902.9  386.27    2973  385.21  3203.6  385.09  3243.7  380.67  3284.8  384.57
  3504.3  379.58  3674.8  371.01  3805.2  369.97  4316.5   364.2  4674.1   363.2
  4718.1  363.26  4900.2  363.73  4976.1     363  4978.9   362.5  4982.1     363
  5001.6     363  5185.4  363.32  5427.1  363.45  5921.1  363.44    6196  366.92
  6306.6  370.37  6740.8  387.53  6974.1  394.84  7172.8  399.42  7201.2  400.44
#Mann= 18 ,-1 , 0
    2433     .05       0  2667.5     .16       0  2833.4     .05       0
    2973      .1       0  3284.8     .16       0  4674.1     .12       0
  4718.1     .16       0  4900.2     .05       0  4976.1    .033       0
  4982.1     .05       0  5001.6     .12       0  5185.4     .05       0
  5427.1     .12       0  5921.1     .16       0    6196      .1       0
  6740.8     .05       0  6974.1      .1       0  7172.8     .16       0
Bank Sta=3805.2,6306.6
XS Rating Curve= 0 ,0
Exp/Cntr=0.3,0.1

Type RM Length L Ch R = 1 ,21731   ,763,763,763
BEGIN DESCRIPTION:
BIG CREEK 9.1
END DESCRIPTION:
XS GIS Cut Line= 5
      3541377.03     10521913.63      3539646.15     10522405.01
      3539099.25     10522885.85      3537120.21      10523292.8
      3536670.13     10523430.08
#Sta/Elev= 30
  2820.7  418.06  2837.8  417.11    2896  415.03  3023.3  410.28  3189.6  409.86
  3241.6  406.36  3395.2  405.29  3553.5  401.44  3657.4  400.97  3673.5  402.41
  4330.9  393.67  4452.9  392.41  4509.8  390.24  4734.2   374.5  4776.2  371.09
  4836.8     363  4839.5   362.5  4842.8     363  5067.4     363    6479     363
  6619.7     363  6721.5     363  6774.6  363.32  6907.3  371.17  7111.5  384.51
  7289.3  399.57  7376.8  401.25  7465.9   400.5  7702.3  402.12  7839.2  402.45
#Mann= 16 ,-1 , 0
  2820.7     .05       0  2837.8      .1       0    2896     .05       0
  3395.2     .16       0  4330.9     .05       0  4452.9     .16       0
  4734.2     .12       0  4836.8     .07       0  4842.8     .12       0
  5067.4     .05       0    6479     .07       0  6619.7     .05       0
  6721.5     .16       0  7376.8      .1       0  7465.9     .16       0
  7702.3     .05       0
Bank Sta=4776.2,6907.3
XS Rating Curve= 0 ,0
Exp/Cntr=0.3,0.1

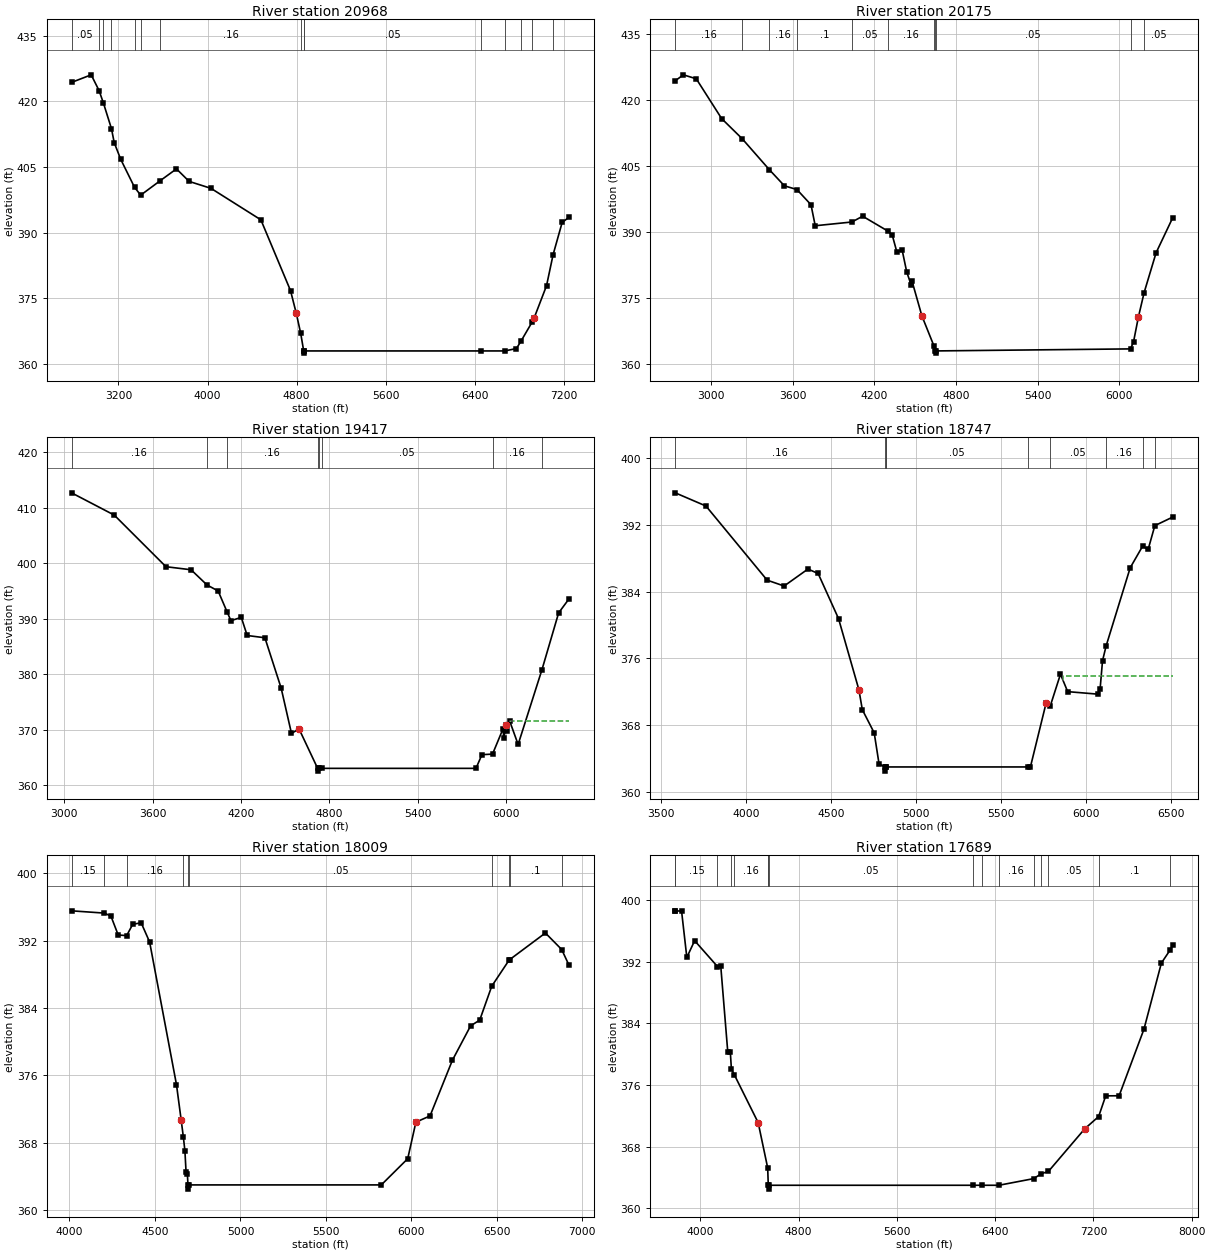
Type RM Length L Ch R = 1 ,20968   ,793,793,793
BEGIN DESCRIPTION:
BIG CREEK 8.1
END DESCRIPTION:
XS GIS Cut Line= 4
      3541232.61     10521383.55      3539210.07     10521917.39
      3538836.81     10522043.26      3536859.82     10522155.65
#Sta/Elev= 30
  2779.4   424.3  2955.7  426.03  3026.5  422.43  3065.5  419.59  3137.8  413.73
  3162.6  410.53    3221  406.73  3344.5  400.37    3400  398.56  3577.2   401.9
  3721.1  404.56  3834.9   401.7  4031.4  400.11  4478.8  392.93    4745  376.76
  4796.7  371.56  4836.4  366.99  4863.1     363  4865.8   362.5  4869.1     363
  6456.5     363  6668.7     363  6772.3  363.55  6812.5  365.19  6913.6   369.6
  6932.5  370.59  7042.7  377.89  7101.7  384.98  7182.9  392.33  7245.3  393.53
#Mann= 15 ,-1 , 0
  2779.4     .05       0  3026.5     .16       0  3065.5      .1       0
  3137.8     .16       0  3344.5      .1       0    3400     .05       0
  3577.2     .16       0  4836.4     .05       0  4863.1    .033       0
  4869.1     .05       0  6456.5     .07       0  6668.7      .1       0
  6812.5     .16       0  6913.6     .05       0  7101.7      .1       0
Bank Sta=4796.7,6932.5
XS Rating Curve= 0 ,0
Exp/Cntr=0.3,0.1

Type RM Length L Ch R = 1 ,20175   ,758,758,758
BEGIN DESCRIPTION:
BIG CREEK 8.0
END DESCRIPTION:
XS GIS Cut Line= 4
      3541219.63     10520584.92      3539236.11     10521157.84
      3538823.78     10521179.55      3537649.76     10521122.66
#Sta/Elev= 30
  2738.7  424.29  2798.6  425.64  2893.2  424.74  3079.6  415.71  3230.1  411.15
  3429.4  404.13  3540.2  400.46  3632.3  399.61  3735.4  396.17  3766.6   391.4
  4035.7  392.25  4114.8  393.56  4304.3  390.11  4332.2  389.26  4365.8  385.46
  4404.7  385.88  4438.3  380.92  4471.9  377.88  4477.1  378.85  4549.6  370.95
  4638.9  364.07  4647.5     363  4650.2   362.5  4653.5     363  6081.4  363.46
  6103.3  365.04    6139  370.67  6181.2  376.23  6269.1  385.27  6391.6  393.25
#Mann= 11 ,-1 , 0
  2738.7     .16       0  3230.1     .05       0  3429.4     .16       0
  3632.3      .1       0  4035.7     .05       0  4304.3     .16       0
  4638.9     .05       0  4647.5    .033       0  4653.5     .05       0
  6081.4     .16       0  6181.2     .05       0
Bank Sta=4549.6,6139
XS Rating Curve= 0 ,0
Exp/Cntr=0.3,0.1

Type RM Length L Ch R = 1 ,19417   ,670,670,670
BEGIN DESCRIPTION:
BIG CREEK 7.1
END DESCRIPTION:
XS GIS Cut Line= 4
       3540821.5     10520108.07      3539293.69     10520198.35
      3538793.69      10520517.8      3537658.44     10521044.52
#Sta/Elev= 30
  3050.5  412.71  3340.4  408.69    3691  399.38  3861.3  398.83  3969.3  396.09
    4045     395  4105.3  391.25  4131.8  389.64  4201.9  390.25    4242  386.97
  4362.2  386.56  4472.4  377.48  4542.5   369.3 4593.75  370.12  4719.9     363
  4722.6   362.5  4725.9     363  4747.7     363  5794.1     363  5834.4  365.47
  5906.3  365.57  5977.3  370.12  5982.9  368.48  6000.2  370.84  6005.8  369.69
  6023.2   371.5    6080  367.31    6242  380.83  6354.8  391.05  6425.8   393.6
#Mann= 8 ,-1 , 0
  3050.5     .16       0  3969.3     .05       0  4105.3     .16       0
  4719.9    .033       0  4725.9     .16       0  4747.7     .05       0
  5906.3     .16       0    6242     .05       0
#XS Ineff= 2 , 0
                         6022.73          371.49
Permanent Ineff=
       F       F
Bank Sta=4593.75,6000.2
XS Rating Curve= 0 ,0
Exp/Cntr=0.3,0.1

Type RM Length L Ch R = 1 ,18747   ,738,738,738
BEGIN DESCRIPTION:
BIG CREEK 6.0
END DESCRIPTION:
XS GIS Cut Line= 3
      3539952.96     10519678.82      3538772.42     10519685.77
      3537523.14     10520907.29
#Sta/Elev= 30
  3581.7  395.83  3762.6  394.25  4122.6  385.37  4222.6  384.67  4362.6   386.7
  4422.6  386.17  4542.6  380.77  4662.6  372.24  4682.6  369.86  4752.6  367.08
  4780.8   363.4  4813.2     363  4815.9   362.5  4819.2     363  4821.4     363
    5658     363  5671.8     363  5763.7  370.62  5788.6   370.3  5848.6  374.11
    5891  372.02  6067.8  371.72  6081.9  372.35  6096.1  375.72  6117.2  377.49
  6258.8  386.85  6331.4  389.42  6364.8  389.07  6403.9   391.9  6509.5  392.93
#Mann= 9 ,-1 , 0
  3581.7     .16       0  4813.2    .033       0  4819.2     .16       0
  4821.4     .05       0    5658     .16       0  5788.6     .05       0
  6117.2     .16       0  6331.4     .05       0  6403.9      .1       0
#XS Ineff= 2 , 0
                         5864.49          373.87
Permanent Ineff=
       F       F
Bank Sta=4662.6,5763.7
XS Rating Curve= 0 ,0
Exp/Cntr=0.3,0.1

Type RM Length L Ch R = 1 ,18009   ,320,320,320
BEGIN DESCRIPTION:
BIG CREEK 6.1
END DESCRIPTION:
XS GIS Cut Line= 4
       3538709.9     10518664.96       3538140.1     10519150.03
      3537446.04     10520838.54      3537346.14     10521159.76
#Sta/Elev= 30
  4012.1  395.53  4204.3  395.26  4242.6   394.9    4285  392.66  4334.5  392.59
  4369.9  393.93  4419.3  394.11  4468.8  391.83  4625.8  374.91  4653.2  370.72
  4666.2  368.67  4675.2  367.04  4681.8  364.57  4689.5  364.35  4693.1     363
  4695.8   362.5  4699.1     363  5823.8     363  5978.4  366.11  6026.3  370.45
    6109  371.19  6239.6  377.79  6346.3  381.88  6399.6  382.56  6469.8  386.58
    6573  389.73  6574.2  389.73  6783.7   392.9    6879  390.94  6922.4  389.05
#Mann= 10 ,-1 , 0
  4012.1     .15       0  4204.3     .05       0  4334.5     .16       0
  4666.2     .05       0  4693.1    .033       0  4699.1     .05       0
  6469.8      .1       0    6573     .05       0  6574.2      .1       0
    6879     .05       0
Bank Sta=4653.2,6026.3
XS Rating Curve= 0 ,0
Exp/Cntr=0.3,0.1

Type RM Length L Ch R = 1 ,17689   ,564,564,564
BEGIN DESCRIPTION:
BIG CREEK 5.01
END DESCRIPTION:
XS GIS Cut Line= 3
      3538686.42     10518402.79      3537498.92     10519444.46
      3535179.53     10520298.61
#Sta/Elev= 30
  3795.1  398.57  3796.2  398.57  3846.9  398.53  3889.6  392.53  3953.2   394.7
  4139.2  391.35  4165.8  391.42  4222.7  380.33  4243.6  380.32  4252.5  378.05
  4275.5  377.35  4470.4  371.12    4548  365.25  4552.8     363  4555.5   362.5
  4558.8     363  6222.6     363    6295     363  6430.5     363  6713.1  363.86
  6776.4   364.5  6833.5  364.79  7129.7  370.32  7242.7  371.91  7300.2  374.59
  7409.4   374.6  7611.9  383.24  7753.5   391.8  7826.8  393.54  7846.4  394.12
#Mann= 16 ,-1 , 0
  3795.1     .05       0  3796.2     .15       0  4139.2      .1       0
  4252.5     .05       0  4275.5     .16       0    4548     .05       0
  4552.8    .033       0  4558.8     .05       0  6222.6     .12       0
    6295     .05       0  6430.5     .16       0  6713.1     .05       0
  6776.4     .12       0  6833.5     .05       0  7242.7      .1       0
  7826.8     .05       0
Bank Sta=4470.4,7129.7
XS Rating Curve= 0 ,0
Exp/Cntr=0.3,0.1