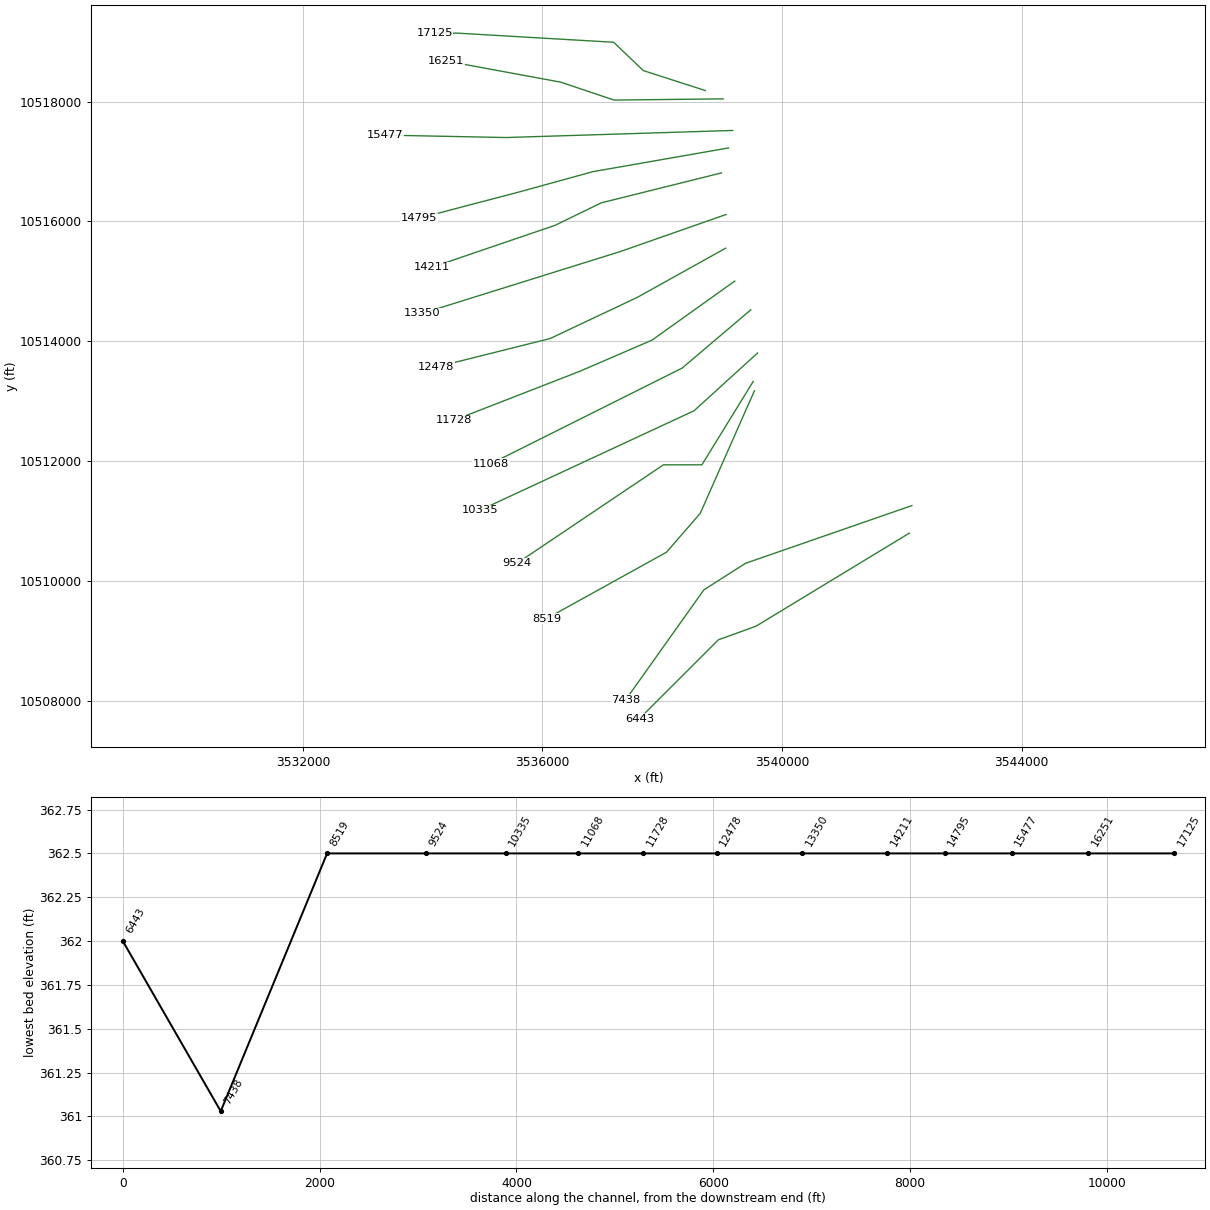
HEC-RAS study BIGELMCREEK.prj: BIG ELM CREEK Base Level Engineering

--- BIGELMCREEK.g01 (geometry) --- (continued)

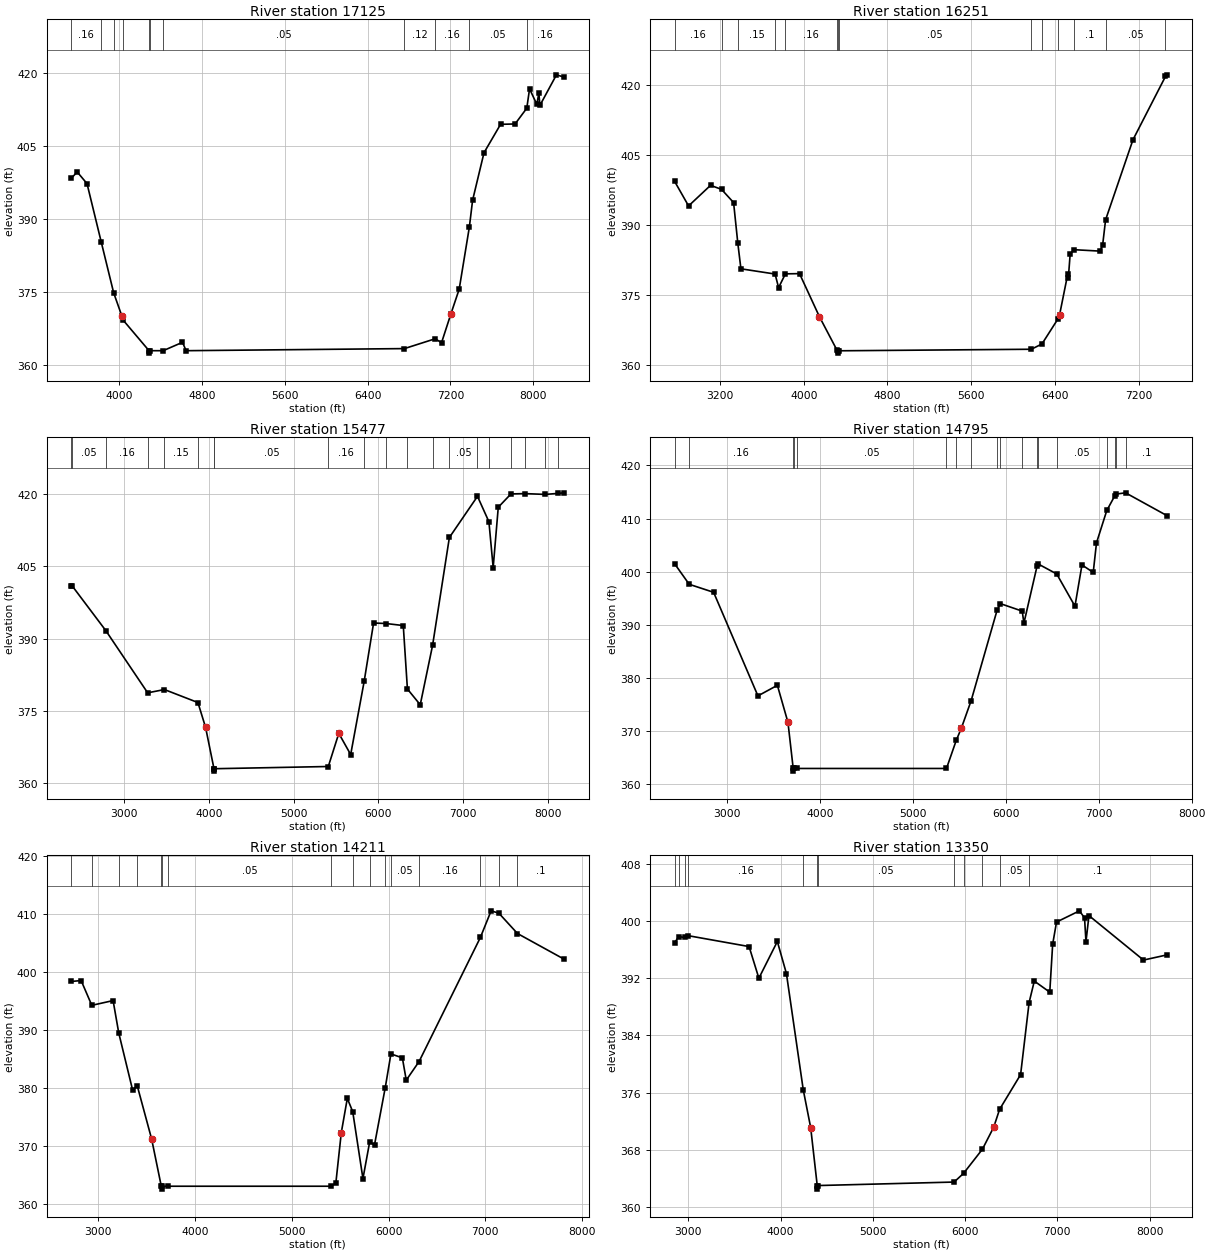
Type RM Length L Ch R = 1 ,17125   ,874,874,874
BEGIN DESCRIPTION:
BIG CREEK 5.0
END DESCRIPTION:
XS GIS Cut Line= 5
      3538716.88     10518185.76      3537682.15      10518519.1
      3537189.09     10518991.32      3534585.49     10519143.49
      3534200.35     10519145.85
#Sta/Elev= 30
  3534.4  398.42  3591.9  399.69  3686.5   397.3  3823.4  385.36    3944  374.89
  4021.9  370.21  4033.9  369.32    4286     363  4288.7   362.5    4292     363
  4422.7     363  4609.6  364.72  4644.6     363  6755.4  363.43  7053.2  365.45
  7114.3  364.63  7204.4  370.52  7285.1  375.63  7383.5  388.39  7414.8  393.89
    7525  403.64  7685.3  409.48  7825.5  409.55  7938.8  412.79  7965.6  416.76
  8035.6  413.58  8055.6  415.87  8065.6  413.36  8225.6  419.64  8297.4  419.18
#Mann= 11 ,-1 , 0
  3534.4     .16       0  3823.4     .05       0    3944     .16       0
  4033.9      .1       0    4286    .033       0    4292      .1       0
  4422.7     .05       0  6755.4     .12       0  7053.2     .16       0
  7383.5     .05       0  7938.8     .16       0
Bank Sta=4021.9,7204.4
XS Rating Curve= 0 ,0
Exp/Cntr=0.3,0.1

Type RM Length L Ch R = 1 ,16251   ,774,774,774
BEGIN DESCRIPTION:
BIG CREEK 4.2
END DESCRIPTION:
XS GIS Cut Line= 4
      3539015.53     10518046.88      3537196.04     10518026.04
      3536307.15     10518324.66      3534390.51     10518678.82
#Sta/Elev= 30
  2766.4  399.29  2899.8  394.03  3109.8  398.44  3214.5  397.58  3329.9  394.75
  3370.5     386  3399.9  380.56  3726.3  379.44  3759.9  376.53  3825.1  379.48
  3959.9  379.53  4149.9  370.31  4319.3  363.07  4326.9     363  4329.7   362.5
  4332.9     363  6175.1  363.33  6276.4  364.47  6429.7  369.85  6444.1  370.65
  6522.8  379.44  6527.9  378.49  6545.8  383.73  6580.3  384.66  6830.5  384.35
  6855.5  385.56  6884.2  391.05  7145.8   408.2  7456.3  421.76  7472.8  422.11
#Mann= 14 ,-1 , 0
  2766.4     .16       0  3214.5     .05       0  3370.5     .15       0
  3726.3     .05       0  3825.1     .16       0  4319.3     .05       0
  4326.9    .033       0  4332.9     .05       0  6175.1     .12       0
  6276.4      .1       0  6429.7     .05       0  6580.3      .1       0
  6884.2     .05       0  7456.3     .16       0
Bank Sta=4149.9,6444.1
XS Rating Curve= 0 ,0
Exp/Cntr=0.3,0.1

Type RM Length L Ch R = 1 ,15477   ,682,682,682
BEGIN DESCRIPTION:
BIG CREEK 3.3
END DESCRIPTION:
XS GIS Cut Line= 3
      3539175.17      10517519.1      3535390.48     10517401.04
      3533368.52     10517441.67
#Sta/Elev= 30
  2378.8     401  2390.2  400.94  2785.4  391.69  3279.4  378.76    3477  379.44
  3872.2  376.74  3962.6  371.57  4061.5     363  4064.3   362.5  4067.5     363
  5409.6  363.46  5533.4  370.34  5673.5  365.94  5832.3  381.12  5943.6  393.26
  6090.5  393.15  6293.7  392.73  6342.6  379.55  6493.8  376.28  6639.5  388.63
  6837.5  411.02  7168.9  419.56  7303.6  414.29  7353.9  404.78    7414   417.3
  7563.7  420.06  7728.2  420.13  7967.7  419.96  8124.1  420.18  8187.7  420.29
#Mann= 20 ,-1 , 0
  2378.8     .16       0  2390.2     .05       0  2785.4     .16       0
  3279.4      .1       0    3477     .15       0  3872.2     .16       0
  4061.5    .033       0  4067.5     .05       0  5409.6     .16       0
  5832.3     .05       0  6090.5     .15       0  6342.6     .05       0
  6639.5      .1       0  6837.5     .05       0  7168.9      .1       0
  7303.6     .05       0  7563.7      .1       0  7728.2     .16       0
  7967.7     .05       0  8124.1     .08       0
Bank Sta=3962.6,5533.4
XS Rating Curve= 0 ,0
Exp/Cntr=0.3,0.1

Type RM Length L Ch R = 1 ,14795   ,584,584,584
BEGIN DESCRIPTION:
BIG CREEK 2.3
END DESCRIPTION:
XS GIS Cut Line= 4
      3539105.78     10517227.44      3536841.87      10516831.6
      3535605.76     10516491.32      3533939.07     10516053.82
#Sta/Elev= 30
    2433   401.5  2590.1  397.64    2853  396.13  3330.1  376.65  3539.5  378.64
  3653.4  371.67  3709.9     363  3712.6   362.5  3715.9     363  3747.5     363
  5360.3     363    5466  368.32  5519.3  370.53  5625.8  375.76    5905  392.76
  5940.9     394  6175.7  392.59  6193.7  390.33  6336.5  401.14  6341.1  401.52
  6547.1  399.58  6743.4  393.52  6818.9  401.28  6940.1  399.87  6975.3  405.43
  7086.2  411.52  7170.9  414.23  7187.4  414.61  7288.6  414.84  7736.5  410.53
#Mann= 18 ,-1 , 0
    2433     .05       0  2590.1     .16       0  3709.9    .033       0
  3715.9     .16       0  3747.5     .05       0  5360.3      .1       0
    5466     .16       0  5625.8     .05       0    5905     .16       0
  5940.9     .05       0  6175.7     .16       0  6336.5     .05       0
  6341.1     .16       0  6547.1     .05       0  7086.2     .16       0
  7170.9     .08       0  7187.4     .16       0  7288.6      .1       0
Bank Sta=3653.4,5519.3
XS Rating Curve= 0 ,0
Exp/Cntr=0.3,0.1

Type RM Length L Ch R = 1 ,14211   ,861,861,861
BEGIN DESCRIPTION:
BIG CREEK 4.1
END DESCRIPTION:
XS GIS Cut Line= 4
      3538987.66     10516810.76      3536980.76     10516310.77
      3536209.92     10515935.77      3534160.24     10515236.62
#Sta/Elev= 30
  2721.2  398.36  2822.9  398.52  2933.2  394.24  3153.2  395.06  3211.9  389.45
  3354.6  379.63  3402.8  380.35  3551.4  371.16  3651.4     363  3654.2   362.5
  3657.4     363  3723.7     363  5402.5     363  5455.2  363.51  5511.9  372.27
    5574  378.17  5629.9  375.88  5735.5  364.32  5804.2  370.57  5855.6  370.19
  5966.2  380.04  6024.7  385.85  6142.9  385.17  6183.2  381.32  6315.9  384.54
  6949.3  405.96  7060.2  410.56  7140.5  410.15  7332.8  406.64  7812.3  402.23
#Mann= 16 ,-1 , 0
  2721.2     .05       0  2933.2      .1       0  3211.9     .05       0
  3402.8     .16       0  3651.4    .033       0  3657.4     .16       0
  3723.7     .05       0  5402.5      .1       0  5629.9     .16       0
  5804.2     .05       0  5966.2     .16       0  6024.7     .05       0
  6315.9     .16       0  6949.3      .1       0  7140.5     .16       0
  7332.8      .1       0
Bank Sta=3551.4,5511.9
XS Rating Curve= 0 ,0
Exp/Cntr=0.3,0.1

Type RM Length L Ch R = 1 ,13350   ,872,872,872
BEGIN DESCRIPTION:
BIG CREEK 3.2
END DESCRIPTION:
XS GIS Cut Line= 3
       3539064.1     10516116.33       3537300.2     10515498.27
      3533986.88     10514464.13
#Sta/Elev= 30
  2850.8  396.97  2895.3  397.83  2961.4  397.71  2998.7  397.96  3658.2  396.44
  3764.2  392.01  3964.5  397.15  4062.8  392.67  4245.4   376.4  4325.8  371.12
  4396.9     363  4399.7   362.5  4402.9     363  5880.5  363.49  5982.9   364.7
  6187.5  368.08  6310.2  371.17  6373.8  373.66  6601.6  378.52  6693.7   388.6
  6750.1  391.61  6917.8  390.06  6949.2  396.77  6991.1  399.87  7239.9  401.44
  7294.9  400.44  7310.2  397.12  7342.7  400.77  7933.9  394.55  8190.8  395.28
#Mann= 12 ,-1 , 0
  2850.8      .1       0  2895.3     .16       0  2961.4     .05       0
  2998.7     .16       0  4245.4     .05       0  4396.9    .033       0
  4402.9     .05       0  5880.5     .16       0  5982.9     .05       0
  6187.5     .16       0  6373.8     .05       0  6693.7      .1       0
Bank Sta=4325.8,6310.2
XS Rating Curve= 0 ,0
Exp/Cntr=0.3,0.1

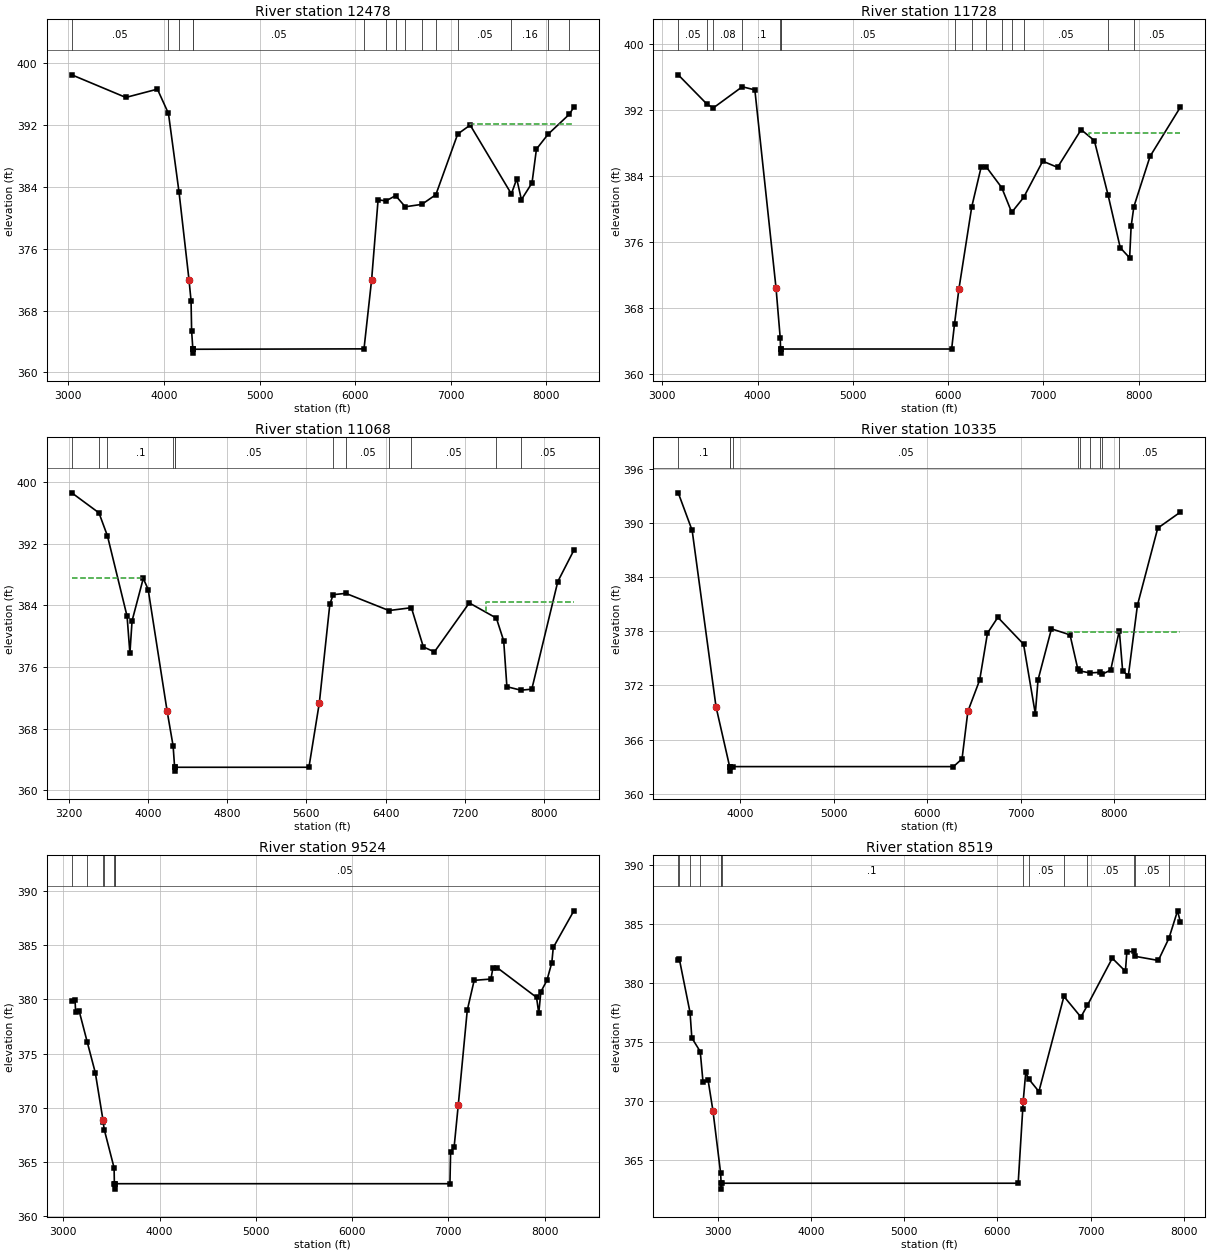
Type RM Length L Ch R = 1 ,12478   ,750,750,750
BEGIN DESCRIPTION:
BIG CREEK 2.2
END DESCRIPTION:
XS GIS Cut Line= 4
      3539057.19     10515553.84      3537584.92     10514734.38
      3536128.74     10514046.15      3534229.97     10513571.03
#Sta/Elev= 30
  3035.5  398.44  3600.9  395.52  3931.4  396.59  4047.1  393.45  4157.8  383.28
  4261.8     372  4283.5  369.26  4289.3  365.41  4302.3     363    4305   362.5
  4308.3     363  4308.8     363    6093  363.05  6172.5  371.96  6240.4  382.31
    6322  382.15  6423.5  382.84  6524.4   381.4  6697.9  381.71  6844.6  382.96
  7073.1  390.79  7203.8  391.95  7634.6  383.06    7691     385  7739.9  382.32
  7850.7  384.48  7897.1  388.85    8019  390.77  8242.2  393.36  8288.4  394.28
#Mann= 16 ,-1 , 0
  3035.5     .05       0  4047.1     .16       0  4157.8      .1       0
  4302.3    .033       0  4308.3      .1       0  4308.8     .05       0
    6093      .1       0    6322     .08       0  6423.5      .1       0
  6524.4     .05       0  6697.9      .1       0  6844.6     .16       0
  7073.1     .05       0  7634.6     .16       0    8019     .05       0
  8242.2     .08       0
#XS Ineff= 2 , 0
                            7200          392.09
Permanent Ineff=
       F       F
Bank Sta=4261.8,6172.5
XS Rating Curve= 0 ,0
Exp/Cntr=0.3,0.1

Type RM Length L Ch R = 1 ,11728   ,660,660,660
BEGIN DESCRIPTION:
BIG CREEK 1.2
END DESCRIPTION:
XS GIS Cut Line= 4
       3539209.9     10515005.19      3537827.98      10514019.1
      3536617.96     10513497.29       3534516.3     10512679.14
#Sta/Elev= 30
  3167.9  396.31  3472.8  392.71  3537.3   392.3  3839.9  394.86  3972.2  394.48
  4194.7  370.39  4238.9  364.29  4242.1     363  4244.8   362.5  4248.1     363
    6038     363  6068.1  366.03    6114  370.26  6249.4  380.29  6347.8   385.1
  6401.3  385.13  6564.1   382.6  6668.5   379.6  6793.5  381.41  6994.4  385.82
    7150  385.07  7397.4  389.65  7536.1  388.32  7679.7  381.73    7808  375.31
  7906.6  374.07  7922.2  377.89    7951  380.29  8121.2  386.41  8438.6  392.37
#Mann= 15 ,-1 , 0
  3167.9     .05       0  3472.8      .1       0  3537.3     .08       0
  3839.9      .1       0  4238.9     .05       0  4242.1    .033       0
  4248.1     .05       0  6068.1      .1       0  6249.4     .08       0
  6401.3     .16       0  6564.1     .05       0  6668.5     .16       0
  6793.5     .05       0  7679.7     .16       0    7951     .05       0
#XS Ineff= 2 , 0
                         7476.14          389.19
Permanent Ineff=
       F       F
Bank Sta=4194.7,6114
XS Rating Curve= 0 ,0
Exp/Cntr=0.3,0.1

Type RM Length L Ch R = 1 ,11068   ,733,733,733
BEGIN DESCRIPTION:
BIG CREEK 4.0
END DESCRIPTION:
XS GIS Cut Line= 3
      3539477.09     10514524.81      3538331.28     10513552.61
      3535138.25     10511956.09
#Sta/Elev= 30
    3230   398.6  3504.7     396  3590.8     393  3788.8  382.59  3817.3  377.79
  3839.3     382  3952.4   387.5  4001.9  386.06  4193.9  370.24    4254  365.76
  4269.1     363  4271.9   362.5  4275.1     363  5626.2     363  5731.1  371.35
  5837.4  384.17  5871.5  385.39  5998.3  385.56  6434.6  383.33  6661.4   383.7
  6782.1  378.61  6893.9  377.97  7246.1  384.32  7519.8  382.35  7593.9   379.4
  7626.2  373.45  7767.3     373  7877.8  373.13  8140.5  387.09  8302.6  391.15
#Mann= 12 ,-1 , 0
    3230     .05       0  3504.7     .08       0  3590.8      .1       0
    4254     .05       0  4269.1    .033       0  4275.1     .05       0
  5871.5     .08       0  5998.3     .05       0  6434.6     .15       0
  6661.4     .05       0  7519.8      .1       0  7767.3     .05       0
#XS Ineff= 2 , 0
         3951.14  387.53 7418.18          384.48
Permanent Ineff=
       F       F
Bank Sta=4193.9,5731.1
XS Rating Curve= 0 ,0
Exp/Cntr=0.3,0.1

Type RM Length L Ch R = 1 ,10335   ,811,811,811
BEGIN DESCRIPTION:
BIG CREEK 3.1
END DESCRIPTION:
XS GIS Cut Line= 3
      3539589.99     10513804.37      3538530.93      10512840.8
      3534963.18      10511182.8
#Sta/Elev= 30
  3337.7  393.31  3486.6  389.14  3741.4  369.63    3887     363  3889.8   362.5
    3893     363  3920.3     363  6279.4     363  6370.9  363.86  6433.3  369.12
  6559.6  372.59  6642.8  377.78  6753.7  379.53  7028.4  376.55  7153.9  368.86
  7183.1   372.6  7326.5  378.25    7525  377.59    7609  373.77  7631.1  373.59
  7738.2  373.37  7845.2  373.44  7863.5   373.2  7959.8  373.69  8051.9  378.06
  8087.4  373.59  8148.4  373.06  8245.5  380.87  8462.5   389.4  8703.7  391.17
#Mann= 10 ,-1 , 0
  3337.7      .1       0    3887    .033       0    3893      .1       0
  3920.3     .05       0    7609      .1       0  7631.1     .07       0
  7738.2     .05       0  7845.2     .07       0  7863.5     .16       0
  8051.9     .05       0
#XS Ineff= 2 , 0
                         7503.41          377.92
Permanent Ineff=
       F       F
Bank Sta=3741.4,6433.3
XS Rating Curve= 0 ,0
Exp/Cntr=0.3,0.1

Type RM Length L Ch R = 1 ,9524    ,1005,1005,1005
BEGIN DESCRIPTION:
BIG CREEK 2.1
END DESCRIPTION:
XS GIS Cut Line= 4
      3539517.88     10513330.75      3538661.14     10511938.02
      3538018.78     10511938.02      3535579.58     10510297.43
#Sta/Elev= 30
  3086.9  379.84  3120.9  379.95  3126.7  378.86  3163.4  378.93  3247.7  376.06
  3331.5  373.23  3410.8  368.89  3412.4  368.71    3425  367.97  3526.7  364.46
  3529.6     363  3532.4   362.5  3535.6     363  3536.1     363  7016.4     363
  7023.5  365.96  7059.7  366.36  7103.4  370.29  7196.4  378.99  7268.4  381.75
  7442.3  381.87  7463.3   382.9  7505.6  382.93  7916.3  380.18  7939.4  378.71
  7961.2  380.69  8024.3  381.75  8075.2  383.39  8090.2  384.78    8304  388.16
#Mann= 7 ,-1 , 0
  3086.9     .08       0  3247.7      .1       0  3412.4     .08       0
    3425      .1       0  3529.6    .033       0  3535.6      .1       0
  3536.1     .05       0
Bank Sta=3410.8,7103.4
XS Rating Curve= 0 ,0
Exp/Cntr=0.3,0.1

Type RM Length L Ch R = 1 ,8519    ,1081,1081,1081
BEGIN DESCRIPTION:
BIG CREEK 1.1
END DESCRIPTION:
XS GIS Cut Line= 4
       3539538.2     10513174.96       3538635.1     10511130.73
      3538070.86     10510479.69      3536070.58     10509372.53
#Sta/Elev= 30
  2577.4  381.92  2588.6  382.04  2704.1  377.48  2723.1  375.33  2813.2  374.17
  2843.4  371.55  2897.2  371.76  2949.3  369.16  3031.6  363.88  3037.2     363
  3039.9   362.5  3043.2     363  6221.8     363  6271.2  369.34  6275.6  369.95
  6303.1  372.42  6334.2  371.85    6444  370.78  6712.2  378.85    6894   377.1
  6963.1  378.08  7230.6  382.09  7371.5  380.98  7386.8  382.62  7461.5  382.68
  7475.2  382.25  7724.2   381.9  7838.8   383.8  7930.3  386.11    7960  385.18
#Mann= 14 ,-1 , 0
  2577.4     .05       0  2588.6     .08       0  2704.1      .1       0
  2813.2     .08       0  3031.6      .1       0  3037.2    .033       0
  3043.2      .1       0  6271.2      .1       0  6334.2     .05       0
  6712.2      .1       0  6963.1     .05       0  7461.5      .1       0
  7475.2     .05       0  7838.8     .08       0
Bank Sta=2949.3,6275.6
XS Rating Curve= 0 ,0
Exp/Cntr=0.3,0.1

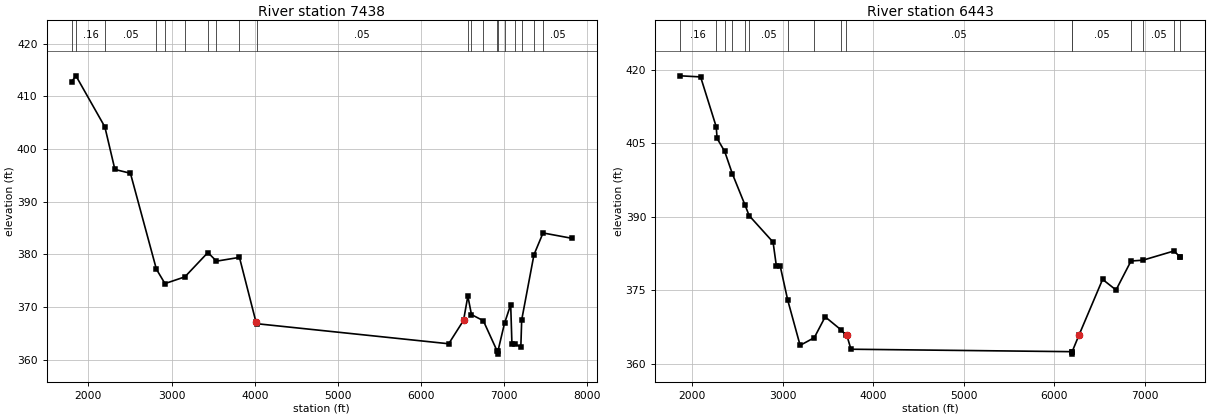
Type RM Length L Ch R = 1 ,7438    ,995,995,995
BEGIN DESCRIPTION:
BIG CREEK 3.0
END DESCRIPTION:
XS GIS Cut Line= 4
      3542166.38     10511257.48      3539388.57     10510293.93
      3538694.13     10509851.22      3537392.04     10508019.62
#Sta/Elev= 30
  1799.3  412.78  1850.6   413.9  2198.3   404.2  2318.9  396.11  2505.7  395.39
  2817.7  377.17  2920.9  374.43  3160.4  375.71  3437.1  380.33  3540.3  378.69
  3816.3  379.41    4016  367.07  4024.6  366.81    6332     363  6510.3  367.44
  6562.1  372.05  6605.7  368.54    6748  367.38  6916.8  361.53  6919.6  361.03
  6922.8  361.53  7002.8  366.89  7077.2  370.43    7092     363  7126.7     363
    7199  362.35  7209.3  367.52  7356.9  379.91  7465.9  384.05  7810.3  383.04
#Mann= 20 ,-1 , 0
  1799.3      .1       0  1850.6     .16       0  2198.3     .05       0
  2817.7     .08       0  2920.9      .1       0  3160.4     .05       0
  3437.1      .1       0  3540.3     .05       0  3816.3      .1       0
  4024.6     .05       0  6562.1     .16       0  6605.7     .05       0
    6748     .05       0  6916.8    .033       0  6922.8     .05       0
  7002.8      .1       0  7126.7     .16       0  7209.3     .05       0
  7356.9     .08       0  7465.9     .05       0
Bank Sta=4016,6510.3
XS Rating Curve= 0 ,0
Exp/Cntr=0.3,0.1

Type RM Length L Ch R = 1 ,6443    ,824,824,824
BEGIN DESCRIPTION:
BIG CREEK 2.0
END DESCRIPTION:
XS GIS Cut Line= 4
      3542122.92     10510797.38      3539562.18     10509243.58
      3538937.18     10509017.89      3537617.38     10507700.42
#Sta/Elev= 30
  1867.2  418.79  2090.4  418.57  2262.8   408.4  2272.6  406.02  2356.7  403.35
  2440.4  398.84  2583.1  392.33  2626.4  390.27    2891  384.86  2927.8  379.94
  2970.5  379.92  3052.4  373.06  3189.9  363.79  3346.7  365.36  3466.7  369.61
  3644.7  366.91  3692.2  365.95  3705.2  365.89  3751.4     363  6189.6   362.5
  6192.3     362  6195.6   362.5  6270.4  365.85    6532  377.25  6680.5  375.09
  6845.7     381  6977.5  381.17  7321.1  383.05  7383.7   381.9  7391.8  381.87
#Mann= 16 ,-1 , 0
  1867.2     .16       0  2262.8     .05       0  2356.7     .16       0
  2440.4     .05       0  2583.1      .1       0  2626.4     .05       0
  3052.4      .1       0  3346.7     .05       0  3644.7      .1       0
  3692.2     .05       0  6189.6    .033       0  6195.6     .05       0
  6845.7     .08       0  6977.5     .05       0  7321.1      .1       0
  7383.7     .05       0
Bank Sta=3705.2,6270.4
XS Rating Curve= 0 ,0
Exp/Cntr=0.3,0.1