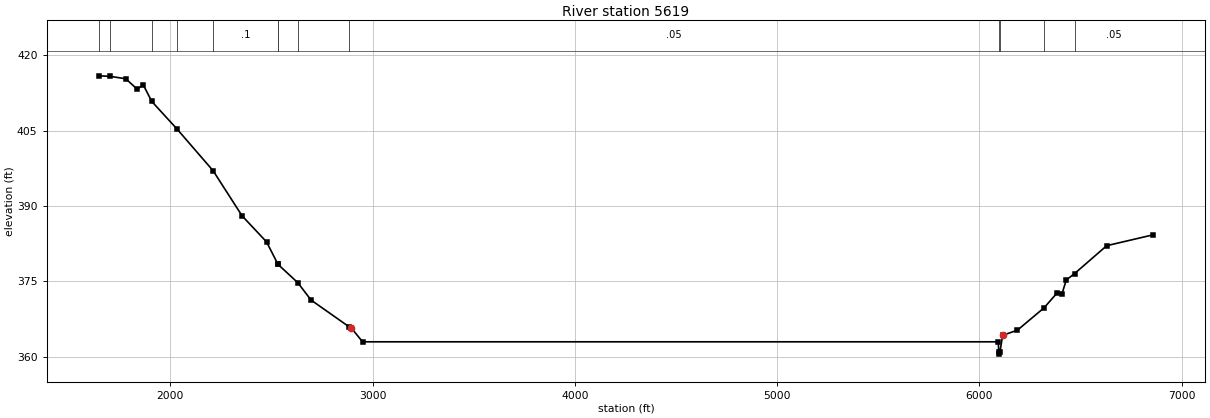
HEC-RAS study BIGELMCREEK.prj: BIG ELM CREEK Base Level Engineering

--- BIGELMCREEK.g01 (geometry) --- (continued)

Type RM Length L Ch R = 1 ,5619    ,0,0,0
BEGIN DESCRIPTION:
BIG CREEK 1.0
END DESCRIPTION:
XS GIS Cut Line= 3
      3542218.41     10510469.69      3540004.89     10508614.24
      3537977.28     10507486.59
#Sta/Elev= 30
  1648.7   415.9  1702.1  415.79  1779.4  415.32  1836.7  413.21  1865.3  414.15
  1907.9  410.81  2032.8  405.32  2211.3  397.02  2354.5  388.05  2475.5  382.87
  2531.8  378.42  2532.3  378.39  2629.7  374.77  2695.3  371.31  2883.4  365.99
  2894.4  365.75  2950.4     363  6093.2     363  6095.9  361.05  6098.7  360.55
  6101.9  361.05  6114.9  364.29  6187.9  365.31    6320  369.77    6386   372.8
  6407.7  372.45  6429.4  375.29  6470.9  376.58  6629.6  382.12  6857.1  384.26
#Mann= 13 ,-1 , 0
  1648.7     .16       0  1702.1     .05       0  1907.9      .1       0
  2032.8     .16       0  2211.3      .1       0  2531.8     .05       0
  2532.3     .08       0  2629.7      .1       0  2883.4     .05       0
  6095.9    .033       0  6101.9     .05       0    6320     .08       0
  6470.9     .05       0
Bank Sta=2894.4,6114.9
XS Rating Curve= 0 ,0
Exp/Cntr=0.3,0.1

Chan Stop Cuts=-1
Use User Specified Reach Order=0
Composite Channel Slope=5