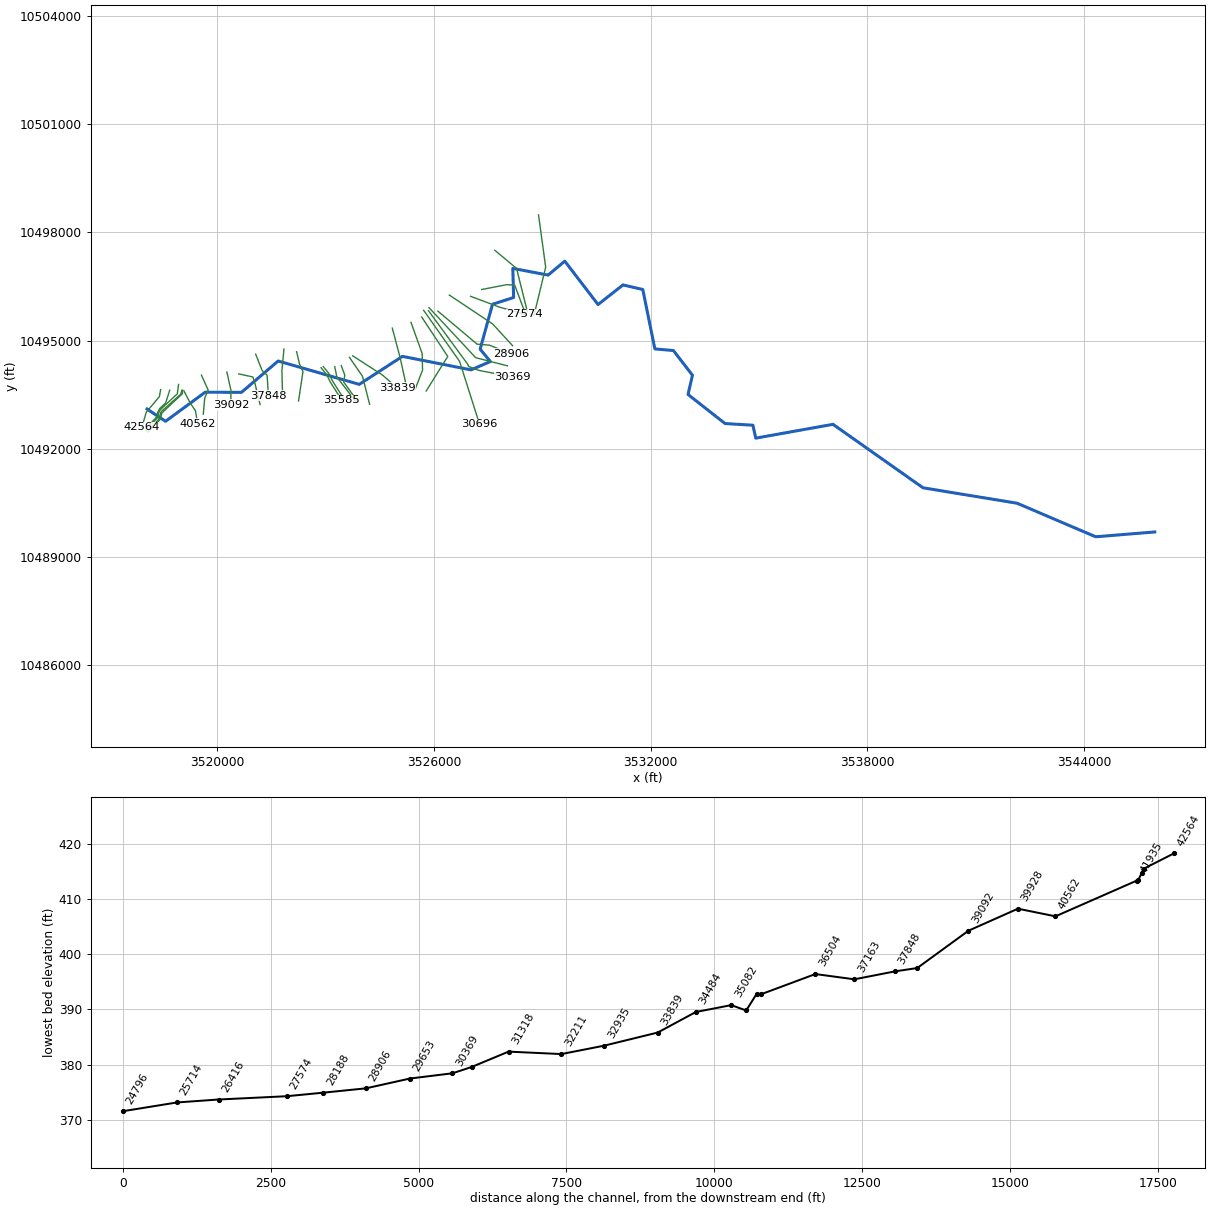
--- BLAINS CREEK.prj (project) ---

Proj Title=BLAINS CREEK Base Level Engineering
Current Plan=p01
Default Exp/Contr=0.3,0.1
English Units
Geom File=g01
Flow File=f01
Plan File=p01
Y Axis Title=Elevation
X Axis Title(PF)=Main Channel Distance
X Axis Title(XS)=Station
BEGIN DESCRIPTION:
BLAINS CREEK
END DESCRIPTION:
DSS Export Rating Curves= 0
DSS Export Rating Curve Sorted= 0
DSS Export Volume Flow Curves= 0
DXF OffsetX= 0
DXF OffsetY= 0
DXF ScaleX= 1
DXF ScaleY= 10

--- BLAINS CREEK.p01 (plan) ---

Plan Title=Multiple Run
Short Identifier=Multiple
Geom File=g01
Flow File=f01
Subcritical Flow
K Sum by GR= 0
Std Step Tol= 0.01
Critical Tol= 0.01
Num of Std Step Trials= 20
Max Error Tol= 0.3
Flow Tol Ratio= 0.001
Split Flow NTrial= 30
Split Flow Tol= 0.02
Split Flow Ratio= 0.02
Log Output Level= 0
Friction Slope Method= 1
Unsteady Friction Slope Method= 2
Unsteady Bridges Friction Slope Method= 1
Parabolic Critical Depth
Global Vel Dist=  1 , 1 , 1
Global Log Level= 0
CheckData=True
Encroach Param= -1, 0, 0, 0
BEGIN DESCRIPTION:
Multiple Run
END DESCRIPTION:

--- BLAINS CREEK.f01 (steady flow) ---

Flow Title=Multiple
Program Version=4.10
Number of Profiles= 7
Profile Names=10-year,25-year,50-year,1pct_min,100-year,1pct_plu,500-year
River Rch & RM=BLAINS CREEK,Reach-1         ,42564
    1386    1927    2377    2135    2887    3905    4252
River Rch & RM=BLAINS CREEK,Reach-1         ,37848
    1807    2548    3172    2875    3888    5258    5827
River Rch & RM=BLAINS CREEK,Reach-1         ,35335
    1900    2675    3327    3009    4069    5503    6077
River Rch & RM=BLAINS CREEK,Reach-1         ,30696
    2869    4113    5178    4736    6404    8661    9780
River Rch & RM=BLAINS CREEK,Reach-1         ,25714
    3173    4546    5720    5224    7064    9554   10759
River Rch & RM=BLAINS CREEK,Reach-1         ,14830
    3437    4928    6201    5663    7659   10358   11663
River Rch & RM=BLAINS CREEK,Reach-1         ,9327
    3520    5034    6324    5763    7794   10540   11820
River Rch & RM=BLAINS CREEK,Reach-1         ,6736
    3967    5687    7157    6530    8832   11944   13427
Boundary for River Rch & Prof#=BLAINS CREEK,Reach-1         , 1
Up Type= 0
Dn Type= 3
Dn Slope=0.001
Boundary for River Rch & Prof#=BLAINS CREEK,Reach-1         , 2
Up Type= 0
Dn Type= 3
Dn Slope=0.001
Boundary for River Rch & Prof#=BLAINS CREEK,Reach-1         , 3
Up Type= 0
Dn Type= 3
Dn Slope=0.001
Boundary for River Rch & Prof#=BLAINS CREEK,Reach-1         , 4
Up Type= 0
Dn Type= 3
Dn Slope=0.001
Boundary for River Rch & Prof#=BLAINS CREEK,Reach-1         , 5
Up Type= 0
Dn Type= 3
Dn Slope=0.001
Boundary for River Rch & Prof#=BLAINS CREEK,Reach-1         , 6
Up Type= 0
Dn Type= 3
Dn Slope=0.001
Boundary for River Rch & Prof#=BLAINS CREEK,Reach-1         , 7
Up Type= 0
Dn Type= 3
Dn Slope=0.001
DSS Import GetInterval= 0
DSS Import GetPeak= 0
DSS Import FillOption= 0

--- BLAINS CREEK.g01 (geometry) ---

Geom Title=Existing Conditions
Program Version=4.10

River Reach=BLAINS CREEK    ,Reach-1
Reach XY= 30
      3518052.11     10493101.64      3518563.97     10492761.43
      3519663.65     10493568.68      3520666.72     10493563.55
      3521682.38     10494432.15      3523927.11     10493785.45
      3525123.16     10494560.44      3527022.67     10494187.09
      3527558.28      10494418.7      3527275.22     10494759.54
      3527617.16     10496004.16      3528201.74     10496192.27
      3528179.95     10496998.15       3529156.4      10496813.3
       3529618.6     10497199.67      3530539.63     10495996.76
      3531229.78     10496539.91      3531778.49       10496414.
       3532113.1     10494767.54      3532626.78     10494722.47
      3533153.73     10494037.91      3533030.78     10493505.13
      3534056.74     10492699.29      3534827.06     10492653.46
      3534906.74     10492295.39      3537045.33     10492677.92
      3539537.53     10490919.25      3542142.11     10490491.64
      3544317.97     10489562.46      3545954.16     10489695.86

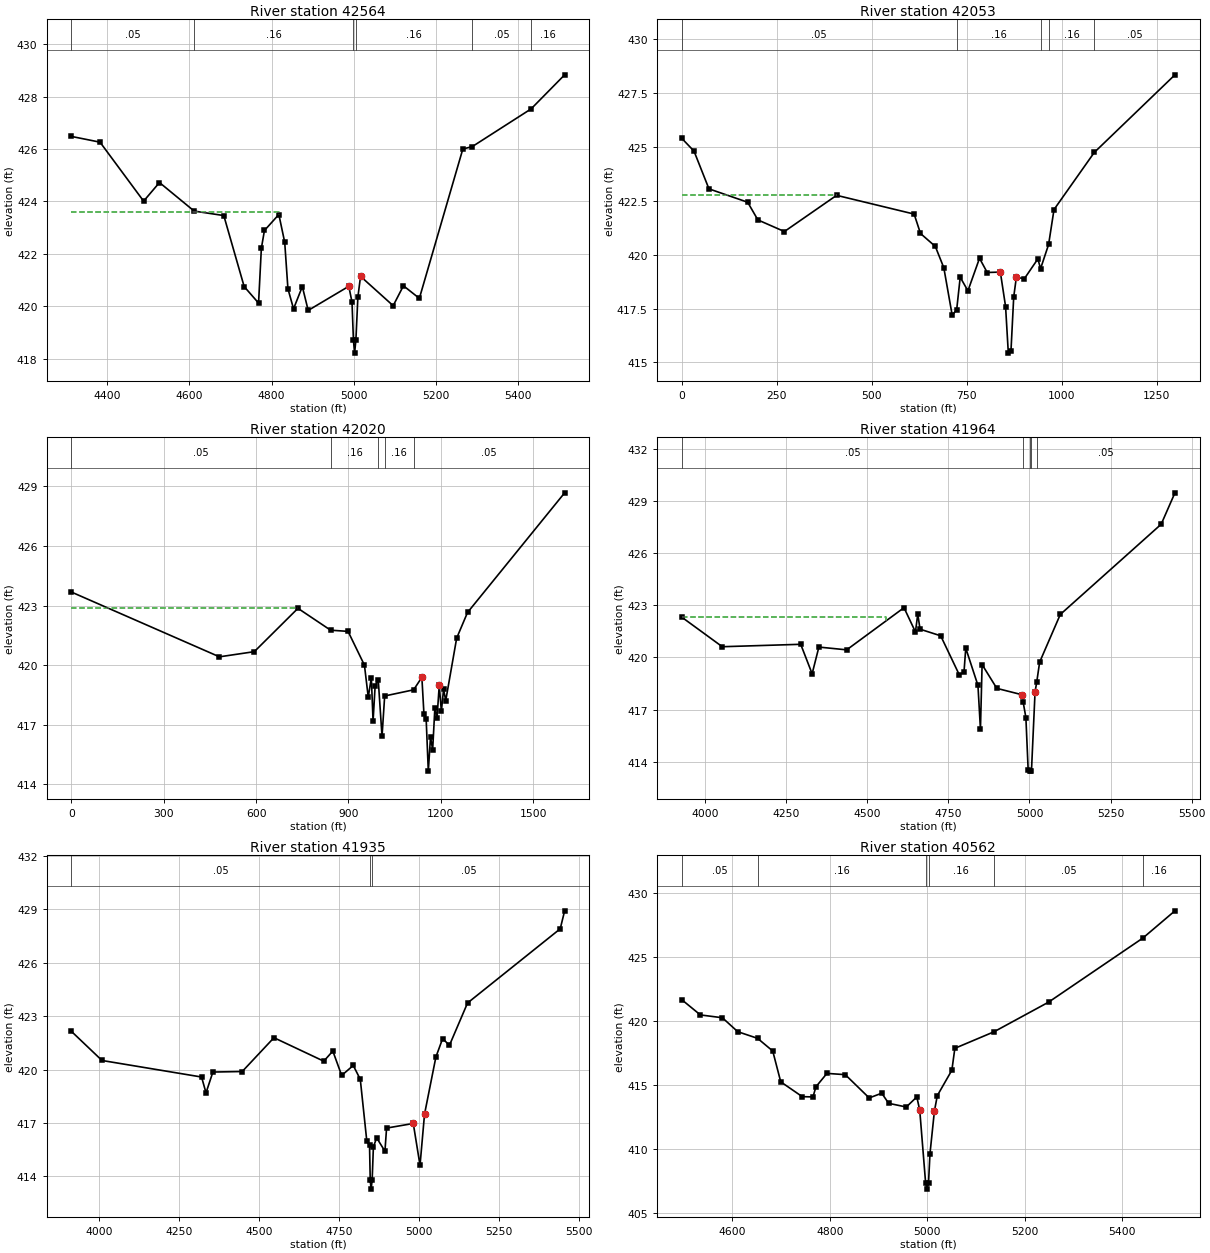
Type RM Length L Ch R = 1 ,42564   ,511,511,511
BEGIN DESCRIPTION:
BLAINS CREEK 44.02
END DESCRIPTION:
XS GIS Cut Line= 4
      3518429.06     10493639.01      3518393.41     10493444.84
       3518029.8      10493012.4       3517907.4     10492590.51
#Sta/Elev= 30
  4312.2  426.48  4382.1  426.26  4488.3  424.01  4526.9  424.72  4611.5  423.63
  4683.6  423.46  4733.2  420.75  4768.3  420.12  4775.1  422.21  4782.6  422.89
  4817.7   423.5    4832  422.44  4839.8  420.67  4853.5   419.9  4874.9  420.75
  4889.2  419.84  4988.1  420.76  4995.9  420.16  4999.4  418.71  5002.2  418.21
  5005.4  418.71  5010.2  420.34  5016.7  421.14  5096.2  420.02  5121.2  420.78
    5160   420.3  5265.9     426  5288.8  426.09  5432.2  427.53  5513.9  428.83
#Mann= 6 ,-1 , 0
  4312.2     .05       0  4611.5     .16       0  4999.4     .07       0
  5005.4     .16       0  5288.8     .05       0  5432.2     .16       0
#XS Ineff= 2 , 0
         4817.52  423.58
Permanent Ineff=
       F       F
Bank Sta=4988.1,5016.7
XS Rating Curve= 0 ,0
Exp/Cntr=0.3,0.1

Type RM Length L Ch R = 1 ,42053   ,33,33,33
BEGIN DESCRIPTION:
BLAINS CREEK 44.01
END DESCRIPTION:
XS GIS Cut Line= 6
      3518679.74     10493622.74      3518567.98     10493272.26
      3518399.59     10493111.36      3518347.51     10493007.19
      3518326.68       10492890.      3518006.36     10492556.67
#Sta/Elev= 30
       0   425.4    32.6   424.8    71.9  423.05   173.8  422.43   200.6  421.61
   270.4  421.07   407.8  422.75   611.8  421.88   628.5  420.98   667.5  420.38
   689.9  419.39   711.9  417.19   723.7  417.44     733  418.95   753.3  418.32
   783.8  419.83   804.1  419.17   838.6  419.19   852.4  417.59   859.6  415.43
   866.6  415.54   873.8  418.04   880.7  418.94   902.1  418.89   937.3   419.8
   944.5  419.35   965.6  420.47   979.8  422.09  1085.8  424.74    1298  428.34
#Mann= 5 ,-1 , 0
       0     .05       0   723.7     .16       0   944.5     .07       0
   965.6     .16       0  1085.8     .05       0
#XS Ineff= 2 , 0
          408.86  422.77
Permanent Ineff=
       F       F
Bank Sta=838.6,880.7
XS Rating Curve= 0 ,0
Exp/Cntr=0.3,0.1

Type RM Length L Ch R = 1 ,42020   ,56,56,56
BEGIN DESCRIPTION:
BLAINS CREEK 44.0
END DESCRIPTION:
XS GIS Cut Line= 6
       3518925.3     10493782.66      3518889.99     10493522.41
      3518420.43     10493085.32      3518368.34     10492981.15
      3518347.51     10492863.96       3518027.2     10492530.63
#Sta/Elev= 30
       0  423.68   480.9  420.42   594.2  420.68   735.9  422.86   841.9  421.76
   898.6   421.7   951.8     420   964.2  418.39   974.2  419.37   979.8  417.18
   986.5  418.95   996.6  419.27  1008.9  416.42  1017.5  418.45  1111.5  418.76
  1138.3  419.39    1145  417.55  1152.2   417.3  1159.2  414.67  1166.4  416.39
  1173.3  415.74  1180.5  417.85  1187.5  417.35  1194.7  418.98  1201.6  417.69
  1208.8  418.78  1215.8  418.22  1251.3  421.36  1286.5  422.65  1601.9  428.67
#Mann= 5 ,-1 , 0
       0     .05       0   841.9     .16       0   996.6     .07       0
  1017.5     .16       0  1111.5     .05       0
#XS Ineff= 2 , 0
          735.34  422.89
Permanent Ineff=
       F       F
Bank Sta=1138.3,1194.7
XS Rating Curve= 0 ,0
Exp/Cntr=0.3,0.1

Type RM Length L Ch R = 1 ,41964   ,29,29,29
BEGIN DESCRIPTION:
BLAINS CREEK 43.0
END DESCRIPTION:
XS GIS Cut Line= 6
      3519019.98     10493623.55      3518981.23     10493509.49
      3518468.26     10493051.85      3518426.59     10492998.03
      3518391.87     10492827.89      3518058.01     10492495.77
#Sta/Elev= 30
  3927.4  422.33  4052.8  420.62  4294.6  420.76  4329.8  419.06  4350.6   420.6
  4436.4  420.44  4613.1  422.87  4648.4  421.47  4655.5   422.5  4662.6  421.63
  4726.2  421.25  4783.6     419  4798.1  419.16  4803.5  420.54  4841.1  418.39
  4848.8  415.86  4853.9  419.59  4899.3  418.22  4977.6  417.85  4980.2  417.46
  4988.9  416.54    4996  413.49  5000.1  413.45  5006.1  413.45  5017.2  418.02
  5022.2  418.56  5031.3  419.73    5095  422.48  5406.1  427.68  5448.5  429.49
#Mann= 5 ,-1 , 0
  3927.4     .05       0  4980.2     .16       0  5000.1     .07       0
  5006.1     .16       0  5022.2     .05       0
#XS Ineff= 2 , 0
         4557.84  422.36
Permanent Ineff=
       F       F
Bank Sta=4977.6,5017.2
XS Rating Curve= 0 ,0
Exp/Cntr=0.3,0.1

Type RM Length L Ch R = 1 ,41935   ,1373,1373,1373
BEGIN DESCRIPTION:
BLAINS CREEK 42.0
END DESCRIPTION:
XS GIS Cut Line= 6
      3519034.04     10493619.91      3519030.92     10493526.69
       3518494.3     10493022.34      3518457.84      10492977.2
      3518421.38     10492817.48      3518078.38     10492465.81
#Sta/Elev= 30
  3913.1  422.15    4009  420.51  4320.4  419.58  4334.3  418.69  4355.8  419.86
  4447.6  419.89  4546.8  421.79  4702.6  420.47  4730.9  421.04  4758.6  419.67
  4794.8  420.23  4816.8  419.45  4837.3  415.96  4845.7  415.76  4847.9  413.78
  4850.6  413.28  4853.9  413.78  4857.8  415.66  4868.1  416.16  4893.9  415.41
    4899  416.71  4982.5  416.97  5003.6  414.62  5017.7  417.49  5053.2   420.7
  5074.3  421.74  5095.6  421.36  5152.2  423.74  5442.1  427.91  5455.9  428.92
#Mann= 3 ,-1 , 0
  3913.1     .05       0  4847.9    .035       0  4853.9     .05       0
#XS Ineff= 2 , 0
         4546.59  421.78
Permanent Ineff=
       F       F
Bank Sta=4982.5,5017.7
XS Rating Curve= 0 ,0
Exp/Cntr=0.3,0.1

Type RM Length L Ch R = 1 ,40562   ,634,634,634
BEGIN DESCRIPTION:
BLAINS CREEK 40.0
END DESCRIPTION:
XS GIS Cut Line= 4
      3519072.25     10493605.73      3519251.65     10493263.05
      3519392.11     10493054.71      3519455.58      10492686.2
#Sta/Elev= 30
    4496  421.65  4534.5  420.45  4579.6  420.23  4611.1  419.14  4651.8  418.62
  4682.9  417.63  4699.3  415.22  4743.5  414.06  4765.5  414.04  4771.5  414.83
  4794.1  415.88  4831.7  415.78  4880.8  413.96  4906.5  414.33  4920.7  413.54
  4956.9  413.25  4978.5  414.04  4984.5  412.99  4996.5  407.33  4999.2  406.83
  5002.5  407.33  5005.5  409.61  5014.5  412.91  5020.5  414.14  5050.4  416.13
  5056.5  417.84  5136.7  419.13  5248.8  421.45  5442.2  426.46    5508  428.59
#Mann= 6 ,-1 , 0
    4496     .05       0  4651.8     .16       0  4996.5     .07       0
  5002.5     .16       0  5136.7     .05       0  5442.2     .16       0
Bank Sta=4984.5,5014.5
XS Rating Curve= 0 ,0
Exp/Cntr=0.3,0.1

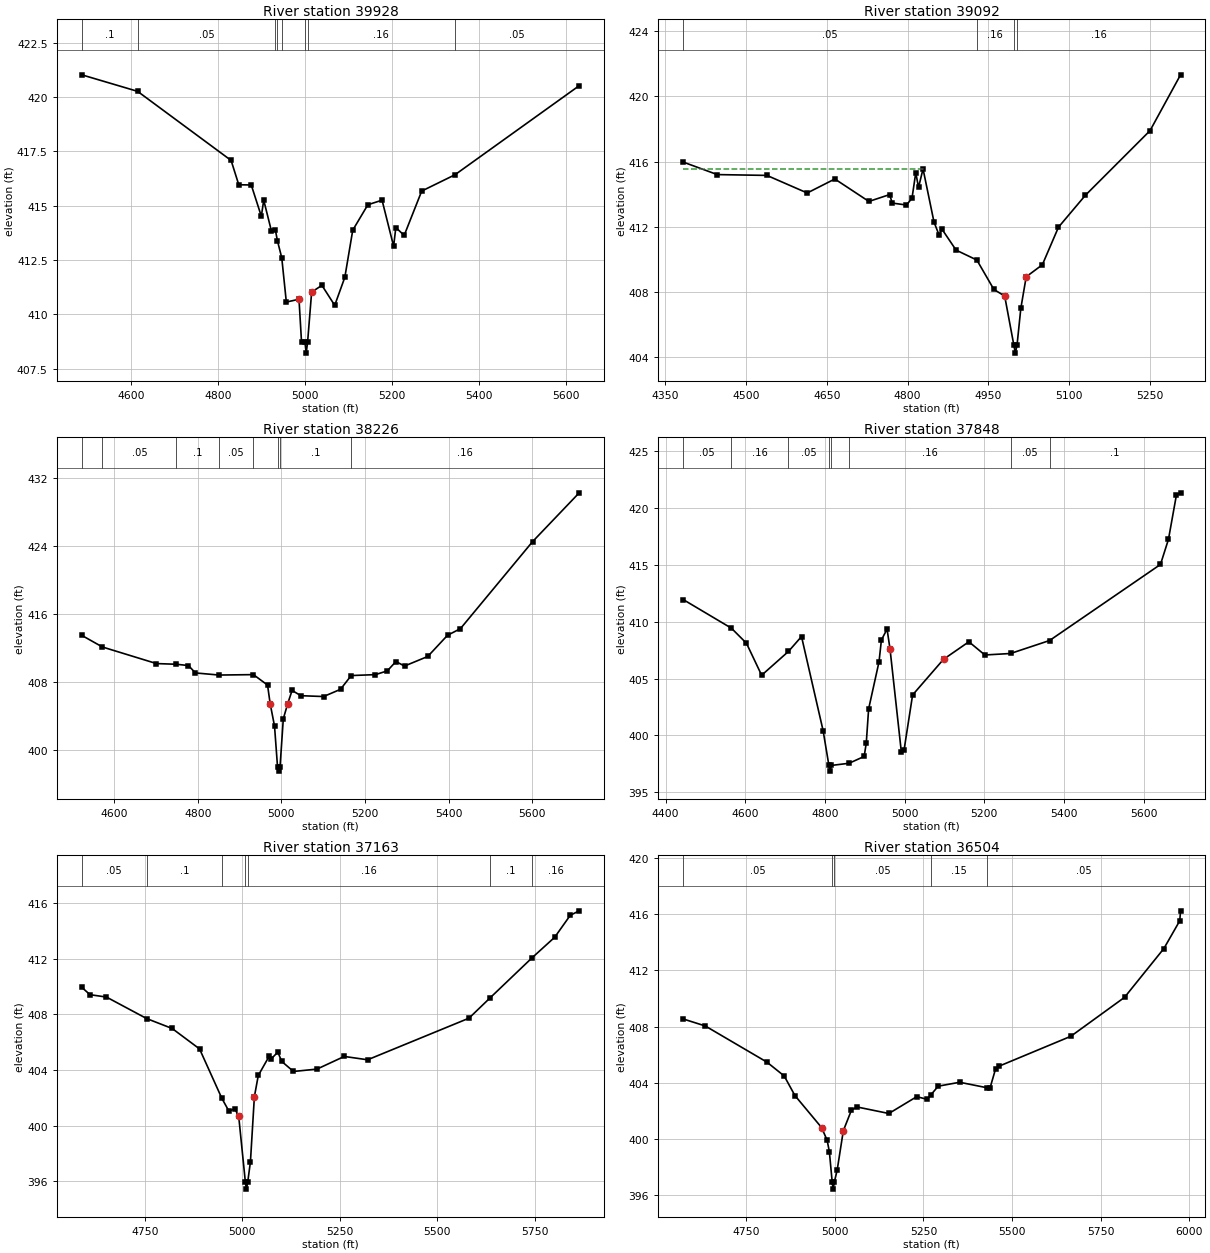
Type RM Length L Ch R = 1 ,39928   ,836,836,836
BEGIN DESCRIPTION:
BLAINS CREEK 39.0
END DESCRIPTION:
XS GIS Cut Line= 4
      3519557.66     10494042.08      3519744.28     10493627.63
      3519648.79      10493404.1      3519609.73     10492961.42
#Sta/Elev= 30
  4487.4  421.02  4615.5  420.26  4830.2  417.08  4847.8  415.96  4876.5  415.95
  4899.6  414.51  4905.1  415.25  4922.8  413.83  4931.7  413.89  4936.7  413.37
  4946.5   412.6    4957  410.56  4986.1  410.69  4991.9  408.72  4999.8  408.71
  5002.6  408.21  5005.8  408.71  5015.1  411.02  5038.7  411.33  5068.1  410.41
  5091.3   411.7  5109.5  413.87  5144.2  415.04  5176.8  415.25  5203.3  413.13
  5208.4  413.99  5227.6  413.63  5267.8  415.67  5344.2  416.42  5629.4  420.52
#Mann= 8 ,-1 , 0
  4487.4      .1       0  4615.5     .05       0  4931.7     .16       0
  4936.7      .1       0  4946.5     .16       0  4999.8     .07       0
  5005.8     .16       0  5344.2     .05       0
Bank Sta=4986.1,5015.1
XS Rating Curve= 0 ,0
Exp/Cntr=0.3,0.1

Type RM Length L Ch R = 1 ,39092   ,866,866,866
BEGIN DESCRIPTION:
BLAINS CREEK 38.0
END DESCRIPTION:
XS GIS Cut Line= 3
      3520262.93     10494126.79      3520375.79     10493618.95
      3520371.46      10493214.9
#Sta/Elev= 30
    4383  415.97  4446.5   415.2  4538.7  415.15  4613.6  414.07  4664.9  414.93
  4728.2  413.55  4766.6  413.97  4771.7  413.45    4798  413.33  4808.3  413.75
  4815.3  415.32  4820.4  414.41  4828.8  415.55  4849.2  412.28  4858.8  411.47
  4863.9  411.85  4890.2  410.56  4928.8  409.95  4960.5  408.14  4980.5  407.74
  4997.5  404.73  5000.3  404.23  5003.5  404.73  5010.5  406.98  5020.5  408.92
  5050.5  409.66  5080.5  411.97  5130.5  413.93  5250.6   417.9  5307.3  421.33
#Mann= 4 ,-1 , 0
    4383     .05       0  4928.8     .16       0  4997.5     .07       0
  5003.5     .16       0
#XS Ineff= 2 , 0
         4829.32  415.53
Permanent Ineff=
       F       F
Bank Sta=4980.5,5020.5
XS Rating Curve= 0 ,0
Exp/Cntr=0.3,0.1

Type RM Length L Ch R = 1 ,38226   ,378,378,378
BEGIN DESCRIPTION:
BLAINS CREEK 37.0
END DESCRIPTION:
XS GIS Cut Line= 4
      3520592.76     10494074.69      3520983.99     10493989.69
      3521039.85     10493814.26      3521182.75     10493225.32
#Sta/Elev= 30
  4522.3  413.46  4571.8  412.09  4701.1  410.14  4748.7  410.06  4777.5  409.91
  4794.3  409.04  4850.8  408.79  4933.1  408.84  4966.9  407.61  4973.1  405.43
  4983.6  402.78  4990.8  397.98  4993.6  397.48  4996.8  397.98  5004.6  403.64
  5015.1  405.41  5025.6  406.98  5046.6  406.36    5101  406.26  5141.5  407.11
  5167.1  408.73  5225.1  408.84  5253.5  409.28  5274.1  410.38  5294.7  409.85
  5350.4  410.98  5397.6  413.47  5428.5  414.25  5601.1  424.49  5712.8  430.24
#Mann= 8 ,-1 , 0
  4522.3      .1       0  4571.8     .05       0  4748.7      .1       0
  4850.8     .05       0  4933.1      .1       0  4990.8     .07       0
  4996.8      .1       0  5167.1     .16       0
Bank Sta=4973.1,5015.1
XS Rating Curve= 0 ,0
Exp/Cntr=0.3,0.1

Type RM Length L Ch R = 1 ,37848   ,685,685,685
BEGIN DESCRIPTION:
BLAINS CREEK 36.2
END DESCRIPTION:
XS GIS Cut Line= 4
      3521059.12     10494625.05      3521238.95     10494167.31
      3521376.22     10494039.96      3521413.11      10493471.4
#Sta/Elev= 30
  4444.2  411.94  4565.5  409.42  4603.2   408.1  4641.3  405.29  4708.6  407.38
  4741.4  408.69  4795.6  400.43  4810.2  397.37  4812.9  396.87  4816.2  397.37
  4860.8  397.56  4898.7  398.16    4904  399.34  4909.9  402.33    4936  406.47
    4942  408.39  4956.2  409.34  4963.6   407.6  4991.9  398.59  4998.7  398.69
  5020.3  403.56  5097.9  406.69  5161.6  408.23  5201.7  407.07  5266.1   407.2
  5364.2  408.34  5642.6  415.02  5662.7  417.23  5682.7  421.13    5693  421.31
#Mann= 8 ,-1 , 0
  4444.2     .05       0  4565.5     .16       0  4708.6     .05       0
  4810.2     .07       0  4816.2     .05       0  4860.8     .16       0
  5266.1     .05       0  5364.2      .1       0
Bank Sta=4963.6,5097.9
XS Rating Curve= 0 ,0
Exp/Cntr=0.3,0.1

Type RM Length L Ch R = 1 ,37163   ,659,659,659
BEGIN DESCRIPTION:
BLAINS CREEK 36.0
END DESCRIPTION:
XS GIS Cut Line= 3
       3521842.8     10494762.63      3521786.38     10494167.99
      3521803.74     10493488.73
#Sta/Elev= 30
  4587.7  409.95  4608.8  409.42    4651  409.25  4754.5   407.7  4819.7  406.99
    4890  405.52  4947.2  401.97  4965.5  401.04  4980.4  401.23  4990.5  400.67
  5007.6  395.94  5010.3  395.44  5013.6  395.94  5020.6  397.41  5030.7  402.08
  5040.7  403.61  5068.6  404.99  5073.7   404.8  5090.9  405.29    5101  404.62
  5131.1   403.9  5191.4  404.07  5261.4  404.98  5321.4  404.74  5581.5  407.73
  5635.7  409.19    5743  412.06  5801.6  413.55  5841.6  415.13  5864.5  415.45
#Mann= 7 ,-1 , 0
  4587.7     .05       0  4754.5      .1       0  4947.2     .16       0
  5007.6     .07       0  5013.6     .16       0  5635.7      .1       0
    5743     .16       0
Bank Sta=4990.5,5030.7
XS Rating Curve= 0 ,0
Exp/Cntr=0.3,0.1

Type RM Length L Ch R = 1 ,36504   ,919,919,919
BEGIN DESCRIPTION:
BLAINS CREEK 36.1
END DESCRIPTION:
XS GIS Cut Line= 4
      3522193.06      10494689.2      3522274.66     10494345.94
      3522370.14     10494141.95      3522246.65     10493325.19
#Sta/Elev= 30
  4571.5  408.54    4634  408.04  4807.9  405.46  4856.8  404.47  4887.1  403.07
  4962.2  400.79    4978  399.88  4984.3  399.06  4992.3  396.89  4995.1  396.39
  4998.3  396.89  5006.4  397.76  5023.7  400.56  5046.5  402.02  5061.6  402.26
  5152.2  401.79  5230.8  402.99  5261.1   402.8  5271.5  403.14  5291.5  403.74
  5352.1  404.02  5428.9  403.63  5437.8  403.61  5453.3  404.96  5463.4  405.17
  5665.7   407.3  5817.4  410.08  5928.6  413.57  5973.4  415.55  5975.6  416.26
#Mann= 5 ,-1 , 0
  4571.5     .05       0  4992.3     .03       0  4998.3     .05       0
  5271.5     .15       0  5428.9     .05       0
Bank Sta=4962.2,5023.7
XS Rating Curve= 0 ,0
Exp/Cntr=0.3,0.1

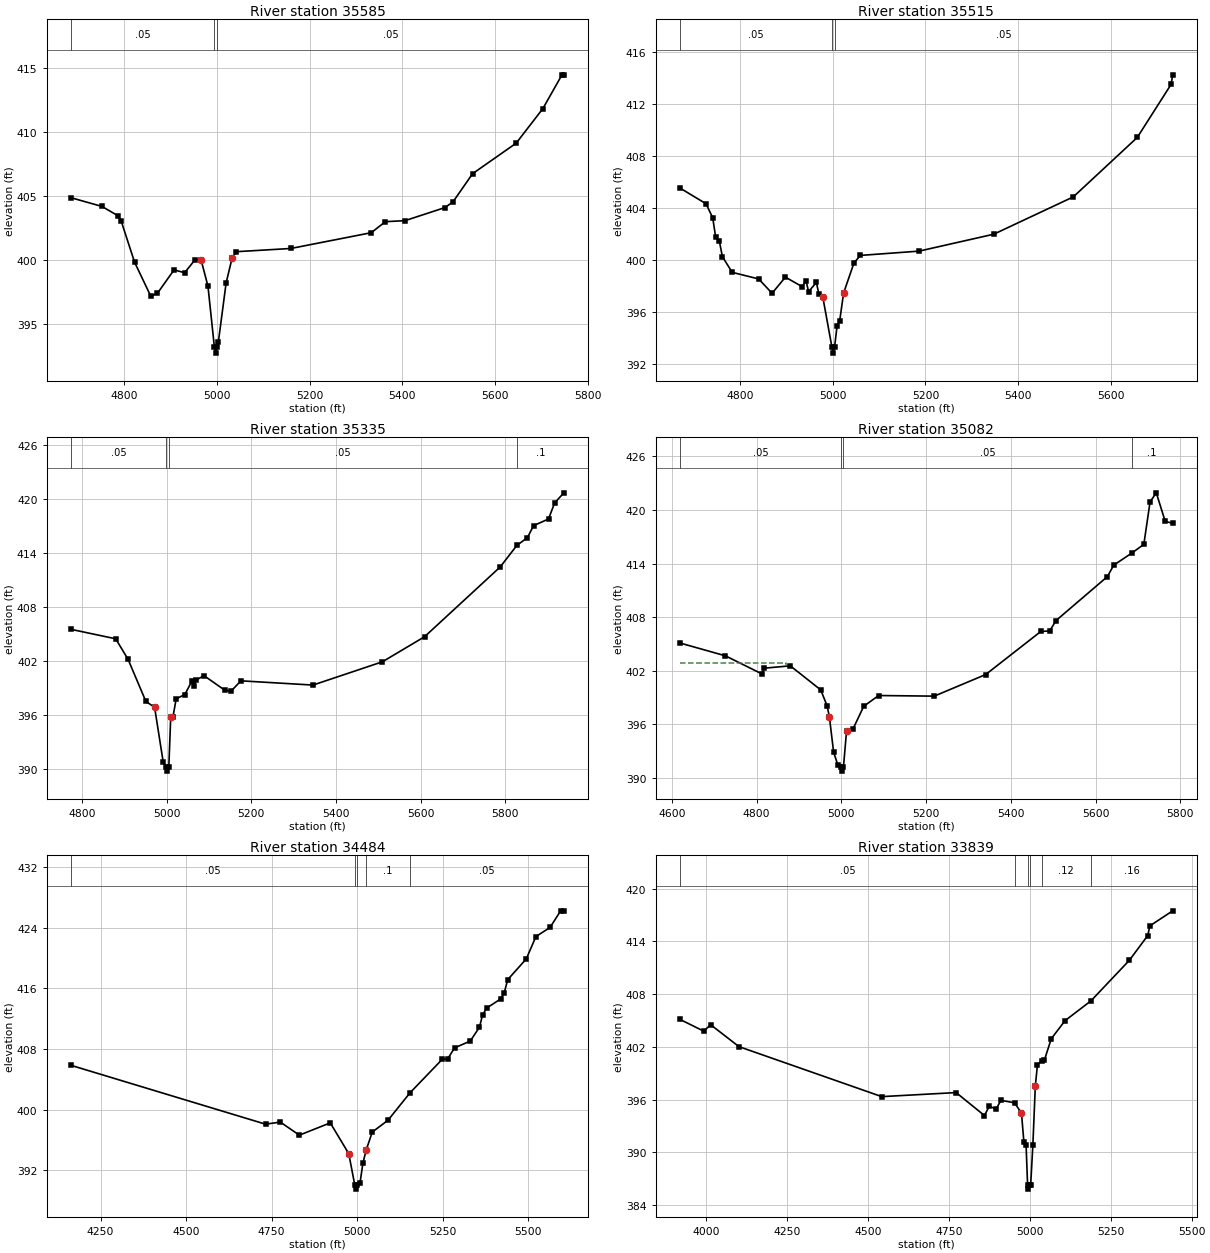
Type RM Length L Ch R = 1 ,35585   ,70,70,70
BEGIN DESCRIPTION:
BLAINS CREEK 35.1
END DESCRIPTION:
XS GIS Cut Line= 4
       3522872.5      10494244.2      3523023.36     10494057.32
      3523131.86      10493840.3       3523442.2     10493349.84
#Sta/Elev= 30
  4685.5  404.84  4751.6  404.17  4786.8  403.43  4793.2  403.03    4822  399.83
  4857.2  397.16  4871.5   397.4  4907.3  399.22  4930.2     399  4952.6  400.01
  4965.6  400.01  4980.5  397.95  4994.3  393.23  4997.1  392.73  5000.3  393.23
  5002.9  393.58  5019.7   398.2  5032.6  400.14    5042  400.64  5159.4  400.89
    5333  402.12  5363.5  402.98  5405.9  403.06  5492.1  404.08  5509.4  404.52
  5551.7  406.72  5645.8   409.1  5703.5   411.8  5744.7  414.43  5748.7  414.43
#Mann= 3 ,-1 , 0
  4685.5     .05       0  4994.3     .03       0  5000.3     .05       0
Bank Sta=4965.6,5032.6
XS Rating Curve= 0 ,0
Exp/Cntr=0.3,0.1

Type RM Length L Ch R = 1 ,35515   ,180,180,180
BEGIN DESCRIPTION:
BLAINS CREEK 35.0
END DESCRIPTION:
XS GIS Cut Line= 4
       3522931.1     10494278.91      3523081.95     10494092.04
      3523190.46     10493875.02      3523500.11     10493385.65
#Sta/Elev= 30
  4671.3  405.55  4727.1  404.35  4741.5  403.27  4747.9  401.77  4755.9  401.46
  4762.3  400.29  4783.4  399.08  4840.7  398.57  4869.4  397.47  4898.2  398.71
  4934.3  397.98  4942.6  398.43  4948.2   397.6    4965   398.3  4970.5  397.39
    4979  397.15  4998.3  393.37  5001.1  392.87  5004.3  393.37  5009.7  394.99
  5015.3  395.37  5023.7  397.49  5046.1  399.81    5060  400.38  5186.4  400.71
  5347.4  402.01    5519  404.88  5656.9  409.45  5729.8  413.53  5733.2  414.26
#Mann= 3 ,-1 , 0
  4671.3     .05       0  4998.3     .03       0  5004.3     .05       0
Bank Sta=4979,5023.7
XS Rating Curve= 0 ,0
Exp/Cntr=0.3,0.1

Type RM Length L Ch R = 1 ,35335   ,253,253,253
BEGIN DESCRIPTION:
BLAINS CREEK 34.0
END DESCRIPTION:
XS GIS Cut Line= 3
      3523249.49      10494274.3      3523308.51     10493986.14
      3523839.77     10493298.63
#Sta/Elev= 30
  4774.9  405.51  4879.7  404.47  4908.9   402.2  4951.1  397.52  4971.6  396.88
    4992  390.78  4999.2   390.3  5001.9   389.8  5005.2   390.3  5009.7  395.82
  5014.9   395.8  5022.6  397.82    5043  398.29  5060.2  399.83  5065.3  399.21
  5068.8  399.88  5088.4  400.38  5138.2  398.74  5152.7  398.69  5175.4  399.81
  5345.6  399.34  5509.5  401.92  5609.1   404.7  5787.6  412.43    5827  414.82
  5851.9  415.68  5866.4  417.01  5901.7  417.75  5916.2  419.53  5937.9  420.65
#Mann= 4 ,-1 , 0
  4774.9     .05       0  4999.2     .03       0  5005.2     .05       0
    5827      .1       0
Bank Sta=4971.6,5009.7
XS Rating Curve= 0 ,0
Exp/Cntr=0.3,0.1

Type RM Length L Ch R = 1 ,35082   ,598,598,598
BEGIN DESCRIPTION:
BLAINS CREEK 33.0
END DESCRIPTION:
XS GIS Cut Line= 4
      3523430.03      10494305.6      3523527.26     10494038.22
      3523496.01     10493850.72      3523897.96     10493292.84
#Sta/Elev= 30
  4619.8   405.1  4726.7  403.67  4813.1  401.64  4818.5  402.29  4879.7  402.55
  4951.5  399.86  4966.4  398.09  4971.8  396.88  4981.9   392.9  4992.1  391.42
  4999.2  391.27    5002  390.77  5005.2  391.27  5012.4  395.26  5027.2  395.44
  5052.9  398.02  5088.1  399.23  5219.3  399.16  5340.8  401.58  5470.9   406.4
  5491.8  406.45  5506.5  407.61    5628  412.54  5642.7  413.81  5684.9  415.15
  5713.9  416.14  5728.6   420.9  5743.3  421.91  5764.2  418.73    5782  418.49
#Mann= 4 ,-1 , 0
  4619.8     .05       0  4999.2     .03       0  5005.2     .05       0
  5684.9      .1       0
#XS Ineff= 2 , 0
         4869.32  402.83
Permanent Ineff=
       F       F
Bank Sta=4971.8,5012.4
XS Rating Curve= 0 ,0
Exp/Cntr=0.3,0.1

Type RM Length L Ch R = 1 ,34484   ,645,645,645
BEGIN DESCRIPTION:
BLAINS CREEK 32.0
END DESCRIPTION:
XS GIS Cut Line= 3
      3523655.73     10494534.76      3524016.85     10494010.44
      3524214.76     10493232.67
#Sta/Elev= 30
  4164.5  405.83    4732  398.09  4775.4  398.36  4830.9  396.64  4921.2  398.26
  4975.3   394.2    4993  390.03  4995.7  389.53    4999  390.03  5008.2  390.36
  5016.6  392.96  5026.2  394.68  5043.9  397.05    5090  398.61  5154.2  402.22
  5248.5  406.64  5264.2  406.68  5284.3  408.14  5330.3  409.04  5357.1  410.86
  5366.1  412.46  5377.8  413.37    5419  414.59  5429.3  415.37  5439.7  417.13
    5494  419.87  5522.2  422.81  5563.5  424.01  5594.4   426.2  5603.7  426.16
#Mann= 5 ,-1 , 0
  4164.5     .05       0    4993     .03       0    4999     .05       0
  5026.2      .1       0  5154.2     .05       0
Bank Sta=4975.3,5026.2
XS Rating Curve= 0 ,0
Exp/Cntr=0.3,0.1

Type RM Length L Ch R = 1 ,33839   ,904,904,904
BEGIN DESCRIPTION:
BLAINS CREEK 31.0
END DESCRIPTION:
XS GIS Cut Line= 3
      3523746.04      10494576.4       3524572.4     10494041.69
      3524977.88      10493688.2
#Sta/Elev= 30
  3919.2  405.12  3992.2  403.79  4013.3  404.53    4101  402.03  4542.2  396.34
  4772.1   396.8  4859.5  394.19  4874.6  395.24  4895.8  394.92  4910.4  395.92
  4952.6  395.64    4974  394.47  4981.6  391.15  4988.3  390.82  4992.9  386.31
  4995.6  385.81  4998.9  386.31  5002.5  386.32  5009.2  390.78  5016.8  397.54
  5023.4  399.96  5036.4  400.43  5045.2  400.53  5066.1  402.93  5108.8  404.99
    5189  407.25  5307.3  411.85  5364.2  414.67  5370.9  415.78  5441.4  417.49
#Mann= 6 ,-1 , 0
  3919.2     .05       0  4952.6     .16       0  4992.9     .07       0
  4998.9     .16       0  5036.4     .12       0    5189     .16       0
Bank Sta=4974,5016.8
XS Rating Curve= 0 ,0
Exp/Cntr=0.3,0.1

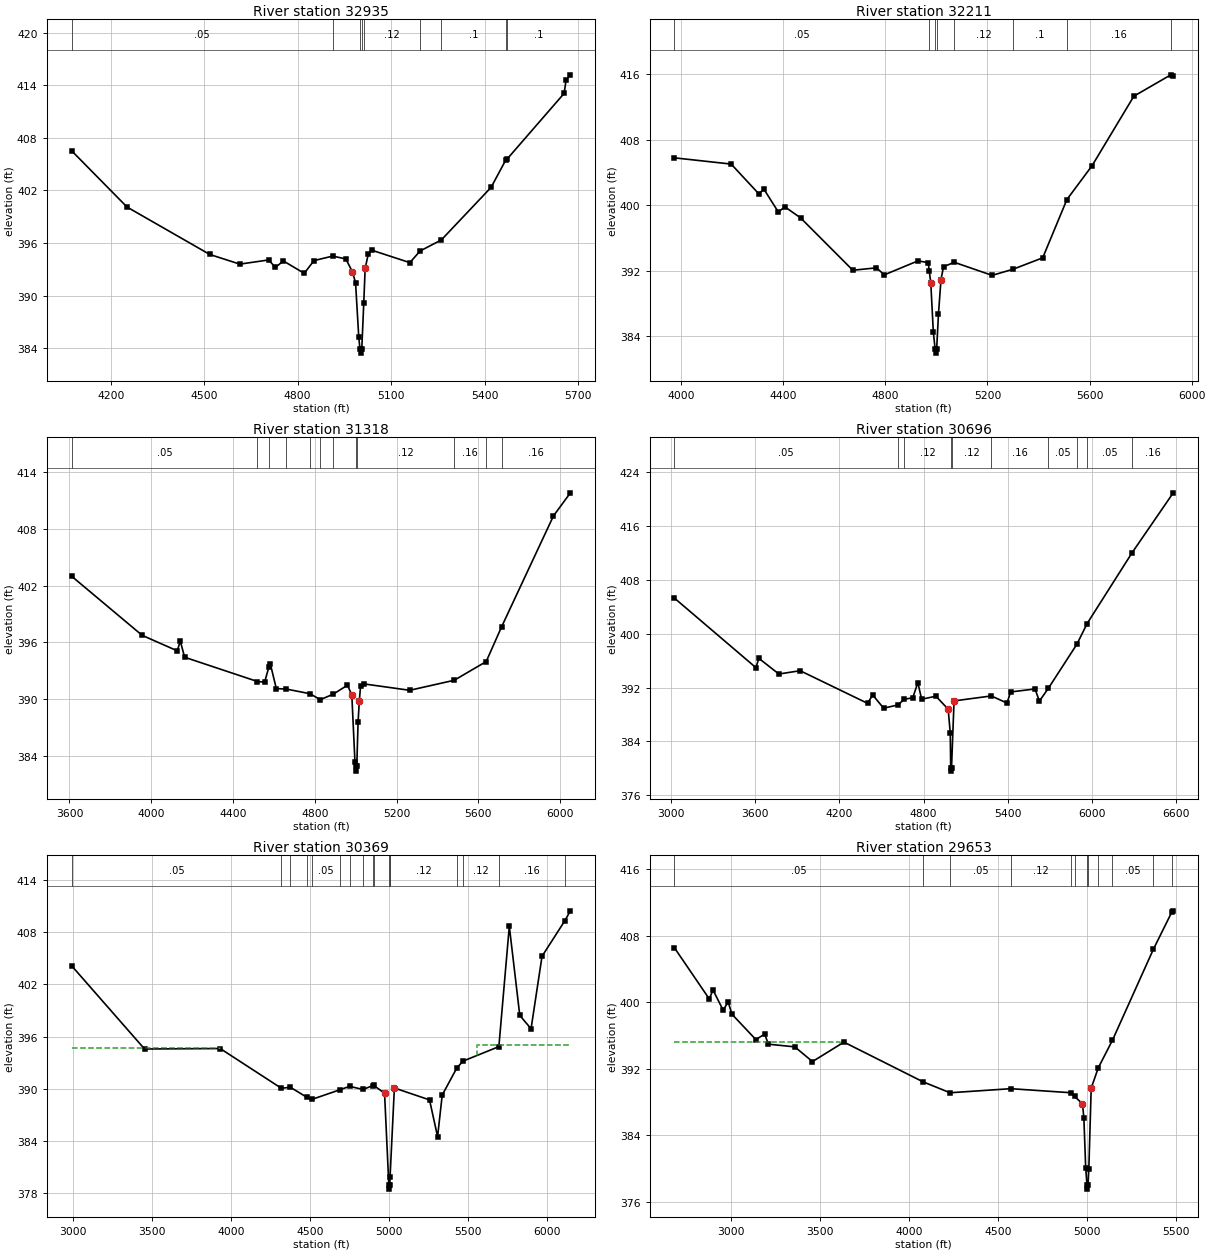
Type RM Length L Ch R = 1 ,32935   ,724,724,724
BEGIN DESCRIPTION:
BLAINS CREEK 32.1
END DESCRIPTION:
XS GIS Cut Line= 4
      3524843.23     10495343.77      3525051.57     10494555.58
      3525096.71     10494357.66      3525221.71     10493788.18
#Sta/Elev= 30
  4074.3  406.52  4252.3   400.1    4518  394.69  4614.4  393.59  4707.5  394.07
  4728.1  393.21  4754.3  393.95  4821.2  392.54  4852.3  393.99  4912.5  394.51
  4954.7  394.18  4975.7  392.73  4985.9  391.47  4996.2  385.24  4999.9  383.94
  5002.6  383.44  5005.9  383.94  5012.2  389.12  5016.7  393.11  5026.9  394.76
  5037.2  395.19  5160.2  393.76  5193.1  395.09  5261.3  396.35  5421.1  402.35
  5467.6  405.43  5472.8  405.59  5655.4  413.06  5661.8  414.59  5675.6  415.18
#Mann= 9 ,-1 , 0
  4074.3     .05       0  4912.5     .16       0  4999.9     .07       0
  5005.9     .16       0  5012.2     .12       0  5193.1     .16       0
  5261.3      .1       0  5467.6     .16       0  5472.8      .1       0
Bank Sta=4975.7,5016.7
XS Rating Curve= 0 ,0
Exp/Cntr=0.3,0.1

Type RM Length L Ch R = 1 ,32211   ,893,893,893
BEGIN DESCRIPTION:
BLAINS CREEK 31.1
END DESCRIPTION:
XS GIS Cut Line= 4
        3525361.     10495502.09      3525670.02     10494637.54
      3525680.43      10494179.2      3525472.09     10493640.99
#Sta/Elev= 30
  3974.2  405.77  4196.3  405.01  4303.9   401.4  4325.1  401.92  4381.1  399.15
  4406.5  399.79  4468.1  398.44    4673  392.04  4765.3  392.34  4796.1  391.48
  4928.2  393.19  4968.2  392.97  4972.3  391.95  4978.2  390.48  4988.2  384.48
  4995.2  382.42    4998  381.92  5001.2  382.42  5008.2  386.65  5018.2  390.91
  5028.2  392.48  5070.4  393.01  5218.3  391.42    5299  392.15  5416.6  393.56
  5511.4  400.68  5610.1  404.82  5773.6   413.3  5918.3  415.91  5927.9  415.81
#Mann= 8 ,-1 , 0
  3974.2     .05       0  4972.3     .16       0  4995.2     .07       0
  5001.2     .16       0  5070.4     .12       0    5299      .1       0
  5511.4     .16       0  5918.3     .05       0
Bank Sta=4978.2,5018.2
XS Rating Curve= 0 ,0
Exp/Cntr=0.3,0.1

Type RM Length L Ch R = 1 ,31318   ,622,622,622
BEGIN DESCRIPTION:
BLAINS CREEK 29.0
END DESCRIPTION:
XS GIS Cut Line= 3
      3525655.74     10495652.79      3526377.96     10494559.05
      3525780.71     10493600.69
#Sta/Elev= 30
  3610.5     403  3955.6  396.74  4127.2   395.1  4142.2  396.13  4163.3  394.42
  4519.5  391.85  4554.6  391.78  4575.2  393.36  4582.5  393.72  4611.8   391.1
  4661.1  391.05  4775.7  390.56  4827.3  389.93  4890.3  390.51    4960  391.46
  4981.2  390.43  4996.6  383.28  4999.4  382.86  5002.2  382.36  5005.4  382.86
  5011.9  387.58  5017.8  389.77  5024.2  391.42    5039   391.6  5264.4  390.92
  5481.9  391.98  5638.5  393.96  5713.6  397.63  5967.7  409.39  6050.4  411.83
#Mann= 12 ,-1 , 0
  3610.5     .05       0  4519.5      .1       0  4575.2     .05       0
  4661.1      .1       0  4775.7     .12       0  4827.3      .1       0
  4890.3     .12       0  4999.4     .07       0  5005.4     .12       0
  5481.9     .16       0  5638.5      .1       0  5713.6     .16       0
Bank Sta=4981.2,5017.8
XS Rating Curve= 0 ,0
Exp/Cntr=0.3,0.1

Type RM Length L Ch R = 1 ,30696   ,327,327,327
BEGIN DESCRIPTION:
BLAINS CREEK 28.1
END DESCRIPTION:
XS GIS Cut Line= 3
      3525710.54     10495838.03      3526706.22     10494421.62
      3527258.35     10492681.99
#Sta/Elev= 30
  3023.9  405.31  3604.6  394.98  3625.5  396.36  3768.4  394.03    3920  394.52
  4400.7  389.67  4437.4  390.92  4515.1  388.95  4617.4  389.43  4661.6  390.27
  4723.3   390.5  4759.3  392.75  4786.4  390.28  4888.4  390.73  4975.6  388.79
  4990.4  385.28  4993.5  380.09  4996.3  379.59  4999.5  380.09  5017.5  390.03
    5283  390.77  5395.2  389.71  5420.4  391.36  5594.6  391.81    5626     390
  5690.4  391.92  5893.7  398.47  5966.2  401.53  6286.8  412.06  6580.4  420.97
#Mann= 10 ,-1 , 0
  3023.9     .05       0  4617.4      .1       0  4661.6     .12       0
  4993.5     .07       0  4999.5     .12       0    5283     .16       0
  5690.4     .05       0  5893.7      .1       0  5966.2     .05       0
  6286.8     .16       0
Bank Sta=4975.6,5017.5
XS Rating Curve= 0 ,0
Exp/Cntr=0.3,0.1

Type RM Length L Ch R = 1 ,30369   ,716,716,716
BEGIN DESCRIPTION:
BLAINS CREEK 28.0
END DESCRIPTION:
XS GIS Cut Line= 5
      3525843.23     10495826.42      3526930.04     10494343.77
      3526957.82     10494281.27       3527235.6     10494173.64
      3528166.13     10493993.08
#Sta/Elev= 30
    2993  404.15  3453.9  394.57  3932.4  394.62  4318.6  390.05  4376.1  390.16
  4479.6  389.01  4513.8  388.78  4690.9  389.89  4750.2  390.27  4834.1  389.91
  4896.3  390.35  4901.7  390.38  4970.9  389.48  4997.9  378.94  5000.6  378.44
  5003.9  378.94  5005.7  379.83    5033  390.08  5255.2  388.71  5306.1  384.48
  5335.4  389.27  5427.7  392.38  5466.5  393.17  5693.4  394.84  5759.4  408.69
  5825.6  398.43  5896.9   396.9  5966.2  405.24  6109.8  409.31  6145.5  410.47
#Mann= 17 ,-1 , 0
    2993     .05       0  4318.6      .1       0  4376.1     .05       0
  4479.6      .1       0  4513.8     .05       0  4690.9     .16       0
  4750.2     .05       0  4834.1     .16       0  4896.3     .12       0
  4901.7     .16       0  4997.9     .07       0  5003.9     .16       0
  5005.7     .12       0  5427.7     .16       0  5466.5     .12       0
  5693.4     .16       0  6109.8     .05       0
#XS Ineff= 2 , 0
         3931.82  394.67 5554.55          395.08
Permanent Ineff=
       F       F
Bank Sta=4970.9,5033
XS Rating Curve= 0 ,0
Exp/Cntr=0.3,0.1

Type RM Length L Ch R = 1 ,29653   ,747,747,747
BEGIN DESCRIPTION:
BLAINS CREEK 27.1
END DESCRIPTION:
XS GIS Cut Line= 3
      3525857.12     10495913.22      3527152.26     10494524.33
      3528028.93      10494299.1
#Sta/Elev= 30
  2681.5  406.52    2877  400.38  2898.5  401.44  2955.2  399.02  2983.5  400.01
  3004.5  398.54  3138.9  395.49  3188.7  396.14  3209.7  394.93  3358.2  394.61
  3457.4  392.84  3634.3  395.18  4079.5   390.4  4230.9  389.09  4572.2  389.58
  4912.7  389.09    4931  388.64  4975.5  387.77  4983.1  386.07  4993.4   380.1
  5000.7     378  5003.5   377.5  5006.7     378  5011.1  379.91  5024.4  389.64
  5064.2  392.09  5143.8   395.4  5373.6  406.33  5476.7  410.78  5485.7  410.97
#Mann= 12 ,-1 , 0
  2681.5     .05       0  4079.5      .1       0  4230.9     .05       0
  4572.2     .12       0  4912.7     .16       0    4931     .12       0
  5000.7     .07       0  5006.7     .12       0  5064.2     .16       0
  5143.8     .05       0  5373.6     .16       0  5476.7      .1       0
#XS Ineff= 2 , 0
       0  3613.3  395.18               0
Permanent Ineff=
       F       F
Bank Sta=4975.5,5024.4
XS Rating Curve= 0 ,0
Exp/Cntr=0.3,0.1

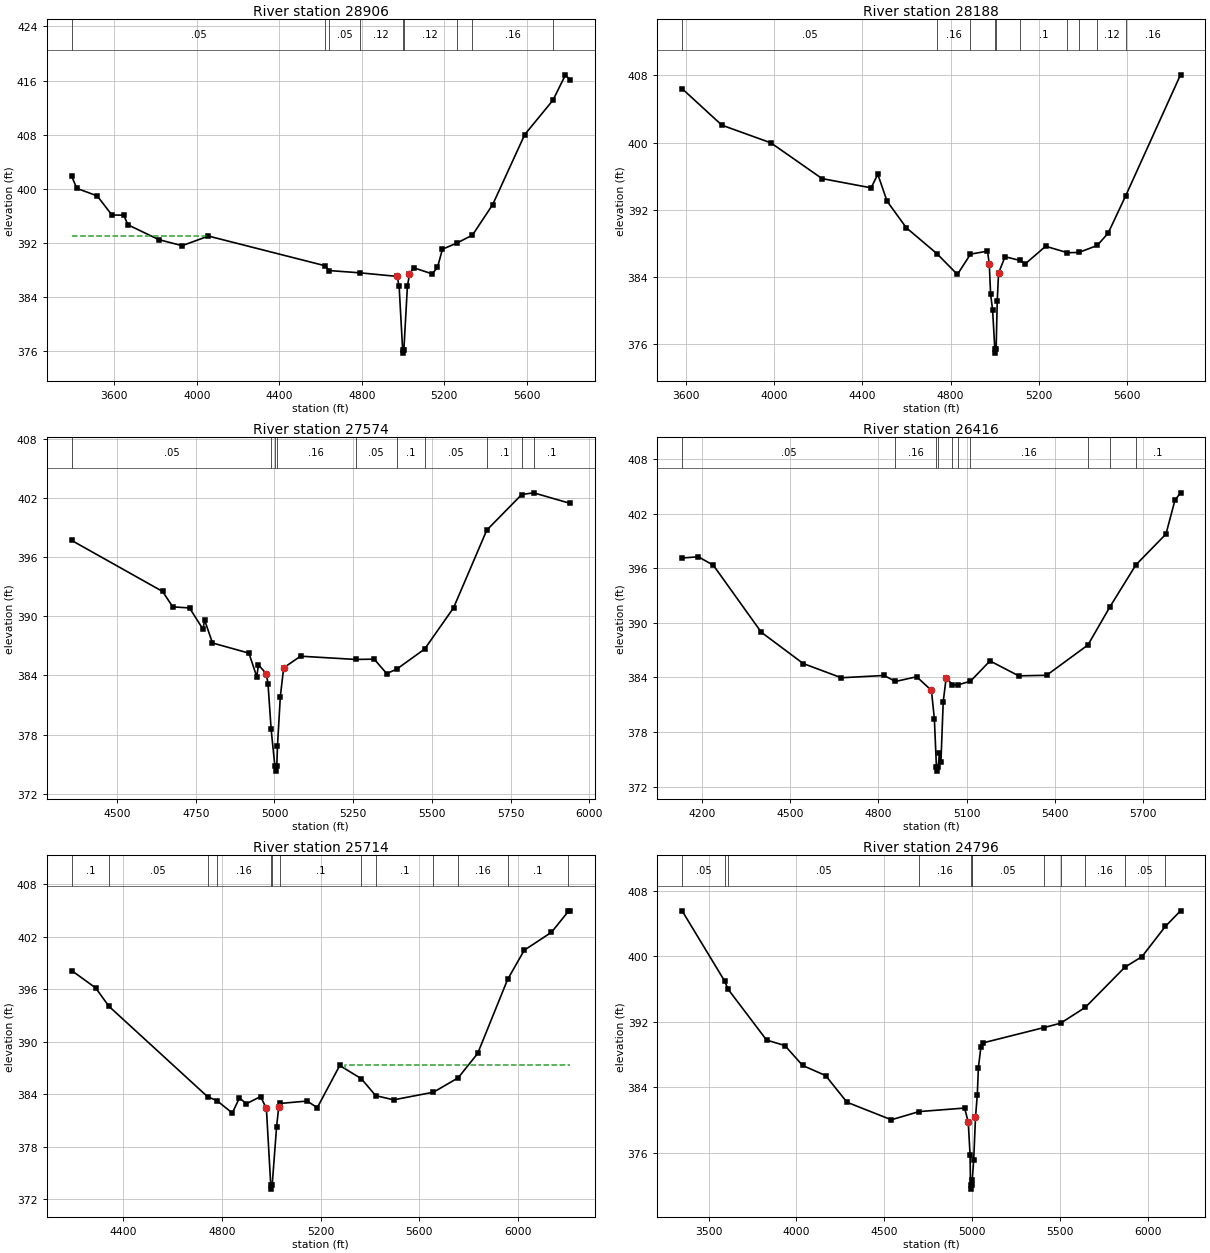
Type RM Length L Ch R = 1 ,28906   ,718,718,718
BEGIN DESCRIPTION:
BLAINS CREEK 27.0
END DESCRIPTION:
XS GIS Cut Line= 4
      3526107.13     10495812.52      3527190.46     10494899.33
      3527534.21     10494871.55      3528141.87     10494625.02
#Sta/Elev= 30
  3392.5  401.89  3417.9  400.07  3516.7  398.96  3588.2  396.13  3645.4  396.11
  3666.2  394.68  3815.8  392.49  3928.9   391.6  4056.4  393.02  4622.7  388.63
  4643.2  387.92  4790.6  387.59  4971.7  387.06  4981.6  385.57  4998.6  376.22
  5001.4  375.72  5004.6  376.22  5021.7  385.58  5031.7  387.35  5051.8  388.34
  5142.1  387.43  5167.7   388.4  5191.8  391.08  5261.1  391.98  5337.3  393.16
  5435.6  397.68    5591  408.02  5727.8   413.1  5788.7  416.85    5810  416.12
#Mann= 9 ,-1 , 0
  3392.5     .05       0  4622.7     .12       0  4643.2     .05       0
  4790.6     .12       0  4998.6     .07       0  5004.6     .12       0
  5261.1      .1       0  5337.3     .16       0  5727.8      .1       0
#XS Ineff= 2 , 0
         4056.24  393.05
Permanent Ineff=
       F       F
Bank Sta=4971.7,5031.7
XS Rating Curve= 0 ,0
Exp/Cntr=0.3,0.1

Type RM Length L Ch R = 1 ,28188   ,614,614,614
BEGIN DESCRIPTION:
BLAINS CREEK 25.0
END DESCRIPTION:
XS GIS Cut Line= 3
      3526421.96     10496259.01      3527621.97       10495459.
      3528171.98     10494858.98
#Sta/Elev= 30
  3584.5   406.4    3764  402.07  3986.3  399.96  4217.7  395.71    4440  394.61
  4470.1  396.23  4512.1  393.02  4599.3  389.86  4737.7  386.78  4830.6   384.3
  4889.8  386.72  4966.8  387.08  4974.9  385.54  4980.9  381.95  4989.9  380.12
  4999.9  375.44  5002.6  374.94  5005.9  375.44  5010.9  381.11  5016.9  384.47
  5046.3  386.41  5113.1  385.98  5138.2  385.57  5230.1  387.66  5328.7  386.89
  5380.2  386.92  5463.6  387.75  5513.1  389.22  5592.1  393.64  5840.7  408.06
#Mann= 10 ,-1 , 0
  3584.5     .05       0  4737.7     .16       0  4889.8     .12       0
  4999.9     .07       0  5005.9     .12       0  5113.1      .1       0
  5328.7     .12       0  5380.2      .1       0  5463.6     .12       0
  5592.1     .16       0
Bank Sta=4974.9,5016.9
XS Rating Curve= 0 ,0
Exp/Cntr=0.3,0.1

Type RM Length L Ch R = 1 ,27574   ,1158,1158,1158
BEGIN DESCRIPTION:
BLAINS CREEK 24.0
END DESCRIPTION:
XS GIS Cut Line= 3
      3527011.39     10496224.97      3527811.38     10495924.98
      3528511.38     10495724.97
#Sta/Elev= 30
  4355.8  397.69  4644.9  392.51    4677  390.95  4730.4  390.84    4773  388.69
  4778.3  389.61  4803.2  387.29  4918.9  386.26  4943.9  383.87  4949.2  385.06
  4974.1  384.18  4979.5  383.18  4989.5  378.55  5001.4   374.8  5004.1   374.3
  5007.4   374.8  5009.7  376.89  5018.7  381.86  5029.3  384.77  5082.8  385.95
  5258.3  385.62  5316.7  385.65  5356.5  384.19  5388.5  384.64  5477.1  386.68
  5568.9  390.86  5674.3  398.73  5785.3  402.34    5823  402.51  5938.2  401.45
#Mann= 10 ,-1 , 0
  4355.8     .05       0  4989.5     .16       0  5001.4     .07       0
  5007.4     .16       0  5258.3     .05       0  5388.5      .1       0
  5477.1     .05       0  5674.3      .1       0  5785.3     .05       0
    5823      .1       0
Bank Sta=4974.1,5029.3
XS Rating Curve= 0 ,0
Exp/Cntr=0.3,0.1

Type RM Length L Ch R = 1 ,26416   ,702,702,702
BEGIN DESCRIPTION:
BLAINS CREEK 23.0
END DESCRIPTION:
XS GIS Cut Line= 4
      3527318.02     10496413.21      3528015.98     10496548.64
      3528232.12     10496533.01      3528502.51     10495815.45
#Sta/Elev= 30
  4132.6  397.12  4187.7  397.25  4238.6  396.32  4401.6  388.96  4544.2  385.52
  4673.6  383.96  4819.3  384.21  4857.8  383.55  4929.9  384.07  4980.1  382.57
  4990.1  379.45  4997.1   374.2  4999.9   373.7  5003.1   374.2  5007.5  375.73
  5012.5  374.73  5020.2  381.32  5030.2  383.95    5051  383.21  5069.3  383.17
  5112.9  383.58  5179.3  385.81  5276.9  384.17  5371.7  384.23  5512.3  387.56
  5587.3  391.76  5675.3  396.36  5777.7  399.75  5808.1  403.46  5827.1  404.28
#Mann= 10 ,-1 , 0
  4132.6     .05       0  4857.8     .16       0  4997.1     .07       0
  5003.1     .16       0    5051     .12       0  5069.3      .1       0
  5112.9     .16       0  5512.3      .1       0  5587.3     .05       0
  5675.3      .1       0
Bank Sta=4980.1,5030.2
XS Rating Curve= 0 ,0
Exp/Cntr=0.3,0.1

Type RM Length L Ch R = 1 ,25714   ,918,918,918
BEGIN DESCRIPTION:
BLAINS CREEK 22.0
END DESCRIPTION:
XS GIS Cut Line= 3
      3527682.31     10497499.31      3528282.32     10496999.31
      3528582.33     10495799.27
#Sta/Elev= 30
  4191.7  398.12  4289.3  396.13  4343.1  394.03  4742.3  383.72  4780.8  383.26
  4842.6  381.85  4871.2  383.57  4899.8  382.92  4957.1  383.73  4980.6  382.38
  4998.2  373.67    5001  373.17  5004.2  373.67  5021.9  380.27  5030.4   382.5
  5035.9  382.95  5145.6  383.22  5186.8  382.47  5277.7  387.28  5365.1  385.77
  5423.2  383.84    5496  383.36  5657.1  384.23  5757.2  385.87  5836.2  388.65
  5957.5   397.1  6025.1  400.44  6135.1  402.48  6203.2  404.86  6209.7  404.93
#Mann= 13 ,-1 , 0
  4191.7      .1       0  4343.1     .05       0  4742.3      .1       0
  4780.8     .16       0  4998.2     .07       0  5004.2     .16       0
  5035.9      .1       0  5365.1     .12       0  5423.2      .1       0
  5657.1     .05       0  5757.2     .16       0  5957.5      .1       0
  6203.2     .16       0
#XS Ineff= 2 , 0
                         5299.72          387.39
Permanent Ineff=
       F       F
Bank Sta=4980.6,5030.4
XS Rating Curve= 0 ,0
Exp/Cntr=0.3,0.1

Type RM Length L Ch R = 1 ,24796   ,961,961,961
BEGIN DESCRIPTION:
BLAINS CREEK 22.1
END DESCRIPTION:
XS GIS Cut Line= 3
      3528891.76     10498479.59      3529089.68     10497031.71
      3528766.93     10495699.08
#Sta/Elev= 30
  3350.3  405.51  3591.9  396.95  3610.6  395.98  3830.2  389.76  3933.6   389.1
  4034.6  386.67  4165.8  385.43  4286.9  382.18  4539.2  380.04  4697.2  381.04
  4955.8  381.47  4976.3  379.74  4986.6  375.79  4989.1  372.08  4991.9  371.58
  4995.1  372.08    4999  372.69  5007.2  375.12  5017.5  380.33  5027.8  383.09
    5034  386.41  5048.4  388.95  5058.7  389.41  5406.7  391.29  5501.3  391.82
  5642.1  393.76    5866  398.64  5964.1  399.95  6096.4  403.62  6182.8  405.53
#Mann= 12 ,-1 , 0
  3350.3     .05       0  3591.9      .1       0  3610.6     .05       0
  4697.2     .16       0  4989.1     .03       0  4995.1     .16       0
    4999     .05       0  5406.7     .16       0  5501.3     .05       0
  5642.1     .16       0    5866     .05       0  6096.4     .16       0
Bank Sta=4976.3,5017.5
XS Rating Curve= 0 ,0
Exp/Cntr=0.3,0.1