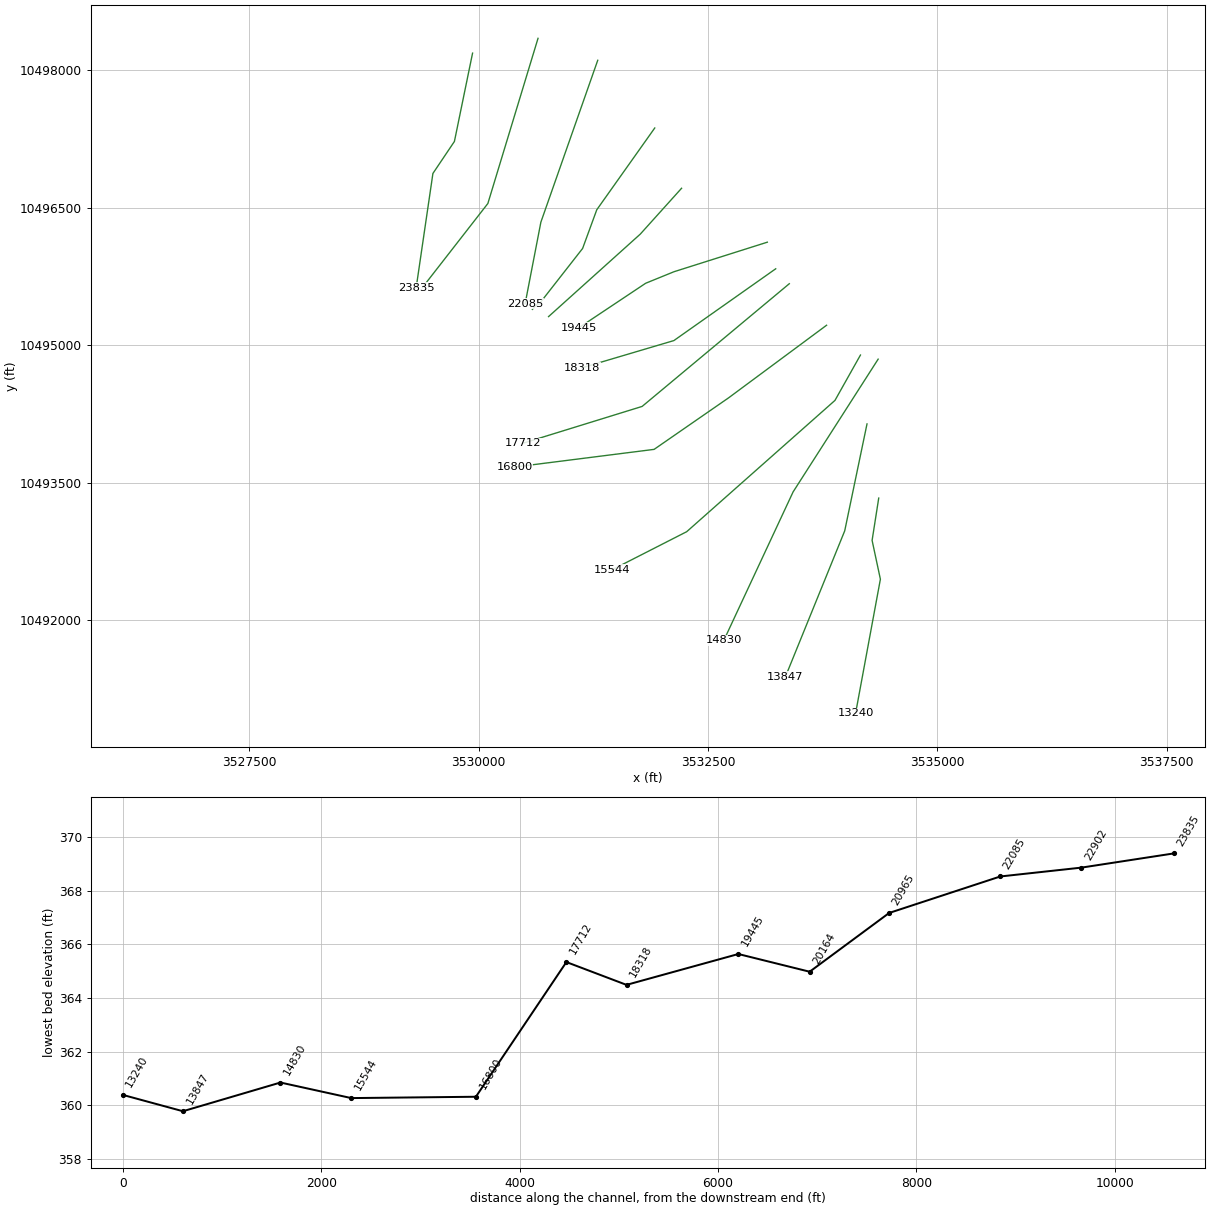
HEC-RAS study BLAINS CREEK.prj: BLAINS CREEK Base Level Engineering

--- BLAINS CREEK.g01 (geometry) --- (continued)

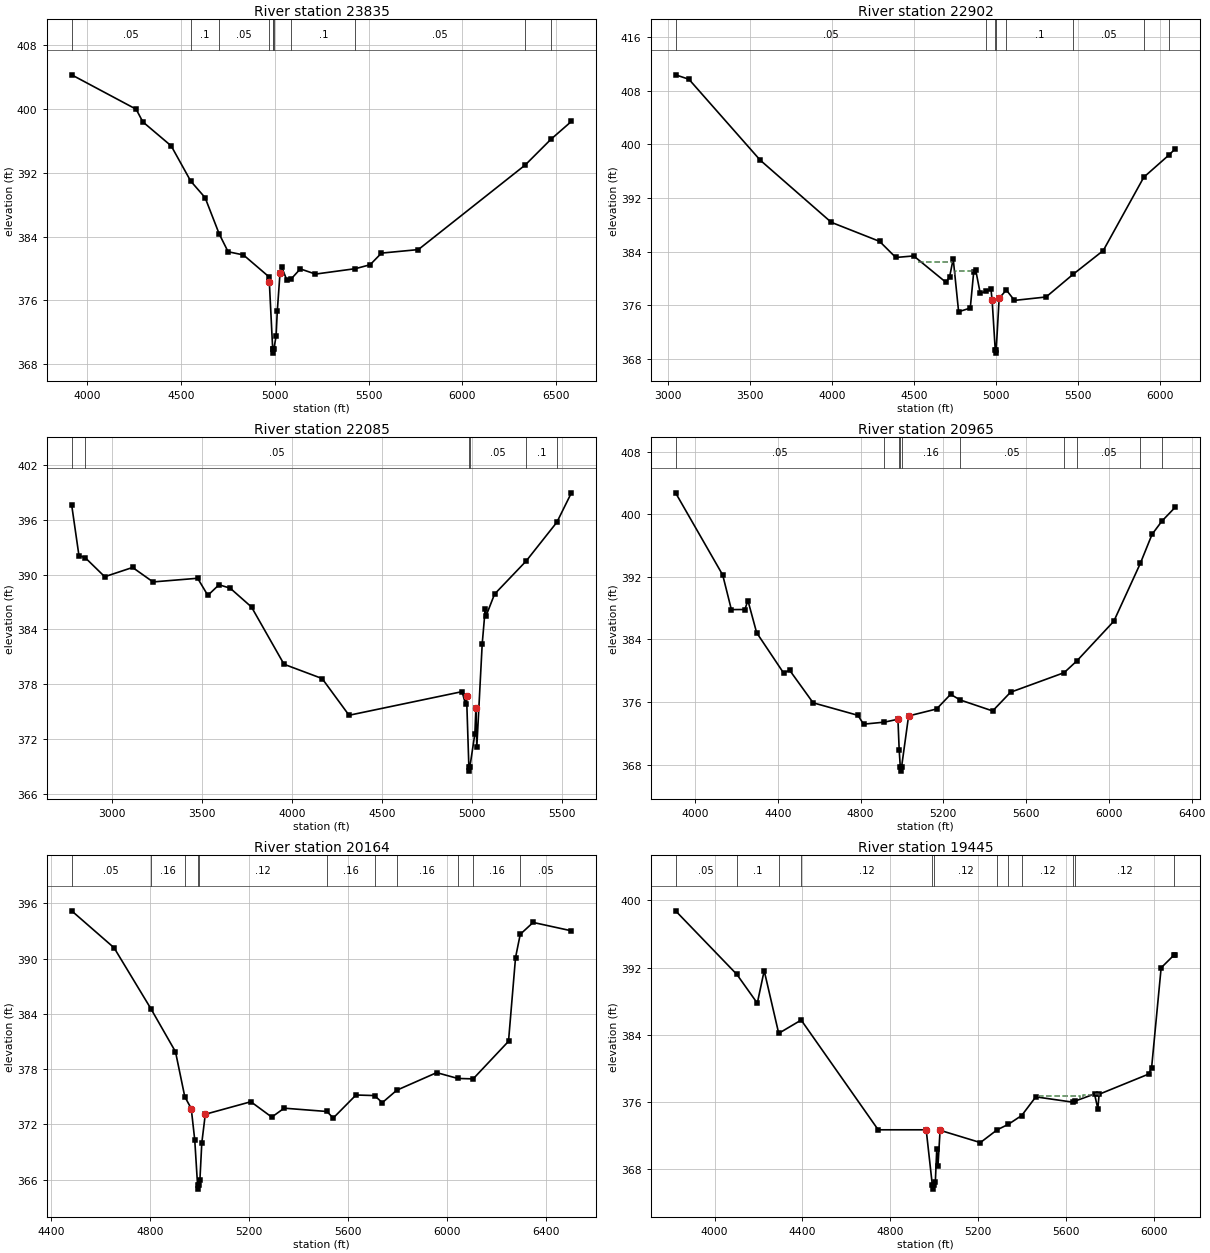
Type RM Length L Ch R = 1 ,23835   ,933,933,933
BEGIN DESCRIPTION:
BLAINS CREEK 21.0
END DESCRIPTION:
XS GIS Cut Line= 4
      3529933.43     10498187.97      3529735.51     10497224.42
      3529501.13     10496875.46      3529318.84     10495630.67
#Sta/Elev= 30
  3918.6  404.28    4262  399.97  4297.8  398.38  4448.9  395.37    4553  390.95
  4629.5  388.88  4704.6  384.33    4752   382.1  4833.6   381.7    4968  378.99
  4971.5  378.35  4989.4  369.93  4989.5  369.89  4992.3  369.39  4995.5  369.89
  5007.5   371.5    5014  374.67  5028.5   379.4  5037.5  380.17  5064.5  378.57
  5089.5  378.73  5136.5  379.95  5217.5   379.3  5430.3  379.98  5508.4  380.47
    5569  381.93  5765.3  382.37  6334.4  392.97  6471.7   396.2  6580.7  398.44
#Mann= 11 ,-1 , 0
  3918.6     .05       0    4553      .1       0  4704.6     .05       0
    4968      .1       0  4989.4     .16       0  4989.5     .07       0
  4995.5     .16       0  5089.5      .1       0  5430.3     .05       0
  6334.4      .1       0  6471.7     .05       0
Bank Sta=4971.5,5028.5
XS Rating Curve= 0 ,0
Exp/Cntr=0.3,0.1

Type RM Length L Ch R = 1 ,22902   ,817,817,817
BEGIN DESCRIPTION:
BLAINS CREEK 21.1
END DESCRIPTION:
XS GIS Cut Line= 3
      3530646.97     10498349.42      3530100.09     10496547.33
      3529386.85     10495631.05
#Sta/Elev= 30
    3047  410.35  3128.3  409.69  3562.5  397.63  3995.7  388.36  4289.9  385.52
  4388.5  383.12  4497.7  383.35    4695   379.4  4716.7  380.27  4738.4  382.92
  4771.3  375.03  4842.3  375.58    4863  380.92  4875.2  381.27  4902.8   377.8
  4937.1  378.06  4968.4  378.37  4975.5  376.72  4994.3  369.36  4997.1  368.86
  5000.3  369.36  5018.2  377.04    5062  378.27  5111.4  376.72  5304.1  377.23
  5468.7  380.61  5652.4  384.15  5899.5  395.09  6051.3  398.37  6091.4  399.33
#Mann= 8 ,-1 , 0
    3047     .05       0  4937.1     .16       0  4994.3     .07       0
  5000.3     .16       0    5062      .1       0  5468.7     .05       0
  5899.5      .1       0  6051.3     .05       0
#XS Ineff= 2 ,-1
  4524.7 4733.31  382.51 4748.27 4862.94  381.05
Permanent Ineff=
       F       F
Bank Sta=4975.5,5018.2
XS Rating Curve= 0 ,0
Exp/Cntr=0.3,0.1

Type RM Length L Ch R = 1 ,22085   ,1120,1120,1120
BEGIN DESCRIPTION:
BLAINS CREEK 20.0
END DESCRIPTION:
XS GIS Cut Line= 3
      3531298.01     10498109.83      3530678.22     10496344.21
      3530506.63     10495455.06
#Sta/Elev= 30
  2775.6  397.61  2816.1  392.07  2851.8  391.82  2959.3  389.76  3114.3  390.77
  3227.7  389.19  3475.6  389.59  3532.3  387.72  3594.3  388.88  3656.3  388.51
  3774.9  386.45  3955.6   380.2  4167.2  378.64  4316.9  374.63  4944.8  377.21
  4964.7  375.81  4969.8  376.74  4982.6  369.03  4985.3  368.53  4988.6  369.03
  5016.1  372.63  5021.7  375.41  5026.8  371.15  5056.8  382.44  5073.5  386.22
  5078.6   385.5  5125.4  387.86  5300.9  391.47  5471.7  395.71  5552.4  398.92
#Mann= 6 ,-1 , 0
  2775.6      .1       0  2851.8     .05       0  4982.6    .035       0
  4988.6     .05       0  5300.9      .1       0  5471.7     .05       0
Bank Sta=4969.8,5021.7
XS Rating Curve= 0 ,0
Exp/Cntr=0.3,0.1

Type RM Length L Ch R = 1 ,20965   ,801,801,801
BEGIN DESCRIPTION:
BLAINS CREEK 19.0
END DESCRIPTION:
XS GIS Cut Line= 6
      3531919.66     10497371.26      3531287.46     10496478.92
      3531133.22     10496056.99      3530657.38     10495448.38
      3530641.76     10495453.58      3530585.78     10495392.51
#Sta/Elev= 30
  3906.4  402.73  4134.2  392.23    4176  387.81  4241.2  387.82    4256  388.97
  4298.1  384.86  4428.3  379.71  4457.4  380.07    4571   375.9  4787.6   374.3
  4814.6  373.17  4915.7  373.43  4980.8   373.8  4986.9  369.87  4992.3  367.67
    4995  367.17  4998.3  367.67  5032.3  374.22  5167.5  375.11  5235.3  376.98
    5282  376.26  5438.4  374.86    5525  377.25  5783.8  379.75  5845.2  381.25
  6024.1  386.33  6152.1  393.72  6208.6  397.42  6256.1  399.11  6321.1   400.9
#Mann= 10 ,-1 , 0
  3906.4     .05       0  4915.7      .1       0  4986.9     .16       0
  4992.3     .07       0  4998.3     .16       0    5282     .05       0
  5783.8     .16       0  5845.2     .05       0  6152.1      .1       0
  6256.1     .16       0
Bank Sta=4980.8,5032.3
XS Rating Curve= 0 ,0
Exp/Cntr=0.3,0.1

Type RM Length L Ch R = 1 ,20164   ,719,719,719
BEGIN DESCRIPTION:
BLAINS CREEK 18.0
END DESCRIPTION:
XS GIS Cut Line= 3
      3532211.92     10496713.54       3531761.9     10496213.52
      3530761.88      10495313.5
#Sta/Elev= 30
  4482.5   395.2  4653.7  391.19  4802.5  384.57  4901.8   379.9  4939.4  375.01
  4965.4  373.73  4979.6  370.31  4990.8  365.48  4993.5  364.98  4996.8  365.48
  5000.5  366.01    5008  369.99  5022.2  373.11  5206.2  374.47  5290.6   372.8
  5340.7  373.77  5513.3  373.41  5538.8   372.7  5630.7   375.2  5705.5  375.14
  5736.9  374.37  5795.4  375.72  5956.6  377.63  6041.5     377  6103.8  376.95
  6246.6  381.03    6275  390.13    6294  392.65    6346  393.94  6500.6  393.03
#Mann= 11 ,-1 , 0
  4482.5     .05       0  4802.5     .16       0  4939.4     .12       0
  4990.8     .07       0  4996.8     .12       0  5513.3     .16       0
  5705.5     .12       0  5795.4     .16       0  6041.5     .12       0
  6103.8     .16       0    6294     .05       0
Bank Sta=4965.4,5022.2
XS Rating Curve= 0 ,0
Exp/Cntr=0.3,0.1

Type RM Length L Ch R = 1 ,19445   ,1127,1127,1127
BEGIN DESCRIPTION:
BLAINS CREEK 16.0
END DESCRIPTION:
XS GIS Cut Line= 4
        3533147.     10496125.47      3532129.13     10495803.06
      3531820.69     10495677.37      3531092.13     10495191.66
#Sta/Elev= 30
  3822.6  398.76  4101.9  391.19  4194.9  387.77  4226.3  391.64  4292.4  384.18
  4394.8  385.76  4745.6   372.7  4964.2   372.7  4992.1  366.14  4994.8  365.64
  4998.1  366.14  5005.9  366.53  5012.3  370.36  5017.7  368.34  5027.5  372.64
    5211  371.18  5287.5   372.7  5338.2  373.35  5399.2   374.4  5463.5  376.62
  5634.4  375.98  5643.4  376.13    5731  376.96    5746  375.21    5752  376.93
  5977.3  379.33  5990.9  380.07  6034.4  391.98  6093.9  393.52    6099  393.55
#Mann= 12 ,-1 , 0
  3822.6     .05       0  4101.9      .1       0  4292.4     .16       0
  4394.8     .12       0  4992.1     .07       0  4998.1     .12       0
  5287.5      .1       0  5338.2     .16       0  5399.2     .12       0
  5634.4     .16       0  5643.4     .12       0  6093.9     .05       0
#XS Ineff= 3 ,-1
 5478.57 5666.29  376.72 5679.39 5722.56  376.81 5731.04 5751.47  376.94
Permanent Ineff=
       F       F       F
Bank Sta=4964.2,5027.5
XS Rating Curve= 0 ,0
Exp/Cntr=0.3,0.1

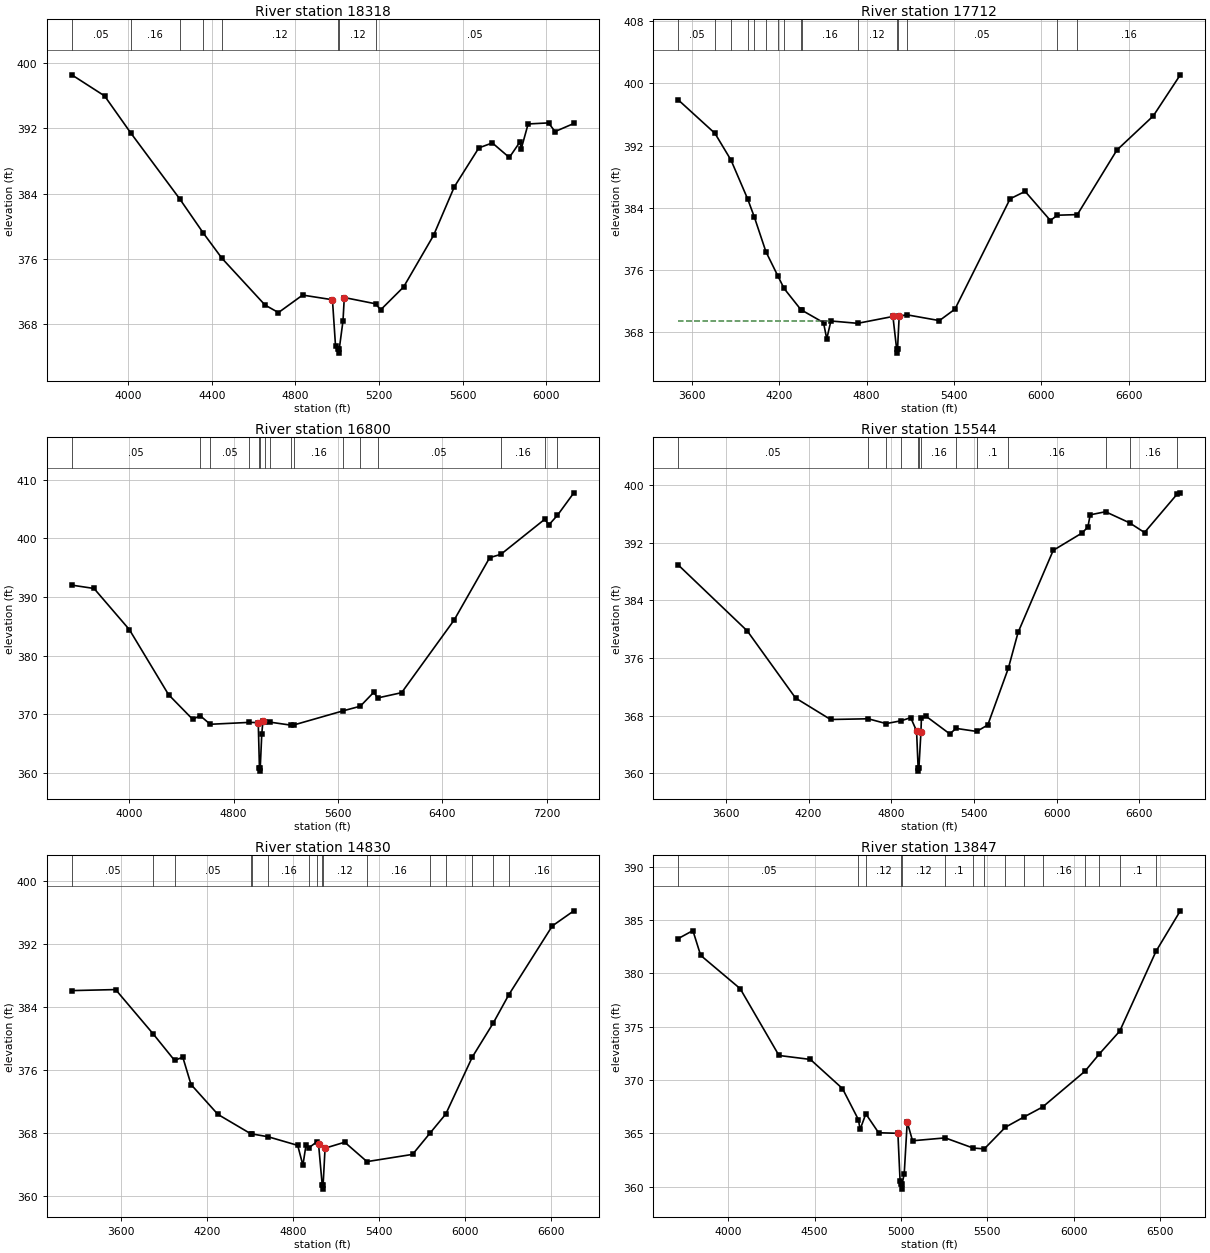
Type RM Length L Ch R = 1 ,18318   ,606,606,606
BEGIN DESCRIPTION:
BLAINS CREEK 15.0
END DESCRIPTION:
XS GIS Cut Line= 3
      3533238.39      10495835.2      3532128.14     10495051.99
      3531125.86     10494754.82
#Sta/Elev= 30
    3729  398.53  3886.1  395.95  4010.9  391.44  4246.3  383.34  4359.6  379.15
  4448.1  376.09  4654.5  370.37  4718.6  369.45  4834.4  371.59  4977.2  371.02
    4992  365.34  5003.8  364.99  5006.5  364.49  5009.8  364.99  5027.7  368.43
  5033.9  371.29  5184.4  370.52  5207.8  369.78  5317.9  372.58  5461.3  378.89
    5561  384.84  5678.1  389.59  5742.8   390.2  5824.1  388.42  5875.7  390.34
    5881  389.46  5914.2  392.52  6011.9  392.65  6043.1  391.59  6133.1  392.58
#Mann= 8 ,-1 , 0
    3729     .05       0  4010.9     .16       0  4246.3     .12       0
  4359.6     .16       0  4448.1     .12       0  5003.8     .07       0
  5009.8     .12       0  5184.4     .05       0
Bank Sta=4977.2,5033.9
XS Rating Curve= 0 ,0
Exp/Cntr=0.3,0.1

Type RM Length L Ch R = 1 ,17712   ,912,912,912
BEGIN DESCRIPTION:
BLAINS CREEK 14.0
END DESCRIPTION:
XS GIS Cut Line= 3
      3533386.52     10495672.31      3531782.38     10494333.79
      3530486.27     10493932.98
#Sta/Elev= 30
  3507.2  397.88  3759.2  393.58  3869.4  390.14  3984.3  385.12  4030.2  382.79
    4109  378.37  4190.9  375.26  4233.6  373.65  4351.7  370.86  4355.9  370.85
  4504.3  369.26  4526.5  367.17  4554.9  369.47  4738.9  369.17  4980.7  370.05
  5006.3  365.84  5009.1  365.34  5012.3  365.84  5023.6  370.08  5074.8  370.27
  5299.6  369.52  5406.3  370.99  5784.9  385.17    5888  386.12  6061.6  382.38
  6108.8  383.06  6246.5  383.14  6517.8  391.43  6767.6  395.82  6953.1   401.1
#Mann= 16 ,-1 , 0
  3507.2     .05       0  3759.2     .16       0  3869.4     .05       0
  3984.3     .16       0  4030.2     .05       0    4109     .16       0
  4190.9     .05       0  4233.6     .16       0  4351.7     .05       0
  4355.9     .16       0  4738.9     .12       0  5006.3     .07       0
  5012.3     .12       0  5074.8     .05       0  6108.8      .1       0
  6246.5     .16       0
#XS Ineff= 2 , 0
         4554.86  369.49
Permanent Ineff=
       F       F
Bank Sta=4980.7,5023.6
XS Rating Curve= 0 ,0
Exp/Cntr=0.3,0.1

Type RM Length L Ch R = 1 ,16800   ,1256,1256,1256
BEGIN DESCRIPTION:
BLAINS CREEK 13.0
END DESCRIPTION:
XS GIS Cut Line= 4
      3533792.79      10495219.2      3532725.09     10494427.54
      3531912.59     10493865.04      3530391.74     10493672.33
#Sta/Elev= 30
  3558.4  392.04    3729  391.47  4000.2  384.45  4300.7  373.36  4486.4  369.14
  4542.3  369.79  4620.1  368.31  4919.1  368.63  4988.5   368.6  4997.7  360.82
  5000.4  360.32  5003.7  360.82  5015.5  366.64  5024.3  368.87  5039.9  368.65
  5079.4  368.67  5242.3  368.15  5260.8  368.19  5639.1   370.6  5771.2  371.39
  5874.4  373.77  5904.5   372.8    6088   373.7  6491.2   386.1  6763.3  396.72
  6849.1  397.29  7184.3  403.25  7218.7  402.35  7283.4  403.96  7408.8  407.78
#Mann= 16 ,-1 , 0
  3558.4     .05       0  4542.3     .16       0  4620.1     .05       0
  4919.1     .16       0  4997.7     .07       0  5003.7     .16       0
  5039.9     .05       0  5079.4     .16       0  5242.3     .05       0
  5260.8     .16       0  5639.1     .05       0  5771.2     .16       0
  5904.5     .05       0  6849.1     .16       0  7184.3      .1       0
  7283.4     .05       0
Bank Sta=4988.5,5024.3
XS Rating Curve= 0 ,0
Exp/Cntr=0.3,0.1

Type RM Length L Ch R = 1 ,15544   ,714,714,714
BEGIN DESCRIPTION:
BLAINS CREEK 12.0
END DESCRIPTION:
XS GIS Cut Line= 4
      3534162.22     10494894.08      3533884.44     10494399.29
      3532268.12       10492967.       3531452.2     10492550.35
#Sta/Elev= 30
  3253.9  388.94  3755.1  379.76    4105  370.44  4359.3  367.45  4632.3  367.55
  4762.6  366.88  4873.2  367.28  4940.6  367.71  4983.3  365.86  4994.5  360.77
  4997.2  360.27  5000.5  360.77  5015.2  365.77  5018.4  367.61  5053.7  367.88
  5224.1  365.45  5270.4  366.21  5419.8  365.79  5500.1  366.69  5649.6   374.6
  5720.1  379.57  5974.9  390.97  6181.9  393.36  6226.4   394.2    6243  395.91
  6354.4  396.34  6528.7   394.8  6637.4  393.45    6873  398.77  6897.1  398.97
#Mann= 13 ,-1 , 0
  3253.9     .05       0  4632.3     .12       0  4762.6      .1       0
  4873.2     .12       0  4994.5     .07       0  5000.5     .12       0
  5015.2     .16       0  5270.4     .05       0  5419.8      .1       0
  5649.6     .16       0  6354.4     .05       0  6528.7     .16       0
    6873     .05       0
Bank Sta=4983.3,5015.2
XS Rating Curve= 0 ,0
Exp/Cntr=0.3,0.1

Type RM Length L Ch R = 1 ,14830   ,983,983,983
BEGIN DESCRIPTION:
BLAINS CREEK 11.0
END DESCRIPTION:
XS GIS Cut Line= 3
      3534355.32     10494849.44      3533428.22      10493401.5
      3532673.01     10491781.72
#Sta/Elev= 30
  3255.7  386.11  3561.8  386.24  3825.1  380.58  3973.6  377.23  4031.1  377.64
  4088.6  374.16  4276.3  370.36    4508  367.87  4515.8  367.87  4627.6  367.51
  4833.5  366.42  4869.9  363.89  4891.7  366.47  4913.4  366.13  4967.3  366.87
    4979  366.62    5005  361.35  5007.7  360.85    5011  361.35  5024.7  366.06
  5161.9  366.82  5317.4  364.35  5635.8  365.27  5757.4  367.97  5867.7   370.4
  6053.2  377.66  6198.6  381.96  6308.9  385.61  6611.9  394.34  6762.2  396.26
#Mann= 16 ,-1 , 0
  3255.7     .05       0  3825.1     .16       0  3973.6     .05       0
    4508     .16       0  4515.8      .1       0  4627.6     .16       0
  4913.4      .1       0  4967.3     .12       0    5005     .07       0
    5011     .12       0  5317.4     .16       0  5757.4     .05       0
  5867.7      .1       0  6053.2     .16       0  6198.6     .05       0
  6308.9     .16       0
Bank Sta=4979,5024.7
XS Rating Curve= 0 ,0
Exp/Cntr=0.3,0.1

Type RM Length L Ch R = 1 ,13847   ,607,607,607
BEGIN DESCRIPTION:
BLAINS CREEK 10.0
END DESCRIPTION:
XS GIS Cut Line= 3
      3534233.77      10494142.8      3533990.72     10492976.15
      3533345.04     10491386.26
#Sta/Elev= 30
  3709.9  383.25  3794.8     384  3839.7  381.68  4068.6  378.56  4293.3   372.3
  4475.1  371.93  4661.1   369.2  4753.3  366.29  4763.2  365.37  4796.3  366.83
  4870.4  365.06    4982  365.01  4994.6  360.58  5000.6  360.28  5003.4  359.78
  5006.6  360.28  5018.7  361.22    5036  366.07  5066.8  364.31    5256  364.58
  5417.5  363.63  5482.3  363.55  5604.7  365.58  5712.3  366.54  5819.9  367.47
  6065.2  370.82  6149.5  372.46  6266.7  374.58  6476.9  382.06  6617.6  385.85
#Mann= 15 ,-1 , 0
  3709.9     .05       0  4753.3     .16       0  4796.3     .12       0
  5000.6     .07       0  5006.6     .12       0    5256      .1       0
  5417.5     .05       0  5482.3      .1       0  5604.7     .05       0
  5712.3      .1       0  5819.9     .16       0  6065.2      .1       0
  6149.5     .16       0  6266.7      .1       0  6476.9     .16       0
Bank Sta=4982,5036
XS Rating Curve= 0 ,0
Exp/Cntr=0.3,0.1

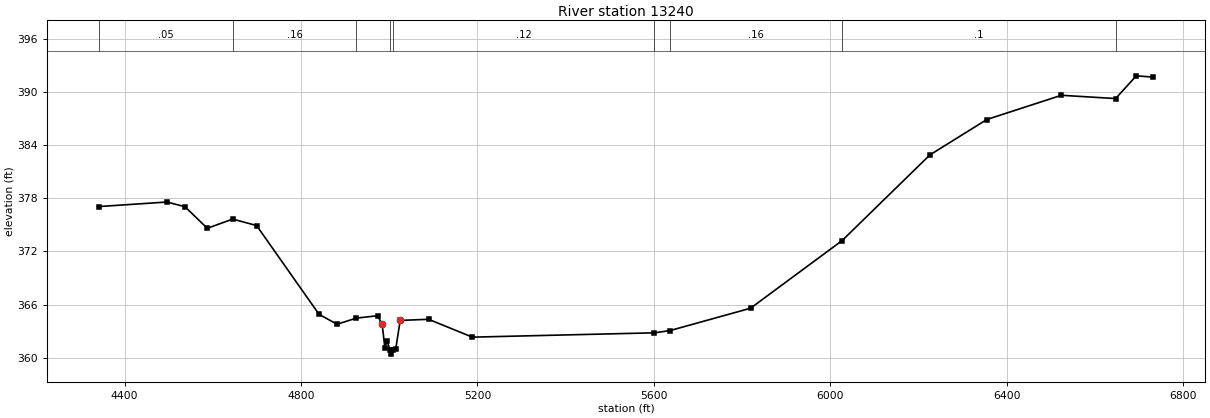
Type RM Length L Ch R = 1 ,13240   ,1784,1784,1784
BEGIN DESCRIPTION:
BLAINS CREEK 8.0
END DESCRIPTION:
XS GIS Cut Line= 4
      3534361.47     10493333.52      3534289.33     10492871.99
      3534379.61     10492448.38      3534109.09     10490984.83
#Sta/Elev= 30
  4342.7  377.08  4495.9  377.59  4536.9  377.06  4587.5  374.62    4645  375.66
  4699.3  374.93  4840.9  364.89  4881.8  363.77  4925.3  364.46  4973.8  364.73
    4984  363.76  4990.1  361.13  4995.2  361.87  5001.5  360.89  5004.2  360.39
  5007.5  360.89  5014.7  360.95  5024.9   364.2  5089.2  364.33  5188.5  362.31
  5601.5   362.8  5637.2  363.06  5819.3  365.58  6026.7  373.22  6226.1  382.92
  6355.1  386.92  6524.1  389.66  6647.1  389.29  6693.9  391.86  6731.3  391.72
#Mann= 9 ,-1 , 0
  4342.7     .05       0    4645     .16       0  4925.3     .12       0
  5001.5     .07       0  5007.5     .12       0  5601.5     .05       0
  5637.2     .16       0  6026.7      .1       0  6647.1     .16       0
Bank Sta=4984,5024.9
XS Rating Curve= 0 ,0
Exp/Cntr=0.3,0.1