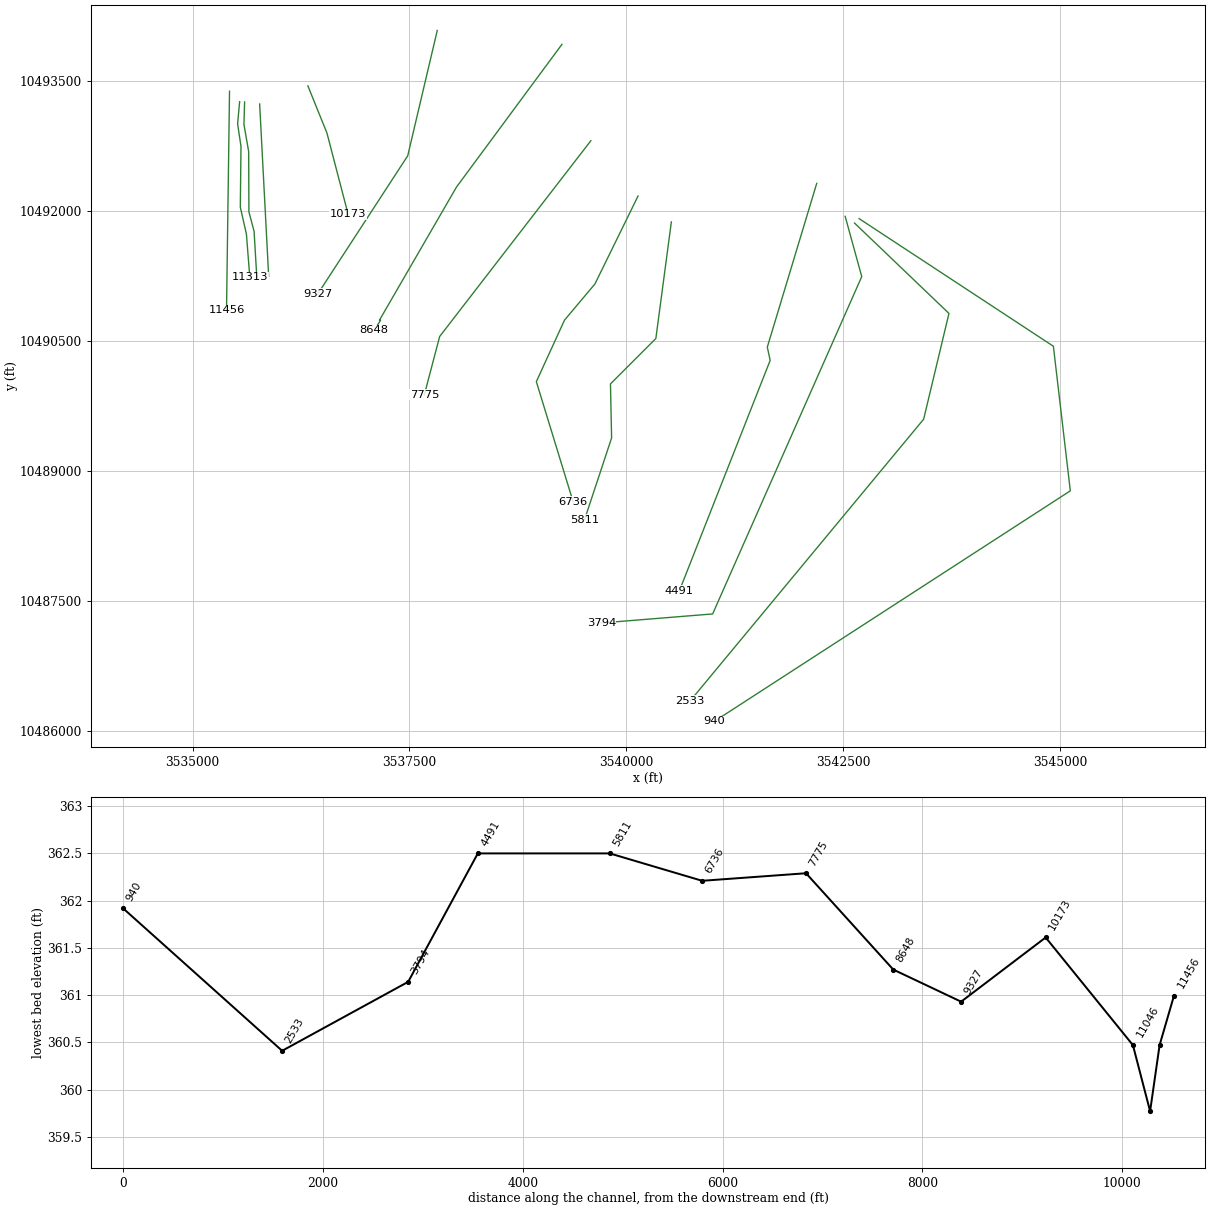
HEC-RAS study BLAINS CREEK.prj: BLAINS CREEK Base Level Engineering

--- BLAINS CREEK.g01 (geometry) --- (continued)

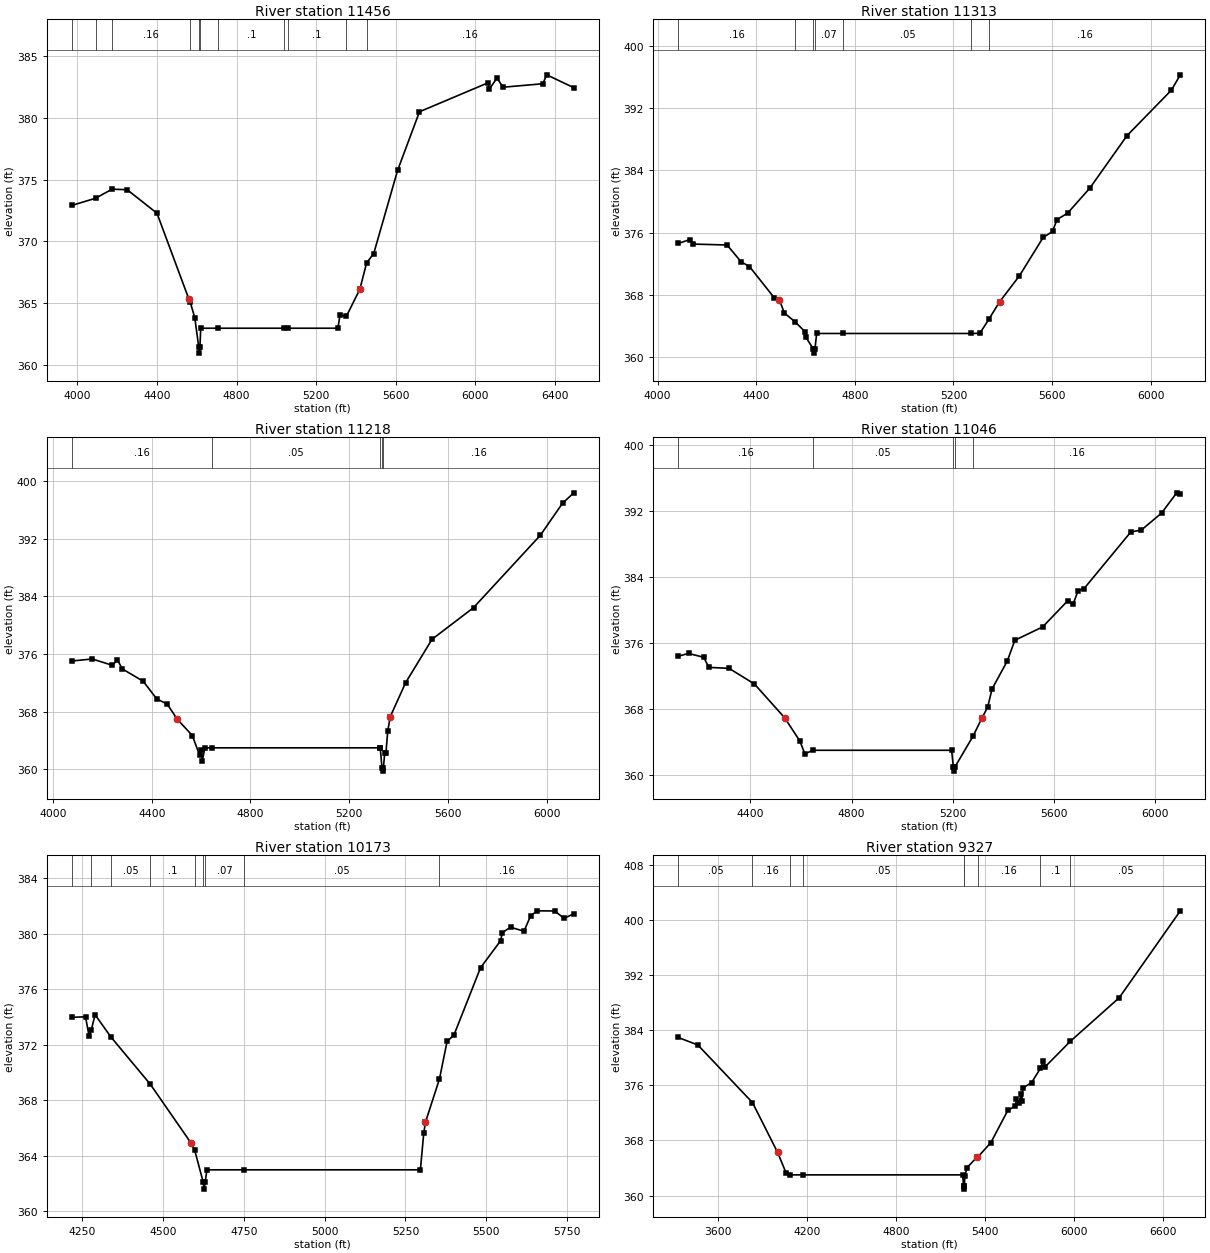
Type RM Length L Ch R = 1 ,11456   ,143,143,143
BEGIN DESCRIPTION:
BLAINS CREEK 7.0
END DESCRIPTION:
XS GIS Cut Line= 2
      3535425.89     10493380.14      3535391.19     10490855.37
#Sta/Elev= 30
  3971.2  372.91  4090.9  373.49  4173.7  374.22  4249.7  374.18  4399.7  372.28
  4559.7  365.37  4567.3  365.09  4589.8  363.85  4609.7  361.49  4612.4  360.99
  4615.7  361.49  4619.8     363    4708     363  5039.9     363  5058.3     363
  5309.8     363  5319.8  364.04  5352.8  363.98  5419.8  366.14  5454.1  368.27
  5489.8  369.03  5609.8  375.74  5719.9  380.47  6065.3  382.81  6070.3  382.28
  6109.9  383.19  6139.9  382.45  6339.9  382.73  6359.9  383.45  6496.2  382.41
#Mann= 11 ,-1 , 0
  3971.2     .16       0  4090.9     .05       0  4173.7     .16       0
  4567.3     .07       0  4609.7     .07       0  4615.7     .07       0
    4708      .1       0  5039.9     .12       0  5058.3      .1       0
  5352.8     .07       0  5454.1     .16       0
Bank Sta=4559.7,5419.8
XS Rating Curve= 0 ,0
Exp/Cntr=0.3,0.1

Type RM Length L Ch R = 1 ,11313   ,95,95,95
BEGIN DESCRIPTION:
BLAINS CREEK 7.01
END DESCRIPTION:
XS GIS Cut Line= 6
      3535542.43     10493259.09      3535518.99     10493003.85
      3535558.06     10492743.43      3535550.24     10492042.91
      3535620.56     10491733.01      3535659.58     10491236.13
#Sta/Elev= 30
  4083.6  374.59  4131.2  375.09  4144.1  374.51  4281.9  374.39  4338.5  372.23
  4372.5  371.62  4473.6  367.57  4493.8  367.34    4514  365.63  4556.8  364.52
  4598.4  363.21  4601.6  362.51    4632  360.97  4634.8  360.47    4638  360.97
    4645     363  4753.4     363  5272.7     363    5307  363.03    5343   364.8
  5387.1  367.08  5467.2  370.41  5563.7  375.36  5601.7  376.13  5619.7  377.66
  5663.1   378.5  5753.4  381.73  5903.8  388.47  6083.9  394.33    6120   396.3
#Mann= 7 ,-1 , 0
  4083.6     .16       0  4556.8     .07       0    4632    .033       0
    4638     .07       0  4753.4     .05       0  5272.7     .07       0
    5343     .16       0
Bank Sta=4493.8,5387.1
XS Rating Curve= 0 ,0
Exp/Cntr=0.3,0.1

Type RM Length L Ch R = 1 ,11218   ,172,172,172
BEGIN DESCRIPTION:
BLAINS CREEK 5.01
END DESCRIPTION:
XS GIS Cut Line= 6
      3535599.72     10493256.46      3535591.91     10492998.64
       3535646.6     10492683.53       3535649.2     10491990.82
       3535709.1     10491764.26      3535740.32      10491236.1
#Sta/Elev= 30
    4076  375.04  4159.1  375.32  4240.9  374.44  4260.9   375.2  4280.9  373.94
  4365.4  372.23    4420  369.79  4462.8  369.06  4503.4  366.96  4564.3  364.71
    4594  361.96    4599  362.69  4604.9  361.21  4615.1     363  4642.2     363
  5323.1     363  5325.6     363  5332.6  360.27  5335.4  359.77  5338.6  360.27
  5343.6  362.25  5348.6  362.25    5356  365.34  5366.3  367.33  5428.4  372.03
  5535.4  378.05  5703.6  382.44  5974.1  392.47  6064.3  396.93  6109.9  398.36
#Mann= 5 ,-1 , 0
    4076     .16       0  4642.2     .05       0  5323.1     .16       0
  5332.6    .033       0  5338.6     .16       0
Bank Sta=4503.4,5366.3
XS Rating Curve= 0 ,0
Exp/Cntr=0.3,0.1

Type RM Length L Ch R = 1 ,11046   ,873,873,873
BEGIN DESCRIPTION:
BLAINS CREEK 5.0
END DESCRIPTION:
XS GIS Cut Line= 2
      3535773.12     10493232.59      3535877.14     10491247.41
#Sta/Elev= 30
  4113.9  374.42  4154.9  374.75    4215  374.28    4235  373.06  4315.1  372.94
  4415.3  371.05  4535.4  366.94  4595.5  364.12  4615.5  362.55  4646.1     363
  5196.3     363  5203.3  360.97  5206.1  360.47  5209.3  360.97  5280.9   364.7
  5316.5  366.92  5339.1  368.24  5356.5  370.45  5416.6  373.82  5446.7  376.35
  5556.8  377.97    5657  381.17    5677  380.71    5697  382.35  5720.5  382.61
  5906.1   389.5  5947.4  389.72  6027.5  391.78  6087.5  394.24  6101.8  394.12
#Mann= 5 ,-1 , 0
  4113.9     .16       0  4646.1     .05       0  5203.3    .033       0
  5209.3     .05       0  5280.9     .16       0
Bank Sta=4535.4,5316.5
XS Rating Curve= 0 ,0
Exp/Cntr=0.3,0.1

Type RM Length L Ch R = 1 ,10173   ,846,846,846
BEGIN DESCRIPTION:
BLAINS CREEK 4.0
END DESCRIPTION:
XS GIS Cut Line= 3
      3536329.26     10493441.42      3536549.06     10492897.69
      3536792.79      10491962.3
#Sta/Elev= 30
    4218  373.98  4260.6  374.02  4271.7  372.61  4278.5  373.08  4290.1  374.17
  4338.9  372.57    4461  369.16  4587.8   364.9    4598  364.44  4624.6  362.11
  4627.4  361.61  4630.6  362.11  4636.1     363  4751.9     363  5296.4     363
  5306.8  365.64  5312.1  366.43  5355.5  369.55  5379.1  372.26  5399.8  372.68
  5482.4  377.55  5544.4  379.49  5549.9  380.08  5575.4  380.47  5616.8  380.18
  5637.4  381.29  5658.1  381.65  5711.9  381.64  5740.8  381.11  5771.1  381.44
#Mann= 9 ,-1 , 0
    4218     .05       0  4278.5     .16       0  4338.9     .05       0
    4461      .1       0    4598     .07       0  4624.6    .033       0
  4630.6     .07       0  4751.9     .05       0  5355.5     .16       0
Bank Sta=4587.8,5312.1
XS Rating Curve= 0 ,0
Exp/Cntr=0.3,0.1

Type RM Length L Ch R = 1 ,9327    ,679,679,679
BEGIN DESCRIPTION:
BLAINS CREEK 3.0
END DESCRIPTION:
XS GIS Cut Line= 3
      3537820.59     10494080.36       3537480.3     10492635.88
      3536442.11     10491041.64
#Sta/Elev= 30
  3330.2  382.94  3462.4  381.85    3831  373.49  4000.7  366.25  4058.3  363.24
  4083.6     363  4169.1     363  5248.9     363  5254.4  361.43  5257.1  360.93
  5260.4  361.43  5263.3  362.84  5278.5  364.05  5344.3  365.56    5352  365.62
  5438.5  367.67  5553.1  372.35  5604.5     373  5610.5  373.98  5631.5  373.48
  5640.7  374.72  5646.7  373.71  5654.6  375.61  5713.2  376.38  5773.5  378.47
  5791.6  379.57  5806.7  378.72  5975.2  382.39  6304.7  388.71  6716.7  401.32
#Mann= 9 ,-1 , 0
  3330.2     .05       0    3831     .16       0  4083.6     .12       0
  4169.1     .05       0  5254.4    .033       0  5260.4     .05       0
    5352     .16       0  5773.5      .1       0  5975.2     .05       0
Bank Sta=4000.7,5344.3
XS Rating Curve= 0 ,0
Exp/Cntr=0.3,0.1

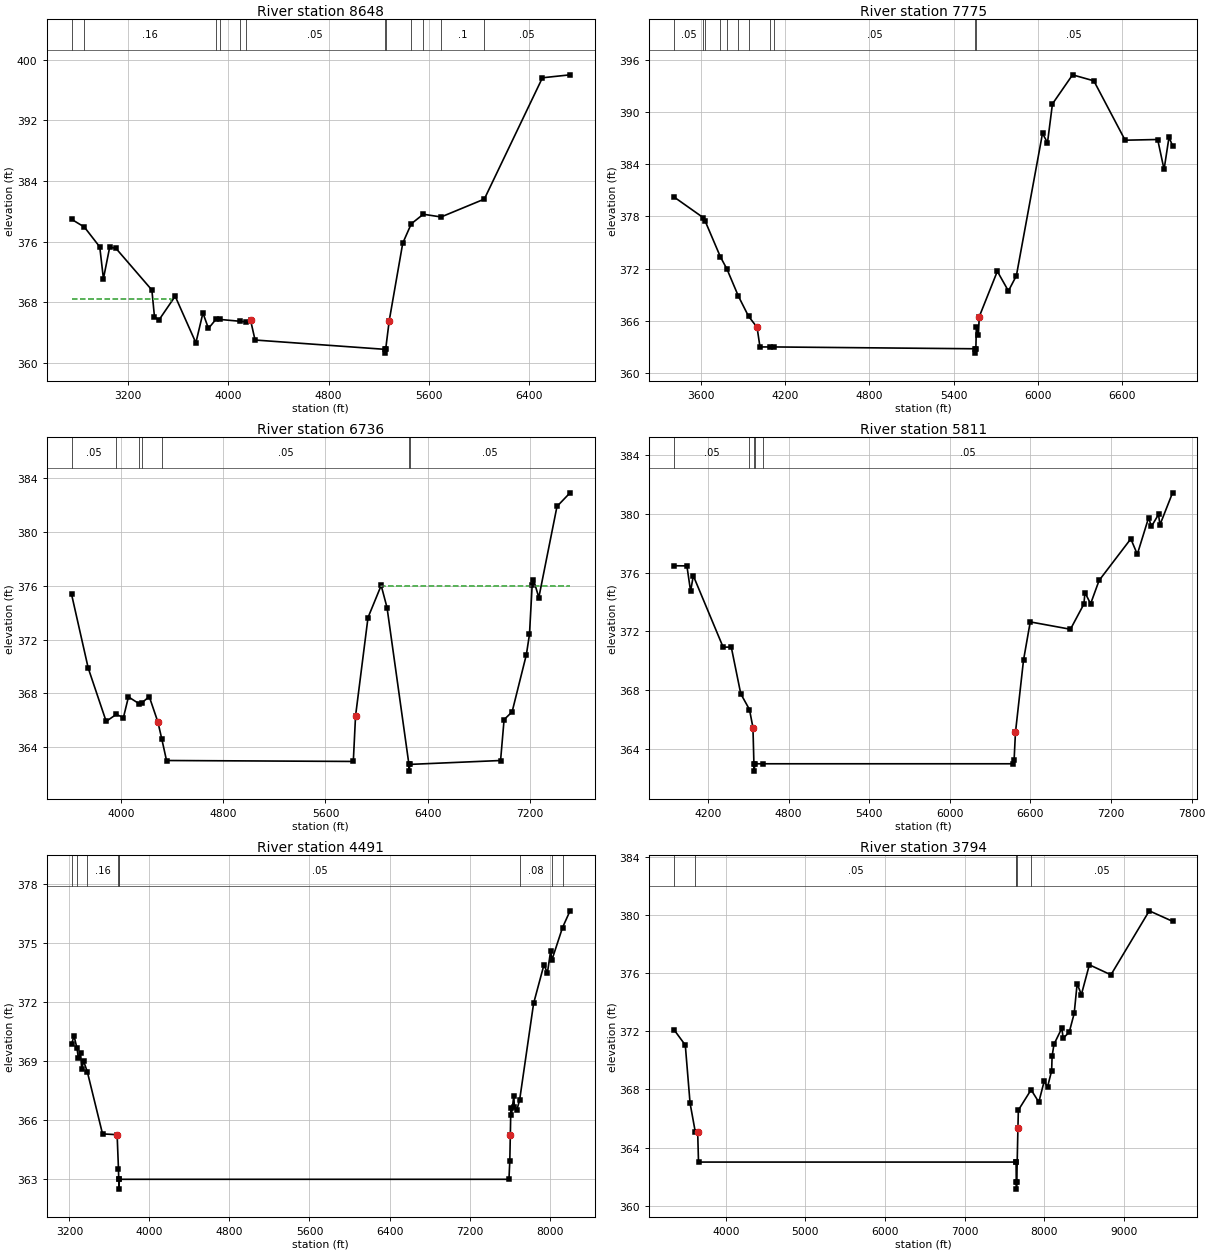
Type RM Length L Ch R = 1 ,8648    ,873,873,873
BEGIN DESCRIPTION:
BLAINS CREEK 2.0
END DESCRIPTION:
XS GIS Cut Line= 5
      3539258.07     10493920.58      3538042.11     10492274.76
      3537153.91     10490740.04       3537167.8     10490740.04
      3537091.41     10490621.98
#Sta/Elev= 30
  2750.8  378.93  2852.5  377.91  2975.3  375.29  3004.6  371.09  3054.7  375.27
  3104.8  375.09  3390.8   369.6  3411.7  366.05  3447.2  365.64  3576.7  368.78
  3741.6  362.63  3797.9  366.57  3841.8  364.53  3904.7  365.79  3937.9  365.71
  4095.8  365.47  4137.8   365.4    4178  365.59  4213.4     363  5248.7  361.77
  5251.4  361.27  5254.7  361.77  5283.2  365.56  5390.9  375.78    5459  378.34
  5554.8   379.6  5696.6  379.24  6041.3   381.6  6504.5  397.61  6724.8     398
#Mann= 12 ,-1 , 0
  2750.8     .05       0  2852.5     .16       0  3904.7     .07       0
  3937.9     .05       0  4095.8     .16       0  4137.8     .05       0
  5248.7    .033       0  5254.7     .05       0    5459      .1       0
  5554.8     .05       0  5696.6      .1       0  6041.3     .05       0
#XS Ineff= 2 , 0
         3542.61  368.46
Permanent Ineff=
       F       F
Bank Sta=4178,5283.2
XS Rating Curve= 0 ,0
Exp/Cntr=0.3,0.1

Type RM Length L Ch R = 1 ,7775    ,1039,1039,1039
BEGIN DESCRIPTION:
BLAINS CREEK 3.1
END DESCRIPTION:
XS GIS Cut Line= 3
      3539591.39     10492809.46      3537848.36     10490552.54
      3537671.29      10489879.9
#Sta/Elev= 30
  3410.8  380.22  3617.7  377.86    3633  377.42  3740.6  373.34  3786.9  371.95
  3868.5  368.83  3940.7  366.52  4001.2  365.26    4022     363  4094.6     363
  4124.3     363  5552.4  362.79  5555.1  362.29  5558.4  362.79  5561.7  365.29
  5576.2  364.35  5582.5  366.48  5711.1  371.69  5789.9  369.43  5846.6  371.18
  6032.6  387.54    6068  386.45  6103.3  390.92  6246.4  394.26  6397.8  393.57
  6620.5  386.75  6852.1  386.83  6897.6  383.39  6932.8  387.09    6958  386.12
#Mann= 11 ,-1 , 0
  3410.8     .05       0  3617.7     .16       0    3633     .05       0
  3740.6     .16       0  3786.9     .05       0  3868.5     .16       0
  3940.7     .05       0  4094.6     .07       0  4124.3     .05       0
  5552.4    .033       0  5558.4     .05       0
Bank Sta=4001.2,5582.5
XS Rating Curve= 0 ,0
Exp/Cntr=0.3,0.1

Type RM Length L Ch R = 1 ,6736    ,925,925,925
BEGIN DESCRIPTION:
BLAINS CREEK 2.1
END DESCRIPTION:
XS GIS Cut Line= 5
      3540135.21     10492171.62      3539638.45     10491158.23
      3539287.41     10490740.96      3538962.86     10490032.25
      3539386.75     10488647.98
#Sta/Elev= 30
  3613.2  375.35  3743.2  369.88  3883.8  365.91  3963.1  366.43  4018.8  366.19
  4058.2  367.73  4142.4  367.22  4163.8   367.3  4221.2  367.75  4288.7  365.86
  4318.4  364.63  4356.2     363    5818  362.93  5835.5  366.31    5933  373.63
  6036.1  376.02    6082  374.37  6253.3  362.71    6256  362.21  6259.3  362.71
  6970.5     363    6998  366.04  7060.8  366.62  7172.3  370.87  7196.7  372.38
  7217.6  376.02  7228.1  376.46  7269.9  375.12  7412.1   381.9  7514.3  382.91
#Mann= 7 ,-1 , 0
  3613.2     .05       0  3963.1      .1       0  4142.4     .05       0
  4163.8      .1       0  4318.4     .05       0  6253.3    .033       0
  6259.3     .05       0
#XS Ineff= 2 , 0
                         6031.25          375.96
Permanent Ineff=
       F       F
Bank Sta=4288.7,5835.5
XS Rating Curve= 0 ,0
Exp/Cntr=0.3,0.1

Type RM Length L Ch R = 1 ,5811    ,1320,1320,1320
BEGIN DESCRIPTION:
BLAINS CREEK 1.0
END DESCRIPTION:
XS GIS Cut Line= 5
      3540519.35     10491873.52      3540340.53     10490529.01
      3539817.28     10490005.76      3539830.52     10489383.16
      3539519.22     10488442.61
#Sta/Elev= 30
    3948  376.47  4043.3  376.46  4070.9  374.74  4091.1  375.79  4313.1  370.93
  4373.6  370.94  4444.2  367.76  4509.1  366.69    4535  365.46  4542.1     363
  4544.8   362.5  4548.1     363  4611.5     363  6468.5     363  6478.5  363.25
  6488.6  365.13  6548.6  370.05  6598.6  372.65  6897.9  372.15  6998.3  373.87
  7005.7  374.65  7047.9  373.88  7111.1  375.47  7347.2   378.3  7395.5  377.25
  7479.8  379.74  7500.5  379.14  7553.5  379.96  7563.9  379.25  7657.8  381.43
#Mann= 5 ,-1 , 0
    3948     .05       0  4509.1      .1       0  4542.1    .033       0
  4548.1      .1       0  4611.5     .05       0
Bank Sta=4535,6488.6
XS Rating Curve= 0 ,0
Exp/Cntr=0.3,0.1

Type RM Length L Ch R = 1 ,4491    ,697,697,697
BEGIN DESCRIPTION:
BLAINS CREEK 1.01
END DESCRIPTION:
XS GIS Cut Line= 4
      3542195.08     10492317.34      3541625.47     10490429.66
      3541658.58     10490277.32      3540612.07      10487621.3
#Sta/Elev= 30
    3222  369.89  3246.6  370.29  3275.5  369.68  3290.6  369.15  3311.5  369.43
    3323  368.62  3342.8     369  3379.3  368.47  3531.3  365.31  3677.1  365.27
  3690.5  363.54  3693.2     363  3695.9   362.5  3699.2     363  7593.6     363
  7602.1  363.92 7607.31  365.25  7612.7  366.63    7618  366.25  7642.4  367.26
  7647.8  366.66  7672.2  366.53  7700.3  367.03    7840  371.95  7942.9   373.9
  7978.3  373.51  8010.6  374.63  8021.7  374.14  8129.3  375.81  8204.4  376.66
#Mann= 9 ,-1 , 0
    3222     .16       0  3275.5     .05       0  3379.3     .16       0
  3690.5     .05       0  3693.2    .033       0  3699.2     .05       0
  7700.3     .08       0  8021.7     .05       0  8129.3     .08       0
Bank Sta=3677.1,7607.31
XS Rating Curve= 0 ,0
Exp/Cntr=0.3,0.1

Type RM Length L Ch R = 1 ,3794    ,1261,1261,1261
BEGIN DESCRIPTION:
UNT0177 IN SAND CK 1.0
END DESCRIPTION:
XS GIS Cut Line= 4
      3542523.13     10491937.44       3542714.1     10491243.01
      3540995.35     10487354.12      3539710.64     10487249.96
#Sta/Elev= 30
  3350.9  372.09  3491.7  371.04  3551.6  367.05  3616.6  365.09  3647.3  365.05
  3657.7     363  7642.9     363  7646.4     363  7648.9  361.64  7651.7  361.14
  7654.9  361.64  7669.6  365.33  7675.2  366.57  7835.2  367.97    7932  367.12
    8000  368.57  8041.1  368.15  8093.2  369.28  8098.7  370.26    8122  371.09
  8220.7   372.2  8238.1  371.52  8313.9  371.92  8376.3  373.22  8413.4  375.26
  8466.6  374.51  8566.9  376.56  8837.8  375.87  9319.4  380.27  9611.8  379.55
#Mann= 6 ,-1 , 0
  3350.9     .16       0  3616.6     .05       0  7642.9      .1       0
  7648.9    .033       0  7654.9      .1       0  7835.2     .05       0
Bank Sta=3647.3,7669.6
XS Rating Curve= 0 ,0
Exp/Cntr=0.3,0.1

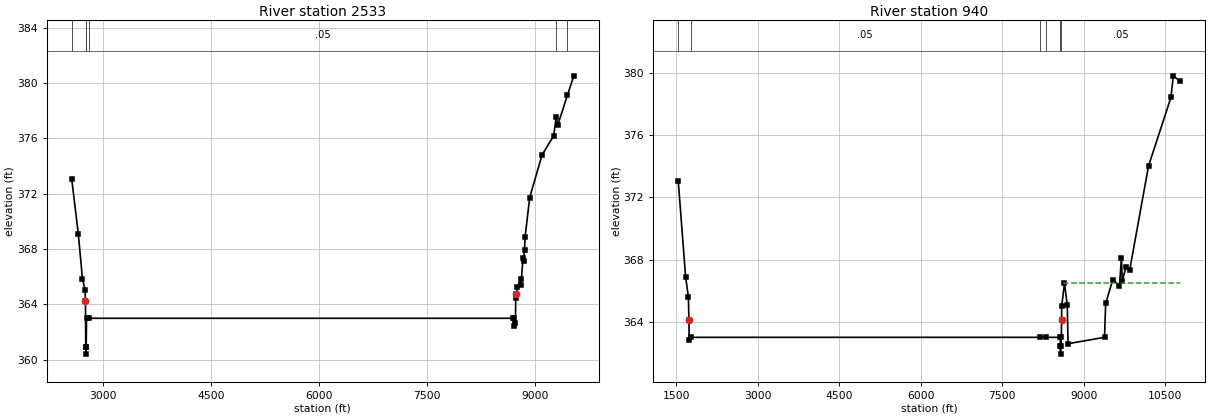
Type RM Length L Ch R = 1 ,2533    ,1593,1593,1593
BEGIN DESCRIPTION:
UNT0177 IN SAND CK 2.0
END DESCRIPTION:
XS GIS Cut Line= 4
      3542631.13      10491860.1      3543719.66     10490818.44
      3543427.77      10489598.9      3540736.93     10486352.53
#Sta/Elev= 30
  2564.5  373.03    2656  369.07  2712.7  365.86  2747.9  365.08  2755.1  364.23
    2759  360.91  2761.8  360.41    2765  360.91  2769.3     363  2804.6     363
  8700.2     363    8708  362.46  8714.5     363  8728.8  362.64 8736.19  364.76
  8743.1  364.47  8757.5  365.25  8800.5  365.84    8807  365.41  8835.6  367.37
  8842.1  367.16  8856.4  367.95  8864.3  368.88  8928.1  371.72  9098.7  374.79
  9261.5  376.19    9296  377.52  9318.8  376.97  9451.4   379.1  9541.7  380.52
#Mann= 6 ,-1 , 0
  2564.5     .16       0    2759    .033       0    2765     .16       0
  2804.6     .05       0    9296     .08       0  9451.4     .05       0
Bank Sta=2755.1,8736.19
XS Rating Curve= 0 ,0
Exp/Cntr=0.3,0.1

Type RM Length L Ch R = 1 ,940     ,0,0,0
BEGIN DESCRIPTION:
UNT0177 IN SAND CK 3.0
END DESCRIPTION:
XS GIS Cut Line= 4
      3542683.74      10491911.4       3544923.3     10490440.06
      3545118.62     10488773.39      3541017.12     10486117.18
#Sta/Elev= 30
  1536.4  373.06  1672.3  366.88  1723.5   365.6 1733.18   364.1  1737.9  362.86
  1762.6     363    8192     363  8308.6     363  8569.3     363  8572.3  362.42
    8575  361.92  8578.3  362.42  8590.4     363 8593.83   364.1  8596.4  364.99
  8647.8  366.49  8699.2  365.07  8713.6  362.59  9385.1     363  9406.2  365.18
  9536.1  366.69  9660.1  366.32  9696.3   368.1  9711.5  366.65    9784  367.53
  9847.4   367.3 10194.9  374.01 10607.9  378.42 10651.2  379.81 10780.6  379.45
#Mann= 6 ,-1 , 0
  1536.4     .16       0  1762.6     .05       0    8192      .1       0
  8308.6     .05       0  8572.3    .033       0  8578.3     .05       0
#XS Ineff= 2 , 0
                         8645.45          366.51
Permanent Ineff=
       F       F
Bank Sta=1733.18,8593.83
XS Rating Curve= 0 ,0
Exp/Cntr=0.3,0.1

Chan Stop Cuts=-1
Use User Specified Reach Order=0
Composite Channel Slope=5