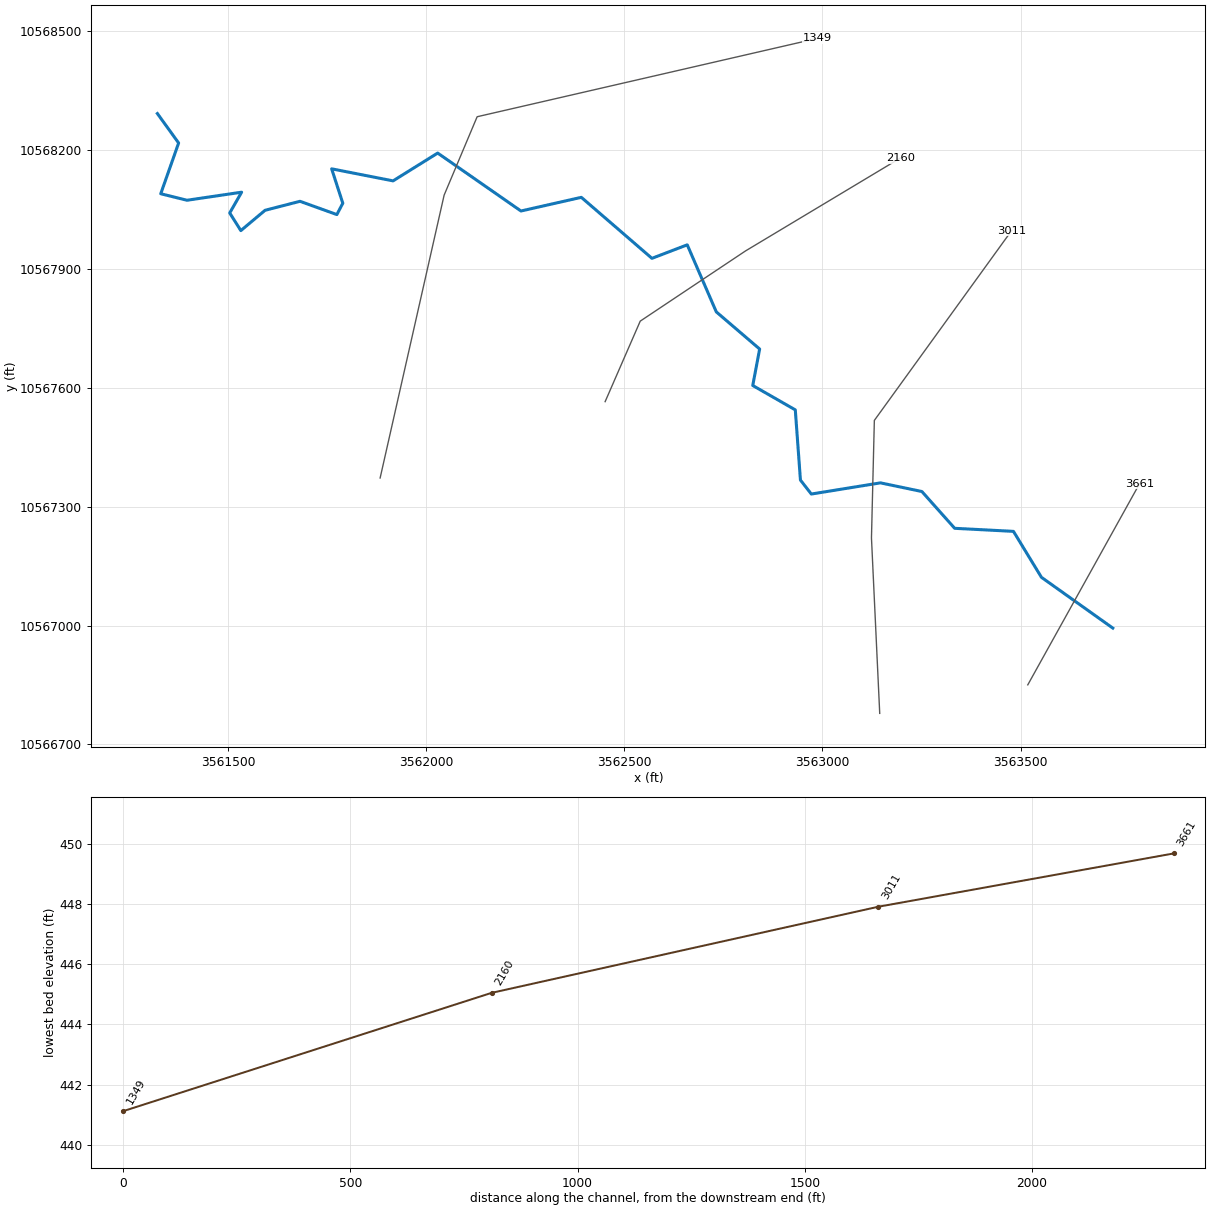
--- CASH BRANCH.prj (project) ---

Proj Title=CASH BRANCH Base Level Engineering
Current Plan=p01
Default Exp/Contr=0.3,0.1
English Units
Geom File=g01
Flow File=f01
Plan File=p01
BEGIN DESCRIPTION:
CASH BRANCH
END DESCRIPTION:

--- CASH BRANCH.p01 (plan) ---

Plan Title=Multiple Run
Short Identifier=Multiple
Geom File=g01
Flow File=f01
Subcritical Flow
K Sum by GR= 0
Std Step Tol= 0.01
Critical Tol= 0.01
Num of Std Step Trials= 20
Max Error Tol= 0.3
Flow Tol Ratio= 0.001
Split Flow NTrial= 30
Split Flow Tol= 0.02
Split Flow Ratio= 0.02
Log Output Level= 0
Friction Slope Method= 1
Unsteady Friction Slope Method= 2
Unsteady Bridges Friction Slope Method= 1
Parabolic Critical Depth
Global Vel Dist=  1 , 1 , 1
Global Log Level= 0
CheckData=True
Encroach Param= -1, 0, 0, 0
BEGIN DESCRIPTION:
Multiple Run
END DESCRIPTION:

--- CASH BRANCH.f01 (steady flow) ---

Flow Title=Multiple
Number of Profiles=7
Profile Names=10-year,25-year,50-year,1pct_min,100-year,1pct_plu,500-year
River Rch & RM= CASH BRANCH,Reach-1,3661
     980    1340    1634    1455    1968    2662    2845
Boundary for River Rch & Prof#=CASH BRANCH,Reach-1,1
Up Type=0
Dn Type=3
Dn Slope=0.005
Boundary for River Rch & Prof#=CASH BRANCH,Reach-1,2
Up Type=0
Dn Type=3
Dn Slope=0.005
Boundary for River Rch & Prof#=CASH BRANCH,Reach-1,3
Up Type=0
Dn Type=3
Dn Slope=0.005
Boundary for River Rch & Prof#=CASH BRANCH,Reach-1,4
Up Type=0
Dn Type=3
Dn Slope=0.005
Boundary for River Rch & Prof#=CASH BRANCH,Reach-1,5
Up Type=0
Dn Type=3
Dn Slope=0.005
Boundary for River Rch & Prof#=CASH BRANCH,Reach-1,6
Up Type=0
Dn Type=3
Dn Slope=0.005
Boundary for River Rch & Prof#=CASH BRANCH,Reach-1,7
Up Type=0
Dn Type=3
Dn Slope=0.005

--- CASH BRANCH.g01 (geometry) ---

Geom Title=Existing Conditions

River Reach=CASH BRANCH,Reach-1
Reach XY= 30
      3563732.47     10566993.58      3563552.44     10567121.67
      3563481.80     10567237.59      3563333.58     10567245.29
      3563250.81     10567338.13      3563146.26     10567359.95
      3562971.86     10567331.73      3562944.42     10567367.01
      3562931.44     10567544.11      3562824.14     10567605.57
      3562841.51     10567697.58      3562732.13     10567791.33
      3562658.87     10567960.43      3562569.77     10567926.40
      3562391.64     10568080.28      3562239.34     10568045.81
      3562029.28     10568191.95      3561916.66     10568121.81
      3561761.75     10568152.20      3561789.89     10568065.43
      3561774.85     10568036.77      3561681.92     10568070.28
      3561593.77     10568047.57      3561532.65     10567996.36
      3561504.58     10568040.88      3561534.65     10568093.25
      3561396.75     10568072.90      3561330.60     10568089.37
      3561375.70     10568217.39      3561322.11     10568291.64

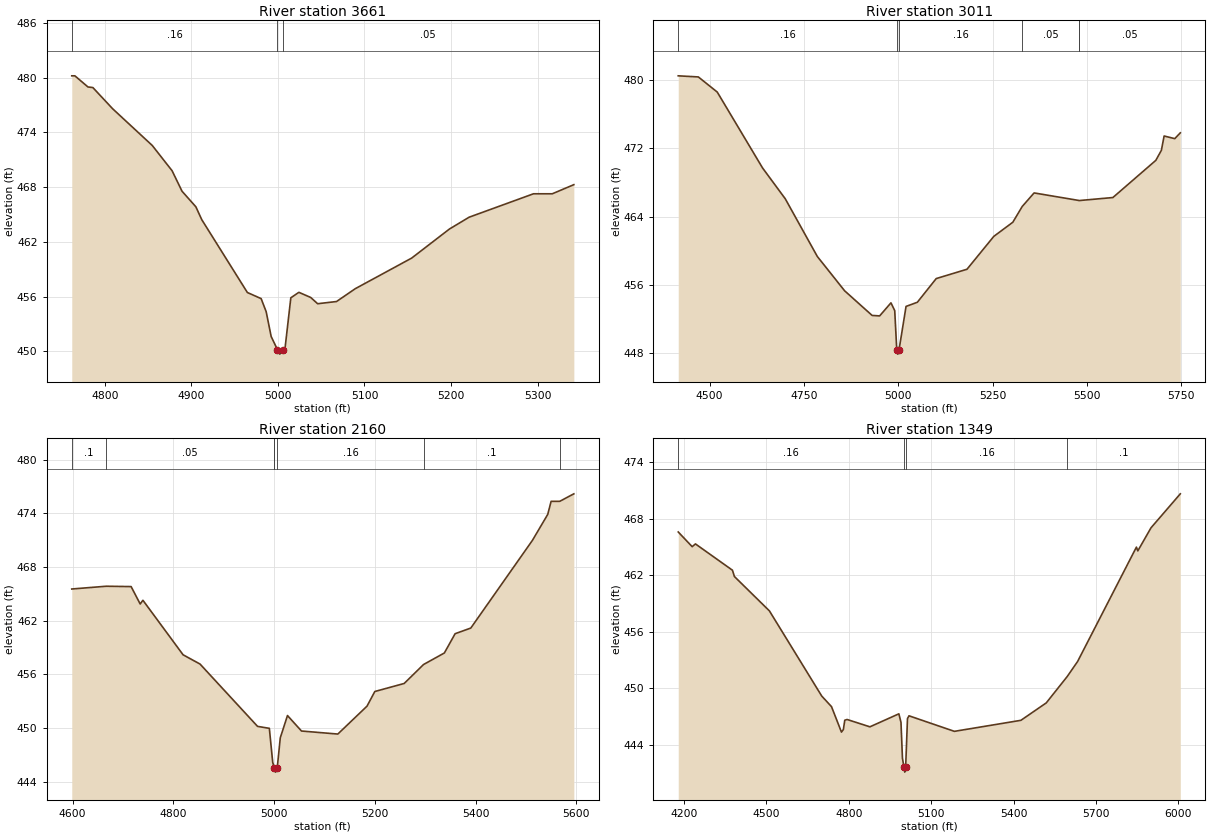
Type RM Length L Ch R = 1,3661,650,650,650
BEGIN DESCRIPTION:
CASH BRANCH 5.0
END DESCRIPTION:
XS GIS Cut Line= 2
      3563517.97     10566850.35      3563799.69     10567357.45
#Sta/Elev= 30
  4761.8  480.21  4765.4  480.21  4780.5  478.99  4786.2  478.92  4809.0  476.60
  4854.8  472.57  4877.7  469.80  4889.2  467.55  4905.2  465.84  4912.0  464.43
  4964.7  456.44  4980.6  455.77  4986.4  454.34  4992.2  451.61  4999.4  450.18
  5002.2  449.68  5005.4  450.18  5008.2  450.31  5014.9  455.86  5024.2  456.46
  5037.8  455.90  5045.9  455.21  5067.7  455.45  5089.4  456.86  5154.6  460.22
  5198.1  463.40  5220.9  464.70  5295.3  467.27  5317.0  467.27  5341.9  468.27
#Mann=3,-1,0
  4761.8    0.16       0  4999.4    0.07       0  5005.4    0.05       0
Bank Sta=4999.4,5005.4
Exp/Cntr=0.3,0.1

Type RM Length L Ch R = 1,3011,851,851,851
BEGIN DESCRIPTION:
CASH BRANCH 3.0
END DESCRIPTION:
XS GIS Cut Line= 4
      3563144.44     10566778.40      3563123.61     10567221.12
      3563130.89     10567517.50      3563477.23     10567996.41
#Sta/Elev= 30
  4416.8  480.47  4470.1  480.34  4520.2  478.57  4640.3  469.69  4700.4  466.09
  4785.5  459.33  4857.8  455.32  4930.6  452.44  4950.6  452.38  4980.6  453.91
  4990.6  453.00  4996.0  448.41  4998.7  447.91  5002.0  448.41  5020.6  453.49
  5050.6  453.98  5100.6  456.75  5182.1  457.84  5253.3  461.69  5303.6  463.34
  5328.6  465.19  5360.0  466.77  5479.6  465.88  5480.3  465.88  5568.8  466.23
  5682.6  470.58  5697.3  471.75  5704.6  473.43  5732.8  473.12  5747.5  473.80
#Mann=6,-1,0
  4416.8    0.16       0  4996.0    0.07       0  5002.0    0.16       0
  5328.6    0.05       0  5479.6     0.1       0  5480.3    0.05       0
Bank Sta=4996,5002
Exp/Cntr=0.3,0.1

Type RM Length L Ch R = 1,2160,811,811,811
BEGIN DESCRIPTION:
CASH BRANCH 2.0
END DESCRIPTION:
XS GIS Cut Line= 4
      3562451.72     10567564.83      3562540.28     10567767.99
      3562805.90     10567945.08      3563196.51     10568179.44
#Sta/Elev= 30
  4598.5  465.54  4666.7  465.85  4716.3  465.81  4734.3  463.86  4739.7  464.28
  4819.4  458.18  4853.1  457.14  4967.2  450.17  4990.6  449.95  4997.3  446.14
  4999.7  445.67  5000.3  445.55  5003.0  445.05  5006.3  445.55  5012.3  448.89
  5026.6  451.38  5054.4  449.65  5126.5  449.31  5184.4  452.43  5199.9  454.07
  5258.2  454.97  5296.6  457.09  5337.9  458.38  5359.3  460.54  5390.4  461.17
  5512.8  470.99  5543.1  473.89  5549.8  475.35  5566.9  475.35  5594.9  476.19
#Mann=7,-1,0
  4598.5     0.1       0  4666.7    0.05       0  4999.7    0.16       0
  5000.3    0.07       0  5006.3    0.16       0  5296.6     0.1       0
  5566.9    0.05       0
Bank Sta=5000.3,5006.3
Exp/Cntr=0.3,0.1

Type RM Length L Ch R = 1,1349,0,0,0
BEGIN DESCRIPTION:
CASH BRANCH 1.0
END DESCRIPTION:
XS GIS Cut Line= 4
      3561884.03     10567372.17      3562045.48     10568085.70
      3562128.82     10568283.62      3562987.62     10568481.41
#Sta/Elev= 30
  4179.1  466.62  4229.8  465.06  4241.8  465.35  4376.4  462.56  4383.6  461.89
  4511.0  458.24  4701.4  449.20  4737.1  448.07  4773.2  445.37  4780.2  445.64
  4785.3  446.63  4793.7  446.71  4876.8  445.93  4982.2  447.31  4989.9  446.41
  4995.3  442.59  5000.9  441.62  5003.7  441.12  5006.9  441.62  5013.6  446.81
  5019.1  447.10  5184.3  445.45  5426.4  446.62  5518.7  448.47  5595.0  451.27
  5632.9  452.87  5846.9  465.01  5852.0  464.61  5900.0  467.06  6006.7  470.67
#Mann=4,-1,0
  4179.1    0.16       0  5000.9    0.07       0  5006.9    0.16       0
  5595.0     0.1       0
Bank Sta=5000.9,5006.9
Exp/Cntr=0.3,0.1

Chan Stop Cuts=-1