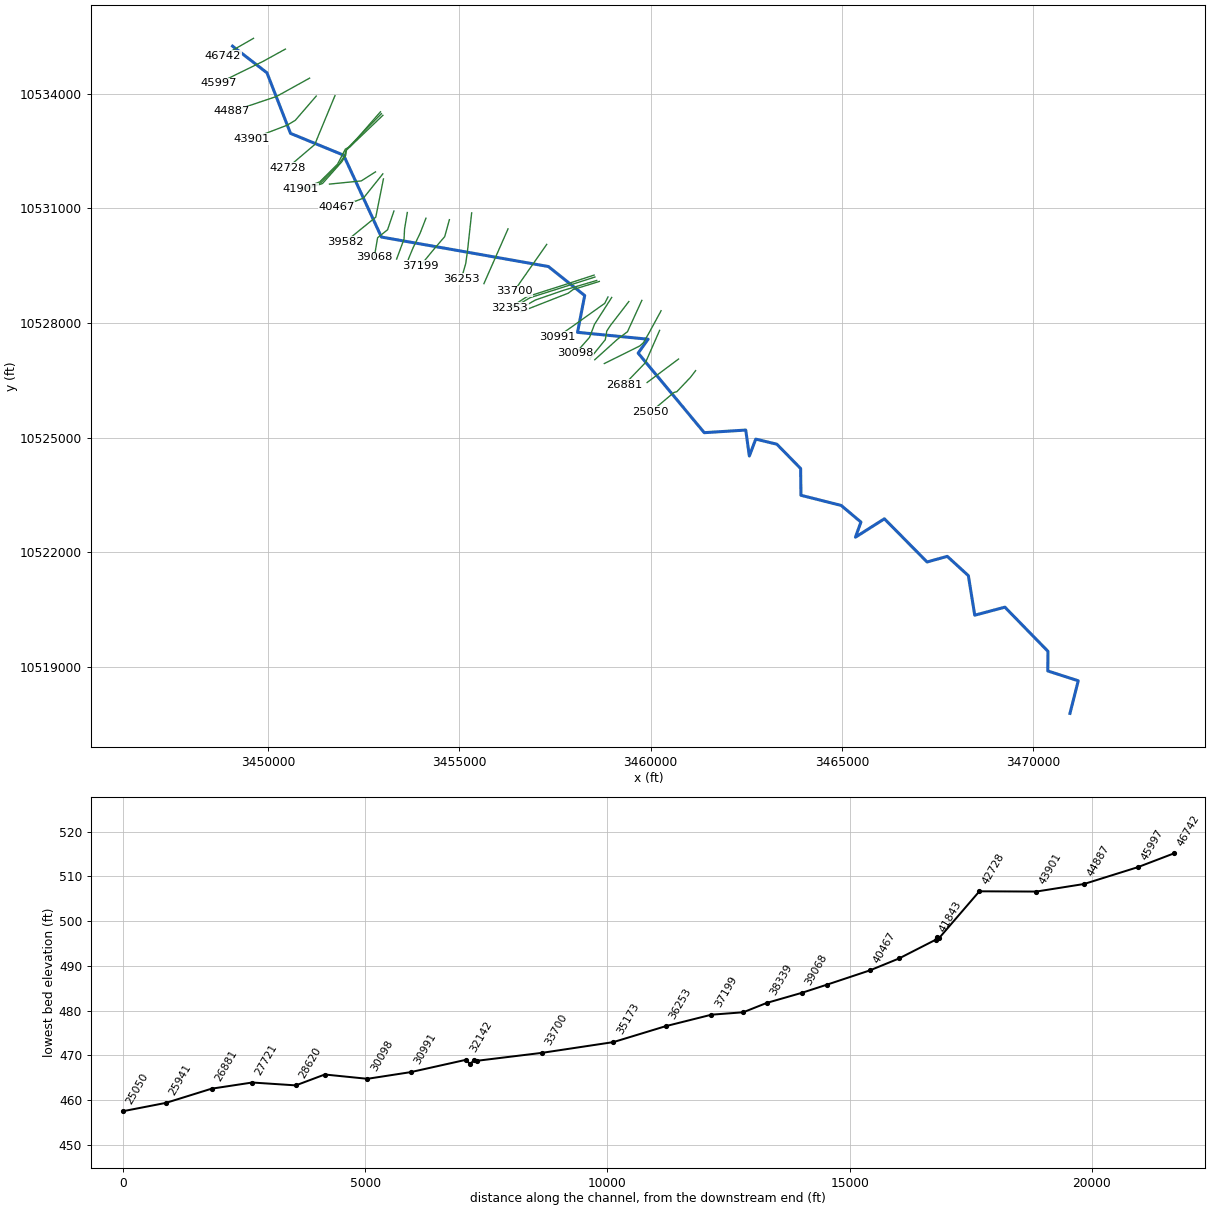
--- CEDAR CREEK 1.prj (project) ---

Proj Title=CEDAR CREEK 1 Base Level Engineering
Current Plan=p01
Default Exp/Contr=0.3,0.1
English Units
Geom File=g01
Flow File=f01
Plan File=p01
Y Axis Title=Elevation
X Axis Title(PF)=Main Channel Distance
X Axis Title(XS)=Station
BEGIN DESCRIPTION:
CEDAR CREEK 1
END DESCRIPTION:
DSS Export Rating Curves= 0
DSS Export Rating Curve Sorted= 0
DSS Export Volume Flow Curves= 0
DXF OffsetX= 0
DXF OffsetY= 0
DXF ScaleX= 1
DXF ScaleY= 10

--- CEDAR CREEK 1.p01 (plan) ---

Plan Title=Multiple Run
Short Identifier=Multiple
Geom File=g01
Flow File=f01
Subcritical Flow
K Sum by GR= 0
Std Step Tol= 0.01
Critical Tol= 0.01
Num of Std Step Trials= 20
Max Error Tol= 0.3
Flow Tol Ratio= 0.001
Split Flow NTrial= 30
Split Flow Tol= 0.02
Split Flow Ratio= 0.02
Log Output Level= 0
Friction Slope Method= 1
Unsteady Friction Slope Method= 2
Unsteady Bridges Friction Slope Method= 1
Parabolic Critical Depth
Global Vel Dist=  1 , 1 , 1
Global Log Level= 0
CheckData=True
Encroach Param= -1, 0, 0, 0
BEGIN DESCRIPTION:
Multiple Run
END DESCRIPTION:

--- CEDAR CREEK 1.f01 (steady flow) ---

Flow Title=Multiple
Program Version=4.10
Number of Profiles= 7
Profile Names=10-year,25-year,50-year,1pct_min,100-year,1pct_plu,500-year
River Rch & RM=CEDAR CREEK 1,Reach-1         ,46742
     890    1213    1478    1314    1777    2403    2561
River Rch & RM=CEDAR CREEK 1,Reach-1         ,44887
    1414    1976    2447    2207    2984    4036    4431
River Rch & RM=CEDAR CREEK 1,Reach-1         ,39068
    1796    2533    3155    2860    3867    5230    5800
River Rch & RM=CEDAR CREEK 1,Reach-1         ,33700
    2089    2952    3680    3336    4511    6101    6766
River Rch & RM=CEDAR CREEK 1,Reach-1         ,24933
    2933    4199    5282    4824    6524    8823    9939
River Rch & RM=CEDAR CREEK 1,Reach-1         ,10872
    3213    4616    5819    5326    7203    9742   11020
River Rch & RM=CEDAR CREEK 1,Reach-1         ,7962
    3488    5020    6337    5806    7851   10618   12034
River Rch & RM=CEDAR CREEK 1,Reach-1         ,5247
    3504    5037    6352    5813    7862   10632   12024
Boundary for River Rch & Prof#=CEDAR CREEK 1,Reach-1         , 1
Up Type= 0
Dn Type= 3
Dn Slope=0.002
Boundary for River Rch & Prof#=CEDAR CREEK 1,Reach-1         , 2
Up Type= 0
Dn Type= 3
Dn Slope=0.002
Boundary for River Rch & Prof#=CEDAR CREEK 1,Reach-1         , 3
Up Type= 0
Dn Type= 3
Dn Slope=0.002
Boundary for River Rch & Prof#=CEDAR CREEK 1,Reach-1         , 4
Up Type= 0
Dn Type= 3
Dn Slope=0.002
Boundary for River Rch & Prof#=CEDAR CREEK 1,Reach-1         , 5
Up Type= 0
Dn Type= 3
Dn Slope=0.002
Boundary for River Rch & Prof#=CEDAR CREEK 1,Reach-1         , 6
Up Type= 0
Dn Type= 3
Dn Slope=0.002
Boundary for River Rch & Prof#=CEDAR CREEK 1,Reach-1         , 7
Up Type= 0
Dn Type= 3
Dn Slope=0.002
DSS Import GetInterval= 0
DSS Import GetPeak= 0
DSS Import FillOption= 0

--- CEDAR CREEK 1.g01 (geometry) ---

Geom Title=Existing Conditions
Program Version=4.10

River Reach=CEDAR CREEK 1   ,Reach-1
Reach XY= 30
      3449074.45     10535242.83       3449973.3     10534545.91
       3450589.6     10532961.25      3451976.62     10532391.49
      3452965.37     10530250.26       3457329.5     10529478.96
      3458278.26     10528720.03      3458090.82     10527757.89
       3459935.6     10527578.14       3459675.7     10527214.24
      3461403.55      10525133.3       3462487.7     10525201.72
      3462581.87     10524522.72      3462749.26     10524965.33
      3463301.84     10524830.92      3463922.34     10524196.39
      3463930.48     10523496.01      3464981.73      10523230.4
      3465498.54     10522794.93        3465355.     10522399.61
      3466111.89     10522880.92      3467227.12     10521751.71
       3467755.2     10521898.52       3468306.2     10521394.12
      3468473.12     10520359.39      3469261.22     10520569.29
       3470387.1      10519414.2      3470381.77     10518901.21
      3471177.99     10518644.38      3470962.11     10517791.64

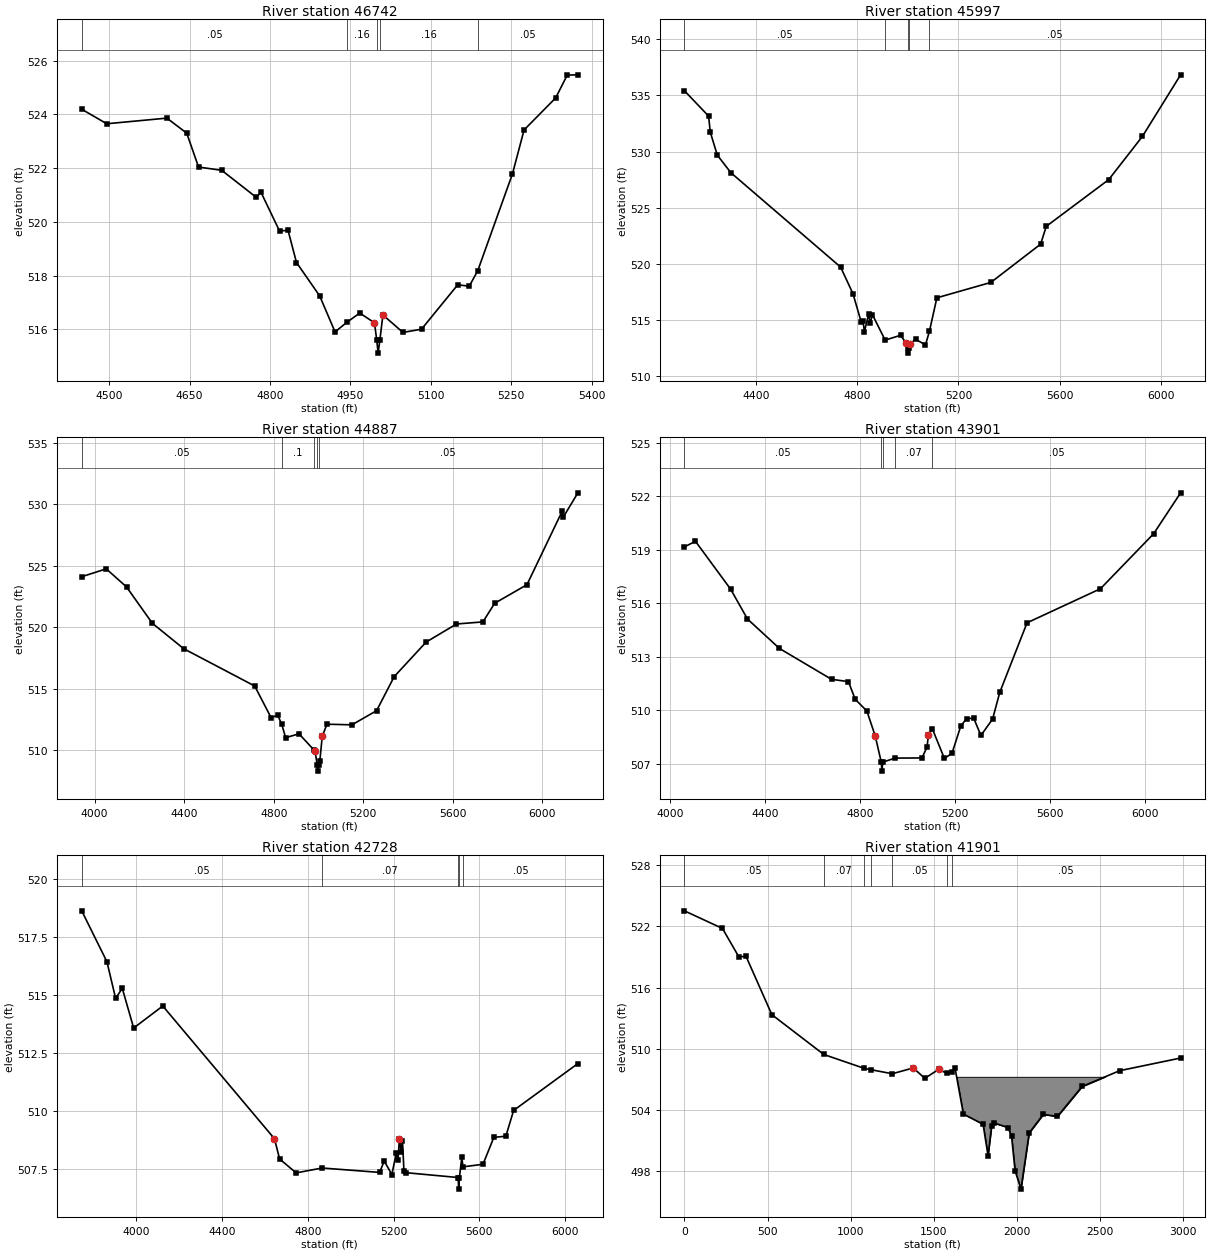
Type RM Length L Ch R = 1 ,46742   ,745,745,745
BEGIN DESCRIPTION:
CEDAR CREEK 1 45.0
END DESCRIPTION:
XS GIS Cut Line= 2
      3449622.07     10535447.34      3448819.04     10534987.23
#Sta/Elev= 30
  4448.8  524.19  4495.5  523.65  4607.7  523.86  4644.7   523.3  4666.7  522.04
  4709.9  521.92  4774.6  520.91    4783  521.11  4817.8  519.66  4833.6  519.69
  4849.4  518.49  4892.6  517.25  4921.3  515.91  4944.3  516.28  4967.4  516.61
  4994.8  516.25    4999  515.62  5001.7  515.12    5005  515.62  5010.6  516.54
    5048  515.89  5082.6  516.01  5150.1  517.66  5171.7  517.61  5187.4  518.18
  5252.3  521.79  5273.9  523.42  5332.8  524.61  5354.4  525.46  5374.3  525.47
#Mann= 5 ,-1 , 0
  4448.8     .05       0  4944.3     .16       0    4999     .07       0
    5005     .16       0  5187.4     .05       0
Bank Sta=4994.8,5010.6
XS Rating Curve= 0 ,0
Exp/Cntr=0.3,0.1

Type RM Length L Ch R = 1 ,45997   ,1110,1110,1110
BEGIN DESCRIPTION:
CEDAR CREEK 1 44.0
END DESCRIPTION:
XS GIS Cut Line= 3
      3450455.97     10535166.36       3449876.1      10534846.9
      3448706.51     10534274.26
#Sta/Elev= 30
  4115.1  535.42  4210.9  533.16  4217.3  531.74  4245.1  529.69  4298.8  528.12
  4733.3  519.71  4782.4  517.33    4815   514.8  4821.9  514.94  4827.5  513.95
  4844.4  515.53    4850  514.71  4859.5  515.46  4909.7   513.2  4970.9  513.63
  4993.1  512.92  4998.9  512.54  5001.7  512.04  5004.9  512.54  5007.5  512.86
    5030  513.27  5069.4  512.78  5084.8  513.97  5114.5  516.97  5328.1  518.34
  5525.1  521.75  5547.6  523.34  5794.8   527.5  5928.4  531.36  6079.4  536.84
#Mann= 5 ,-1 , 0
  4115.1     .05       0  4909.7      .1       0  4998.9     .07       0
  5004.9      .1       0  5084.8     .05       0
Bank Sta=4993.1,5007.5
XS Rating Curve= 0 ,0
Exp/Cntr=0.3,0.1

Type RM Length L Ch R = 1 ,44887   ,986,986,986
BEGIN DESCRIPTION:
CEDAR CREEK 1 42.0
END DESCRIPTION:
XS GIS Cut Line= 3
      3451087.89     10534405.93      3450223.32     10533926.76
      3449060.09     10533534.39
#Sta/Elev= 30
  3942.2  524.11  4051.7  524.75  4142.2  523.28  4257.5  520.32  4397.5  518.25
  4714.8  515.21  4787.8  512.64  4817.7  512.83  4835.2  512.11  4853.1     511
  4912.6  511.32    4979  510.01  4984.7  509.88  4994.1  508.78  4996.8  508.28
  5000.1  508.78  5005.8  509.12  5016.4  511.11  5037.5   512.1  5149.2  512.05
  5259.1   513.2    5338  515.98  5480.7  518.79    5616  520.26    5734  520.43
  5786.8  521.95  5930.8  523.46  6088.1  529.44  6093.4  528.97  6158.3  530.94
#Mann= 5 ,-1 , 0
  3942.2     .05       0  4835.2      .1       0    4979     .05       0
  4994.1     .03       0  5000.1     .05       0
Bank Sta=4984.7,5016.4
XS Rating Curve= 0 ,0
Exp/Cntr=0.3,0.1

Type RM Length L Ch R = 1 ,43901   ,1173,1173,1173
BEGIN DESCRIPTION:
CEDAR CREEK 1 41.0
END DESCRIPTION:
XS GIS Cut Line= 4
       3451261.5     10533937.16       3450712.9     10533301.76
      3450497.63     10533173.29      3449561.39     10532816.14
#Sta/Elev= 30
  4059.6  519.17  4106.1  519.48  4254.2   516.8  4325.5  515.12  4460.4  513.47
  4679.8  511.74  4751.1  511.61  4779.6  510.62    4829  509.96  4864.1  508.56
  4889.6  507.09  4892.4  506.59  4895.6  507.09  4947.1  507.32  5061.2  507.33
  5082.6  507.94  5088.4  508.63  5105.4  508.95  5155.7   507.3  5187.8  507.59
  5224.9  509.12  5249.6  509.54  5279.7  509.55  5309.8  508.59    5359  509.51
  5389.3  511.01  5504.3  514.91  5813.8  516.82  6038.4  519.91  6151.8   522.2
#Mann= 5 ,-1 , 0
  4059.6     .05       0  4889.6     .07       0  4895.6     .05       0
  4947.1     .07       0  5105.4     .05       0
Bank Sta=4864.1,5088.4
XS Rating Curve= 0 ,0
Exp/Cntr=0.3,0.1

Type RM Length L Ch R = 1 ,42728   ,827,827,827
BEGIN DESCRIPTION:
CEDAR CREEK 1 40.0
END DESCRIPTION:
XS GIS Cut Line= 4
      3451751.08     10533947.56      3451320.54      10532909.4
      3451223.32     10532669.82      3450515.02     10532065.68
#Sta/Elev= 30
  3746.2  518.64  3863.6  516.45  3904.2  514.87  3935.3   515.3  3988.4  513.59
  4124.1  514.54  4644.9  508.82  4668.8  507.95  4745.9  507.35  4867.1  507.56
  5135.2  507.37  5156.5  507.86  5192.3  507.28  5213.1  508.22  5220.8   507.9
  5227.4  508.83  5235.1  508.26  5241.7  508.74  5248.5  507.44    5256  507.36
  5501.1  507.15  5503.9  506.65  5507.1  507.15  5518.4  508.02  5523.7  507.61
  5617.2  507.72  5667.7  508.88  5723.7  508.93  5759.9  510.04  6059.6  512.06
#Mann= 5 ,-1 , 0
  3746.2     .05       0  4867.1     .07       0  5501.1     .07       0
  5507.1     .07       0  5523.7     .05       0
Bank Sta=4644.9,5227.4
XS Rating Curve= 0 ,0
Exp/Cntr=0.3,0.1

Type RM Length L Ch R = 1 ,41901   ,39,39,39
BEGIN DESCRIPTION:
CEDAR CREEK 1 38.02
END DESCRIPTION:
XS GIS Cut Line= 6
      3452940.31     10533526.01      3452146.61     10532617.04
      3452022.48     10532549.34       3451819.1     10532156.97
      3451352.95     10531692.13      3450853.51     10531508.65
#Sta/Elev= 30
       0  523.53   228.9   521.8   327.6  519.01   370.3  519.08     526  513.35
   838.3  509.45  1079.4   508.1  1121.2  507.96  1250.5  507.56  1376.8  508.13
    1446  507.11    1529  507.98  1578.7  507.61  1607.5  507.71    1628  508.12
  1678.3  503.61  1796.7  502.61  1826.6  499.53  1847.8  502.39    1862  502.74
  1946.8  502.29    1968  501.44  1989.3  498.06  2024.6  496.25  2074.1  501.76
    2159  503.58  2243.8  503.37  2392.3  506.31  2618.5  507.86  2985.2   509.1
#Mann= 7 ,-1 , 0
       0     .05       0   838.3     .07       0  1079.4     .05       0
  1121.2     .16       0  1250.5     .05       0  1578.7     .07       0
  1607.5     .05       0
#Block Obstruct= 1 ,-1
 1639.91 2551.87  507.26
Bank Sta=1376.8,1529
XS Rating Curve= 0 ,0
Exp/Cntr=0.3,0.1

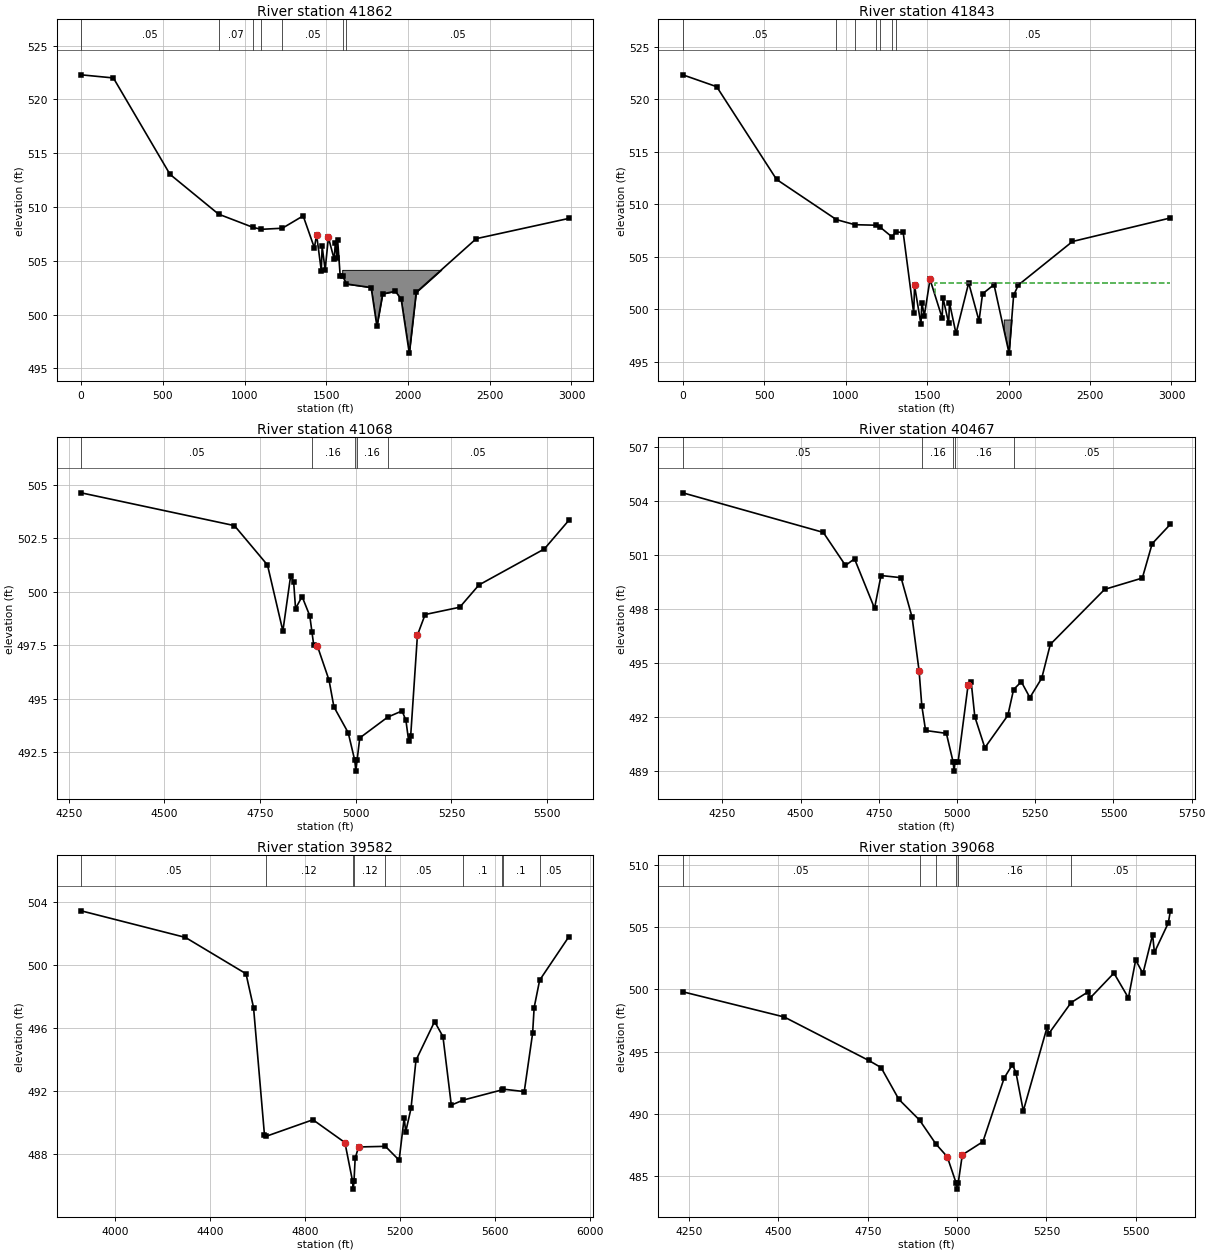
Type RM Length L Ch R = 1 ,41862   ,33,33,33
BEGIN DESCRIPTION:
CEDAR CREEK 1 38.0
END DESCRIPTION:
XS GIS Cut Line= 6
      3452964.62      10533477.4      3452044.08     10532537.85
      3452002.85     10532375.09      3451850.94     10532151.56
       3451381.1     10531668.49      3450863.93     10531480.87
#Sta/Elev= 30
       0  522.29   197.1     522   543.5  513.04   840.6  509.34  1053.2   508.1
  1102.6  507.93  1230.8  508.03  1358.2  509.18  1426.8  506.21  1440.5  507.42
  1469.2  504.07  1474.4  506.35  1492.6  504.16  1512.7  507.17    1548  505.15
  1555.1  506.65  1566.8  505.22    1569  506.97  1584.9  503.57    1599  503.63
    1622  502.85    1774  502.52  1809.3  498.92  1844.6  501.93  1922.5  502.17
  1957.8  501.43  2007.4  496.42  2049.8  502.07  2417.4  507.06    2983  508.94
#Mann= 7 ,-1 , 0
       0     .05       0   840.6     .07       0  1053.2     .12       0
  1102.6     .16       0  1230.8     .05       0    1599     .07       0
    1622     .05       0
#Block Obstruct= 1 ,-1
 1597.02 2261.84  504.16
Bank Sta=1440.5,1512.7
XS Rating Curve= 0 ,0
Exp/Cntr=0.3,0.1

Type RM Length L Ch R = 1 ,41843   ,761,761,761
BEGIN DESCRIPTION:
CEDAR CREEK 1 38.01
END DESCRIPTION:
XS GIS Cut Line= 6
      3453003.68       10533434.      3452051.24     10532522.37
      3452031.28     10532386.08      3451930.58     10532218.55
      3451427.11     10531651.71      3450882.15     10531465.25
#Sta/Elev= 30
       0  522.34   207.9  521.21   575.6  512.38   943.3  508.55  1056.4  508.07
  1183.6  508.02  1211.9  507.83  1283.9  506.91  1307.1  507.37  1352.8  507.34
  1417.6  499.62  1422.7  502.28  1461.9  498.58  1467.7  500.64  1482.6  499.41
  1517.8  502.86  1592.1  499.19  1597.3  501.11    1632  498.69  1637.2  500.63
  1677.2  497.71    1755  502.53  1818.5  498.91  1840.3  501.49  1910.5  502.36
  2002.7  495.84  2030.9  501.33  2059.4  502.32  2392.2  506.47  2993.2  508.71
#Mann= 7 ,-1 , 0
       0     .05       0   943.3     .07       0  1056.4     .12       0
  1183.6     .16       0  1211.9     .05       0  1283.9     .07       0
  1307.1     .05       0
#XS Ineff= 2 , 0
       0                 1546.37       0  502.56
Permanent Ineff=
       F       T
#Block Obstruct= 1 ,-1
 1970.44 2020.41  499.04
Bank Sta=1422.7,1517.8
XS Rating Curve= 0 ,0
Exp/Cntr=0.3,0.1

Type RM Length L Ch R = 1 ,41068   ,601,601,601
BEGIN DESCRIPTION:
CEDAR CREEK 1 36.0
END DESCRIPTION:
XS GIS Cut Line= 3
      3452810.16     10531954.56       3452438.6     10531718.43
      3451608.72      10531635.1
#Sta/Elev= 30
  4282.3  504.62  4682.8  503.09  4769.3  501.25  4809.5  498.17  4829.6  500.72
  4837.6  500.48  4842.6  499.22  4859.7  499.78  4879.8  498.88  4885.4  498.14
  4889.9  497.54  4899.9  497.46  4930.1  495.88  4942.9  494.63  4980.3  493.42
  4997.4  492.13  5000.2  491.63  5003.4  492.13  5010.5  493.18  5083.4  494.15
    5121  494.44  5131.1     494  5138.4  493.02  5143.5  493.26  5161.2  497.98
  5181.3  498.94  5271.8  499.28    5322  500.32  5492.9     502  5556.6  503.33
#Mann= 5 ,-1 , 0
  4282.3     .05       0  4885.4     .16       0  4997.4     .07       0
  5003.4     .16       0  5083.4     .05       0
Bank Sta=4899.9,5161.2
XS Rating Curve= 0 ,0
Exp/Cntr=0.3,0.1

Type RM Length L Ch R = 1 ,40467   ,885,885,885
BEGIN DESCRIPTION:
CEDAR CREEK 1 35.0
END DESCRIPTION:
XS GIS Cut Line= 4
      3453002.45     10531902.24      3452494.15     10531267.04
      3452303.18     10531194.13       3451786.5     10531034.61
#Sta/Elev= 30
  4123.2  504.45  4572.2  502.25  4643.3  500.41  4672.1  500.78  4736.1  498.03
  4756.9  499.85    4821  499.73  4856.2  497.53  4878.6  494.54  4887.3   492.6
  4899.4  491.23  4965.8  491.07  4987.5  489.47  4990.3  488.97  4993.5  489.47
  5003.2  489.47  5035.3  493.77  5045.3   493.9  5056.7     492  5088.8  490.27
  5162.3  492.07  5180.7  493.51  5205.4  493.94  5232.8  493.06  5270.7  494.14
  5298.1  496.02  5471.8  499.08  5592.3  499.71  5623.7  501.62  5681.9   502.7
#Mann= 5 ,-1 , 0
  4123.2     .05       0  4887.3     .16       0  4987.5     .07       0
  4993.5     .16       0  5180.7     .05       0
Bank Sta=4878.6,5035.3
XS Rating Curve= 0 ,0
Exp/Cntr=0.3,0.1

Type RM Length L Ch R = 1 ,39582   ,514,514,514
BEGIN DESCRIPTION:
CEDAR CREEK 1 33.0
END DESCRIPTION:
XS GIS Cut Line= 3
       3453018.5     10531771.51      3452818.49      10530771.5
      3452018.49      10530121.5
#Sta/Elev= 30
  3857.8  503.47  4296.2  501.78  4551.1  499.47  4582.8  497.32  4628.7  489.23
  4634.3  489.13  4832.6  490.19  4967.1  488.74  4999.3  486.28    5002  485.78
  5005.3  486.28  5010.2  487.74  5024.6  488.46  5137.3   488.5  5195.1  487.62
  5216.4  490.32  5222.8  489.42  5245.1  490.91  5265.9  493.97  5344.2  496.43
  5379.4  495.48  5414.6  491.12  5464.5  491.44  5628.1  492.09  5630.1  492.14
  5721.4  491.98  5756.5  495.68    5763  497.32  5786.1  499.06  5908.4  501.81
#Mann= 9 ,-1 , 0
  3857.8     .05       0  4634.3     .12       0  4999.3     .07       0
  5005.3     .12       0  5137.3     .05       0  5464.5      .1       0
  5628.1     .16       0  5630.1      .1       0  5786.1     .05       0
#XS Ineff= 2 , 0
                         5344.37          496.42
Permanent Ineff=
       F       F
Bank Sta=4967.1,5024.6
XS Rating Curve= 0 ,0
Exp/Cntr=0.3,0.1

Type RM Length L Ch R = 1 ,39068   ,729,729,729
BEGIN DESCRIPTION:
CEDAR CREEK 1 32.0
END DESCRIPTION:
XS GIS Cut Line= 4
       3453292.1     10530930.23       3453126.1     10530440.65
      3452865.68     10530232.32      3452778.99     10529726.04
#Sta/Elev= 30
  4232.7  499.81  4516.3  497.79  4752.9   494.3  4787.4  493.73  4837.1  491.18
  4895.1  489.51  4940.9  487.59  4972.5  486.57  4997.3  484.47  5000.1  483.97
  5003.3  484.47  5014.7  486.72  5072.4  487.78  5131.7  492.88  5154.9  493.97
    5165   493.3  5185.3  490.25  5251.8  496.95  5256.9  496.46    5319  498.94
  5366.9  499.81    5372   499.3  5438.9  501.31  5479.5  499.32  5499.8  502.36
  5520.1  501.28  5547.1  504.39  5552.2  502.97  5591.1  505.34  5596.8  506.31
#Mann= 6 ,-1 , 0
  4232.7     .05       0  4895.1     .12       0  4940.9     .16       0
  4997.3     .07       0  5003.3     .16       0    5319     .05       0
Bank Sta=4972.5,5014.7
XS Rating Curve= 0 ,0
Exp/Cntr=0.3,0.1

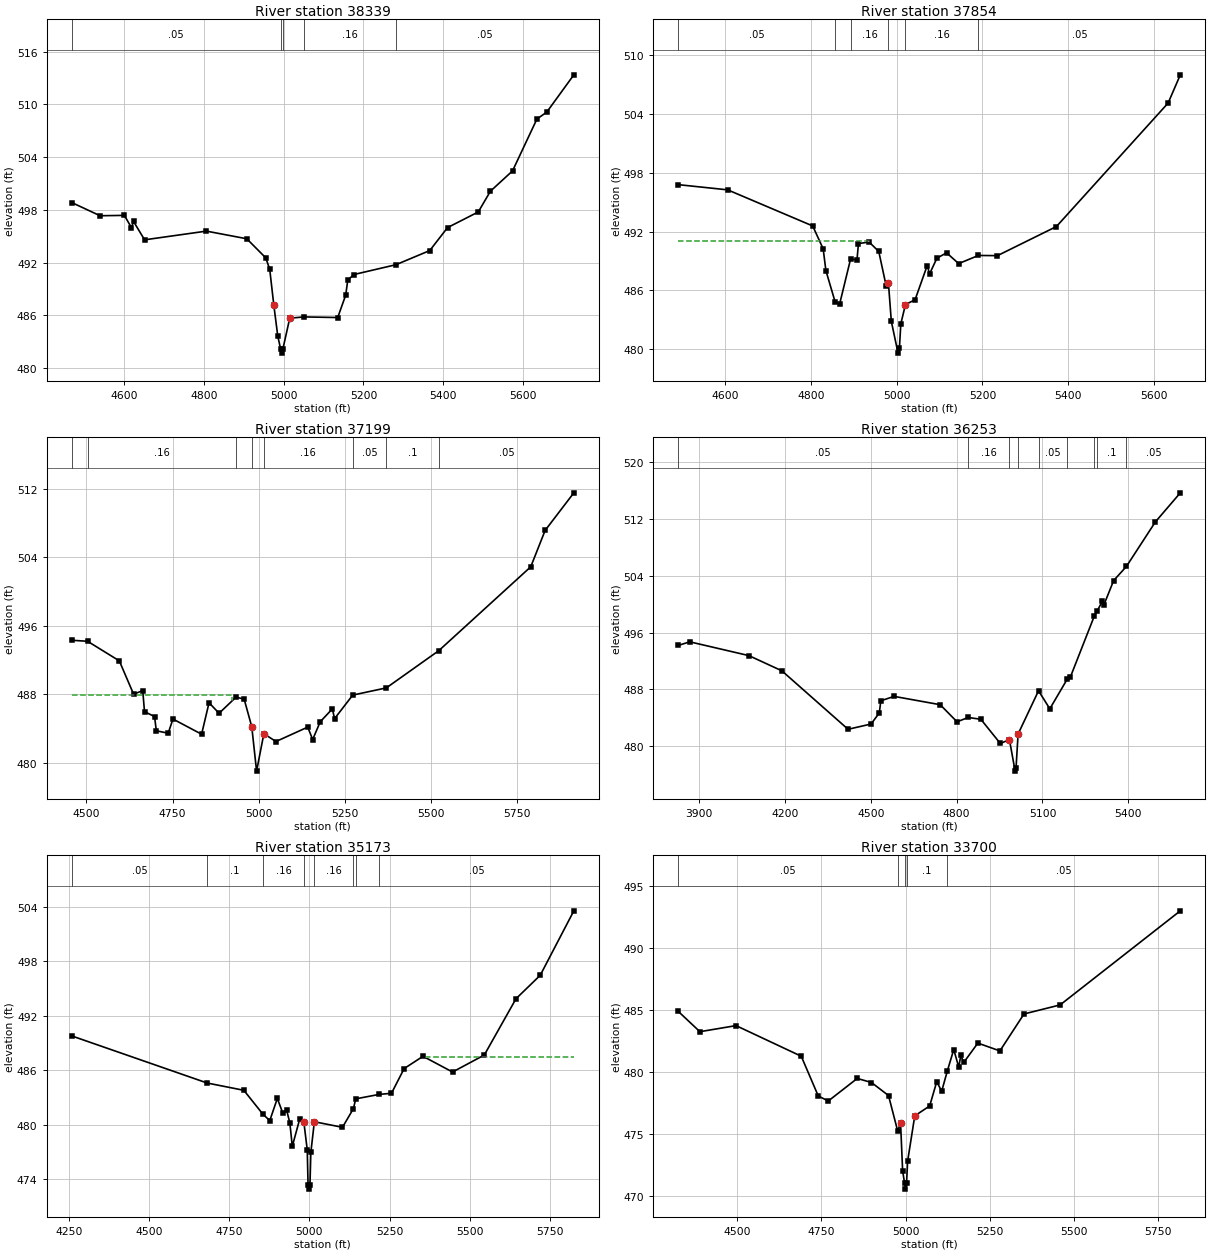
Type RM Length L Ch R = 1 ,38339   ,485,485,485
BEGIN DESCRIPTION:
CEDAR CREEK 1 31.0
END DESCRIPTION:
XS GIS Cut Line= 4
       3453642.1      10530891.6      3453570.54     10530461.49
      3453556.65      10530197.6      3453362.83     10529674.96
#Sta/Elev= 30
  4469.5  498.83  4540.4  497.33  4601.2  497.37  4619.1  495.97  4624.2  496.68
  4651.9  494.59  4806.8  495.58  4907.9  494.71  4955.4  492.54  4965.4  491.23
  4975.7  487.13  4985.5  483.65  4992.5   482.2  4995.2   481.7  4998.5   482.2
  5015.5  485.67  5050.9  485.82  5135.7  485.75  5155.7   488.3  5160.9  490.01
  5176.1  490.64  5281.7  491.76  5366.3  493.37  5410.8  495.98  5487.8  497.76
  5518.2  500.12  5573.6  502.43  5634.7  508.33  5659.4  509.12  5727.2  513.36
#Mann= 5 ,-1 , 0
  4469.5     .05       0  4992.5    .035       0  4998.5     .05       0
  5050.9     .16       0  5281.7     .05       0
Bank Sta=4975.7,5015.5
XS Rating Curve= 0 ,0
Exp/Cntr=0.3,0.1

Type RM Length L Ch R = 1 ,37854   ,655,655,655
BEGIN DESCRIPTION:
CEDAR CREEK 1 30.0
END DESCRIPTION:
XS GIS Cut Line= 4
      3454129.56     10530742.72      3453976.79     10530350.38
      3453792.76     10529968.43      3453667.81     10529666.47
#Sta/Elev= 30
    4490  496.79  4605.4  496.26  4803.8  492.58  4828.3  490.24  4834.6  488.03
  4856.3  484.81  4866.8  484.64  4892.2   489.2  4907.2  489.13  4910.6  490.78
  4935.4  490.94    4958  489.98  4975.1   486.5  4980.6  486.74  4987.3  482.86
    5003  479.61  5006.2  480.11  5009.5   482.6  5020.3  484.56  5042.8  485.06
  5071.1  488.54  5076.6  487.69  5093.7  489.29  5116.3  489.84  5144.5  488.74
  5190.6  489.57    5235  489.55  5372.7  492.52  5633.3  505.11  5661.8  507.99
#Mann= 6 ,-1 , 0
    4490     .05       0  4856.3     .12       0  4892.2     .16       0
  4980.6     .07       0  5020.3     .16       0  5190.6     .05       0
#XS Ineff= 2 , 0
         4934.92  491.01
Permanent Ineff=
       F       F
Bank Sta=4980.6,5020.3
XS Rating Curve= 0 ,0
Exp/Cntr=0.3,0.1

Type RM Length L Ch R = 1 ,37199   ,946,946,946
BEGIN DESCRIPTION:
CEDAR CREEK 1 29.0
END DESCRIPTION:
XS GIS Cut Line= 4
      3454742.11     10530704.56      3454619.15      10530260.1
      3454344.85     10529940.65      3453980.23      10529497.1
#Sta/Elev= 30
  4457.4  494.32  4503.3   494.2  4595.3  491.92  4636.8  488.03  4663.2  488.46
  4668.4     486  4697.5  485.43  4702.7  483.77  4737.1  483.49  4750.9  485.14
    4834  483.37  4855.6  487.04  4884.7  485.81  4934.1   487.7  4957.5  487.45
  4979.5  484.25  4993.5  479.07  5014.6  483.43  5049.7  482.52  5141.9   484.2
  5156.2  482.75  5178.1  484.82  5213.2  486.32  5219.8  485.19  5272.4  487.93
  5369.9  488.77  5522.1  493.11  5788.8  502.88  5830.5  507.12  5913.8   511.5
#Mann= 8 ,-1 , 0
  4457.4     .05       0  4503.3     .16       0  4934.1     .05       0
  4979.5    .035       0  5014.6     .16       0  5272.4     .05       0
  5369.9      .1       0  5522.1     .05       0
#XS Ineff= 2 , 0
         4923.19  487.94
Permanent Ineff=
       F       F
Bank Sta=4979.5,5014.6
XS Rating Curve= 0 ,0
Exp/Cntr=0.3,0.1

Type RM Length L Ch R = 1 ,36253   ,1080,1080,1080
BEGIN DESCRIPTION:
CEDAR CREEK 1 27.0
END DESCRIPTION:
XS GIS Cut Line= 4
      3455324.01     10530881.58      3455219.85     10529930.24
      3455171.24     10529565.65      3455053.17     10529152.43
#Sta/Elev= 30
  3827.2  494.19  3867.4   494.7    4074  492.76  4189.3  490.62  4420.7  482.39
  4501.1  483.13    4530   484.7  4535.1   486.4  4581.6  487.02  4742.6  485.85
  4801.5  483.44  4840.3  484.05  4884.7   483.8  4952.8  480.39  4984.6  480.94
  5004.5   476.5  5007.8     477  5014.9  481.72  5086.3  487.81  5125.8  485.27
  5187.1  489.48  5197.8  489.76  5281.3  498.33  5290.3  498.98  5309.8  500.43
    5315  499.92  5348.8  503.32  5393.5  505.31  5494.5  511.57  5581.8  515.67
#Mann= 9 ,-1 , 0
  3827.2     .05       0  4840.3     .16       0  4984.6     .07       0
  5014.9     .16       0  5086.3     .05       0  5187.1      .1       0
  5281.3     .05       0  5290.3      .1       0  5393.5     .05       0
Bank Sta=4984.6,5014.9
XS Rating Curve= 0 ,0
Exp/Cntr=0.3,0.1

Type RM Length L Ch R = 1 ,35173   ,1473,1473,1473
BEGIN DESCRIPTION:
CEDAR CREEK 1 25.0
END DESCRIPTION:
XS GIS Cut Line= 2
      3456274.78     10530463.68      3455644.58      10529031.4
#Sta/Elev= 30
  4259.3  489.79  4681.4  484.61  4795.6  483.81  4855.5  481.16  4876.5  480.48
  4899.9  482.91    4917  481.31  4928.7  481.65  4938.9  480.24  4946.6  477.65
  4969.9  480.67  4982.6  480.33  4993.2  477.26  4995.7  473.44  4998.5  472.94
  5001.7  473.44  5004.4  476.97  5015.4  480.35    5103  479.74    5137  481.79
  5144.4  482.87  5217.6  483.36  5255.7  483.48  5295.2   486.2    5354  487.55
  5446.1  485.82    5545  487.69  5643.8  493.88  5719.3  496.46  5824.1  503.55
#Mann= 8 ,-1 , 0
  4259.3     .05       0  4681.4      .1       0  4855.5     .16       0
  4982.6     .07       0  5015.4     .16       0    5137      .1       0
  5144.4     .16       0  5217.6     .05       0
#XS Ineff= 2 , 0
                         5363.99           487.5
Permanent Ineff=
       F       F
Bank Sta=4982.6,5015.4
XS Rating Curve= 0 ,0
Exp/Cntr=0.3,0.1

Type RM Length L Ch R = 1 ,33700   ,1347,1347,1347
BEGIN DESCRIPTION:
CEDAR CREEK 1 23.0
END DESCRIPTION:
XS GIS Cut Line= 2
      3457285.22     10530057.47      3456432.16      10528835.1
#Sta/Elev= 30
    4325  484.88  4389.3  483.24  4496.6  483.73  4690.2  481.26  4740.8  478.05
  4770.5  477.65  4856.5  479.47  4898.7  479.14  4949.3  478.09  4976.5  475.23
  4985.1  475.86  4991.2  472.01  4996.9  471.04  4999.7  470.54  5002.9  471.04
    5006  472.79  5027.2  476.45  5071.5  477.25  5092.4   479.2  5107.2  478.44
  5124.1  480.09    5143   481.8  5157.8  480.38  5163.9  481.33  5172.7  480.76
  5214.5  482.32    5280  481.69  5351.5  484.67  5458.8   485.4  5815.6  492.99
#Mann= 5 ,-1 , 0
    4325     .05       0  4976.5      .1       0  4996.9     .07       0
  5002.9      .1       0  5124.1     .05       0
Bank Sta=4985.1,5027.2
XS Rating Curve= 0 ,0
Exp/Cntr=0.3,0.1

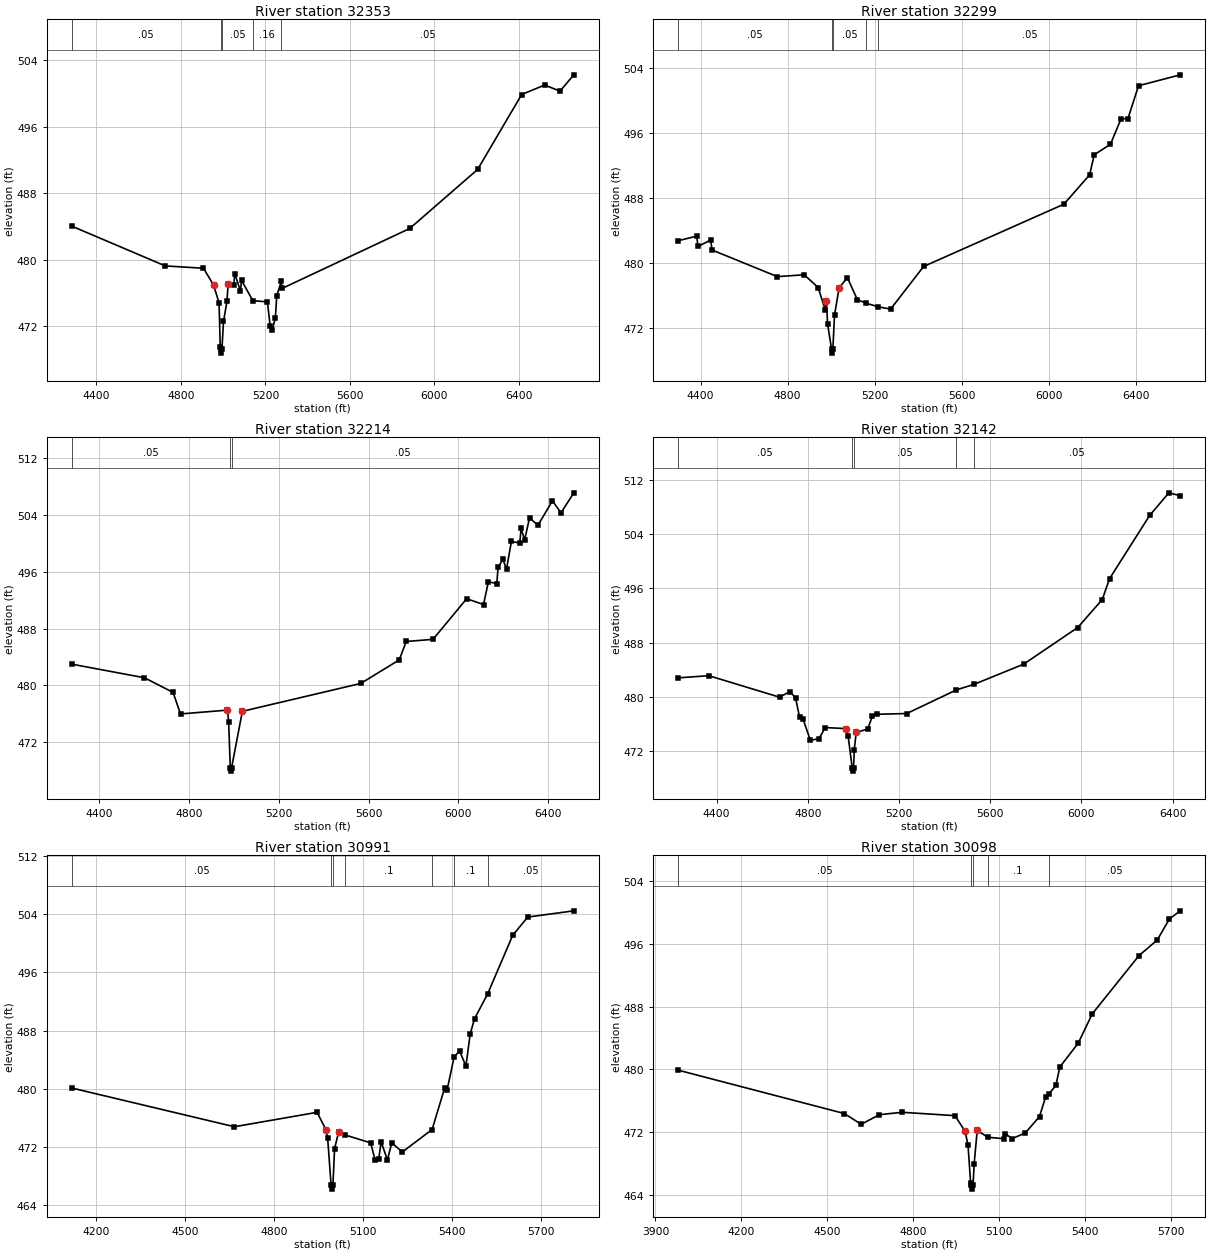
Type RM Length L Ch R = 1 ,32353   ,54,54,54
BEGIN DESCRIPTION:
CEDAR CREEK 1 22.0
END DESCRIPTION:
XS GIS Cut Line= 4
      3458524.77     10529255.38      3457665.43     10528974.14
      3456764.39     10528687.68      3456321.66     10528401.22
#Sta/Elev= 30
    4283  484.05  4725.8  479.26  4906.6  478.98    4954  476.97  4980.3  474.82
  4985.9  469.52  4988.1  469.26  4990.9  468.76  4994.1  469.26  5001.3  472.57
  5017.7  474.98    5023  477.03  5049.6  476.97  5054.9  478.32  5081.5  476.25
  5086.7  477.53  5140.1  475.08  5209.2  474.93  5222.2  472.06  5232.7  471.59
  5246.7  472.97  5253.6  475.68  5275.3   477.4  5278.9  476.55  5883.2  483.77
  6204.6  490.88    6413   499.9  6521.8  501.04  6594.4  500.31    6660  502.27
#Mann= 5 ,-1 , 0
    4283     .05       0  4988.1    .035       0  4994.1     .05       0
  5140.1     .16       0  5275.3     .05       0
Bank Sta=4954,5023
XS Rating Curve= 0 ,0
Exp/Cntr=0.3,0.1

Type RM Length L Ch R = 1 ,32299   ,85,85,85
BEGIN DESCRIPTION:
CEDAR CREEK 1 20.0
END DESCRIPTION:
XS GIS Cut Line= 4
      3458545.62      10529203.3      3457566.47     10528890.81
      3456858.14     10528666.85      3456396.37     10528397.06
#Sta/Elev= 30
  4297.7  482.78  4382.7  483.34    4388  482.07  4447.1  482.86  4452.4  481.64
  4752.8  478.36  4876.1  478.59  4940.5  477.01  4972.7  474.26  4977.9  475.36
  4983.7  472.52  5001.7  469.46  5004.4  468.96  5007.7  469.46  5015.4  473.62
  5036.2  476.97  5074.5  478.24  5120.1  475.53  5161.1  475.09  5216.5  474.65
  5272.9  474.37  5424.5  479.61  6068.4  487.26  6186.6  490.86  6208.1  493.34
  6282.5  494.63  6331.2  497.76  6362.6  497.77  6411.4  501.82  6603.2  503.16
#Mann= 5 ,-1 , 0
  4297.7     .05       0  5001.7    .035       0  5007.7     .05       0
  5161.1     .16       0  5216.5     .05       0
Bank Sta=4977.9,5036.2
XS Rating Curve= 0 ,0
Exp/Cntr=0.3,0.1

Type RM Length L Ch R = 1 ,32214   ,72,72,72
BEGIN DESCRIPTION:
CEDAR CREEK 1 19.0
END DESCRIPTION:
XS GIS Cut Line= 4
       3458592.5     10529114.76      3457717.51     10528854.35
      3456993.55     10528604.35      3456505.51     10528329.18
#Sta/Elev= 30
  4276.4  482.99  4600.3  481.08  4728.1  479.02  4761.3  475.99  4970.8  476.53
    4976  474.92  4983.3  468.45    4986  467.95  4989.3  468.45  5037.2  476.36
  5565.3  480.28  5736.8  483.59    5768  486.18  5887.5  486.48  6037.5  492.19
  6112.7  491.37  6134.3  494.57  6171.9  494.33  6177.6  496.63  6199.3  497.72
  6215.2  496.34  6236.9  500.24  6274.5  500.03  6280.2  502.07  6296.1  500.47
  6317.8  503.55  6355.4  502.53  6420.3  505.96  6457.9  504.26  6515.5  507.08
#Mann= 3 ,-1 , 0
  4276.4     .05       0  4983.3    .035       0  4989.3     .05       0
Bank Sta=4970.8,5037.2
XS Rating Curve= 0 ,0
Exp/Cntr=0.3,0.1

Type RM Length L Ch R = 1 ,32142   ,1151,1151,1151
BEGIN DESCRIPTION:
CEDAR CREEK 1 19.01
END DESCRIPTION:
XS GIS Cut Line= 4
      3458660.24     10529088.73      3457972.72     10528875.18
      3457847.72     10528781.43      3456613.33     10528297.05
#Sta/Elev= 30
  4231.8  482.79    4366  483.11    4676  479.94    4722  480.77  4746.4  479.82
  4763.9  476.99  4778.9  476.75  4811.5  473.54  4849.3  473.83  4876.6  475.45
  4968.6  475.29  4976.9  474.21  4994.8  469.51  4997.5  469.01  5000.8  469.51
    5004  472.18  5012.4  474.72  5062.4  475.23  5083.2   477.1  5103.6  477.41
  5234.1  477.52  5451.2     481  5529.7  481.84  5746.6  484.81  5984.1  490.23
  6091.6  494.36  6123.8  497.46  6299.6  506.79  6383.7  510.13    6434   509.7
#Mann= 5 ,-1 , 0
  4231.8     .05       0  4994.8    .035       0  5000.8     .05       0
  5451.2      .1       0  5529.7     .05       0
Bank Sta=4968.6,5012.4
XS Rating Curve= 0 ,0
Exp/Cntr=0.3,0.1

Type RM Length L Ch R = 1 ,30991   ,893,893,893
BEGIN DESCRIPTION:
CEDAR CREEK 1 18.0
END DESCRIPTION:
XS GIS Cut Line= 4
      3458887.01     10528682.62      3458803.16     10528516.72
      3457905.01     10527875.18      3457572.12     10527646.32
#Sta/Elev= 30
  4118.3  480.12  4666.8   474.8  4945.8  476.78  4975.3  474.42  4981.4  473.24
  4993.2  466.73  4995.9  466.23  4999.2  466.73  5004.8   471.8  5018.2  474.04
  5039.4  473.68  5126.4  472.59  5141.1  470.29  5153.5  470.36  5162.1   472.7
    5183  470.24  5197.7  472.59  5233.3  471.33  5333.8  474.42  5375.9   480.1
  5384.5  479.86  5407.6  484.33  5426.3  485.24  5447.9  483.13  5462.2  487.55
  5477.1  489.65  5521.1  493.05  5605.6  501.09  5656.3   503.6  5811.9  504.46
#Mann= 7 ,-1 , 0
  4118.3     .05       0  4993.2    .035       0  4999.2     .05       0
  5039.4      .1       0  5333.8     .05       0  5407.6      .1       0
  5521.1     .05       0
Bank Sta=4975.3,5018.2
XS Rating Curve= 0 ,0
Exp/Cntr=0.3,0.1

Type RM Length L Ch R = 1 ,30098   ,880,880,880
BEGIN DESCRIPTION:
CEDAR CREEK 1 17.0
END DESCRIPTION:
XS GIS Cut Line= 4
      3458983.75     10528669.84      3458535.82     10527968.43
      3458403.88     10527624.68      3458039.28     10527211.47
#Sta/Elev= 30
  3979.7  479.91    4559  474.38    4618  473.01  4681.5  474.23  4760.7  474.54
  4945.1  474.11  4980.5   472.1  4990.6  470.34  4999.8   465.5  5002.2  465.24
  5004.9  464.74  5008.2  465.24    5012  467.96  5022.7  472.23  5059.4  471.36
  5114.5  471.17  5119.9  471.83  5144.6  471.18  5190.6  471.91    5240     474
  5261.7  476.53  5271.9  476.84  5296.9  477.96  5311.1  480.33  5374.7  483.33
  5424.2   487.1  5587.1  494.52    5651  496.52  5693.4  499.21  5731.2  500.23
#Mann= 5 ,-1 , 0
  3979.7     .05       0  5002.2    .035       0  5008.2     .05       0
  5059.4      .1       0  5271.9     .05       0
Bank Sta=4980.5,5022.7
XS Rating Curve= 0 ,0
Exp/Cntr=0.3,0.1

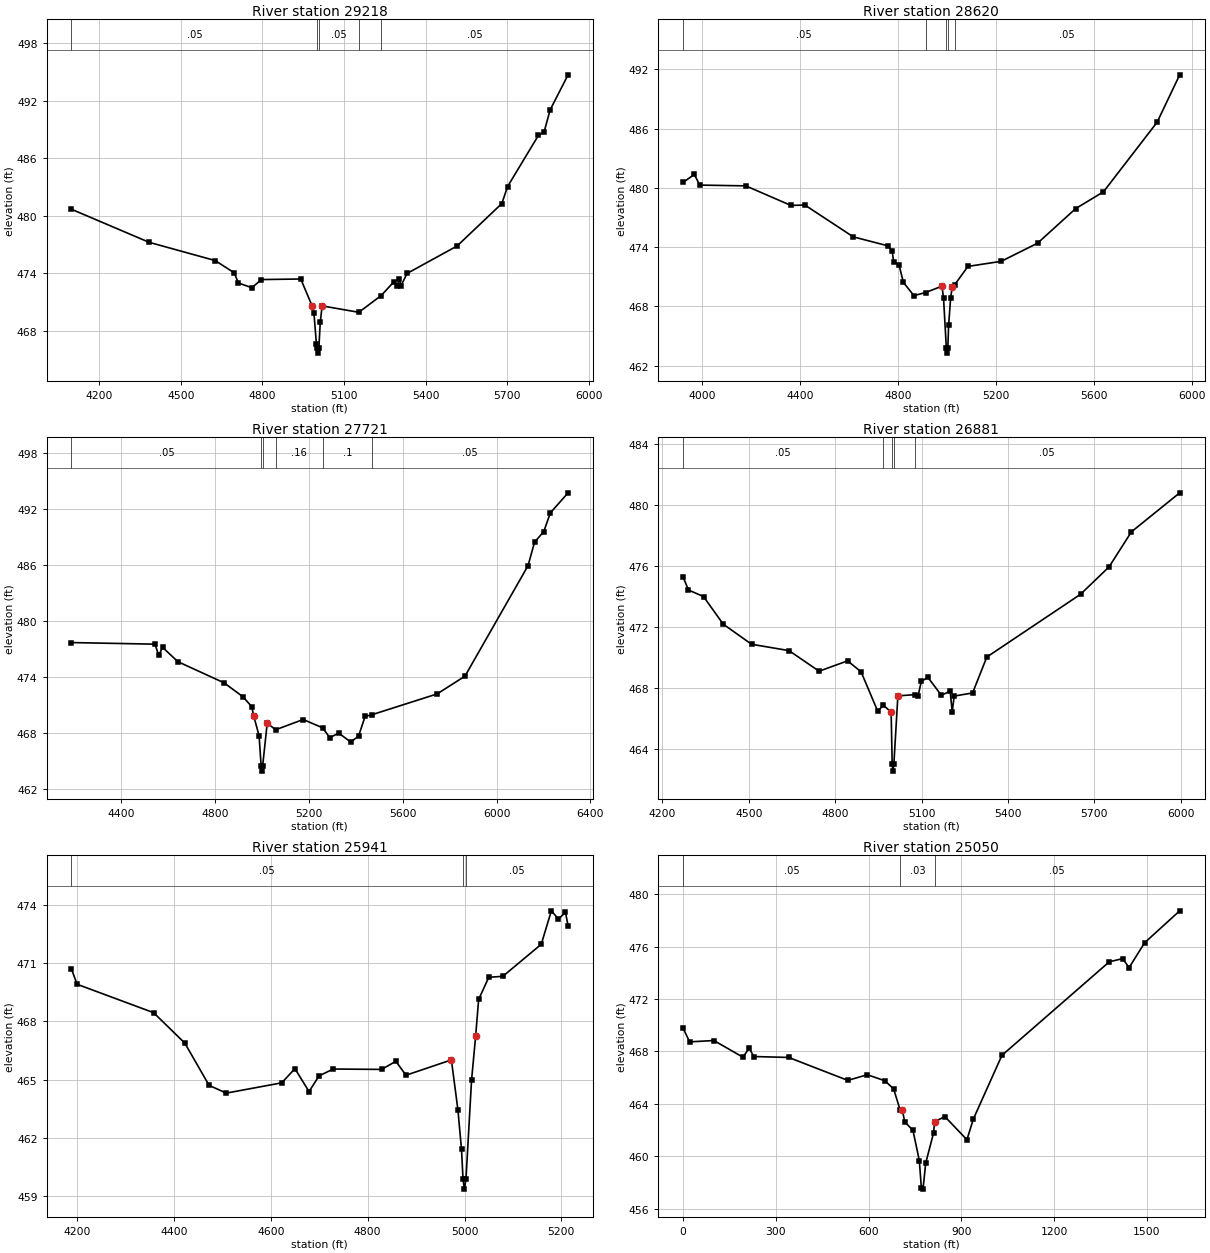
Type RM Length L Ch R = 1 ,29218   ,598,598,598
BEGIN DESCRIPTION:
CEDAR CREEK 1 16.0
END DESCRIPTION:
XS GIS Cut Line= 5
      3459431.63     10528562.16      3458949.08     10527935.27
      3458855.26     10527791.35      3458817.07     10527565.65
      3458417.75     10527072.58
#Sta/Elev= 30
    4098  480.68  4383.4  477.24  4626.2  475.34  4696.8  474.06  4711.4  473.01
  4761.2  472.51  4796.5  473.36  4941.2  473.42  4983.6  470.57  4989.6  469.87
  4998.7  466.65  5001.7   466.2  5004.5   465.7  5007.7   466.2  5012.8   468.9
  5019.8  470.62  5154.7  469.95    5237   471.7  5283.7  473.13  5295.6  472.73
  5303.5  473.38    5310  472.74  5332.3     474  5516.2  476.86  5680.8  481.28
  5701.6  483.04  5815.1  488.37  5835.9  488.71  5858.2  491.03  5924.3  494.68
#Mann= 5 ,-1 , 0
    4098     .05       0  5001.7    .035       0  5007.7     .05       0
  5154.7      .1       0    5237     .05       0
Bank Sta=4983.6,5019.8
XS Rating Curve= 0 ,0
Exp/Cntr=0.3,0.1

Type RM Length L Ch R = 1 ,28620   ,899,899,899
BEGIN DESCRIPTION:
CEDAR CREEK 1 15.0
END DESCRIPTION:
XS GIS Cut Line= 4
      3459771.91     10528593.39      3459396.93     10527773.99
      3459129.57      10527572.6      3458542.11     10527041.64
#Sta/Elev= 30
  3923.6  480.55  3969.5  481.36  3991.5  480.28  4179.7   480.2  4363.8  478.22
  4420.8  478.26  4618.4  475.04  4761.3  474.12    4777  473.62  4783.3  472.54
  4805.5  472.18  4823.1  470.43  4866.1  469.09  4913.4   469.4  4980.6  470.05
  4986.9  468.88  4998.5  463.77  5001.2  463.27  5004.5  463.77  5007.7  466.07
    5016  468.84  5022.3  469.93  5032.2  470.18  5086.8  472.05  5222.3  472.56
    5371   474.4  5526.5   477.9  5640.1   479.6    5859  486.64  5951.3  491.44
#Mann= 5 ,-1 , 0
  3923.6     .05       0  4913.4      .1       0  4998.5     .07       0
  5004.5      .1       0  5032.2     .05       0
Bank Sta=4980.6,5022.3
XS Rating Curve= 0 ,0
Exp/Cntr=0.3,0.1

Type RM Length L Ch R = 1 ,27721   ,840,840,840
BEGIN DESCRIPTION:
CEDAR CREEK 1 14.0
END DESCRIPTION:
XS GIS Cut Line= 5
       3460275.4     10528322.59      3459955.96     10527735.79
      3459810.13     10527482.32      3459719.85     10527402.46
      3458792.07     10526941.62
#Sta/Elev= 30
  4188.2  477.68  4544.1  477.51  4560.2   476.3  4576.4  477.17  4641.9  475.63
  4838.5  473.37  4919.4  471.87  4956.7  470.81  4964.9  469.83    4988  467.68
  4996.8  464.41  4999.6  463.91  5002.8  464.41  5022.6  469.05  5058.4  468.34
  5175.9  469.44  5258.8  468.55  5289.1   467.5  5327.7  467.98  5378.4  467.03
  5411.8  467.65  5439.8  469.77  5468.8  469.95  5746.9  472.18  5865.5  474.08
  6134.3  485.91  6162.3  488.44  6201.5  489.57  6229.5  491.57  6305.2  493.72
#Mann= 6 ,-1 , 0
  4188.2     .05       0  4996.8    .035       0  5002.8     .05       0
  5058.4     .16       0  5258.8      .1       0  5468.8     .05       0
Bank Sta=4964.9,5022.6
XS Rating Curve= 0 ,0
Exp/Cntr=0.3,0.1

Type RM Length L Ch R = 1 ,26881   ,940,940,940
BEGIN DESCRIPTION:
CEDAR CREEK 1 12.0
END DESCRIPTION:
XS GIS Cut Line= 3
      3460236.61      10527809.2      3459866.82     10526965.46
      3459309.54     10526387.35
#Sta/Elev= 30
  4272.2  475.27  4290.9  474.42  4343.1  473.99  4411.5  472.18  4509.7  470.86
    4640  470.44  4744.4  469.09  4843.3  469.77  4890.1  469.05  4947.8  466.47
  4967.6  466.85  4994.5  466.41  4998.1  463.03  5000.8  462.53  5004.1  463.03
  5017.9  467.47  5076.6  467.55    5088  467.46  5099.3  468.43  5122.3  468.68
    5169  467.51  5199.5  467.78  5206.5  466.42  5213.5  467.46  5277.3  467.66
  5326.7  470.02  5652.1  474.14  5751.2  475.94  5828.8  478.24  5996.4   480.8
#Mann= 5 ,-1 , 0
  4272.2     .05       0  4967.6      .1       0  4998.1     .07       0
  5004.1      .1       0  5076.6     .05       0
Bank Sta=4994.5,5017.9
XS Rating Curve= 0 ,0
Exp/Cntr=0.3,0.1

Type RM Length L Ch R = 1 ,25941   ,891,891,891
BEGIN DESCRIPTION:
CEDAR CREEK 1 16.2
END DESCRIPTION:
XS GIS Cut Line= 2
      3460731.38      10527059.2      3459909.81     10526445.62
#Sta/Elev= 30
  4188.5  470.68  4200.1   469.9    4358  468.44  4422.6  466.87  4472.6   464.7
  4508.1   464.3  4622.7  464.83  4649.8  465.56    4679  464.38  4699.8  465.19
    4729  465.54  4829.1  465.52  4858.3  465.94  4879.1  465.22  4972.9  466.01
  4986.4  463.44  4993.8  461.41    4997  459.86  4999.8  459.36    5003  459.86
  5014.6  464.98    5023  467.23  5029.2  469.12  5050.1  470.26  5079.2  470.31
  5158.5  471.96  5179.3  473.68  5193.9  473.26  5208.5   473.6  5213.9  472.91
#Mann= 3 ,-1 , 0
  4188.5     .05       0    4997    .035       0    5003     .05       0
Bank Sta=4972.9,5023
XS Rating Curve= 0 ,0
Exp/Cntr=0.3,0.1

Type RM Length L Ch R = 1 ,25050   ,44,44,44
BEGIN DESCRIPTION:
CEDAR CREEK 1 15.21
END DESCRIPTION:
XS GIS Cut Line= 5
      3461177.35     10526756.43       3461042.4     10526579.65
      3460686.61     10526205.74      3460611.96     10526184.91
      3460006.05     10525676.23
#Sta/Elev= 30
       0  469.78    20.9  468.73    99.8  468.83   193.3  467.56   214.1  468.25
   228.3  467.61   341.6  467.54   532.5  465.79     596  466.22   652.6  465.76
   680.9  465.14   702.3  463.51   709.2  463.54   716.5  462.64   743.5  461.97
     764  459.67   770.8  457.55     776  457.49   784.7  459.48   810.1  461.78
   813.4  462.63   846.5  463.03     918  461.26   938.8  462.84  1031.2   467.7
  1378.5  474.84  1421.4  475.08  1442.6   474.4    1493   476.3  1606.2  478.73
#Mann= 3 ,-1 , 0
       0     .05       0   702.3     .03       0   813.4     .05       0
Bank Sta=709.2,813.4
XS Rating Curve= 0 ,0
Exp/Cntr=0.3,0.1