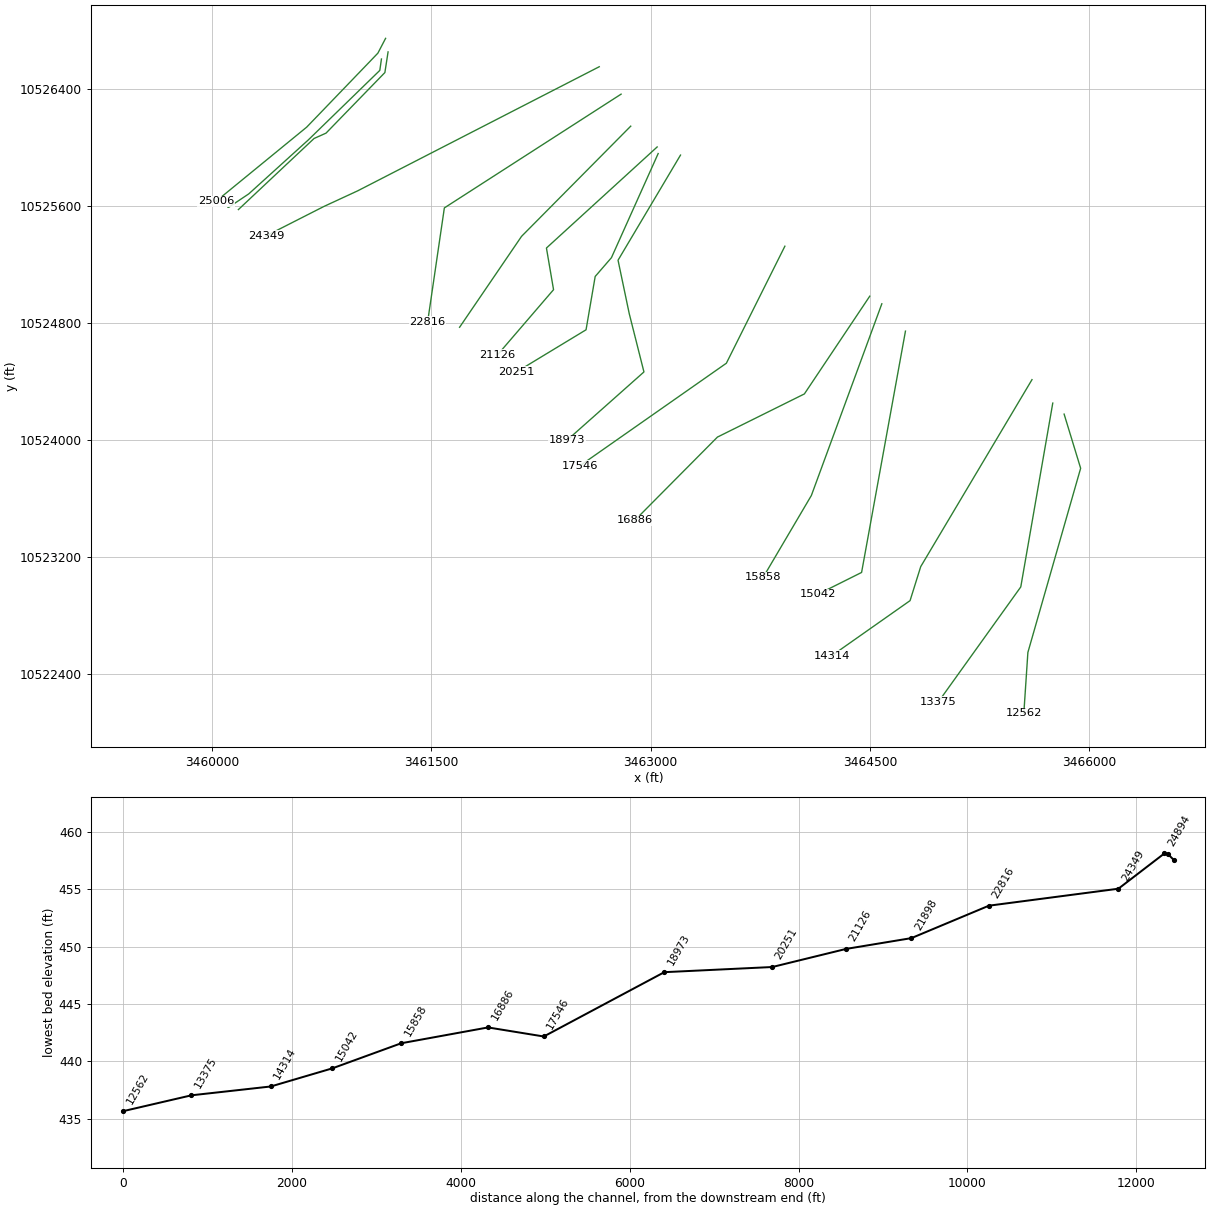
HEC-RAS study CEDAR CREEK 1.prj: CEDAR CREEK 1 Base Level Engineering

--- CEDAR CREEK 1.g01 (geometry) --- (continued)

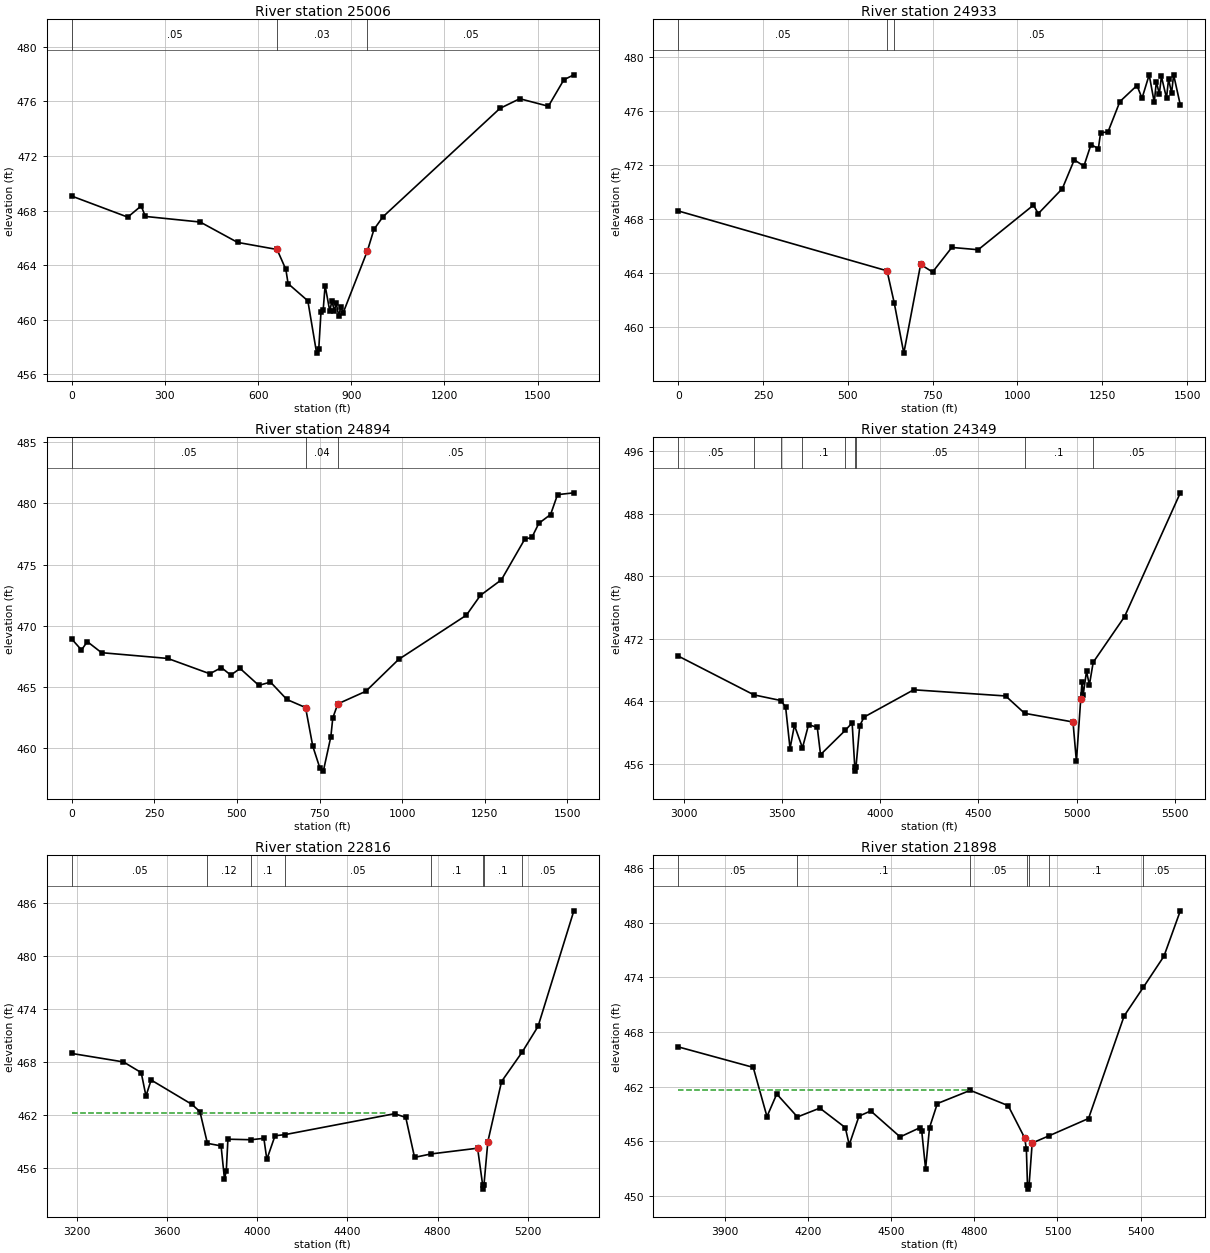
Type RM Length L Ch R = 1 ,25006   ,73,73,73
BEGIN DESCRIPTION:
CEDAR CREEK 1 15.2
END DESCRIPTION:
XS GIS Cut Line= 5
      3461187.77     10526743.41      3461135.18     10526642.38
      3461059.34     10526563.24      3460648.42      10526136.3
      3460028.62     10525629.35
#Sta/Elev= 30
       0  469.06   180.3  467.52   223.5  468.34   236.9  467.57   413.6  467.16
   533.8  465.67   661.1  465.15   689.4  463.69   696.6  462.65   760.2  461.39
   788.5  457.56   795.4  457.87   802.6   460.6   809.6  460.72   815.8  462.51
     831  460.62   837.5  461.39   845.4  460.67   851.8   461.2   859.7  460.26
   866.2  460.96   874.1  460.52   952.3  465.07   973.1  466.62  1001.9  467.54
  1378.7  475.48  1442.6  476.19  1534.8  475.64  1584.7  477.58  1616.8  477.94
#Mann= 3 , 0 , 0
       0     .05       0   661.1     .03       0   952.3     .05       0
Bank Sta=661.1,952.3
XS Rating Curve= 0 ,0
Exp/Cntr=0.3,0.1

Type RM Length L Ch R = 1 ,24933   ,39,39,39
BEGIN DESCRIPTION:
CEDAR CREEK 1 15.22
END DESCRIPTION:
XS GIS Cut Line= 6
      3461159.32      10526602.3      3461148.25      10526524.3
      3460658.83     10526048.33      3460252.58     10525680.28
      3460115.43     10525588.26      3460110.22     10525588.26
#Sta/Elev= 30
       0  468.62   615.5  464.19   636.6  461.83   664.9   458.1   714.5  464.66
   749.8   464.1   806.5  465.92   884.2  465.75  1047.1  469.05  1061.3  468.42
  1132.2  470.27  1167.4   472.4  1195.8  471.94  1216.7  473.53  1238.4  473.23
  1245.1  474.41  1266.7  474.46  1301.9  476.71  1352.2   477.9  1367.2  476.96
  1388.2  478.69  1403.2  476.65  1409.3  478.17  1418.2  477.28  1424.3  478.57
  1439.3  476.97  1445.3  478.37  1454.3  477.35  1460.3  478.69    1480  476.46
#Mann= 3 ,-1 , 0
       0     .05       0   615.5     .04       0   636.6     .05       0
Bank Sta=615.5,714.5
XS Rating Curve= 0 ,0
Exp/Cntr=0.3,0.1

Type RM Length L Ch R = 1 ,24894   ,545,545,545
BEGIN DESCRIPTION:
CEDAR CREEK 1 15.23
END DESCRIPTION:
XS GIS Cut Line= 5
      3461204.69     10526650.67      3461182.85     10526509.39
      3460780.36     10526095.21      3460698.76     10526058.75
       3460181.4     10525572.64
#Sta/Elev= 30
       0  468.92    29.4  468.03    47.1  468.71    90.1  467.81   290.5  467.34
   417.8  466.09     453  466.59   481.3  465.98   509.6  466.52   566.2  465.14
   601.5  465.41   651.1  463.99   707.7  463.33   729.5  460.18   751.4  458.36
   761.5  458.14   784.3  460.96   790.1  462.48   805.3  463.63   890.2  464.66
   989.4  467.26  1194.5  470.87    1237  472.49  1300.5  473.76  1371.3  477.08
  1392.8  477.22  1413.8  478.37  1449.4  479.09  1470.4  480.71  1519.8  480.86
#Mann= 3 , 0 , 0
       0     .05       0   707.7     .04       0   805.3     .05       0
Bank Sta=707.7,805.3
XS Rating Curve= 0 ,0
Exp/Cntr=0.3,0.1

Type RM Length L Ch R = 1 ,24349   ,1533,1533,1533
BEGIN DESCRIPTION:
CEDAR CREEK 1 17.1
END DESCRIPTION:
XS GIS Cut Line= 4
      3462648.56     10526549.32      3460997.63     10525701.07
      3460764.99     10525593.43      3460369.12     10525392.02
#Sta/Elev= 30
  2971.3  469.79  3356.7  464.82    3495  464.09  3518.2  463.24  3540.6  457.95
  3562.8  460.93    3604  458.04  3634.9  461.01  3679.3  460.65  3695.9  457.17
  3821.8  460.28  3856.8  461.24  3870.3  455.56  3873.1  455.06  3876.3  455.56
  3895.5  460.88  3917.7  461.98  4170.3  465.47  4638.5  464.68  4735.1  462.46
  4981.5  461.35  4998.8   456.3  5020.8  464.26  5027.4   466.5  5032.9  464.77
  5050.3  467.83  5064.9  466.09  5084.3  468.99    5244  474.83  5527.9  490.68
#Mann= 9 ,-1 , 0
  2971.3     .05       0  3356.7      .1       0    3495     .12       0
    3604      .1       0  3821.8     .05       0  3870.3     .07       0
  3876.3     .05       0  4735.1      .1       0  5084.3     .05       0
Bank Sta=4981.5,5020.8
XS Rating Curve= 0 ,0
Exp/Cntr=0.3,0.1

Type RM Length L Ch R = 1 ,22816   ,918,918,918
BEGIN DESCRIPTION:
CEDAR CREEK 1 15.1
END DESCRIPTION:
XS GIS Cut Line= 3
      3462797.87     10526361.83       3461589.5     10525584.03
       3461475.2     10524804.72
#Sta/Elev= 30
  3178.8  468.96  3407.9     468  3486.5  466.79  3507.6  464.14  3530.5  465.95
  3710.3   463.2  3746.6  462.37  3779.8  458.77  3840.4  458.48  3855.5  454.71
  3863.5  455.69  3870.7  459.24  3973.7  459.18    4030  459.34  4043.1  456.95
  4079.4  459.63  4123.7  459.76  4608.9  462.13  4658.7  461.71  4697.7  457.18
  4770.9  457.57    4977  458.22  4999.3  454.08  5002.1  453.58  5005.3  454.08
  5022.5  458.97  5083.2  465.78  5174.9  469.13  5244.9  472.03  5403.5  485.13
#Mann= 8 ,-1 , 0
  3178.8     .05       0  3779.8     .12       0  3973.7      .1       0
  4123.7     .05       0  4770.9      .1       0  4999.3     .07       0
  5005.3      .1       0  5174.9     .05       0
#XS Ineff= 2 , 0
         4565.24  462.17
Permanent Ineff=
       F       F
Bank Sta=4977,5022.5
XS Rating Curve= 0 ,0
Exp/Cntr=0.3,0.1

Type RM Length L Ch R = 1 ,21898   ,772,772,772
BEGIN DESCRIPTION:
CEDAR CREEK 1 11.0
END DESCRIPTION:
XS GIS Cut Line= 3
      3462863.78     10526143.03      3462117.28     10525389.58
      3461693.66     10524768.05
#Sta/Elev= 30
  3730.8  466.36  4001.6  464.11  4051.2  458.71  4086.5  461.19  4161.2  458.67
  4242.1  459.64    4334   457.5  4348.2  455.62  4383.5  458.76  4425.9  459.33
    4532  456.48  4602.7  457.48  4609.8  457.17  4623.9  452.97  4638.1   457.5
  4666.3  460.14  4785.2  461.59  4922.1  459.91  4981.8  456.36  4987.8  455.12
  4991.7  451.25  4994.4  450.75  4997.7  451.25  5008.8  455.81    5071  456.62
  5212.2   458.5  5340.9  469.76  5410.1   472.9  5484.5  476.31  5543.6  481.29
#Mann= 7 ,-1 , 0
  3730.8     .05       0  4161.2      .1       0  4785.2     .05       0
  4991.7    .035       0  4997.7     .05       0    5071      .1       0
  5410.1     .05       0
#XS Ineff= 2 , 0
         4779.67  461.63
Permanent Ineff=
       F       F
Bank Sta=4981.8,5008.8
XS Rating Curve= 0 ,0
Exp/Cntr=0.3,0.1

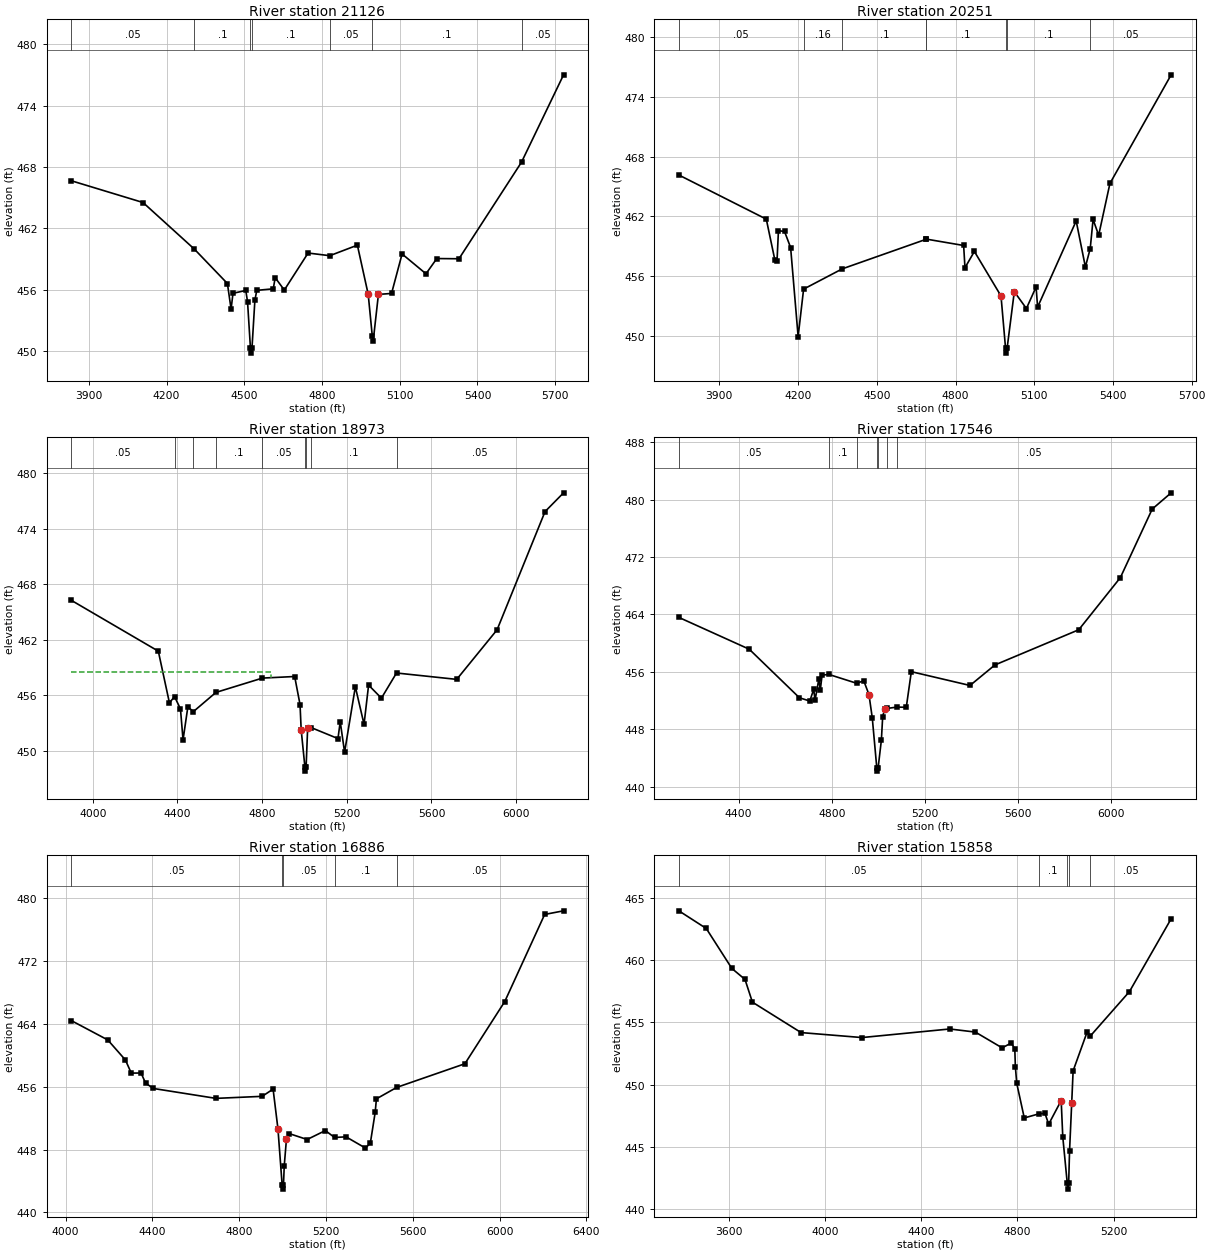
Type RM Length L Ch R = 1 ,21126   ,875,875,875
BEGIN DESCRIPTION:
CEDAR CREEK 1 14.1
END DESCRIPTION:
XS GIS Cut Line= 4
       3463044.4     10526000.72      3462287.42     10525309.72
      3462336.03       10525025.      3461954.08     10524580.55
#Sta/Elev= 30
  3832.4  466.67  4109.3  464.54  4307.5  459.98  4434.9  456.62  4449.1  454.12
  4456.5  455.66  4505.8  455.94  4512.6  454.85  4523.8  450.31  4526.5  449.81
  4529.8  450.31    4541     455  4548.4  455.95  4611.9   456.1  4619.3  457.19
  4654.5  455.98  4746.3   459.6    4830  459.34  4936.5  460.37  4978.3  455.56
    4994  451.49  4997.4  450.96  5017.7  455.55  5068.4  455.65    5109  459.51
  5201.3  457.57    5243  459.06  5328.6  459.04    5570  468.49  5732.2  477.03
#Mann= 7 ,-1 , 0
  3832.4     .05       0  4307.5      .1       0  4523.8     .07       0
  4529.8      .1       0    4830     .05       0    4994      .1       0
    5570     .05       0
#XS Ineff= 2 , 0
       0 4896.83   458.1               0
Permanent Ineff=
       F       F
Bank Sta=4978.3,5017.7
XS Rating Curve= 0 ,0
Exp/Cntr=0.3,0.1

Type RM Length L Ch R = 1 ,20251   ,1278,1278,1278
BEGIN DESCRIPTION:
CEDAR CREEK 1 13.0
END DESCRIPTION:
XS GIS Cut Line= 5
      3463051.31     10525955.56      3462731.86     10525243.75
      3462620.75     10525115.28      3462558.25     10524750.69
       3462082.6     10524462.53
#Sta/Elev= 30
  3745.7  466.15  4078.9  461.71  4111.7  457.58  4119.8  457.52  4125.2  460.55
  4148.4  460.47  4171.6  458.85  4200.2   449.9  4221.1  454.67  4368.5  456.71
  4688.7  459.69  4689.1   459.7    4831  459.06  4836.1  456.82  4871.9  458.46
  4973.4  453.98  4990.7  448.73  4993.4  448.23  4996.7  448.73  5024.1  454.41
  5070.2  452.72  5107.1  454.89  5112.9  452.86  5259.9  461.53    5295   456.9
  5313.4  458.75  5324.3  461.68  5345.6  460.09  5388.5   465.3  5621.8  476.23
#Mann= 8 ,-1 , 0
  3745.7     .05       0  4221.1     .16       0  4368.5      .1       0
  4688.7     .05       0  4689.1      .1       0  4990.7     .07       0
  4996.7      .1       0  5313.4     .05       0
#XS Ineff= 2 , 0
         4686.83  459.66
Permanent Ineff=
       F       F
Bank Sta=4973.4,5024.1
XS Rating Curve= 0 ,0
Exp/Cntr=0.3,0.1

Type RM Length L Ch R = 1 ,18973   ,1427,1427,1427
BEGIN DESCRIPTION:
CEDAR CREEK 1 10.0
END DESCRIPTION:
XS GIS Cut Line= 5
      3463204.07     10525945.11        3462777.     10525226.39
      3462853.39     10524861.81      3462954.09      10524462.5
       3462426.7      10523994.1
#Sta/Elev= 30
  3898.4  466.25  4309.6  460.75  4362.1  455.16  4386.2  455.84  4414.2  454.51
  4426.4  451.16  4449.1  454.72  4475.5  454.22  4581.7  456.29  4801.5  457.84
  4953.8  458.01  4979.1  454.98  4984.5  452.25  5001.9  448.28  5004.7  447.78
  5007.9  448.28  5015.1  452.43  5032.4  452.48  5158.3   451.3    5169  453.13
  5189.6  449.82  5240.4   456.9  5281.5  452.84    5303  457.08  5363.6  455.67
  5434.9  458.39  5719.3   457.7    5910  463.06  6136.6  475.84  6224.1  477.87
#Mann= 9 ,-1 , 0
  3898.4     .05       0  4386.2      .1       0  4475.5     .16       0
  4581.7      .1       0  4801.5     .05       0  5001.9    .035       0
  5007.9     .05       0  5032.4      .1       0  5434.9     .05       0
#XS Ineff= 2 , 0
          4842.1  458.48
Permanent Ineff=
       F       F
Bank Sta=4984.5,5015.1
XS Rating Curve= 0 ,0
Exp/Cntr=0.3,0.1

Type RM Length L Ch R = 1 ,17546   ,660,660,660
BEGIN DESCRIPTION:
CEDAR CREEK 1 9.0
END DESCRIPTION:
XS GIS Cut Line= 3
      3463917.61      10525322.1      3463517.61     10524522.08
      3462517.61     10523822.08
#Sta/Elev= 30
  4143.1  463.58  4445.5  459.15    4661  452.39  4705.7  451.93  4722.5  453.57
  4728.1  452.01  4744.9  455.06  4750.5  453.41  4758.5  455.54  4787.2  455.64
  4907.6   454.4  4937.4  454.76  4959.8  452.84  4974.1  449.59  4993.4  442.67
  4996.2  442.17  4999.4  442.67  5013.2  446.49  5018.8  449.75  5026.9   450.8
  5039.2  450.91  5081.1  451.09  5120.2  451.06  5141.9  456.02    5394   454.1
  5501.2  456.96  5861.3  461.86    6040  469.12  6176.9  478.67  6258.2  480.93
#Mann= 7 ,-1 , 0
  4143.1     .05       0  4787.2      .1       0  4907.6     .05       0
  4993.4    .035       0  4999.4     .05       0  5039.2      .1       0
  5081.1     .05       0
Bank Sta=4959.8,5026.9
XS Rating Curve= 0 ,0
Exp/Cntr=0.3,0.1

Type RM Length L Ch R = 1 ,16886   ,1028,1028,1028
BEGIN DESCRIPTION:
CEDAR CREEK 1 8.2
END DESCRIPTION:
XS GIS Cut Line= 4
      3464498.08     10524980.62      3464051.01     10524312.18
      3463456.39     10524017.04      3462892.18     10523448.49
#Sta/Elev= 30
  4026.1  464.43  4194.5  461.96  4275.6  459.41  4302.6  457.74  4347.7  457.75
  4368.7  456.46  4404.7  455.78    4693  454.52  4905.9  454.78  4956.3   455.7
  4978.7  450.63  4998.1  443.46  5000.9  442.96  5004.1  443.46  5007.7  445.94
    5018  449.37    5030  450.04  5113.2  449.28  5197.2  450.42  5239.6  449.54
  5292.5  449.62  5382.1  448.19  5404.5  448.82  5426.9  452.75  5432.5  454.46
  5526.2  455.92  5840.3  458.93  6024.2  466.86    6208  477.95  6295.1  478.41
#Mann= 5 ,-1 , 0
  4026.1     .05       0  4998.1    .035       0  5004.1     .05       0
  5239.6      .1       0  5526.2     .05       0
Bank Sta=4978.7,5018
XS Rating Curve= 0 ,0
Exp/Cntr=0.3,0.1

Type RM Length L Ch R = 1 ,15858   ,816,816,816
BEGIN DESCRIPTION:
CEDAR CREEK 1 8.0
END DESCRIPTION:
XS GIS Cut Line= 3
      3464580.53     10524928.53      3464098.75     10523617.74
      3463768.88     10523057.81
#Sta/Elev= 30
  3392.7  463.98  3506.6  462.56  3613.1  459.34  3667.6  458.46  3698.4  456.63
  3900.8  454.18  4153.7  453.78  4518.7  454.47  4625.3  454.22  4736.6  452.95
  4774.4  453.34  4789.2  452.88  4791.5  451.45  4797.3  450.09  4828.6  447.31
  4889.5  447.64  4914.4  447.68  4930.1  446.81    4982  448.71  4988.6  445.79
  5007.1  442.08  5009.8  441.58  5013.1  442.08  5016.8  444.66  5025.8  448.53
  5031.6   451.1  5090.1  454.24  5102.1  453.88  5265.8  457.48  5439.1  463.34
#Mann= 5 ,-1 , 0
  3392.7     .05       0  4889.5      .1       0  5007.1     .07       0
  5013.1      .1       0  5102.1     .05       0
Bank Sta=4982,5025.8
XS Rating Curve= 0 ,0
Exp/Cntr=0.3,0.1

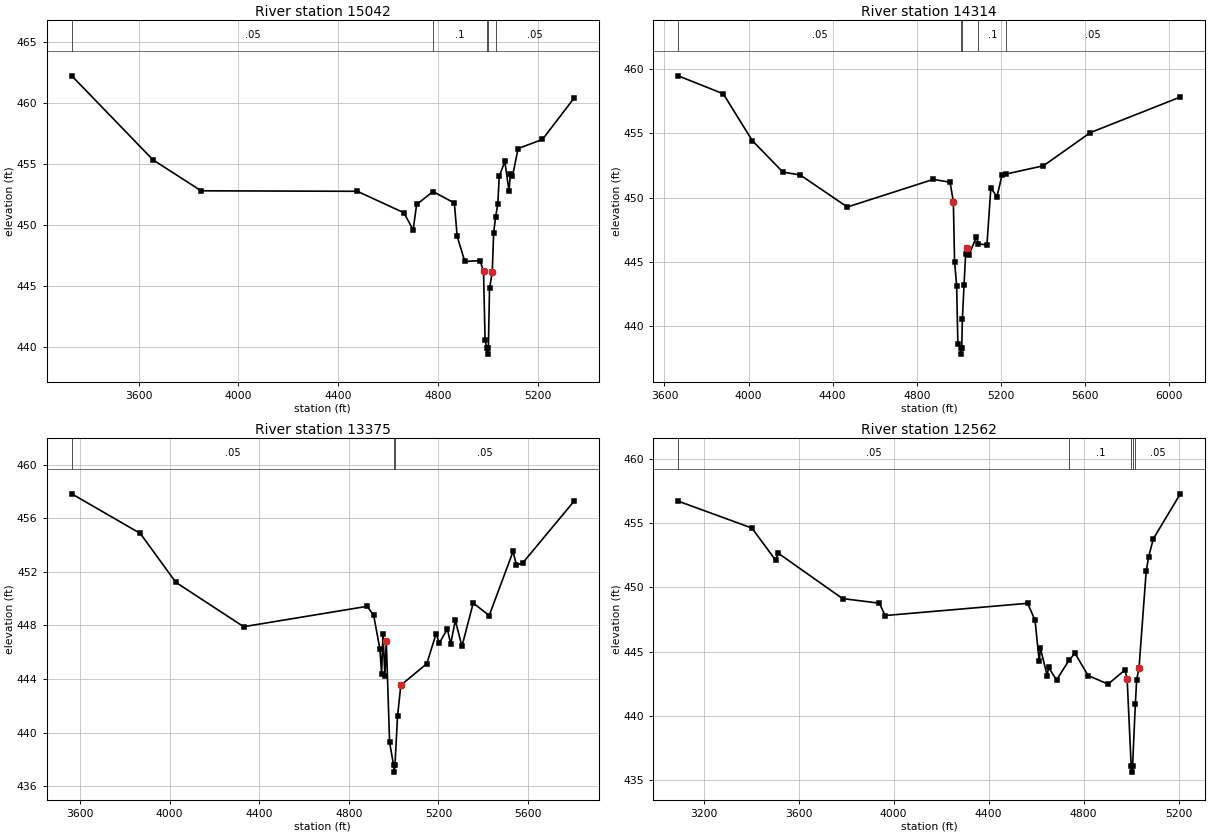
Type RM Length L Ch R = 1 ,15042   ,728,728,728
BEGIN DESCRIPTION:
CEDAR CREEK 1 7.0
END DESCRIPTION:
XS GIS Cut Line= 3
      3464742.11     10524741.67      3464442.11     10523091.64
      3464142.09     10522941.64
#Sta/Elev= 30
  3332.2  462.19  3657.5  455.31  3850.6  452.77  4476.9  452.73  4663.7  450.97
  4700.5  449.56  4714.5  451.65  4780.1  452.71  4865.7  451.77  4877.1  449.04
  4907.6  446.98  4968.6  447.05  4982.6   446.2  4988.9  440.52  4996.1  439.89
  4998.9  439.39  5002.1  439.89  5006.7  444.77  5017.7  446.12  5023.3  449.35
    5031  450.61    5040  451.73  5045.6  453.95    5068  455.18  5084.7  452.76
  5090.3  454.11  5098.7  453.95  5121.1  456.23  5218.9  456.98  5344.7  460.34
#Mann= 5 ,-1 , 0
  3332.2     .05       0  4780.1      .1       0  4996.1     .07       0
  5002.1      .1       0    5031     .05       0
Bank Sta=4982.6,5017.7
XS Rating Curve= 0 ,0
Exp/Cntr=0.3,0.1

Type RM Length L Ch R = 1 ,14314   ,939,939,939
BEGIN DESCRIPTION:
CEDAR CREEK 1 8.1
END DESCRIPTION:
XS GIS Cut Line= 4
      3465607.18      10524409.9      3464846.47     10523131.54
      3464773.56      10522898.9       3464236.2     10522521.01
#Sta/Elev= 30
  3665.6  459.47  3879.8  458.07  4018.1  454.42  4163.9  451.97  4245.4  451.76
  4469.9  449.26  4878.9  451.41  4958.7  451.19  4974.3  449.67  4980.1  444.98
  4989.9  443.15  4995.7  438.63  5008.3  438.31  5011.1  437.81  5014.3  438.31
  5017.1  440.52  5025.1  443.18  5032.7  445.57  5038.6   446.1  5048.3  445.51
  5083.2  446.91  5093.6  446.41    5134  446.29  5152.6  450.73  5181.9  450.07
  5205.5  451.72    5226  451.83  5402.9  452.47  5625.9  455.05  6053.9  457.82
#Mann= 5 ,-1 , 0
  3665.6     .05       0  5008.3    .035       0  5014.3     .05       0
  5093.6      .1       0    5226     .05       0
Bank Sta=4974.3,5038.6
XS Rating Curve= 0 ,0
Exp/Cntr=0.3,0.1

Type RM Length L Ch R = 1 ,13375   ,813,813,813
BEGIN DESCRIPTION:
CEDAR CREEK 1 7.1
END DESCRIPTION:
XS GIS Cut Line= 3
      3465749.25      10524249.6       3465530.5     10522992.65
      3464968.02     10522207.96
#Sta/Elev= 30
  3563.3  457.84  3869.1  454.88  4028.1  451.22  4330.8  447.91  4881.4  449.43
  4910.8  448.78  4938.8  446.24  4946.5  444.38  4952.6  447.39  4961.2  444.25
  4967.3  446.83  4982.1  439.28    5000  437.54  5002.7  437.04    5006  437.54
  5017.7  441.26  5032.4  443.54  5147.9  445.14  5189.6  447.37  5204.4   446.7
    5240  447.73  5254.7  446.62  5275.6  448.38  5305.1  446.44  5355.4  449.68
  5426.7  448.74  5533.5  453.54  5548.3   452.5  5577.7   452.7  5804.6  457.27
#Mann= 3 ,-1 , 0
  3563.3     .05       0    5000    .035       0    5006     .05       0
Bank Sta=4967.3,5032.4
XS Rating Curve= 0 ,0
Exp/Cntr=0.3,0.1

Type RM Length L Ch R = 1 ,12562   ,1115,1115,1115
BEGIN DESCRIPTION:
CEDAR CREEK 1 6.0
END DESCRIPTION:
XS GIS Cut Line= 4
      3465826.81     10524174.17      3465939.84     10523803.94
      3465579.11     10522544.73      3465551.34     10522128.11
#Sta/Elev= 30
    3093  456.71  3403.2  454.62  3503.3  452.12  3513.7  452.67  3784.9  449.14
  3940.2  448.78  3964.1  447.82  4564.3  448.77  4595.5  447.47  4613.4  444.27
  4618.6  445.26  4647.2  443.12  4652.4   443.8  4686.1  442.81  4740.8   444.4
    4764  444.88  4819.1  443.16  4903.3  442.49  4974.5  443.59  4983.5  442.92
  5000.5  436.15  5003.3  435.65  5006.5  436.15  5018.1  440.92  5023.6  442.83
  5033.6  443.73  5063.7  451.26  5073.7  452.34  5093.7  453.78  5207.5  457.28
#Mann= 5 ,-1 , 0
    3093     .05       0  4740.8      .1       0  5000.5     .07       0
  5006.5      .1       0  5018.1     .05       0
Bank Sta=4983.5,5033.6
XS Rating Curve= 0 ,0
Exp/Cntr=0.3,0.1