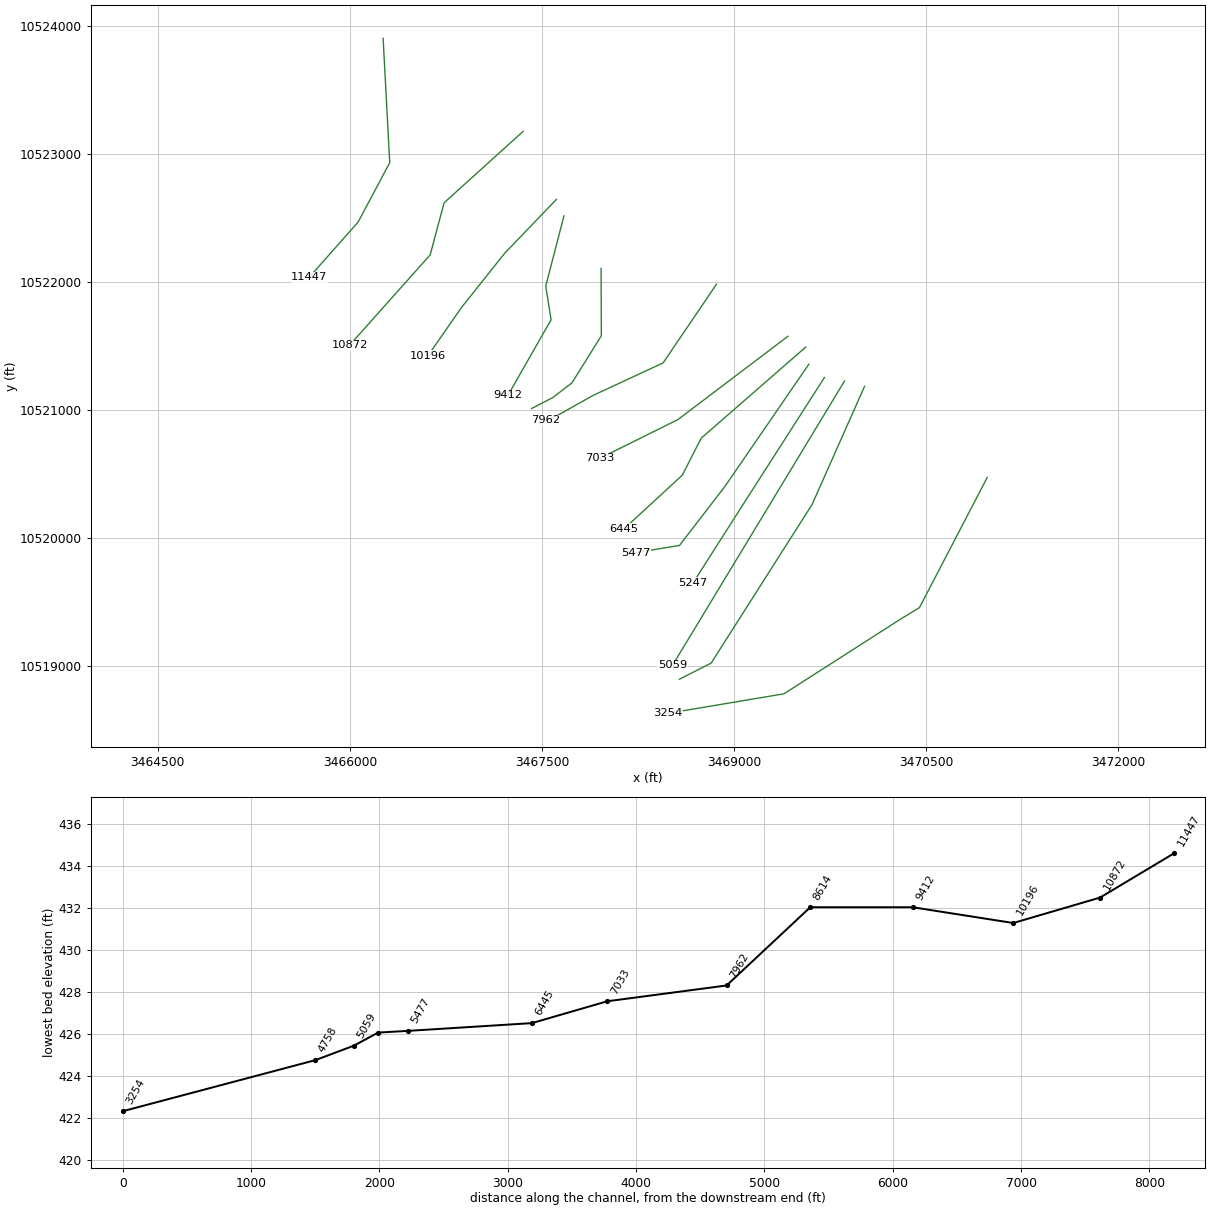
HEC-RAS study CEDAR CREEK 1.prj: CEDAR CREEK 1 Base Level Engineering

--- CEDAR CREEK 1.g01 (geometry) --- (continued)

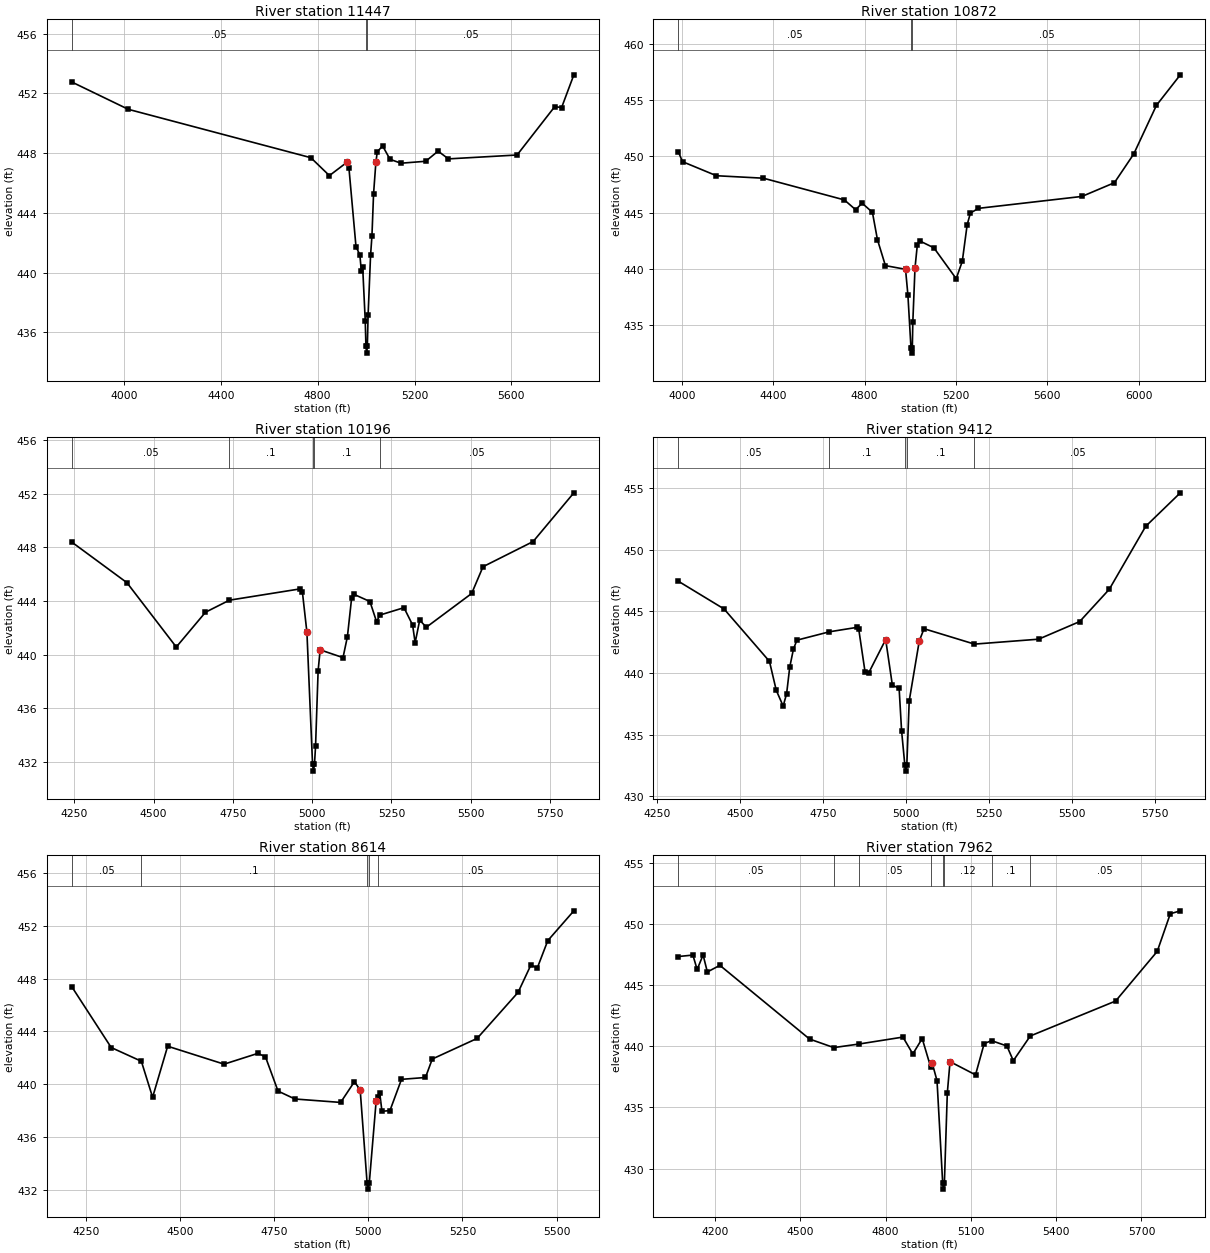
Type RM Length L Ch R = 1 ,11447   ,575,575,575
BEGIN DESCRIPTION:
CEDAR CREEK 1 5.0
END DESCRIPTION:
XS GIS Cut Line= 4
      3466259.99     10523904.75      3466311.77     10522932.85
      3466064.47     10522468.25       3465683.9     10522038.55
#Sta/Elev= 30
  3784.5  452.76  4017.9  450.93  4771.9  447.69  4848.5  446.49    4920  447.37
  4929.1  447.02  4958.3  441.74  4974.4  441.17  4980.3  440.11    4986  440.34
  4996.6  436.75  4999.3   435.1    5002   434.6  5005.3   435.1  5008.4  437.17
  5018.6  441.17  5024.2  442.44    5031  445.29  5040.5  447.38  5046.2  448.08
  5068.2  448.48    5099  447.58  5144.3  447.32  5246.3  447.45  5297.4  448.13
  5340.1  447.61  5623.6  447.87  5779.2  451.11  5807.6  451.05  5858.1  453.24
#Mann= 3 ,-1 , 0
  3784.5     .05       0  4999.3    .035       0  5005.3     .05       0
Bank Sta=4920,5040.5
XS Rating Curve= 0 ,0
Exp/Cntr=0.3,0.1

Type RM Length L Ch R = 1 ,10872   ,676,676,676
BEGIN DESCRIPTION:
CEDAR CREEK 1 4.0
END DESCRIPTION:
XS GIS Cut Line= 4
      3467353.07     10523177.32      3466736.61     10522619.66
       3466627.4     10522212.07      3465998.93      10521507.2
#Sta/Elev= 30
  3984.6  450.42  4003.3  449.52    4152  448.27  4357.5  448.05  4711.7  446.12
    4761  445.25  4789.4  445.83  4834.5  445.02  4856.5  442.59  4891.4  440.28
  4979.5  439.95  4989.8  437.69  5003.2     433    5006   432.5  5009.2     433
  5011.4  435.26  5020.9  440.07  5031.2  442.14  5041.1  442.48  5103.7  441.86
  5201.2  439.12  5227.9  440.66  5249.2  443.91  5263.4  444.95  5298.5  445.37
  5751.7  446.43  5893.8  447.65  5978.3   450.2  6077.8  454.53  6182.2  457.24
#Mann= 3 ,-1 , 0
  3984.6     .05       0  5003.2    .035       0  5009.2     .05       0
Bank Sta=4979.5,5020.9
XS Rating Curve= 0 ,0
Exp/Cntr=0.3,0.1

Type RM Length L Ch R = 1 ,10196   ,784,784,784
BEGIN DESCRIPTION:
CEDAR CREEK 1 3.0
END DESCRIPTION:
XS GIS Cut Line= 4
      3467613.54     10522646.13      3467207.26     10522222.48
      3466870.46     10521798.87      3466611.02     10521425.28
#Sta/Elev= 30
    4242   448.4  4415.8  445.37  4571.5  440.56  4663.6  443.16  4739.1  444.06
    4961   444.9    4969   444.7  4983.4  441.66  5001.2  431.79    5004  431.29
  5007.2  431.79  5010.6  433.13  5018.7  438.78  5025.1  440.35  5097.2  439.77
  5111.1  441.34  5124.4  444.23  5132.4  444.49  5182.1  443.96  5202.9  442.46
  5213.7  442.95  5289.4   443.5  5316.6  442.21  5324.6  440.88    5339  442.57
  5359.9  442.04  5502.8  444.56  5538.6  446.56  5696.6  448.44    5825  452.08
#Mann= 5 ,-1 , 0
    4242     .05       0  4739.1      .1       0  5001.2     .07       0
  5007.2      .1       0  5213.7     .05       0
Bank Sta=4983.4,5025.1
XS Rating Curve= 0 ,0
Exp/Cntr=0.3,0.1

Type RM Length L Ch R = 1 ,9412    ,798,798,798
BEGIN DESCRIPTION:
CEDAR CREEK 1 4.1
END DESCRIPTION:
XS GIS Cut Line= 4
      3467672.54     10522517.65      3467530.18     10521969.01
      3467571.84     10521705.12      3467235.57     10521115.77
#Sta/Elev= 30
  4313.8  447.46    4452   445.2  4588.6  440.95  4609.1   438.6  4629.9  437.32
  4640.3  438.33  4649.7  440.48  4660.9  441.95  4671.3  442.67  4769.1  443.35
  4852.5  443.71  4857.7  443.54  4876.7  440.07  4888.1  440.04  4938.7  442.72
  4958.9  439.01  4979.2  438.77  4986.7  435.29  4996.4  432.54  4999.2  432.04
  5002.4  432.54  5009.6  437.74  5039.9   442.6  5054.2   443.6  5206.2  442.35
  5399.4  442.75  5523.2  444.18  5612.3   446.8    5722  451.91  5826.3  454.63
#Mann= 5 ,-1 , 0
  4313.8     .05       0  4769.1      .1       0  4996.4     .07       0
  5002.4      .1       0  5206.2     .05       0
Bank Sta=4938.7,5039.9
XS Rating Curve= 0 ,0
Exp/Cntr=0.3,0.1

Type RM Length L Ch R = 1 ,8614    ,652,652,652
BEGIN DESCRIPTION:
CEDAR CREEK 1 3.1
END DESCRIPTION:
XS GIS Cut Line= 5
      3467962.38     10522106.48      3467964.21     10521580.12
      3467735.04     10521212.07      3467585.73     10521097.48
      3467420.59     10521011.77
#Sta/Elev= 30
  4211.8  447.38  4316.6  442.77  4396.7  441.73  4426.6     439  4466.6  442.87
  4616.6  441.51  4706.6  442.33  4726.6  442.06  4759.9  439.47  4804.8  438.87
  4926.3  438.61  4962.9  440.18  4978.2  439.56  4996.5  432.54  4999.2  432.04
  5002.5  432.54  5020.7  438.73    5026  439.05  5030.2  439.31  5036.1  437.94
  5057.3  437.99    5088  440.36  5151.7   440.5  5169.8   441.9  5288.9  443.46
  5397.8  446.95  5432.1  449.04  5448.6  448.78  5476.7  450.87    5546  453.13
#Mann= 5 ,-1 , 0
  4211.8     .05       0  4396.7      .1       0  4996.5     .07       0
  5002.5      .1       0    5026     .05       0
Bank Sta=4978.2,5020.7
XS Rating Curve= 0 ,0
Exp/Cntr=0.3,0.1

Type RM Length L Ch R = 1 ,7962    ,929,929,929
BEGIN DESCRIPTION:
CEDAR CREEK 1 2.1
END DESCRIPTION:
XS GIS Cut Line= 5
      3468863.53     10521982.92      3468446.84     10521368.32
      3467901.71     10521114.84      3467594.16      10520942.3
      3467529.06     10520918.44
#Sta/Elev= 30
    4071  447.35  4122.5  447.47  4137.5  446.29  4158.4  447.48  4173.4  446.09
  4217.5  446.63  4532.8   440.6  4618.1   439.9  4706.1  440.19  4861.2  440.76
    4896  439.38    4929  440.64  4958.6  438.32  4963.7  438.67  4981.1  437.19
    5001  428.82  5003.7  428.32    5007  428.82  5017.3  436.19  5026.9  438.75
  5116.5  437.67  5146.8  440.22  5172.7  440.47  5226.8  440.03  5249.4  438.83
  5309.1  440.85  5609.2  443.71  5755.5  447.77  5801.5  450.85  5836.7  451.09
#Mann= 8 ,-1 , 0
    4071     .05       0  4618.1      .1       0  4706.1     .05       0
  4958.6     .12       0    5001     .07       0    5007     .12       0
  5172.7      .1       0  5309.1     .05       0
Bank Sta=4963.7,5026.9
XS Rating Curve= 0 ,0
Exp/Cntr=0.3,0.1

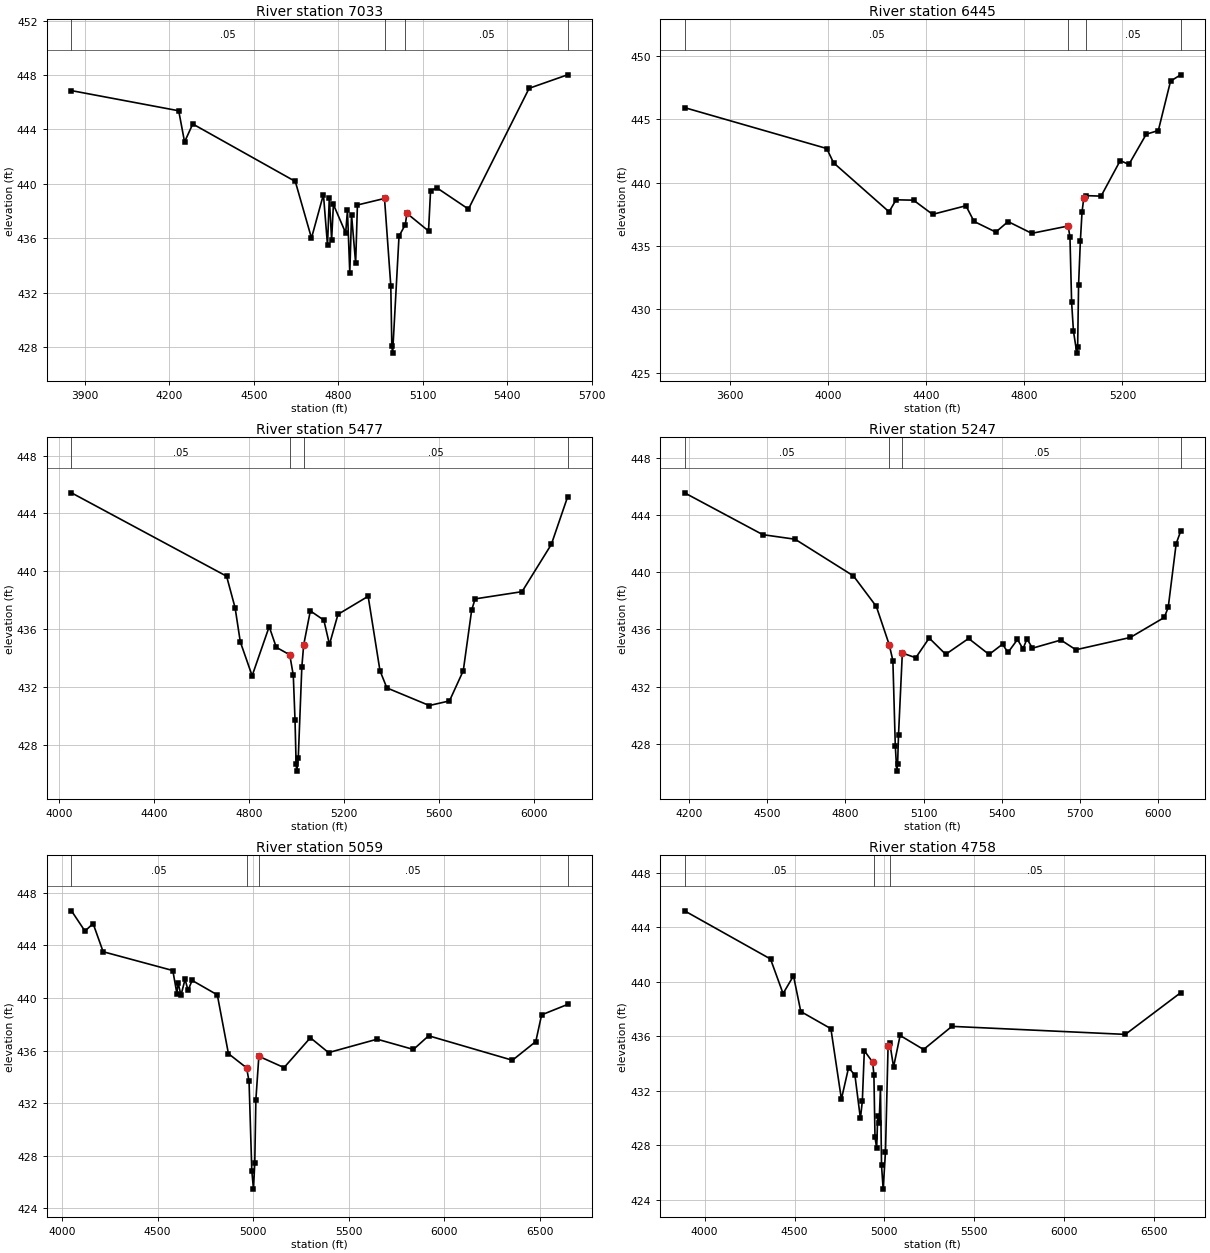
Type RM Length L Ch R = 1 ,7033    ,588,588,588
BEGIN DESCRIPTION:
CEDAR CREEK 1 2.0
END DESCRIPTION:
XS GIS Cut Line= 3
      3469421.43       10521576.      3468562.04     10520924.94
      3467950.06     10520621.12
#Sta/Elev= 30
  3852.2  446.85    4233  445.37  4253.8  443.08  4282.9   444.4    4647  440.18
  4704.5  436.02  4746.9  439.22  4761.4  435.49  4767.7  438.96    4776   435.9
  4782.3  438.49  4825.9   436.4  4832.2  438.05  4840.5  433.46  4846.7  437.73
  4861.3  434.18  4867.6  438.45  4963.8  438.93  4986.1  432.53  4989.8  428.07
  4992.6  427.57  5015.3  436.16  5037.7  437.01  5043.2  437.84  5120.1  436.54
  5127.3  439.49  5149.7  439.71  5261.8  438.15  5477.3  447.02  5613.6  448.01
#Mann= 4 ,-1 , 0
  3852.2     .05       0  4963.8     .03       0  5037.7     .05       0
  5613.6     .05       0
Bank Sta=4963.8,5043.2
XS Rating Curve= 0 ,0
Exp/Cntr=0.3,0.1

Type RM Length L Ch R = 1 ,6445    ,968,968,968
BEGIN DESCRIPTION:
CEDAR CREEK 1 1.0
END DESCRIPTION:
XS GIS Cut Line= 4
      3469560.34     10521491.56      3468744.33     10520779.72
      3468596.76      10520491.1      3468143.19     10520072.25
#Sta/Elev= 30
  3412.9  445.92  3993.1  442.69    4021  441.56  4247.5  437.69    4276  438.64
  4347.2  438.61  4425.1  437.49  4561.1  438.17  4594.3  436.93  4683.1  436.09
  4733.2  436.92  4829.8  435.99  4978.3  436.57  4985.7   435.7  4992.5  430.53
  4999.9  428.28  5013.8  426.53  5017.1  427.03  5020.9  431.94  5028.2  435.39
    5035  437.68  5042.4  438.82  5049.2  438.97  5112.7  438.93    5191  441.74
  5226.1  441.43    5297  443.82  5346.3  444.11  5396.2  448.01  5437.3  448.51
#Mann= 4 ,-1 , 0
  3412.9     .05       0  4978.3     .03       0  5049.2     .05       0
  5437.3     .05       0
Bank Sta=4978.3,5042.4
XS Rating Curve= 0 ,0
Exp/Cntr=0.3,0.1

Type RM Length L Ch R = 1 ,5477    ,230,230,230
BEGIN DESCRIPTION:
ROCKY CREEK 30.6
END DESCRIPTION:
XS GIS Cut Line= 4
      3469584.92     10521357.83      3468932.16     10520406.46
      3468574.52     10519941.18       3468230.8     10519885.63
#Sta/Elev= 30
  4052.3  445.42  4705.5  439.65  4741.4  437.46  4763.2  435.11  4813.1  432.76
  4884.9  436.16  4914.7  434.73  4971.5  434.21  4986.4  432.79  4993.6  429.72
  4998.3  426.66    5001  426.16  5007.4  427.09  5022.3  433.35    5030  434.88
  5058.1  437.25    5115  436.61  5138.7  434.93  5174.6  437.01  5301.6  438.26
  5351.4  433.11  5380.4  431.92    5559   430.7  5644.1  431.02  5702.2  433.11
  5737.5   437.3    5752  438.08  5949.6  438.58    6073  441.85  6141.1  445.12
#Mann= 4 ,-1 , 0
  4052.3     .05       0  4971.5     .03       0    5030     .05       0
  6141.1     .05       0
Bank Sta=4971.5,5030
XS Rating Curve= 0 ,0
Exp/Cntr=0.3,0.1

Type RM Length L Ch R = 1 ,5247    ,188,188,188
BEGIN DESCRIPTION:
ROCKY CREEK 29.5
END DESCRIPTION:
XS GIS Cut Line= 3
      3469706.45     10521253.66      3469055.42     10520236.76
      3468680.43     10519648.22
#Sta/Elev= 30
  4181.9  445.57  4482.3  442.64  4606.5  442.32  4830.6  439.75  4918.5  437.61
    4968  434.93    4982  433.82  4991.3  427.85  4996.9  426.08  5000.2  426.58
  5003.6  428.61  5018.3  434.35  5069.9  434.02  5121.5   435.4  5184.9  434.26
  5272.8  435.37  5351.5  434.25  5403.1  434.97  5424.2  434.39  5460.6   435.3
  5481.8  434.64    5497  435.34  5518.2  434.69  5627.4  435.26  5684.9  434.58
    5894  435.44  6024.4  436.84  6039.6  437.55  6070.1  442.01  6087.2  442.87
#Mann= 4 ,-1 , 0
  4181.9     .05       0    4968     .03       0  5018.3     .05       0
  6087.2     .05       0
Bank Sta=4968,5018.3
XS Rating Curve= 0 ,0
Exp/Cntr=0.3,0.1

Type RM Length L Ch R = 1 ,5059    ,301,301,301
BEGIN DESCRIPTION:
ROCKY CREEK 30.4
END DESCRIPTION:
XS GIS Cut Line= 2
      3469863.77     10521226.89       3468520.6     10519005.62
#Sta/Elev= 30
    4049  446.62  4119.6  445.08  4162.3  445.65  4214.7  443.51  4579.4  442.08
  4600.8  440.32  4606.6  441.17  4622.1   440.2  4643.5  441.42    4659  440.57
  4680.3  441.33  4812.2  440.23  4870.4  435.76  4965.5  434.68  4978.3  433.65
  4992.7  426.86  5001.5  425.46  5008.2  427.45    5014  432.26  5029.6  435.56
  5161.5   434.7  5299.2  436.97  5394.3  435.84  5648.4  436.86  5838.6  436.08
  5918.1  437.12  6356.6  435.26  6478.8  436.68  6509.2  438.71  6644.8   439.5
#Mann= 4 ,-1 , 0
    4049     .05       0  4965.5     .03       0  5029.6     .05       0
  6644.8     .05       0
Bank Sta=4965.5,5029.6
XS Rating Curve= 0 ,0
Exp/Cntr=0.3,0.1

Type RM Length L Ch R = 1 ,4758    ,1501,1501,1501
BEGIN DESCRIPTION:
ROCKY CREEK 29.4
END DESCRIPTION:
XS GIS Cut Line= 4
      3470020.02     10521185.22      3469610.28     10520261.58
      3468822.09       10519022.       3468573.8      10518895.6
#Sta/Elev= 30
  3888.8  445.22  4366.6  441.68  4436.4  439.14  4494.4  440.44  4534.9  437.82
  4702.3  436.56  4760.8  431.38  4800.7   433.7    4836  433.14  4866.4  429.96
  4877.1  431.22  4888.2  434.94  4934.7   434.1  4941.5  433.15  4947.5  428.59
  4956.8  427.78  4962.7  430.16  4970.3  429.61    4978  432.18  4983.9  426.51
  4992.9  424.77  5005.8   427.5  5020.3  435.29  5029.5  435.52  5050.8  433.75
  5087.2  436.06  5217.6  435.03  5375.1  436.73  6339.6  436.14  6646.8   439.2
#Mann= 3 ,-1 , 0
  3888.8     .05       0  4941.5     .03       0  5029.5     .05       0
Bank Sta=4934.7,5020.3
XS Rating Curve= 0 ,0
Exp/Cntr=0.3,0.1

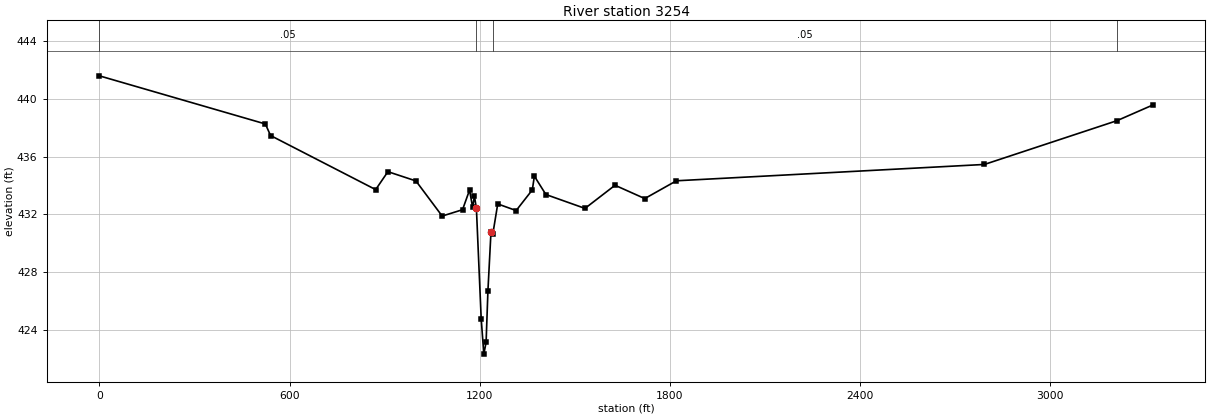
Type RM Length L Ch R = 1 ,3254    ,0,0,0
BEGIN DESCRIPTION:
ROCKY CREEK 30.5
END DESCRIPTION:
XS GIS Cut Line= 5
      3470978.07     10520472.78       3470448.9     10519455.78
      3470300.07     10519364.83      3469390.56     10518781.91
      3468481.04     10518628.95
#Sta/Elev= 30
       0  441.59   523.8  438.26   540.2  437.46   871.8  433.72   910.4  434.96
   998.8  434.32  1081.6  431.89  1145.9  432.33    1168  433.69  1177.6   432.5
  1183.4  433.26  1189.6  432.43  1204.7   424.8    1213  422.34  1220.2  423.16
    1226  426.74  1235.6   430.8  1241.5  430.66  1256.9  432.73    1315  432.27
    1366   433.7  1372.5  434.65  1408.8  433.38  1532.2  432.42  1626.9  434.02
  1720.8   433.1  1820.6  434.33  2792.3  435.46  3210.8  438.49  3323.4  439.57
#Mann= 4 ,-1 , 0
       0     .05       0  1189.6     .03       0  1241.5     .05       0
  3210.8     .05       0
Bank Sta=1189.6,1235.6
XS Rating Curve= 0 ,0
Exp/Cntr=0.3,0.1

Chan Stop Cuts=-1
Use User Specified Reach Order=0
Composite Channel Slope=5