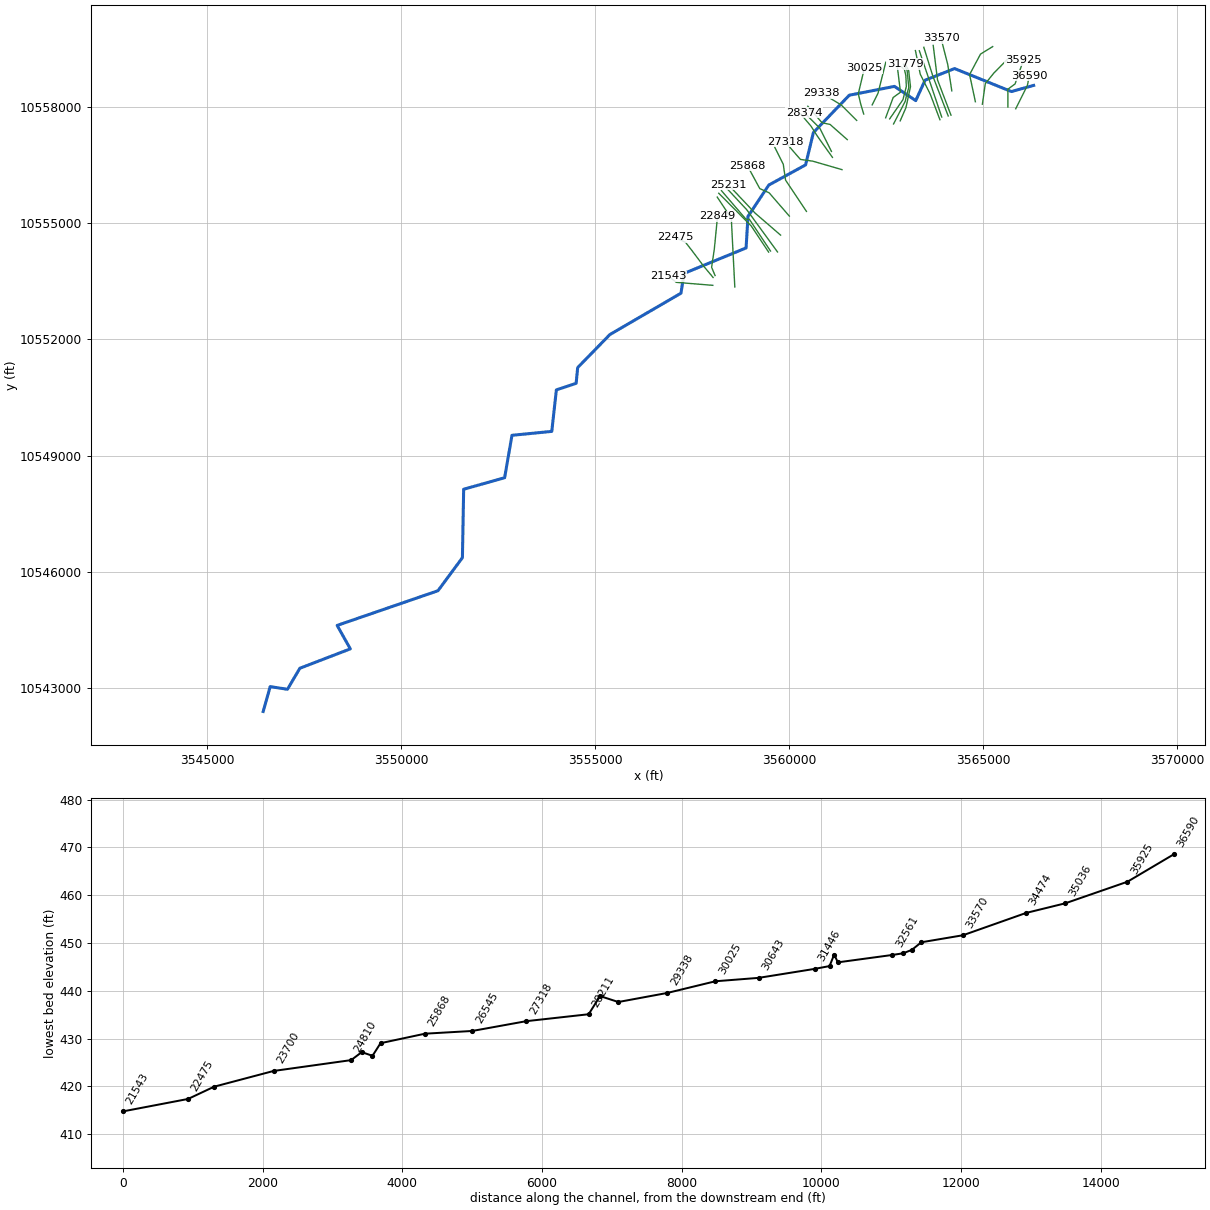
--- CEDAR CREEK 2.prj (project) ---

Proj Title=CEDAR CREEK 2 Base Level Engineering
Current Plan=p01
Default Exp/Contr=0.3,0.1
English Units
Geom File=g01
Flow File=f01
Plan File=p01
Y Axis Title=Elevation
X Axis Title(PF)=Main Channel Distance
X Axis Title(XS)=Station
BEGIN DESCRIPTION:
CEDAR CREEK 2
END DESCRIPTION:
DSS Export Rating Curves= 0
DSS Export Rating Curve Sorted= 0
DSS Export Volume Flow Curves= 0
DXF OffsetX= 0
DXF OffsetY= 0
DXF ScaleX= 1
DXF ScaleY= 10

--- CEDAR CREEK 2.p01 (plan) ---

Plan Title=Multiple Run
Short Identifier=Multiple
Geom File=g01
Flow File=f01
Subcritical Flow
K Sum by GR= 0
Std Step Tol= 0.01
Critical Tol= 0.01
Num of Std Step Trials= 20
Max Error Tol= 0.3
Flow Tol Ratio= 0.001
Split Flow NTrial= 30
Split Flow Tol= 0.02
Split Flow Ratio= 0.02
Log Output Level= 0
Friction Slope Method= 1
Unsteady Friction Slope Method= 2
Unsteady Bridges Friction Slope Method= 1
Parabolic Critical Depth
Global Vel Dist=  1 , 1 , 1
Global Log Level= 0
CheckData=True
Encroach Param= -1, 0, 0, 0
BEGIN DESCRIPTION:
Multiple Run
END DESCRIPTION:

--- CEDAR CREEK 2.f01 (steady flow) ---

Flow Title=Multiple
Program Version=4.10
Number of Profiles= 7
Profile Names=10-year,25-year,50-year,1pct_min,100-year,1pct_plu,500-year
River Rch & RM=CEDAR CREEK 2,Reach-1         ,36590
     972    1320    1602    1419    1919    2595    2742
River Rch & RM=CEDAR CREEK 2,Reach-1         ,32715
    1738    2440    3030    2739    3704    5009    5521
River Rch & RM=CEDAR CREEK 2,Reach-1         ,22475
    1852    2607    3242    2934    3968    5366    5930
River Rch & RM=CEDAR CREEK 2,Reach-1         ,21056
    2696    3862    4861    4448    6015    8135    9192
River Rch & RM=CEDAR CREEK 2,Reach-1         ,19578
    3157    4545    5738    5263    7118    9626   10930
River Rch & RM=CEDAR CREEK 2,Reach-1         ,14976
    3520    5079    6422    5897    7975   10785   12274
River Rch & RM=CEDAR CREEK 2,Reach-1         ,8541
    3612    5212    6591    6052    8184   11068   12593
River Rch & RM=CEDAR CREEK 2,Reach-1         ,5248
    3792    5478    6933    6369    8614   11649   13270
River Rch & RM=CEDAR CREEK 2,Reach-1         ,2145
    3735    5382    6798    6233    8429   11399   12934
Boundary for River Rch & Prof#=CEDAR CREEK 2,Reach-1         , 1
Up Type= 0
Dn Type= 3
Dn Slope=0.00146
Boundary for River Rch & Prof#=CEDAR CREEK 2,Reach-1         , 2
Up Type= 0
Dn Type= 3
Dn Slope=0.00146
Boundary for River Rch & Prof#=CEDAR CREEK 2,Reach-1         , 3
Up Type= 0
Dn Type= 3
Dn Slope=0.00146
Boundary for River Rch & Prof#=CEDAR CREEK 2,Reach-1         , 4
Up Type= 0
Dn Type= 3
Dn Slope=0.00146
Boundary for River Rch & Prof#=CEDAR CREEK 2,Reach-1         , 5
Up Type= 0
Dn Type= 3
Dn Slope=0.00146
Boundary for River Rch & Prof#=CEDAR CREEK 2,Reach-1         , 6
Up Type= 0
Dn Type= 3
Dn Slope=0.00146
Boundary for River Rch & Prof#=CEDAR CREEK 2,Reach-1         , 7
Up Type= 0
Dn Type= 3
Dn Slope=0.00146
DSS Import GetInterval= 0
DSS Import GetPeak= 0
DSS Import FillOption= 0

--- CEDAR CREEK 2.g01 (geometry) ---

Geom Title=Existing Conditions
Program Version=4.10

River Reach=CEDAR CREEK 2   ,Reach-1
Reach XY= 30
       3566303.4     10558544.27      3565730.48     10558385.59
      3564265.81     10558978.42       3563504.1     10558677.28
      3563264.52     10558151.59      3562716.39     10558518.76
      3561551.39     10558290.97      3560627.03     10557328.31
      3560425.09     10556494.19      3559476.85     10555974.59
      3558940.84       10555167.      3558891.88     10554353.59
      3557293.32     10553696.84      3557213.41     10553186.83
      3555381.83     10552120.73      3554551.24     10551269.13
      3554511.38     10550862.39      3554001.95     10550694.45
      3553883.47     10549623.84      3552857.78     10549522.45
       3552668.1     10548429.04      3551612.45     10548131.99
      3551580.31     10546367.61      3550950.51     10545515.59
      3548351.17     10544621.24      3548691.01     10544016.81
       3547389.5     10543516.22      3547071.29     10542974.91
      3546625.43      10543043.5      3546445.52     10542402.88

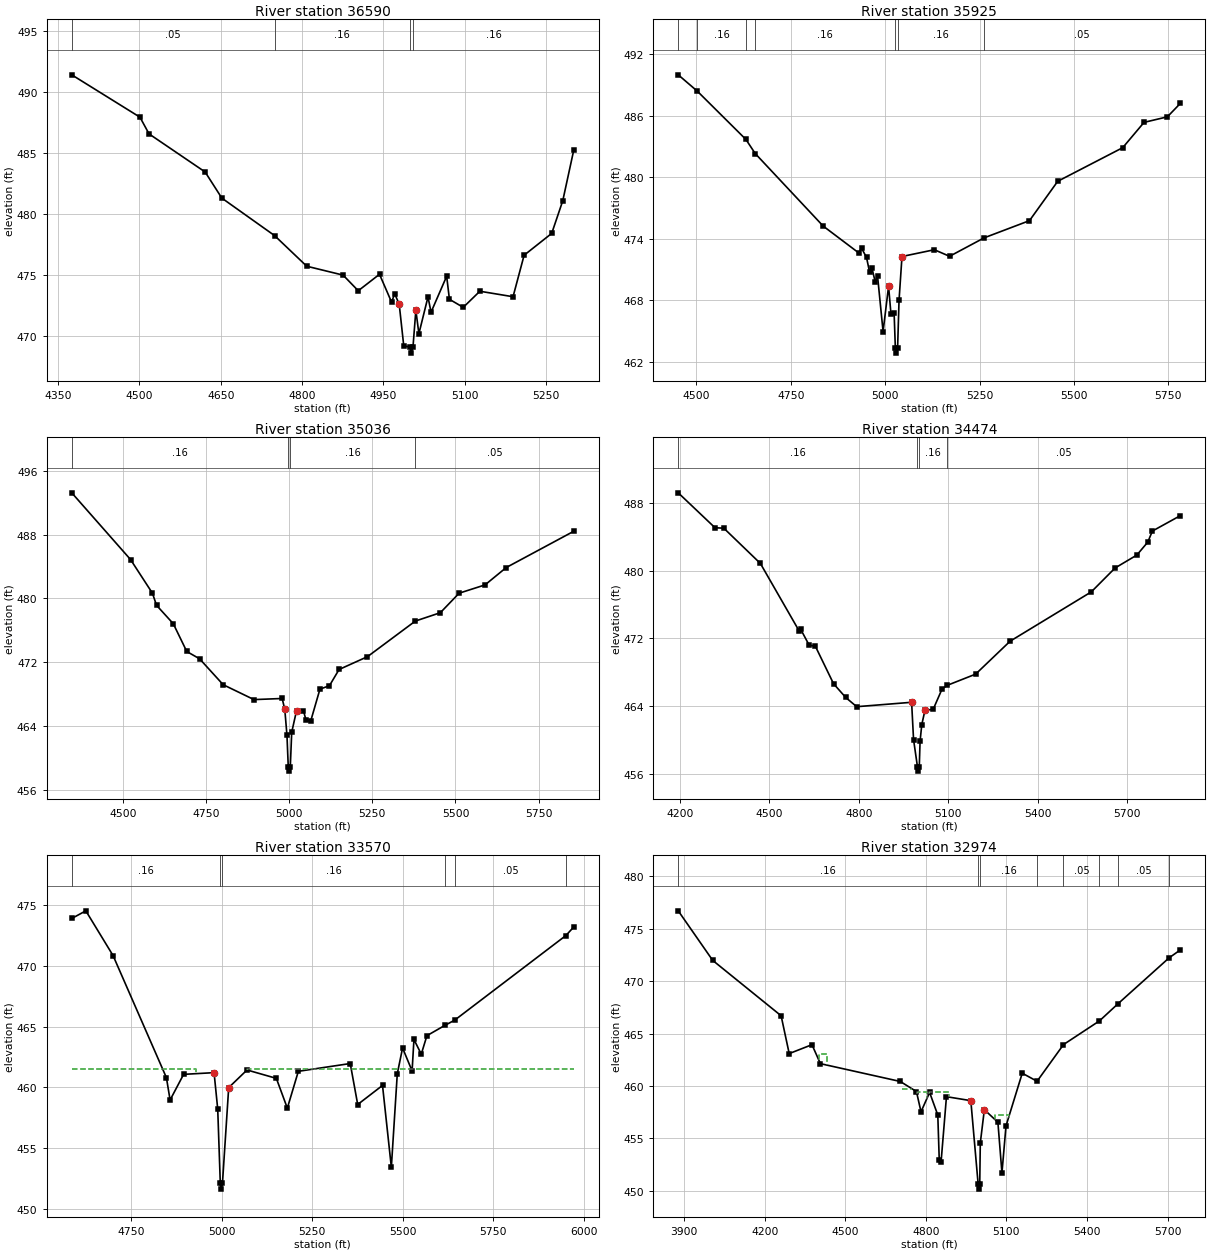
Type RM Length L Ch R = 1 ,36590   ,665,665,665
BEGIN DESCRIPTION:
CEDAR CREEK 2 75.0
END DESCRIPTION:
XS GIS Cut Line= 3
      3565842.12     10557941.67      3566142.11     10558541.64
       3566192.1     10558791.61
#Sta/Elev= 30
  4375.3  491.38    4501  487.91  4517.8  486.54  4621.2  483.42    4652  481.28
  4749.2  478.21  4808.5   475.7  4875.6  474.97  4903.5  473.69  4942.7  475.04
    4965  472.75  4970.6  473.45    4979  472.59  4987.4  469.17  4998.4  469.08
  5001.1  468.58  5004.4  469.08  5009.7  472.09  5015.3  470.17  5032.1  473.19
  5037.7  471.93  5066.5  474.88  5071.6  472.99  5097.1  472.33  5127.7  473.65
  5188.9   473.2  5209.3   476.6  5260.2  478.39  5280.6  481.07    5301  485.25
#Mann= 4 ,-1 , 0
  4375.3     .05       0  4749.2     .16       0  4998.4     .07       0
  5004.4     .16       0
Bank Sta=4979,5009.7
XS Rating Curve= 0 ,0
Exp/Cntr=0.3,0.1

Type RM Length L Ch R = 1 ,35925   ,889,889,889
BEGIN DESCRIPTION:
CEDAR CREEK 2 74.0
END DESCRIPTION:
XS GIS Cut Line= 4
      3565640.09     10557987.64      3565640.09     10558445.97
      3565824.12     10558581.38      3566038.97     10559187.84
#Sta/Elev= 30
  4451.7  489.99  4502.1   488.4  4631.1  483.68  4655.6  482.31  4835.7  475.23
  4929.6  472.62  4937.4  473.07  4950.5  472.17  4958.9   470.7  4965.1   471.1
  4973.5  469.79  4979.7  470.38  4994.4  464.94    5009  469.36  5015.2  466.68
  5023.7  466.71  5026.9  463.33  5029.6  462.83  5032.9  463.33  5036.7  467.98
  5044.5  472.26  5130.2  472.92  5170.6  472.28  5262.1  474.08  5382.3  475.76
  5457.1   479.6  5629.3  482.88  5685.8  485.35  5747.6  485.89  5781.9   487.2
#Mann= 7 ,-1 , 0
  4451.7     .05       0  4502.1     .16       0  4631.1     .05       0
  4655.6     .16       0  5026.9     .07       0  5032.9     .16       0
  5262.1     .05       0
Bank Sta=5009,5044.5
XS Rating Curve= 0 ,0
Exp/Cntr=0.3,0.1

Type RM Length L Ch R = 1 ,35036   ,562,562,562
BEGIN DESCRIPTION:
CEDAR CREEK 2 72.0
END DESCRIPTION:
XS GIS Cut Line= 4
      3564982.55      10558059.5      3565058.14     10558590.88
       3565277.6       10558861.      3565715.18     10559306.05
#Sta/Elev= 30
  4346.9  493.26  4523.6  484.88  4589.4  480.65  4601.6  479.14  4652.1  476.82
  4692.5  473.34  4731.1  472.42  4801.9  469.17  4894.5   467.3  4979.2  467.44
  4987.1  466.07  4993.6  462.83  4997.6  458.82  5000.3  458.32  5003.6  458.82
  5007.9   463.2  5022.3  465.89  5043.1   465.9  5051.1  464.71    5065  464.61
  5092.7  468.61  5121.4  469.05  5150.2  471.08  5235.6  472.69  5379.4  477.16
  5454.6  478.21  5511.1  480.66  5588.9   481.7  5652.6  483.88  5855.8  488.44
#Mann= 4 ,-1 , 0
  4346.9     .16       0  4997.6     .07       0  5003.6     .16       0
  5379.4     .05       0
Bank Sta=4987.1,5022.3
XS Rating Curve= 0 ,0
Exp/Cntr=0.3,0.1

Type RM Length L Ch R = 1 ,34474   ,904,904,904
BEGIN DESCRIPTION:
CEDAR CREEK 2 71.0
END DESCRIPTION:
XS GIS Cut Line= 4
      3564801.99     10558122.07      3564652.69     10558823.43
      3564933.94     10559351.21      3565248.53      10559544.8
#Sta/Elev= 30
  4194.3  489.21  4317.7  485.08  4347.2  485.03  4469.9  480.86  4599.9  472.88
    4605  473.08  4633.5   471.2  4654.5  471.06  4715.3  466.64  4756.2  465.01
    4793  463.92  4977.3  464.44  4983.8  460.03    4997   456.8  4999.8   456.3
    5003   456.8  5005.7  459.84  5011.4  461.79    5022  463.49  5049.7  463.61
  5079.3     466  5095.7  466.43  5192.1  467.77  5307.6  471.66  5580.3   477.5
  5659.9  480.32  5732.9  481.85  5769.6  483.38  5785.1  484.69  5878.8  486.51
#Mann= 4 ,-1 , 0
  4194.3     .16       0    4997     .07       0    5003     .16       0
  5095.7     .05       0
Bank Sta=4977.3,5022
XS Rating Curve= 0 ,0
Exp/Cntr=0.3,0.1

Type RM Length L Ch R = 1 ,33570   ,596,596,596
BEGIN DESCRIPTION:
CEDAR CREEK 2 69.0
END DESCRIPTION:
XS GIS Cut Line= 3
      3564194.35     10558403.34      3564090.19     10559080.37
      3563916.84     10559759.91
#Sta/Elev= 30
    4586  473.89  4624.8  474.52    4700  470.84  4847.3   460.8  4857.5  458.96
  4894.8  461.07  4978.9  461.21    4989  458.21  4996.1  452.13  4998.9  451.63
  5002.1  452.13  5019.3  459.98  5069.9  461.43  5150.9  460.74  5181.2  458.29
  5211.6  461.32  5354.9  461.96  5375.5  458.59    5444  460.16  5468.4  453.43
  5484.8  461.12  5499.4  463.24  5525.7  461.35  5530.8  463.94    5551  462.73
  5566.6  464.25  5615.7  465.09  5643.4  465.53  5950.4  472.49  5972.3   473.2
#Mann= 6 ,-1 , 0
    4586     .16       0  4996.1     .07       0  5002.1     .16       0
  5615.7      .1       0  5643.4     .05       0  5950.4      .1       0
#XS Ineff= 2 , 0
         4928.18  461.55    5070          461.48
Permanent Ineff=
       F       F
Bank Sta=4978.9,5019.3
XS Rating Curve= 0 ,0
Exp/Cntr=0.3,0.1

Type RM Length L Ch R = 1 ,32974   ,136,136,136
BEGIN DESCRIPTION:
CEDAR CREEK 2 68.03
END DESCRIPTION:
XS GIS Cut Line= 3
      3564173.07     10557777.07      3563825.84     10558686.82
      3563714.72     10559575.73
#Sta/Elev= 30
  3878.1  476.71  4006.5  471.98  4261.2   466.7  4291.3  463.09  4376.1  463.94
  4407.5  462.13    4705  460.43  4765.1  459.47  4782.1  457.54  4814.2  459.38
  4844.6  457.23    4850  452.98  4856.8  452.74  4876.9  458.98  4967.6   458.6
  4994.8  450.66  4997.6  450.16  5000.8  450.66  5002.9  454.56    5018  457.74
  5068.4  456.54  5083.5  451.71  5098.6  456.19  5159.1  461.22  5214.3  460.45
  5312.7  463.95  5446.6  466.21  5514.6  467.82  5706.2  472.23  5747.7  472.98
#Mann= 8 ,-1 , 0
  3878.1     .16       0  4994.8     .07       0  5000.8     .16       0
  5214.3      .1       0  5312.7     .05       0  5446.6      .1       0
  5514.6     .05       0  5706.2     .16       0
#XS Ineff= 5 ,-1
 4401.99  4430.4  463.03 4710.23    4750  459.72 4767.05 4803.98  459.46
  4812.5 4887.78  459.39 5058.24 5107.95  457.25
Permanent Ineff=
       F       F       F       F       F
Bank Sta=4967.6,5018
XS Rating Curve= 0 ,0
Exp/Cntr=0.3,0.1

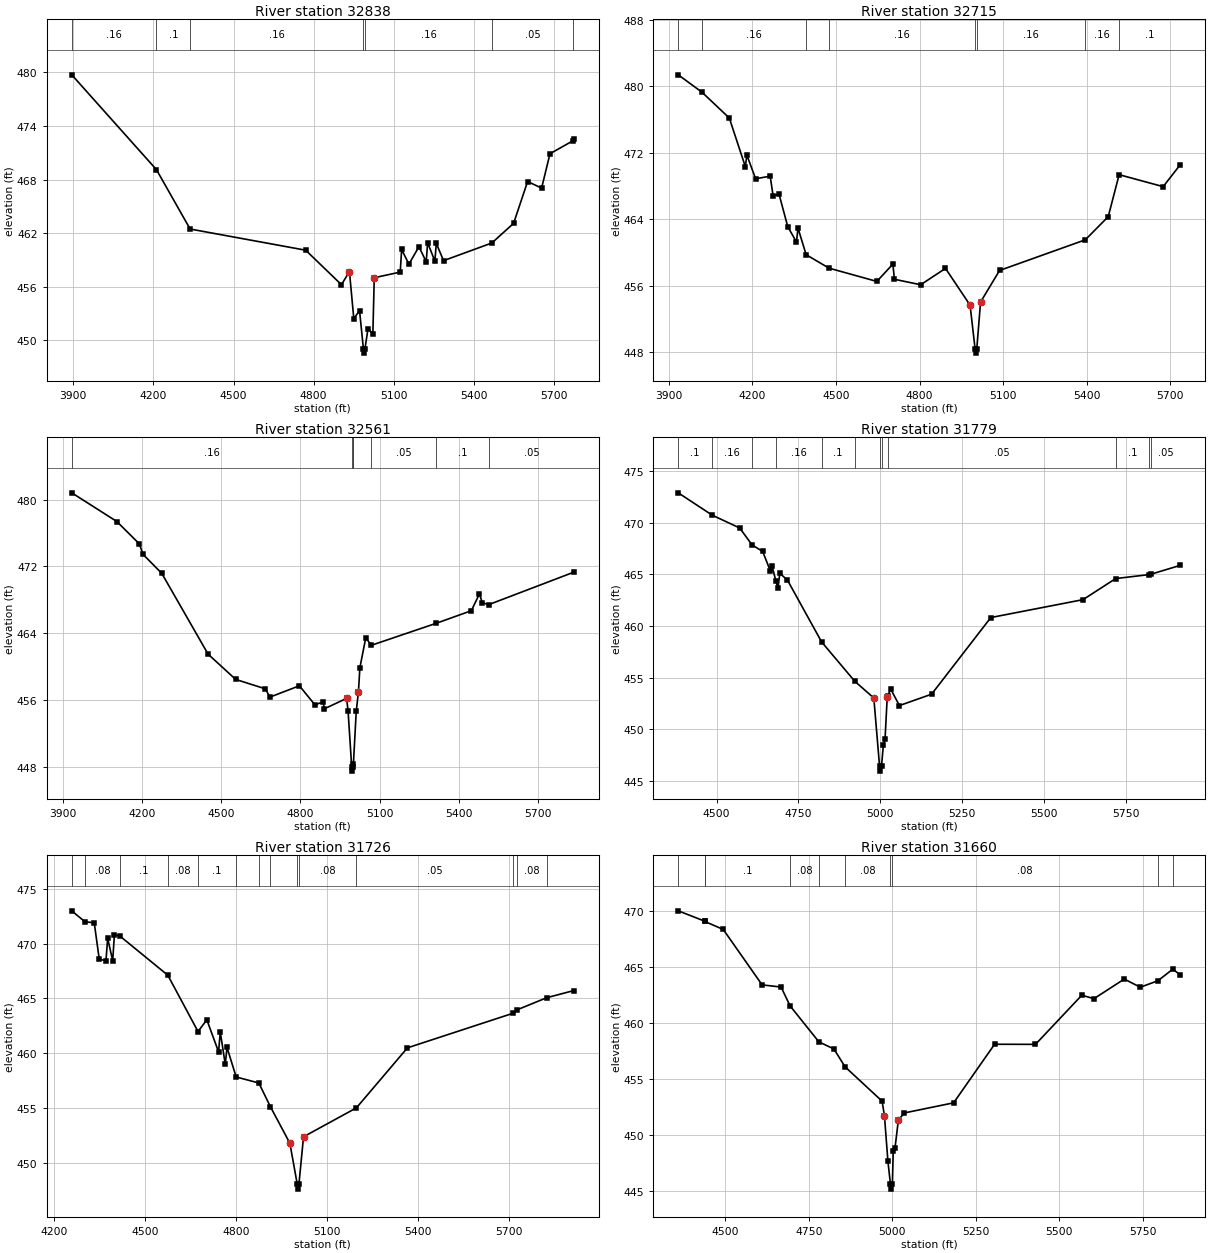
Type RM Length L Ch R = 1 ,32838   ,123,123,123
BEGIN DESCRIPTION:
CEDAR CREEK 2 68.01
END DESCRIPTION:
XS GIS Cut Line= 3
      3564101.01     10557756.61      3563709.52      10558771.8
      3563472.59     10559526.84
#Sta/Elev= 30
  3894.5  479.72  4211.4  469.11  4337.5  462.46  4770.2  460.09  4903.9  456.23
  4933.9   457.7  4950.2  452.42  4971.7  453.34  4986.1  449.07  4988.9  448.57
  4992.1  449.07  5003.4  451.31  5021.5   450.7  5026.8  457.01    5124  457.64
  5129.3  460.17  5156.5  458.53  5194.1  460.48  5221.3  458.79  5226.6  460.94
  5253.7  458.86    5259  460.85  5286.2  458.92  5467.1   460.9  5548.4   463.1
  5600.8  467.78  5653.2  467.04  5684.6  470.89  5771.8  472.36  5773.9  472.54
#Mann= 7 ,-1 , 0
  3894.5     .16       0  4211.4      .1       0  4337.5     .16       0
  4986.1     .07       0  4992.1     .16       0  5467.1     .05       0
  5771.8     .16       0
Bank Sta=4933.9,5026.8
XS Rating Curve= 0 ,0
Exp/Cntr=0.3,0.1

Type RM Length L Ch R = 1 ,32715   ,154,154,154
BEGIN DESCRIPTION:
CEDAR CREEK 2 68.0
END DESCRIPTION:
XS GIS Cut Line= 2
      3563934.36      10557728.8      3563358.05      10559436.9
#Sta/Elev= 30
  3933.7  481.36  4018.9  479.27  4117.1  476.16  4174.7   470.3    4180  471.71
  4211.5  468.85  4263.9  469.16  4274.4  466.75  4295.4  467.02  4326.8   463.1
  4358.3  461.22  4363.6  462.92  4392.9  459.71  4475.1  458.09  4646.8  456.49
  4704.5  458.58  4709.8  456.75  4804.2  456.09  4893.3  458.06  4981.5  453.64
  4999.6  448.36  5002.4  447.86  5005.6  448.36  5019.2  454.01  5087.4  457.81
  5395.3   461.5  5477.6  464.29  5516.7  469.34  5674.8   467.9  5736.4  470.55
#Mann= 8 ,-1 , 0
  3933.7      .1       0  4018.9     .16       0  4392.9      .1       0
  4475.1     .16       0  4999.6     .07       0  5005.6     .16       0
  5395.3     .16       0  5516.7      .1       0
Bank Sta=4981.5,5019.2
XS Rating Curve= 0 ,0
Exp/Cntr=0.3,0.1

Type RM Length L Ch R = 1 ,32561   ,782,782,782
BEGIN DESCRIPTION:
CEDAR CREEK 2 68.02
END DESCRIPTION:
XS GIS Cut Line= 4
      3563888.35     10557659.01      3563638.34     10558318.76
      3563381.39     10558832.65      3563256.74     10559442.05
#Sta/Elev= 30
  3933.6   480.8  4104.3  477.37  4189.4   474.7  4203.8  473.43  4274.5  471.17
  4450.1   461.5  4554.6  458.48  4667.3  457.35  4684.1  456.36  4795.9  457.72
  4854.8  455.44  4885.3  455.79  4890.9  454.97  4974.7  456.21  4980.3  454.74
  4994.1  448.01  4996.9  447.51  5000.1  448.01  5000.6  448.38  5011.3  454.67
  5019.5  456.93  5025.1  459.88  5047.4  463.47  5068.3  462.56  5314.9   465.2
  5447.4   466.7    5478  468.71    5489  467.64  5513.6  467.43  5835.7  471.31
#Mann= 7 ,-1 , 0
  3933.6     .16       0  4994.1     .07       0  5000.1     .16       0
  5000.6      .1       0  5068.3     .05       0  5314.9      .1       0
  5513.6     .05       0
Bank Sta=4974.7,5019.5
XS Rating Curve= 0 ,0
Exp/Cntr=0.3,0.1

Type RM Length L Ch R = 1 ,31779   ,53,53,53
BEGIN DESCRIPTION:
CEDAR CREEK 2 67.0
END DESCRIPTION:
XS GIS Cut Line= 5
      3562864.06     10557629.82      3563011.63     10557968.36
      3563129.68     10558511.76      3563082.81     10558926.69
      3562994.33      10559096.7
#Sta/Elev= 30
  4382.8  472.87  4486.6  470.71  4570.6  469.47  4608.6  467.83  4640.9   467.2
  4664.3  465.32  4669.8  465.76  4681.5  464.31  4687.8  463.63  4693.2  465.09
  4716.6  464.43  4821.1  458.45  4922.4  454.65  4980.6  453.03  4998.1  446.46
  5000.8  445.96  5004.1  446.46  5009.8  448.48  5014.9  449.05  5021.5  453.08
  5023.8  453.27  5031.8  453.91  5058.9   452.3  5157.2   453.4  5338.2  460.81
    5620  462.54  5719.9  464.58  5821.3  464.96  5827.7     465  5917.4  465.86
#Mann= 12 ,-1 , 0
  4382.8      .1       0  4486.6     .16       0  4608.6      .1       0
  4681.5     .16       0  4821.1      .1       0  4922.4     .08       0
  4998.1     .07       0  5004.1     .08       0  5023.8     .05       0
  5719.9      .1       0  5821.3     .08       0  5827.7     .05       0
Bank Sta=4980.6,5021.5
XS Rating Curve= 0 ,0
Exp/Cntr=0.3,0.1

Type RM Length L Ch R = 1 ,31726   ,66,66,66
BEGIN DESCRIPTION:
CEDAR CREEK 2 66.0
END DESCRIPTION:
XS GIS Cut Line= 6
      3562693.21      10557550.8      3562995.31     10558136.76
      3563023.95     10558274.78      3563086.28     10558489.19
      3563042.88     10558928.43      3562946.38     10559092.13
#Sta/Elev= 30
  4259.5     473  4303.3  471.99  4333.5  471.92  4350.1  468.58  4372.2  468.44
  4377.8  470.49  4394.4  468.44    4400  470.81  4418.4  470.69  4576.1  467.12
  4675.6  461.98  4704.7  463.05  4743.4  460.12    4749  461.94  4765.5  458.97
  4771.1  460.53  4801.4  457.83  4876.1  457.28  4914.1  455.12  4978.4  451.78
  5002.4  448.09  5005.2  447.59  5008.4  448.09  5023.4  452.37  5197.7  455.01
  5365.9  460.49  5715.3  463.66  5726.3  463.95  5825.3  465.07  5914.4  465.72
#Mann= 14 ,-1 , 0
  4259.5      .1       0  4303.3     .08       0  4418.4      .1       0
  4576.1     .08       0  4675.6      .1       0  4801.4     .08       0
  4876.1      .1       0  4914.1     .08       0  5002.4     .07       0
  5008.4     .08       0  5197.7     .05       0  5715.3      .1       0
  5726.3     .08       0  5825.3     .05       0
Bank Sta=4978.4,5023.4
XS Rating Curve= 0 ,0
Exp/Cntr=0.3,0.1

Type RM Length L Ch R = 1 ,31660   ,214,214,214
BEGIN DESCRIPTION:
CEDAR CREEK 2 65.0
END DESCRIPTION:
XS GIS Cut Line= 6
      3562593.22     10557681.89      3562935.24     10558176.69
      3563022.04     10558515.23      3563009.89     10558796.48
      3562975.17     10558947.52      3562893.07     10559027.91
#Sta/Elev= 30
  4359.5  469.98  4438.5  469.06  4439.2  469.03  4494.2  468.32  4610.5  463.38
  4667.2  463.19  4694.2  461.51  4780.5   458.3  4825.4  457.67  4858.7  456.08
  4969.5  453.02  4976.6  451.72    4987  447.65  4994.4  445.68  4997.2  445.18
  5000.4  445.68  5002.9  448.56  5008.1  448.83  5018.3  451.34  5036.2  451.97
  5183.6  452.87  5306.2  458.09  5428.6  458.08  5567.3  462.46  5603.5  462.15
  5694.4   463.9  5742.3  463.17    5795  463.75  5839.5  464.78    5862  464.27
#Mann= 10 ,-1 , 0
  4359.5      .1       0  4438.5     .08       0  4439.2      .1       0
  4694.2     .08       0  4780.5      .1       0  4858.7     .08       0
  4994.4     .07       0  5000.4     .08       0    5795      .1       0
  5839.5     .08       0
Bank Sta=4976.6,5018.3
XS Rating Curve= 0 ,0
Exp/Cntr=0.3,0.1

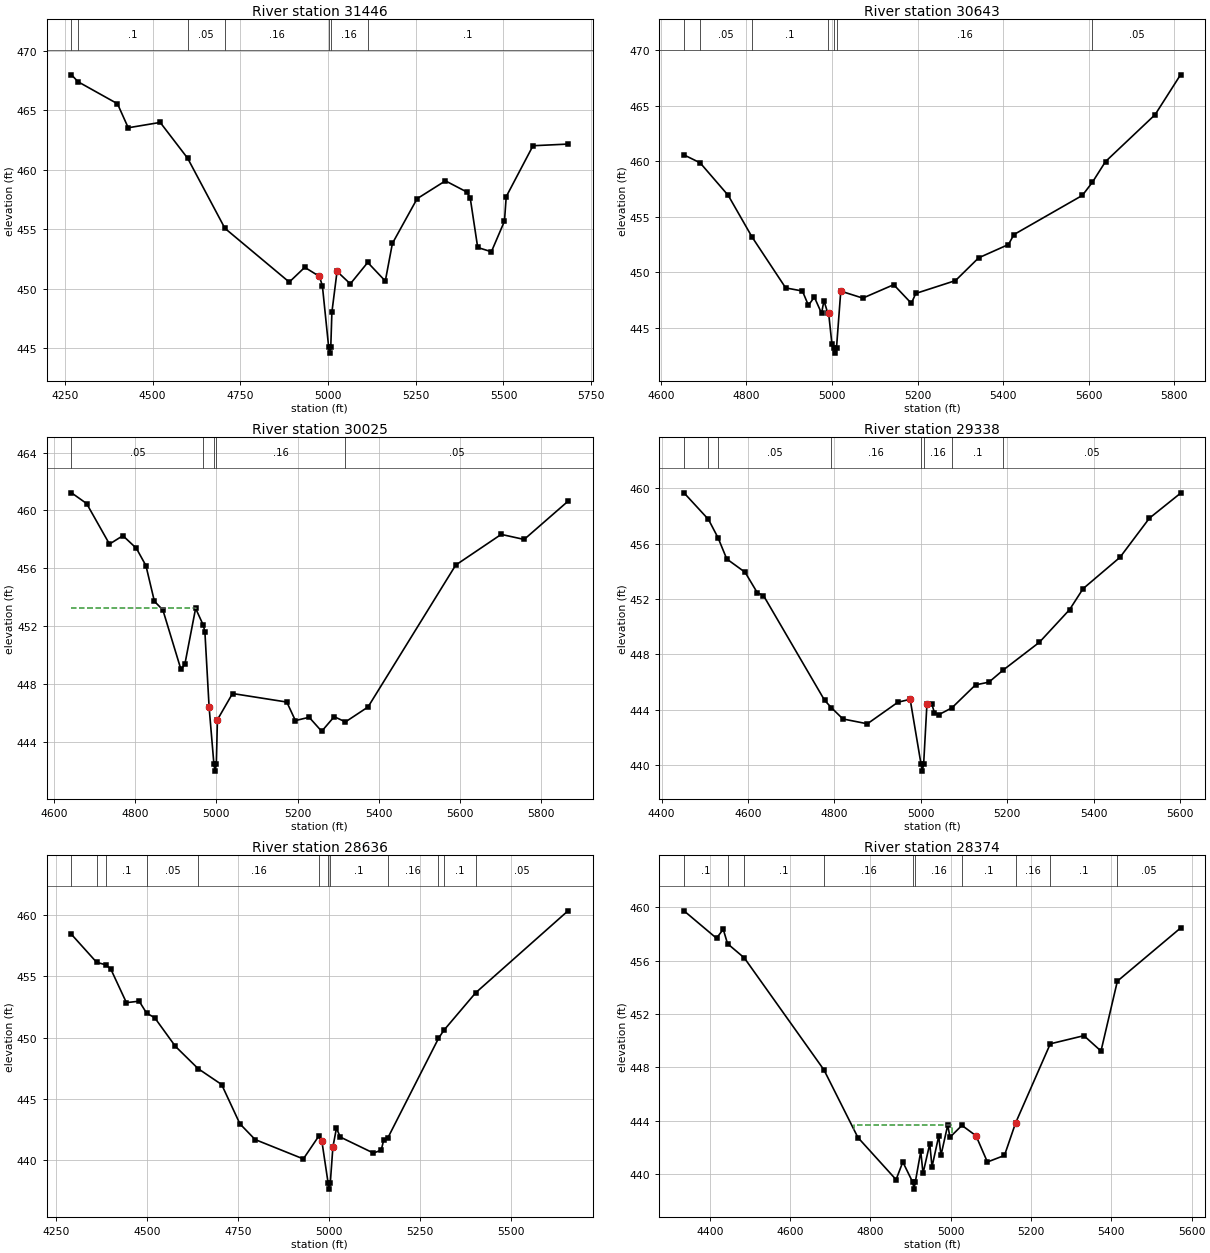
Type RM Length L Ch R = 1 ,31446   ,803,803,803
BEGIN DESCRIPTION:
CEDAR CREEK 2 64.0
END DESCRIPTION:
XS GIS Cut Line= 4
      3562489.49     10557708.84      3562683.94     10558233.15
      3562871.44     10558368.57      3562795.26     10558988.41
#Sta/Elev= 30
  4268.9  467.98  4287.5   467.4  4399.9  465.55  4430.6  463.53  4521.7  463.98
  4599.9  460.97  4706.1  455.08  4889.5  450.56  4933.6   451.8  4975.4  451.04
  4983.9  450.25  5001.8  445.09  5004.5  444.59  5007.8  445.09    5011  448.03
  5025.7  451.46  5063.5  450.41  5113.1  452.21  5163.2  450.65  5183.4  453.81
  5253.9  457.57  5334.5  459.07    5395  458.14  5405.1  457.65  5426.5  453.47
  5465.5  453.11  5502.8  455.68  5507.8  457.74  5584.1  462.02  5683.9  462.16
#Mann= 7 ,-1 , 0
  4268.9     .05       0  4287.5      .1       0  4599.9     .05       0
  4706.1     .16       0  5001.8     .07       0  5007.8     .16       0
  5113.1      .1       0
#XS Ineff= 2 , 0
                         5404.55          457.61
Permanent Ineff=
       F       F
Bank Sta=4975.4,5025.7
XS Rating Curve= 0 ,0
Exp/Cntr=0.3,0.1

Type RM Length L Ch R = 1 ,30643   ,618,618,618
BEGIN DESCRIPTION:
CEDAR CREEK 2 63.0
END DESCRIPTION:
XS GIS Cut Line= 3
      3562142.12     10558041.67      3562292.11     10558341.64
       3562492.1     10559141.64
#Sta/Elev= 30
  4654.3  460.58  4691.9  459.87  4757.7  456.93  4813.3  453.18  4891.9  448.59
    4931  448.31    4945  447.02  4958.9  447.76  4975.7   446.3  4981.3  447.44
  4990.3  446.31  4992.3  446.31    5000   443.5  5004.7  443.21  5007.5  442.71
  5010.7  443.21  5020.6   448.3  5072.1  447.67  5144.3  448.88  5185.5   447.2
  5195.8  448.09  5288.6  449.25  5342.7   451.3  5412.3   452.5  5425.2   453.4
    5585  456.93  5608.4  458.11  5639.1  459.98    5755  464.21  5814.3   467.8
#Mann= 7 ,-1 , 0
  4654.3      .1       0  4691.9     .05       0  4813.3      .1       0
  4990.3     .16       0  5004.7     .07       0  5010.7     .16       0
  5608.4     .05       0
Bank Sta=4992.3,5020.6
XS Rating Curve= 0 ,0
Exp/Cntr=0.3,0.1

Type RM Length L Ch R = 1 ,30025   ,687,687,687
BEGIN DESCRIPTION:
CEDAR CREEK 2 62.0
END DESCRIPTION:
XS GIS Cut Line= 4
      3561923.53     10557806.03      3561843.66     10558073.43
      3561784.64     10558330.37      3561942.11     10558991.68
#Sta/Elev= 30
  4643.3  461.22  4680.5  460.48  4736.8  457.68  4769.9  458.26    4803  457.39
  4826.6  456.19  4847.4  453.73  4868.3  453.13  4912.8  449.02  4922.4  449.38
  4948.9  453.24  4968.1  452.06  4971.8  451.59  4982.1  446.43  4993.9   442.5
  4996.7     442  4999.9   442.5  5002.6  445.55  5039.8  447.36  5173.4  446.77
  5194.6  445.49  5228.4  445.72  5259.3  444.75  5290.1  445.76  5317.8   445.4
  5373.4  446.43  5589.3  456.23  5701.3  458.35  5757.8     458  5865.8  460.64
#Mann= 5 ,-1 , 0
  4643.3     .05       0  4968.1     .16       0  4993.9     .07       0
  4999.9     .16       0  5317.8     .05       0
#XS Ineff= 2 , 0
            4950  453.27
Permanent Ineff=
       F       F
Bank Sta=4982.1,5002.6
XS Rating Curve= 0 ,0
Exp/Cntr=0.3,0.1

Type RM Length L Ch R = 1 ,29338   ,702,702,702
BEGIN DESCRIPTION:
CEDAR CREEK 2 60.0
END DESCRIPTION:
XS GIS Cut Line= 3
      3561742.11     10557641.64      3561342.11     10558041.64
      3560842.09     10558341.65
#Sta/Elev= 30
    4452  459.67  4508.6  457.75    4531  456.41    4551  454.89  4593.4  453.93
  4621.7  452.45  4635.9  452.25  4777.3  444.68  4793.2  444.14  4819.7  443.33
  4876.3  442.98    4947  444.54  4975.3  444.75  5000.5  440.06  5003.3  439.56
  5006.5  440.06  5014.2  444.44  5025.5  444.41  5031.3  443.79    5041  443.63
  5071.8  444.13  5126.5  445.79  5157.6  445.99    5190  446.85  5274.3  448.87
  5344.2  451.23  5375.3  452.74  5460.8  455.01  5528.9  457.84  5600.8  459.64
#Mann= 8 ,-1 , 0
    4452     .05       0  4508.6     .16       0    4531     .05       0
  4793.2     .16       0  5000.5     .07       0  5006.5     .16       0
  5071.8      .1       0    5190     .05       0
Bank Sta=4975.3,5014.2
XS Rating Curve= 0 ,0
Exp/Cntr=0.3,0.1

Type RM Length L Ch R = 1 ,28636   ,262,262,262
BEGIN DESCRIPTION:
CEDAR CREEK 2 59.0
END DESCRIPTION:
XS GIS Cut Line= 4
      3561499.89     10557146.37      3561055.47     10557538.71
      3560850.61     10557580.37      3560482.93     10558007.02
#Sta/Elev= 30
  4291.7  458.41  4360.7  456.14    4387  455.92    4400  455.57  4442.7  452.85
  4477.8  452.97  4498.1     452  4520.5  451.62  4577.4  449.29    4640  447.47
  4704.5  446.18  4754.7  442.98  4796.5   441.7  4929.1  440.12  4971.6  441.98
  4979.8  441.62  4997.2  438.16    5000  437.66  5003.2  438.16  5010.4  441.09
  5020.1  442.62  5030.8   441.9  5121.7   440.6  5143.2  440.83  5149.8  441.63
  5161.9  441.86  5300.7  449.94  5315.2  450.59  5403.1  453.66  5656.8  460.33
#Mann= 12 ,-1 , 0
  4291.7      .1       0  4360.7     .05       0    4387      .1       0
  4498.1     .05       0    4640     .16       0  4971.6      .1       0
  4997.2     .07       0  5003.2      .1       0  5161.9     .16       0
  5300.7     .05       0  5315.2      .1       0  5403.1     .05       0
Bank Sta=4979.8,5010.4
XS Rating Curve= 0 ,0
Exp/Cntr=0.3,0.1

Type RM Length L Ch R = 1 ,28374   ,163,163,163
BEGIN DESCRIPTION:
CEDAR CREEK 2 58.0
END DESCRIPTION:
XS GIS Cut Line= 3
      3561092.08     10556841.69      3560792.11     10557441.64
      3560392.07     10557841.67
#Sta/Elev= 30
  4335.8  459.72  4416.8  457.67  4433.6  458.34  4444.3  457.26    4486   456.2
  4684.4  447.82    4769  442.76    4864  439.61  4880.8  440.93  4905.7   439.4
  4908.5   438.9  4911.7   439.4  4925.5  441.72  4931.1  440.08  4947.9  442.29
  4953.5  440.57  4970.2  442.87  4975.8  441.43  4992.6  443.69  4998.2  442.78
    5028  443.67  5063.1  442.89  5091.4  440.93  5133.9  441.42  5161.5  443.84
    5248  449.77  5331.8  450.38  5374.3  449.23  5415.1  454.46  5572.3  458.43
#Mann= 10 ,-1 , 0
  4335.8      .1       0  4444.3     .05       0    4486      .1       0
  4684.4     .16       0  4905.7     .07       0  4911.7     .16       0
    5028      .1       0  5161.5     .16       0    5248      .1       0
  5415.1     .05       0
#XS Ineff= 1 ,-1
    4760 5003.41  443.67
Permanent Ineff=
       F
Bank Sta=5063.1,5161.5
XS Rating Curve= 0 ,0
Exp/Cntr=0.3,0.1

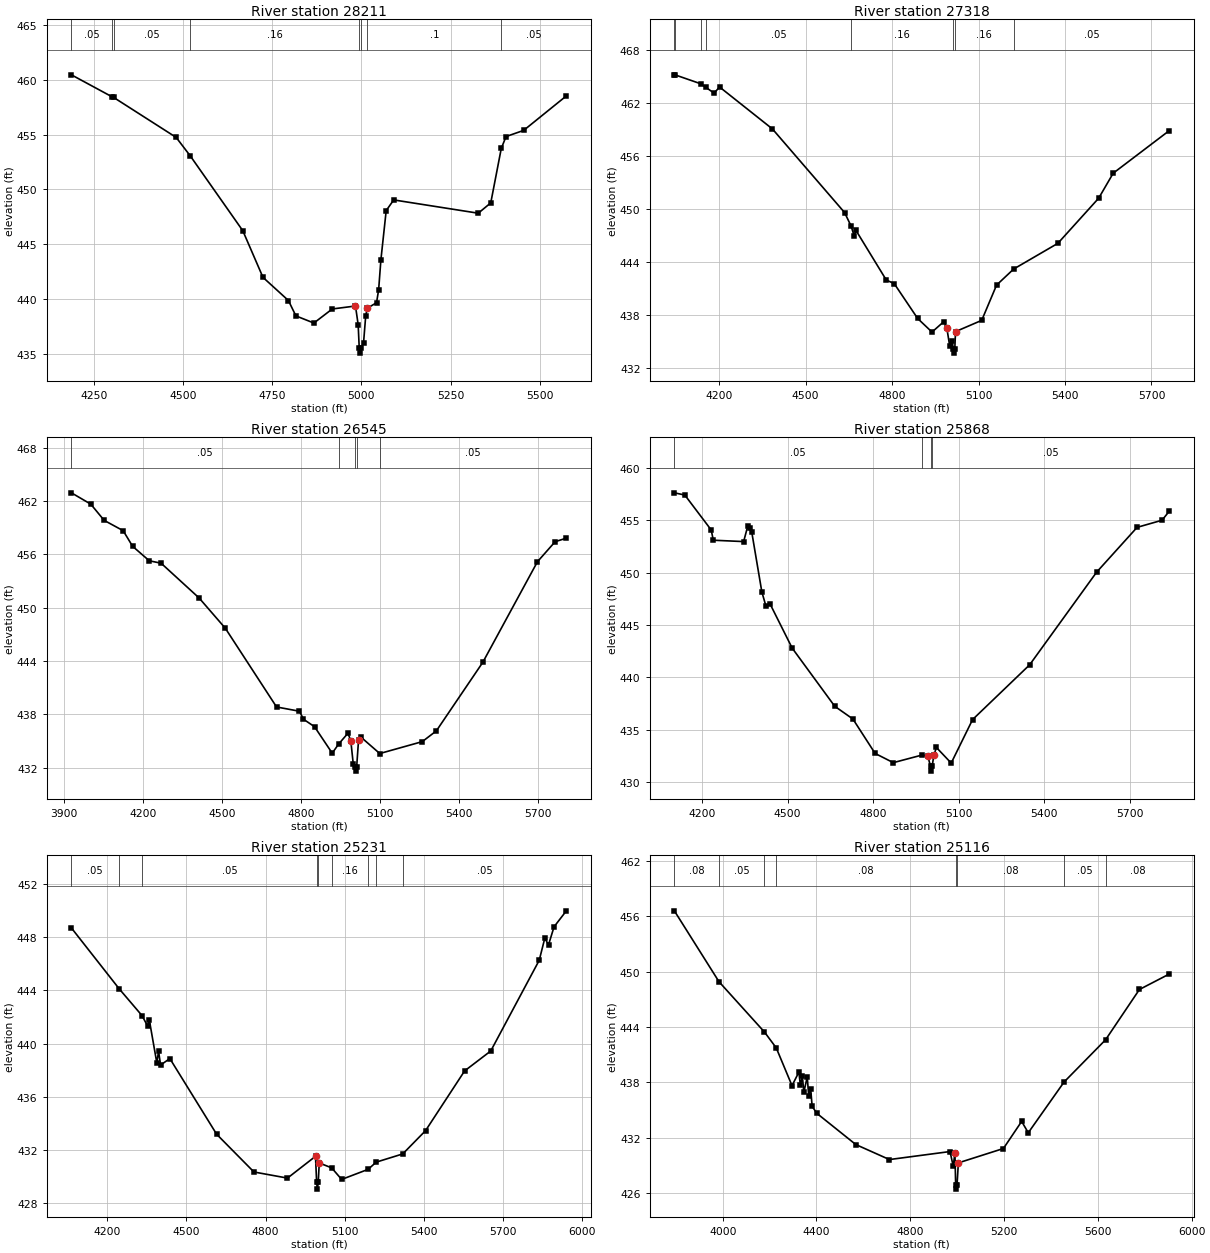
Type RM Length L Ch R = 1 ,28211   ,893,893,893
BEGIN DESCRIPTION:
CEDAR CREEK 2 57.0
END DESCRIPTION:
XS GIS Cut Line= 4
      3561117.99     10556687.98      3560736.02     10557226.21
      3560562.41     10557497.04      3560299.75     10557808.09
#Sta/Elev= 30
  4186.2  460.44  4300.2  458.44  4304.3  458.39  4480.2  454.74  4519.9  453.05
  4667.2  446.24  4723.7     442  4795.1  439.89  4816.1  438.49  4866.6  437.84
  4918.1  439.12  4983.3  439.39  4990.8   437.7  4993.8   435.6  4996.5   435.1
  4999.8   435.6    5006  436.06    5012  438.49  5016.5  439.19  5042.4  439.69
  5048.3  440.87  5054.6  443.59  5069.5  448.08  5090.6  449.05  5327.8  447.84
  5362.9  448.78  5392.4  453.74  5405.8  454.82  5455.2  455.38    5575  458.52
#Mann= 8 ,-1 , 0
  4186.2     .05       0  4300.2      .1       0  4304.3     .05       0
  4519.9     .16       0  4993.8     .07       0  4999.8     .16       0
  5016.5      .1       0  5392.4     .05       0
Bank Sta=4983.3,5016.5
XS Rating Curve= 0 ,0
Exp/Cntr=0.3,0.1

Type RM Length L Ch R = 1 ,27318   ,773,773,773
BEGIN DESCRIPTION:
CEDAR CREEK 2 56.0
END DESCRIPTION:
XS GIS Cut Line= 4
      3561364.54     10556372.03      3560611.02     10556590.79
      3560291.58     10556635.93      3559892.76     10557097.17
#Sta/Elev= 30
  4044.8  465.23  4046.9  465.23  4135.9  464.22  4154.1  463.81  4182.7  463.15
  4201.6  463.85    4385  459.09  4635.4   449.6  4658.3  448.04    4669   446.9
  4674.2  447.61  4780.1  441.94  4807.5  441.54  4888.9  437.58  4938.6  436.04
  4979.8  437.23  4989.9  436.53    5000  434.47  5009.6  434.99  5011.7  434.15
  5014.4  433.65  5017.7  434.15  5020.2  436.09  5111.1  437.37  5162.6  441.37
  5221.8  443.19  5375.3  446.11  5516.8  451.23  5567.3  454.07  5761.8   458.9
#Mann= 8 ,-1 , 0
  4044.8      .1       0  4046.9     .05       0  4135.9      .1       0
  4154.1     .05       0  4658.3     .16       0  5011.7     .07       0
  5017.7     .16       0  5221.8     .05       0
Bank Sta=4989.9,5020.2
XS Rating Curve= 0 ,0
Exp/Cntr=0.3,0.1

Type RM Length L Ch R = 1 ,26545   ,677,677,677
BEGIN DESCRIPTION:
CEDAR CREEK 2 54.0
END DESCRIPTION:
XS GIS Cut Line= 4
      3560447.84     10555295.63      3559909.64     10556101.21
      3559850.61     10556510.93      3559628.38     10556955.39
#Sta/Elev= 30
    3929  462.92  4002.4  461.65  4053.4  459.82  4125.5  458.66  4161.5   456.9
  4224.9  455.27  4269.6     455  4413.8  451.09  4513.5  447.68  4708.1  438.82
  4795.2  438.34  4810.3  437.44  4852.3   436.6  4919.5  433.62  4944.2  434.66
  4979.1  435.86    4990  435.04  4999.3  432.43  5006.4   432.1  5009.1   431.6
  5012.4   432.1  5019.5  435.09  5029.6   435.4  5100.1  433.58  5261.6  434.92
    5315  436.13  5491.5  443.85    5699  455.17  5766.1  457.42  5808.7  457.82
#Mann= 5 ,-1 , 0
    3929     .05       0  4944.2     .16       0  5006.4     .07       0
  5012.4     .16       0  5100.1     .05       0
Bank Sta=4990,5019.5
XS Rating Curve= 0 ,0
Exp/Cntr=0.3,0.1

Type RM Length L Ch R = 1 ,25868   ,637,637,637
BEGIN DESCRIPTION:
CEDAR CREEK 2 52.0
END DESCRIPTION:
XS GIS Cut Line= 4
      3560006.87     10555174.11      3559486.02     10555774.82
      3559245.63     10555882.83      3558923.52     10556476.22
#Sta/Elev= 30
  4103.6  457.63  4140.2  457.42  4232.7  454.08    4240   453.1  4346.3  452.97
  4360.6  454.44  4367.2  454.25  4374.8  453.87    4410  448.17  4424.2  446.82
  4438.5  447.03  4516.3  442.79  4665.4  437.23  4729.1  436.01  4806.9  432.72
  4870.6  431.84  4970.2  432.56  4990.7   432.5  5000.9  431.53  5003.7  431.03
  5006.9  431.53  5012.6  432.54  5021.6  433.29  5073.4   431.8  5148.4  435.96
  5348.2  441.19  5582.9  450.05  5724.6  454.33    5812  455.01  5837.4  455.88
#Mann= 4 ,-1 , 0
  4103.6     .05       0  4970.2     .16       0  5000.9     .07       0
  5006.9     .05       0
Bank Sta=4990.7,5012.6
XS Rating Curve= 0 ,0
Exp/Cntr=0.3,0.1

Type RM Length L Ch R = 1 ,25231   ,115,115,115
BEGIN DESCRIPTION:
CEDAR CREEK 2 51.01
END DESCRIPTION:
XS GIS Cut Line= 3
      3559781.55     10554683.94      3559121.84     10555253.37
      3558430.84     10555986.05
#Sta/Elev= 30
  4063.3   448.7  4244.6  444.12  4331.4   442.1  4352.4  441.32    4359  441.78
  4387.5  438.54  4394.1  439.42  4401.8  438.38  4436.9  438.87  4614.6  433.17
  4756.1  430.33  4883.4  429.87  4989.8  431.51  4994.1  429.54  4996.9  429.04
  5000.1  429.54    5004  431.01  5051.2  430.64    5089  429.77  5189.6  430.53
    5220  431.07  5320.9  431.69  5407.4  433.44  5555.8  437.94    5655  439.44
    5839  446.27  5860.1  447.93  5874.2  447.43  5895.3  448.79  5941.9  449.99
#Mann= 9 ,-1 , 0
  4063.3     .05       0  4244.6     .16       0  4331.4     .05       0
  4994.1     .03       0  5000.1     .05       0  5051.2     .16       0
  5189.6     .05       0    5220     .08       0  5320.9     .05       0
Bank Sta=4989.8,5004
XS Rating Curve= 0 ,0
Exp/Cntr=0.3,0.1

Type RM Length L Ch R = 1 ,25116   ,154,154,154
BEGIN DESCRIPTION:
CEDAR CREEK 2 51.0
END DESCRIPTION:
XS GIS Cut Line= 3
      3559701.68     10554249.94      3558913.51     10555333.23
      3558387.61     10555897.19
#Sta/Elev= 30
  3793.8  456.61  3984.3  448.91  4178.2  443.45  4228.4  441.73  4295.6  437.63
    4325  439.11  4331.2  437.65  4339.7  438.69  4345.9  436.91  4360.5  438.58
  4366.7  436.56  4375.2  437.29  4381.4  435.38  4402.3  434.61  4567.6  431.24
    4711  429.61  4969.5  430.48  4983.1  428.89  4990.3  430.31  4993.5   426.9
  4996.3   426.4  4999.5   426.9    5005  429.25  5197.2  430.81  5274.9  433.75
  5303.2  432.52  5455.9  438.03  5632.8  442.61  5777.1  448.07  5904.6  449.75
#Mann= 8 ,-1 , 0
  3793.8     .08       0  3984.3     .05       0  4178.2     .16       0
  4228.4     .08       0  4993.5     .07       0  4999.5     .08       0
  5455.9     .05       0  5632.8     .08       0
Bank Sta=4990.3,5005
XS Rating Curve= 0 ,0
Exp/Cntr=0.3,0.1

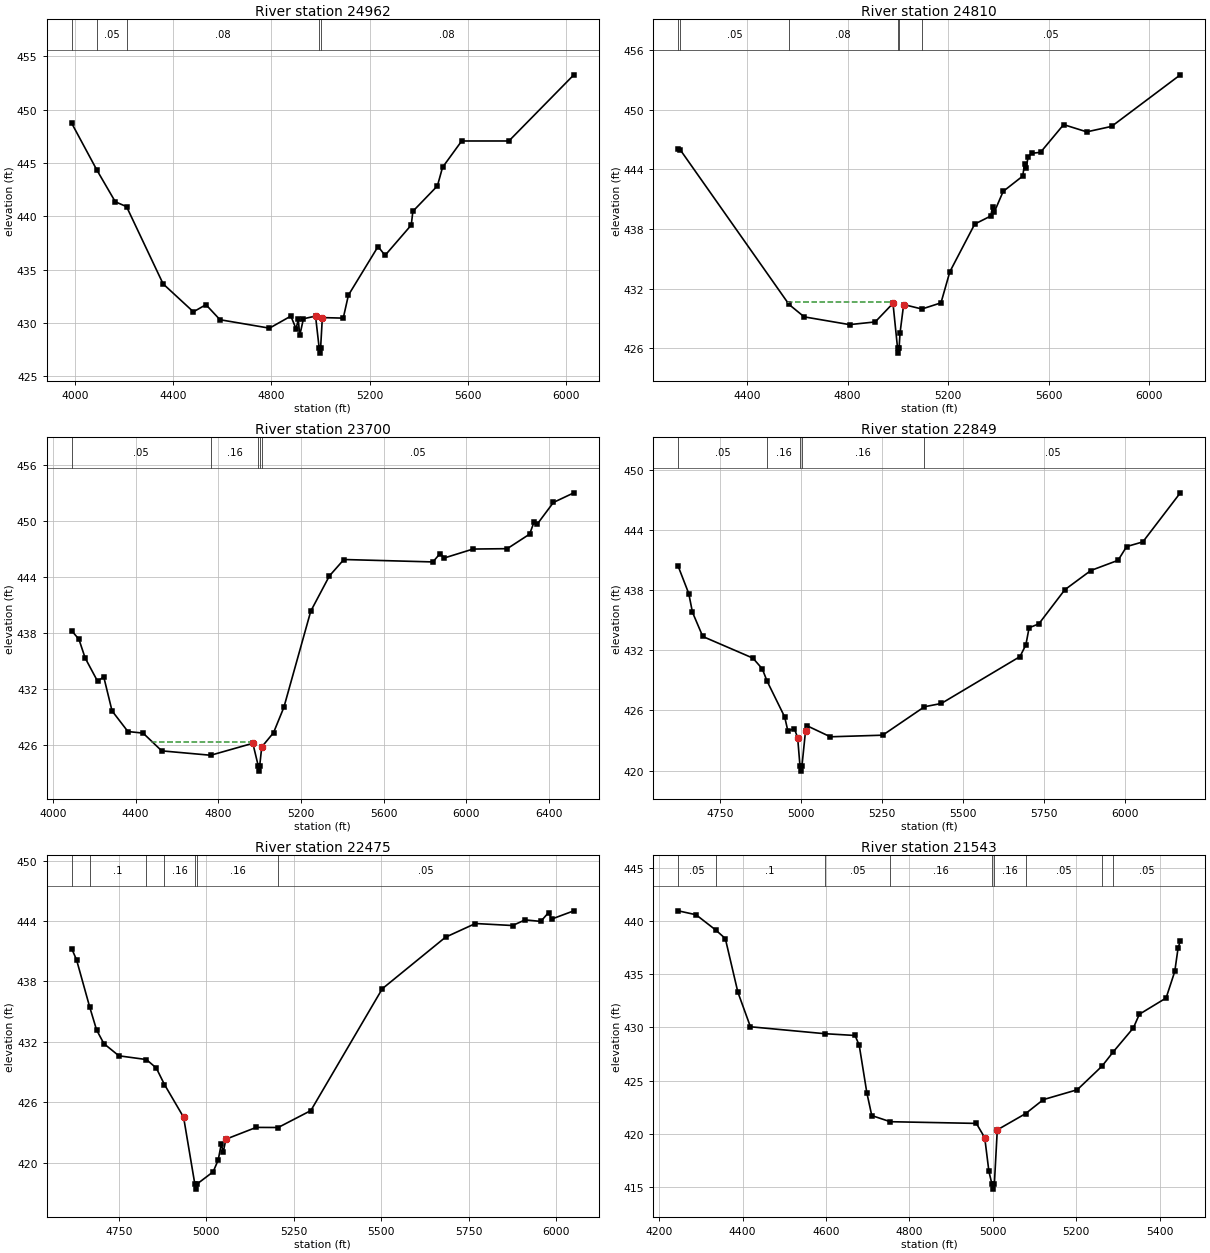
Type RM Length L Ch R = 1 ,24962   ,152,152,152
BEGIN DESCRIPTION:
CEDAR CREEK 2 49.0
END DESCRIPTION:
XS GIS Cut Line= 4
      3559521.13     10554274.23      3558972.54     10555097.12
      3558889.21     10555093.65      3558257.23     10555829.79
#Sta/Elev= 30
  3987.5   448.7  4090.5  444.29  4164.7  441.35  4210.3   440.9  4359.1  433.66
  4482.3  431.04  4533.4  431.71  4590.5   430.3  4791.8  429.51  4878.9  430.64
    4900  429.45    4909  430.33    4915  428.83    4930  430.39  4979.2  430.64
  4993.9  427.67  4996.7  427.17  4999.9  427.67  5006.9   430.5    5092  430.45
  5112.9   432.6  5233.6  437.16  5262.1  436.33  5368.6  439.17  5375.2  440.46
    5475  442.84  5495.9  444.58  5573.8  447.05  5765.8  447.05  6030.1  453.25
#Mann= 5 ,-1 , 0
  3987.5     .08       0  4090.5     .05       0  4210.3     .08       0
  4993.9     .07       0  4999.9     .08       0
Bank Sta=4979.2,5006.9
XS Rating Curve= 0 ,0
Exp/Cntr=0.3,0.1

Type RM Length L Ch R = 1 ,24810   ,1110,1110,1110
BEGIN DESCRIPTION:
CEDAR CREEK 2 49.01
END DESCRIPTION:
XS GIS Cut Line= 3
      3559472.54     10554246.42      3559024.62     10554920.04
       3558187.8      10555763.8
#Sta/Elev= 30
  4126.3  446.06  4134.1  445.97    4567   430.4  4627.3  429.15  4807.7  428.37
  4909.9  428.64  4980.6  430.51  4998.8     426  5001.5   425.5  5004.8     426
  5008.8  427.56    5023  430.39  5095.6  429.94  5171.5  430.56  5206.8  433.69
  5305.8  438.49  5369.5   439.3  5376.5  440.18  5383.6   439.7    5419  441.78
  5496.8  443.32  5503.8  444.54  5510.9  444.18    5518  445.25  5532.1  445.61
  5567.5  445.71  5659.4   448.5  5751.4  447.77  5850.3  448.32  6123.6  453.51
#Mann= 6 ,-1 , 0
  4126.3     .08       0  4134.1     .05       0    4567     .08       0
  4998.8     .07       0  5004.8     .08       0  5095.6     .05       0
#XS Ineff= 1 ,-1
 4563.92 4971.59  430.67
Permanent Ineff=
       F
Bank Sta=4980.6,5023
XS Rating Curve= 0 ,0
Exp/Cntr=0.3,0.1

Type RM Length L Ch R = 1 ,23700   ,851,851,851
BEGIN DESCRIPTION:
CEDAR CREEK 2 48.0
END DESCRIPTION:
XS GIS Cut Line= 3
      3558601.01     10553347.12      3558510.73     10555117.95
      3558148.31     10555663.98
#Sta/Elev= 30
  4091.5  438.25  4126.1  437.35  4156.1  435.35  4216.2  432.86  4246.2  433.32
  4286.3  429.68    4363  427.47  4436.5   427.3  4526.6   425.4  4763.4  424.93
  4967.2  426.21  4994.2  423.73    4997  423.23  5000.2  423.73  5010.4  425.82
  5067.3  427.34  5117.4  430.06  5247.5  440.36  5337.6  444.13  5407.7  445.89
  5838.3  445.63  5873.1  446.53  5894.2  446.06  6032.5  447.01  6197.9  447.05
  6306.2  448.61  6327.2  449.89  6342.3  449.66  6421.2     452    6520  453.03
#Mann= 5 ,-1 , 0
  4091.5     .05       0  4763.4     .16       0  4994.2     .07       0
  5000.2     .16       0  5010.4     .05       0
#XS Ineff= 1 ,-1
 4475.57 4959.66   426.4
Permanent Ineff=
       F
Bank Sta=4967.2,5010.4
XS Rating Curve= 0 ,0
Exp/Cntr=0.3,0.1

Type RM Length L Ch R = 1 ,22849   ,374,374,374
BEGIN DESCRIPTION:
CEDAR CREEK 2 46.0
END DESCRIPTION:
XS GIS Cut Line= 4
      3558092.11     10553641.63      3558003.39     10553854.68
      3558072.83     10554323.43      3558156.13     10555166.87
#Sta/Elev= 30
  4619.7  440.39  4652.2  437.68  4663.6  435.82  4695.5  433.39  4850.5  431.23
  4879.3  430.17  4894.5  428.92  4948.8  425.35  4958.6  423.96  4978.8  424.18
  4988.9  423.27  4996.1  420.44  4998.8  419.94  5002.1  420.44  5013.3  423.97
  5019.3  424.45    5090  423.37  5251.8  423.53  5380.9  426.37  5433.1   426.7
  5676.2  431.38  5694.4  432.55  5704.4  434.26  5734.5  434.65  5814.9  438.06
  5895.3  439.98  5979.5     441  6005.9  442.37  6056.1  442.84  6171.9  447.74
#Mann= 5 ,-1 , 0
  4619.7     .05       0  4894.5     .16       0  4996.1     .07       0
  5002.1     .16       0  5380.9     .05       0
Bank Sta=4988.9,5013.3
XS Rating Curve= 0 ,0
Exp/Cntr=0.3,0.1

Type RM Length L Ch R = 1 ,22475   ,932,932,932
BEGIN DESCRIPTION:
CEDAR CREEK 2 45.0
END DESCRIPTION:
XS GIS Cut Line= 5
       3558042.1     10553591.65      3557792.11     10553891.64
      3557492.11     10554291.64      3557332.94     10554495.68
      3557077.65     10554623.77
#Sta/Elev= 30
  4615.9  441.24  4629.6  440.14  4667.1  435.46  4686.8  433.18  4707.7  431.82
  4750.6  430.61  4829.2  430.24  4857.4   429.4  4880.8  427.76  4935.5  424.51
  4967.6  417.87  4970.4  417.37  4973.6  417.87  5019.9  419.09  5034.5  420.27
  5042.9  421.82  5049.1  421.09  5056.4  422.33  5142.9   423.5  5205.8  423.49
  5299.1  425.17  5503.3  437.27    5684  442.39  5769.5  443.75  5875.6  443.55
  5911.6  444.11  5956.3  443.96  5978.7  444.84  5987.3  444.19  6050.8  445.01
#Mann= 7 ,-1 , 0
  4615.9     .05       0  4667.1      .1       0  4829.2     .05       0
  4880.8     .16       0  4967.6     .07       0  4973.6     .16       0
  5205.8     .05       0
Bank Sta=4935.5,5056.4
XS Rating Curve= 0 ,0
Exp/Cntr=0.3,0.1

Type RM Length L Ch R = 1 ,21543   ,487,487,487
BEGIN DESCRIPTION:
CEDAR CREEK 2 43.0
END DESCRIPTION:
XS GIS Cut Line= 3
      3558034.66      10553389.4      3557092.05     10553466.68
      3556890.27     10553627.81
#Sta/Elev= 30
  4245.8  440.98  4288.5  440.61  4336.1  439.16  4358.7  438.37  4388.8  433.32
  4418.9  430.06  4596.7  429.41  4669.8  429.24  4679.8  428.32  4698.2  423.82
  4709.9   421.7  4754.1  421.12  4960.7  420.96  4980.8  419.61  4990.8  416.44
  4997.9  415.27  5000.6  414.77  5003.9  415.27  5010.9  420.35  5078.7  421.88
  5121.3   423.2  5202.7  424.13    5262  426.35  5288.8  427.69  5337.2  429.95
  5351.6  431.24  5415.7  432.77  5436.5  435.27  5444.5  437.49  5449.8  438.13
#Mann= 9 ,-1 , 0
  4245.8     .05       0  4336.1      .1       0  4596.7     .05       0
  4754.1     .16       0  4997.9     .07       0  5003.9     .16       0
  5078.7     .05       0    5262     .16       0  5288.8     .05       0
Bank Sta=4980.8,5010.9
XS Rating Curve= 0 ,0
Exp/Cntr=0.3,0.1