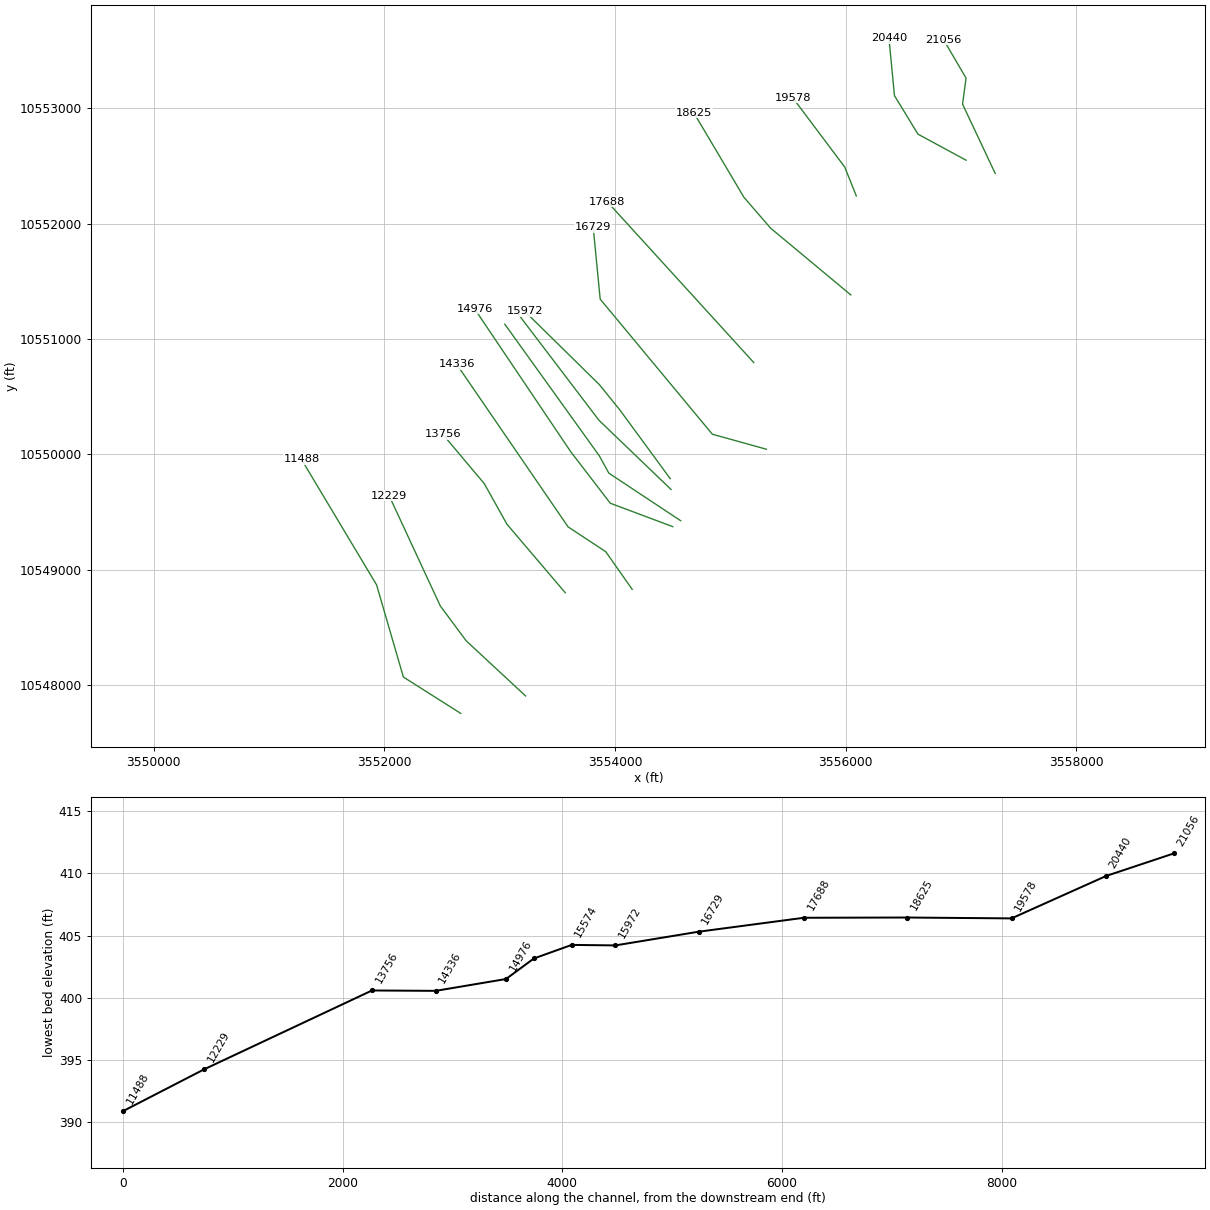
HEC-RAS study CEDAR CREEK 2.prj: CEDAR CREEK 2 Base Level Engineering

--- CEDAR CREEK 2.g01 (geometry) --- (continued)

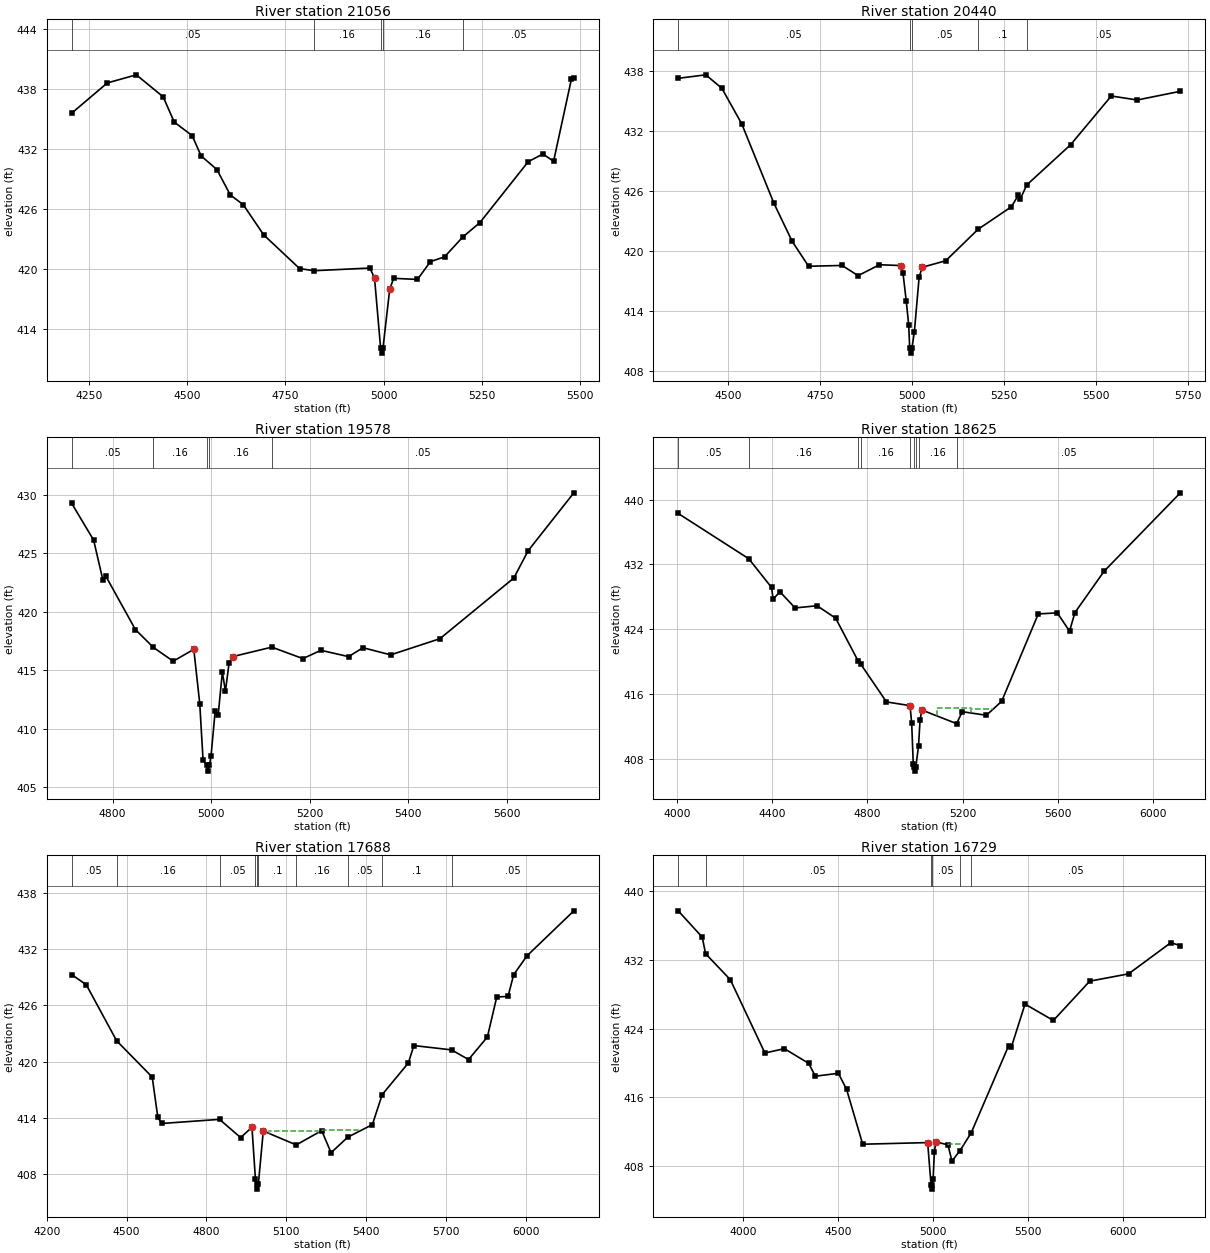
Type RM Length L Ch R = 1 ,21056   ,616,616,616
BEGIN DESCRIPTION:
CEDAR CREEK 2 42.0
END DESCRIPTION:
XS GIS Cut Line= 4
      3557296.44     10552436.33      3557013.34     10553037.55
      3557043.72     10553263.25      3556848.64     10553597.05
#Sta/Elev= 30
  4205.7   435.6  4296.2  438.62  4370.1  439.43  4438.5  437.23  4466.8   434.7
  4512.4  433.35  4535.2  431.32  4575.3  429.96  4609.5  427.42  4642.6  426.44
  4694.7  423.42  4785.9  420.06  4822.5  419.84  4965.2  420.11  4976.9   419.1
  4992.4   412.1  4995.2   411.6  4998.4   412.1  5015.6     418  5025.7  419.08
  5086.3  418.97  5119.3  420.75  5155.3  421.23  5201.9  423.22  5245.3  424.65
  5368.5  430.75  5405.7  431.51    5433  430.79  5478.3  438.98  5484.6  439.11
#Mann= 5 ,-1 , 0
  4205.7     .05       0  4822.5     .16       0  4992.4     .07       0
  4998.4     .16       0  5201.9     .05       0
Bank Sta=4976.9,5015.6
XS Rating Curve= 0 ,0
Exp/Cntr=0.3,0.1

Type RM Length L Ch R = 1 ,20440   ,862,862,862
BEGIN DESCRIPTION:
CEDAR CREEK 2 41.0
END DESCRIPTION:
XS GIS Cut Line= 4
      3557043.75     10552551.43      3556627.05     10552777.13
      3556423.06     10553111.34       3556375.5     10553608.53
#Sta/Elev= 30
  4364.2  437.31  4439.1  437.66  4482.8  436.31  4536.7  432.76  4624.5  424.78
    4674  420.98  4718.6  418.49  4809.6  418.57  4853.2  417.55  4911.3  418.64
  4969.4  418.56  4975.2  417.81    4984  415.02  4990.7  412.62  4993.5  410.29
  4996.3  409.79  4999.5  410.29  5006.1  411.91  5019.1  417.41  5027.5  418.39
  5091.4  419.04  5179.6   422.2  5270.1  424.45  5288.7  425.61  5293.7  425.19
  5311.6  426.63  5430.9  430.66  5541.4  435.54    5612  435.14  5729.1  436.01
#Mann= 5 ,-1 , 0
  4364.2     .05       0  4993.5     .03       0  4999.5     .05       0
  5179.6      .1       0  5311.6     .05       0
Bank Sta=4969.4,5027.5
XS Rating Curve= 0 ,0
Exp/Cntr=0.3,0.1

Type RM Length L Ch R = 1 ,19578   ,953,953,953
BEGIN DESCRIPTION:
CEDAR CREEK 2 39.0
END DESCRIPTION:
XS GIS Cut Line= 3
      3556092.09     10552241.68      3555992.11     10552491.64
      3555542.11     10553091.63
#Sta/Elev= 30
  4717.1  429.24  4761.5  426.11  4780.3   422.7  4785.7  423.07  4846.3  418.47
  4882.9  416.94    4923  415.77  4964.8  416.78  4976.9  412.15  4983.6  407.33
  4990.6  406.88  4993.4  406.38  4996.6  406.88  4999.9  407.71  5008.2  411.52
  5014.4  411.21  5022.8  414.85    5029  413.19  5036.3  415.58  5043.6  416.16
  5123.2  416.97  5186.3  415.99  5222.8   416.7    5279  416.16  5308.2  416.92
  5364.4  416.31  5464.4  417.69  5614.4  422.87  5643.6  425.21  5736.3  430.15
#Mann= 5 ,-1 , 0
  4717.1     .05       0  4882.9     .16       0  4990.6     .07       0
  4996.6     .16       0  5123.2     .05       0
Bank Sta=4964.8,5043.6
XS Rating Curve= 0 ,0
Exp/Cntr=0.3,0.1

Type RM Length L Ch R = 1 ,18625   ,937,937,937
BEGIN DESCRIPTION:
CEDAR CREEK 2 37.0
END DESCRIPTION:
XS GIS Cut Line= 4
      3556045.02     10551382.48      3555348.92      10551962.1
      3555117.97     10552229.68      3554683.96     10552962.29
#Sta/Elev= 30
  4004.5  438.28  4300.9  432.69  4396.9  429.14  4403.4   427.7  4432.1   428.6
  4495.9  426.61  4588.3  426.88  4666.4  425.34  4761.8     420    4772  419.66
  4879.9     415  4978.9  414.54    4986  412.36  4992.6   407.3  4997.3  406.95
    5000  406.45  5003.3  406.95  5014.8  409.58  5021.1  412.75  5028.6     414
  5174.6  412.32  5198.8  413.79  5299.9  413.35  5364.2  415.07  5518.2  425.87
  5598.2     426  5649.6  423.74  5672.3  426.04  5795.1  431.15  6115.3  440.83
#Mann= 9 ,-1 , 0
  4004.5     .05       0  4300.9     .16       0  4761.8      .1       0
    4772     .16       0  4978.9     .05       0  4997.3     .03       0
  5003.3     .05       0  5014.8     .16       0  5174.6     .05       0
#XS Ineff= 2 ,-1
 5093.75 5234.38  414.26  5235.8  5326.7  414.11
Permanent Ineff=
       F       F
Bank Sta=4978.9,5028.6
XS Rating Curve= 0 ,0
Exp/Cntr=0.3,0.1

Type RM Length L Ch R = 1 ,17688   ,959,959,959
BEGIN DESCRIPTION:
CEDAR CREEK 2 35.0
END DESCRIPTION:
XS GIS Cut Line= 2
      3555203.43     10550795.92      3553932.59     10552191.76
#Sta/Elev= 30
  4293.8  429.27  4348.3   428.2  4462.5  422.23  4596.3  418.36  4617.2   414.1
  4631.4  413.42  4849.3  413.86  4928.7  411.92  4971.3  413.02  4984.2  407.55
  4989.2  406.93    4992  406.43  4995.2  406.93  5013.9  412.62  5137.7  411.14
  5233.5  412.66  5268.6  410.31  5331.9  411.97    5424   413.3    5461   416.5
  5559.1  419.86  5580.1  421.72  5721.9  421.26  5785.5  420.23  5856.4  422.63
  5891.6  426.89  5934.1  426.96  5955.1  429.26  6005.1  431.27  6181.5  436.07
#Mann= 10 ,-1 , 0
  4293.8     .05       0  4462.5     .16       0  4849.3     .05       0
  4984.2      .1       0  4989.2     .07       0  4995.2      .1       0
  5137.7     .16       0  5331.9     .05       0    5461      .1       0
  5721.9     .05       0
#XS Ineff= 2 ,-1
 5036.93 5218.75  412.67 5232.95 5370.74  412.71
Permanent Ineff=
       F       F
Bank Sta=4971.3,5013.9
XS Rating Curve= 0 ,0
Exp/Cntr=0.3,0.1

Type RM Length L Ch R = 1 ,16729   ,757,757,757
BEGIN DESCRIPTION:
CEDAR CREEK 2 33.0
END DESCRIPTION:
XS GIS Cut Line= 4
      3555312.97     10550044.04      3554844.18     10550174.26
      3553871.96     10551346.14      3553811.19     10551971.19
#Sta/Elev= 30
  3661.4  437.72  3787.6  434.65  3804.9  432.73    3935   429.7  4116.6  421.16
  4218.8  421.67  4346.4  419.96  4381.6  418.46  4502.7   418.8  4545.7  416.92
  4630.3  410.54  4971.5  410.73  4989.3  405.81  4992.1  405.31  4995.3  405.81
  5000.2  406.48  5006.7  409.61  5014.5  410.82  5078.3  410.46  5099.1  408.57
  5141.4   409.8  5199.9  411.85  5397.3  422.03  5411.7  421.89  5482.9  426.86
  5631.8  424.95    5823  429.53  6026.8  430.38  6248.8  434.01  6298.6  433.67
#Mann= 6 ,-1 , 0
  3661.4     .16       0  3804.9     .05       0  4989.3     .03       0
  4995.3     .05       0  5141.4     .16       0  5199.9     .05       0
#XS Ineff= 1 ,-1
 5078.41 5163.64  410.52
Permanent Ineff=
       F
Bank Sta=4971.5,5014.5
XS Rating Curve= 0 ,0
Exp/Cntr=0.3,0.1

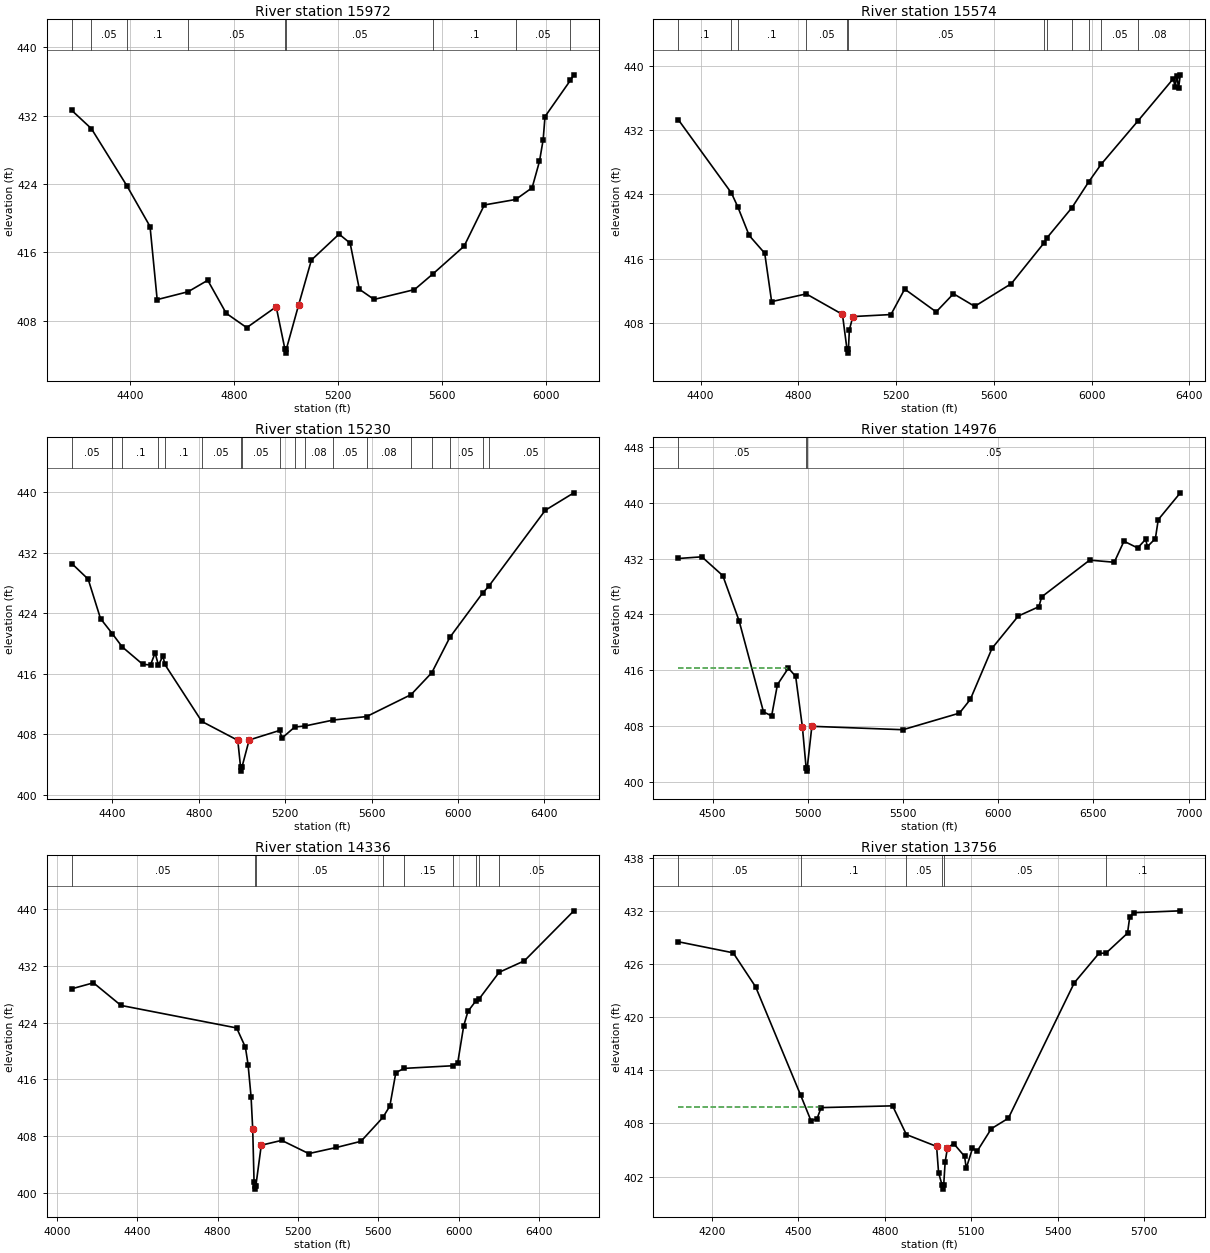
Type RM Length L Ch R = 1 ,15972   ,398,398,398
BEGIN DESCRIPTION:
CEDAR CREEK 2 32.0
END DESCRIPTION:
XS GIS Cut Line= 4
      3554479.07     10549788.72      3554041.58     10550385.93
       3553864.5     10550604.68      3553216.17      10551242.6
#Sta/Elev= 30
  4176.7   432.6  4252.3  430.46  4388.5  423.79  4477.8  419.02  4505.2  410.47
  4624.1  411.39  4699.7  412.73  4770.7  408.87  4849.7  407.19    4963  409.63
  4996.4  404.71  4999.1  404.21  5002.4  404.71  5048.9   409.8  5098.5   415.1
    5205  418.13  5247.5  417.07  5282.9  411.68  5339.5  410.49    5495  411.64
  5567.6  413.52  5685.9  416.72  5763.7  421.54  5884.3  422.18  5947.5  423.55
  5975.8  426.64  5989.9  429.16  5997.1  431.88  6094.4   436.1    6108  436.76
#Mann= 9 ,-1 , 0
  4176.7      .1       0  4252.3     .05       0  4388.5      .1       0
  4624.1     .05       0  4996.4     .03       0  5002.4     .05       0
  5567.6      .1       0  5884.3     .05       0  6094.4     .08       0
Bank Sta=4963,5048.9
XS Rating Curve= 0 ,0
Exp/Cntr=0.3,0.1

Type RM Length L Ch R = 1 ,15574   ,344,344,344
BEGIN DESCRIPTION:
CEDAR CREEK 2 31.0
END DESCRIPTION:
XS GIS Cut Line= 3
      3554486.04     10549694.94      3553861.02     10550295.65
      3553142.08     10551241.68
#Sta/Elev= 30
  4308.2  433.31  4525.6  424.19  4551.6  422.48  4598.6  418.89  4662.2  416.68
  4690.5  410.66  4832.1  411.62  4980.4  409.07  4998.8  404.75  5001.5  404.25
  5004.8  404.75  5008.7  407.15  5022.9   408.8  5178.9  409.05  5235.1  412.22
    5364  409.38  5434.8  411.64  5521.7  410.07  5671.8   412.9  5804.4  417.92
  5816.8  418.57  5919.7  422.35  5989.2   425.6  6039.3  427.75  6188.7   433.1
  6335.2  438.42  6341.4  437.35  6349.7  438.78    6356  437.18  6363.3  438.88
#Mann= 12 ,-1 , 0
  4308.2      .1       0  4525.6     .05       0  4551.6      .1       0
  4832.1     .05       0  4998.8     .03       0  5004.8     .05       0
  5804.4      .1       0  5816.8     .05       0  5919.7      .1       0
  5989.2     .08       0  6039.3     .05       0  6188.7     .08       0
Bank Sta=4980.4,5022.9
XS Rating Curve= 0 ,0
Exp/Cntr=0.3,0.1

Type RM Length L Ch R = 1 ,15230   ,254,254,254
BEGIN DESCRIPTION:
CEDAR CREEK 2 30.0
END DESCRIPTION:
XS GIS Cut Line= 4
      3554569.39      10549424.1      3553946.82     10549836.67
       3553864.5     10549986.62      3553045.05     10551128.99
#Sta/Elev= 30
  4212.5  430.57  4288.4   428.5  4345.5   423.3  4399.8  421.32    4446  419.56
    4541  417.26  4577.1  417.18  4598.2  418.77  4613.6  417.15  4634.3  418.36
  4643.4  417.24  4814.4  409.72  4980.8  407.23  4993.9  403.66  4996.7  403.16
  4999.9  403.66  5033.5  407.27  5174.5  408.53  5185.8  407.53  5244.3  408.98
  5291.9  409.12  5423.8  409.91  5576.8  410.36  5782.9  413.26    5879  416.16
  5962.4  420.82  6113.8  426.66    6142  427.55  6404.2   437.6  6536.3   439.9
#Mann= 18 ,-1 , 0
  4212.5     .05       0  4399.8     .08       0    4446      .1       0
  4613.6     .08       0  4643.4      .1       0  4814.4     .05       0
  4993.9     .03       0  4999.9     .05       0  5174.5     .08       0
  5244.3     .05       0  5291.9     .08       0  5423.8     .05       0
  5576.8     .08       0  5782.9     .05       0    5879     .08       0
  5962.4     .05       0  6113.8     .08       0    6142     .05       0
Bank Sta=4980.8,5033.5
XS Rating Curve= 0 ,0
Exp/Cntr=0.3,0.1

Type RM Length L Ch R = 1 ,14976   ,640,640,640
BEGIN DESCRIPTION:
CEDAR CREEK 2 28.0
END DESCRIPTION:
XS GIS Cut Line= 4
      3554501.33     10549372.37      3553959.64     10549575.51
      3553615.89     10550023.43      3552782.56       10551263.
#Sta/Elev= 30
  4319.8  432.01  4443.8  432.25  4553.9  429.55  4639.4  423.07  4767.5  410.01
  4810.3  409.43  4840.8  413.92  4898.3  416.29  4936.5   415.1  4971.8  407.86
  4991.3  402.01    4994  401.51  4997.3  402.01  5021.6  407.94  5499.8  407.45
  5796.7  409.83  5853.8   411.8  5967.8  419.13  6105.7  423.76  6213.7  425.09
  6228.7  426.51  6480.7  431.78  6609.7  431.47  6660.7  434.49  6732.7  433.52
  6774.7  434.77  6783.7  433.71  6825.7  434.87  6840.7  437.58  6956.6  441.43
#Mann= 3 ,-1 , 0
  4319.8     .05       0  4991.3     .03       0  4997.3     .05       0
#XS Ineff= 2 , 0
         4891.48  416.33
Permanent Ineff=
       F       F
Bank Sta=4971.8,5021.6
XS Rating Curve= 0 ,0
Exp/Cntr=0.3,0.1

Type RM Length L Ch R = 1 ,14336   ,580,580,580
BEGIN DESCRIPTION:
CEDAR CREEK 2 29.0
END DESCRIPTION:
XS GIS Cut Line= 4
      3554149.33     10548828.74      3553920.14     10549155.16
      3553593.75     10549370.44      3552628.46     10550780.19
#Sta/Elev= 30
  4074.3  428.75  4182.1  429.59    4319  426.41  4894.7  423.24  4938.3  420.53
  4951.6  418.09  4966.5  413.55  4974.7  409.02  4981.4  401.55  4984.5  401.06
  4987.2  400.56  4990.5  401.06  5017.3  406.74  5118.9  407.42  5253.5  405.56
    5391  406.42  5513.5  407.29  5622.2  410.64  5657.1  412.25  5686.9  416.95
  5727.9  417.55  5969.5  417.92  5994.9  418.35  6024.7  423.54  6045.7  425.57
  6085.3  427.05  6099.4  427.25    6201  431.07  6326.7  432.69  6572.7  439.72
#Mann= 9 ,-1 , 0
  4074.3     .05       0  4984.5     .03       0  4990.5     .05       0
  5622.2      .1       0  5727.9     .15       0  5969.5      .1       0
  6085.3     .05       0  6099.4      .1       0    6201     .05       0
Bank Sta=4974.7,5017.3
XS Rating Curve= 0 ,0
Exp/Cntr=0.3,0.1

Type RM Length L Ch R = 1 ,13756   ,1527,1527,1527
BEGIN DESCRIPTION:
CEDAR CREEK 2 27.0
END DESCRIPTION:
XS GIS Cut Line= 4
      3553569.03     10548799.44       3553063.8     10549393.22
      3552866.91     10549746.03      3552506.79     10550174.14
#Sta/Elev= 30
    4083  428.51  4273.7  427.26  4351.7  423.42  4507.8  411.21  4543.9  408.31
  4564.7  408.52    4579  409.79  4827.2  409.99    4875  406.75    4980  405.41
  4986.8  402.45  4998.7  401.09  5001.5  400.59  5004.7  401.09  5009.7  403.67
  5017.7  405.24  5039.4  405.73  5077.1  404.29  5082.9  402.95  5104.6  405.19
  5120.6  404.86    5170  407.41  5229.1  408.59  5458.1  423.88  5543.9  427.21
  5567.9  427.22  5642.8  429.48  5650.6  431.33  5664.9  431.79  5826.1     432
#Mann= 6 ,-1 , 0
    4083     .05       0  4507.8      .1       0    4875     .05       0
  4998.7     .03       0  5004.7     .05       0  5567.9      .1       0
#XS Ineff= 2 , 0
         4580.68  409.81
Permanent Ineff=
       F       F
Bank Sta=4980,5017.7
XS Rating Curve= 0 ,0
Exp/Cntr=0.3,0.1

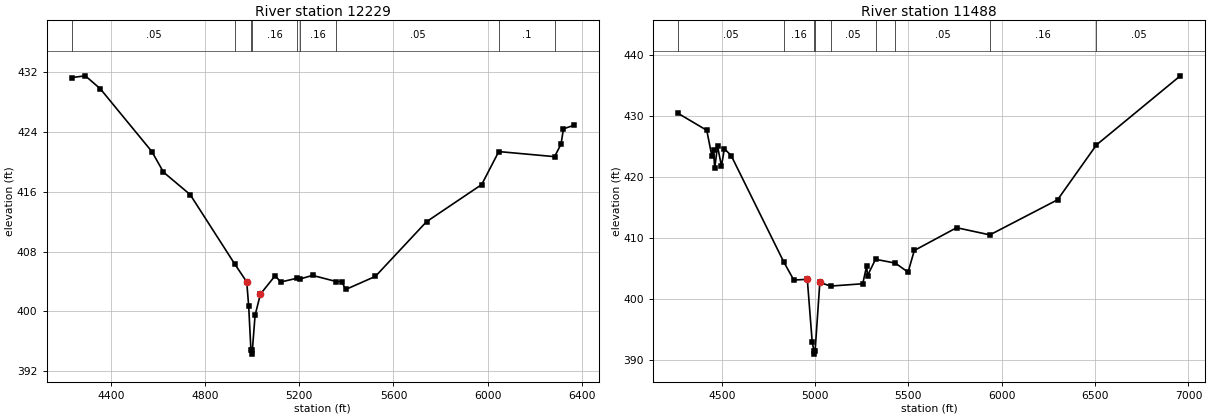
Type RM Length L Ch R = 1 ,12229   ,741,741,741
BEGIN DESCRIPTION:
CEDAR CREEK 2 24.0
END DESCRIPTION:
XS GIS Cut Line= 4
      3553225.25     10547903.64      3552709.64      10548382.8
      3552485.68     10548684.89      3552042.11     10549641.63
#Sta/Elev= 30
  4232.4  431.32    4290  431.55  4353.5  429.82  4572.9   421.4  4622.3  418.64
  4735.6  415.64  4926.1  406.29  4976.3  403.94  4984.6  400.65  4994.1  394.76
  4996.9  394.26  5000.1  394.76  5011.7  399.46  5034.4   402.3  5097.3  404.78
  5120.3  403.92  5188.8  404.42  5200.8  404.31  5255.9  404.81  5356.5  403.99
  5380.3  403.97  5396.9  402.92  5523.3  404.68  5740.5     412  5975.1  416.98
  6047.7   421.4  6285.1  420.72  6312.4   422.4  6322.8  424.45  6366.9  424.92
#Mann= 9 ,-1 , 0
  4232.4     .05       0  4926.1     .16       0  4994.1     .07       0
  5000.1     .16       0  5188.8     .05       0  5200.8     .16       0
  5356.5     .05       0  6047.7      .1       0  6285.1     .05       0
Bank Sta=4976.3,5034.4
XS Rating Curve= 0 ,0
Exp/Cntr=0.3,0.1

Type RM Length L Ch R = 1 ,11488   ,1209,1209,1209
BEGIN DESCRIPTION:
CEDAR CREEK 2 22.0
END DESCRIPTION:
XS GIS Cut Line= 4
      3552662.75      10547752.6      3552165.71     10548068.04
      3551933.59     10548867.18      3551282.57      10549955.7
#Sta/Elev= 30
  4267.2  430.43    4420  427.66  4447.1  423.46  4456.5  424.39  4462.4  421.39
  4477.6  425.06  4498.8  421.77  4514.1  424.63  4550.5  423.52  4832.3  406.04
  4886.2  403.06  4958.5  403.18  4984.6  392.94  4994.2  391.39    4997  390.89
  5000.2  391.39  5025.6  402.66  5083.2  402.07  5255.3  402.45    5276  405.32
  5281.2   403.8  5323.9  406.47  5430.5  405.84  5498.1  404.35  5531.7  407.92
  5758.2  411.66  5936.5  410.48    6299  416.25  6507.2  425.26  6956.4  436.61
#Mann= 9 ,-1 , 0
  4267.2     .05       0  4832.3     .16       0  4994.2     .07       0
  5000.2     .16       0  5083.2     .05       0  5323.9      .1       0
  5430.5     .05       0  5936.5     .16       0  6507.2     .05       0
Bank Sta=4958.5,5025.6
XS Rating Curve= 0 ,0
Exp/Cntr=0.3,0.1