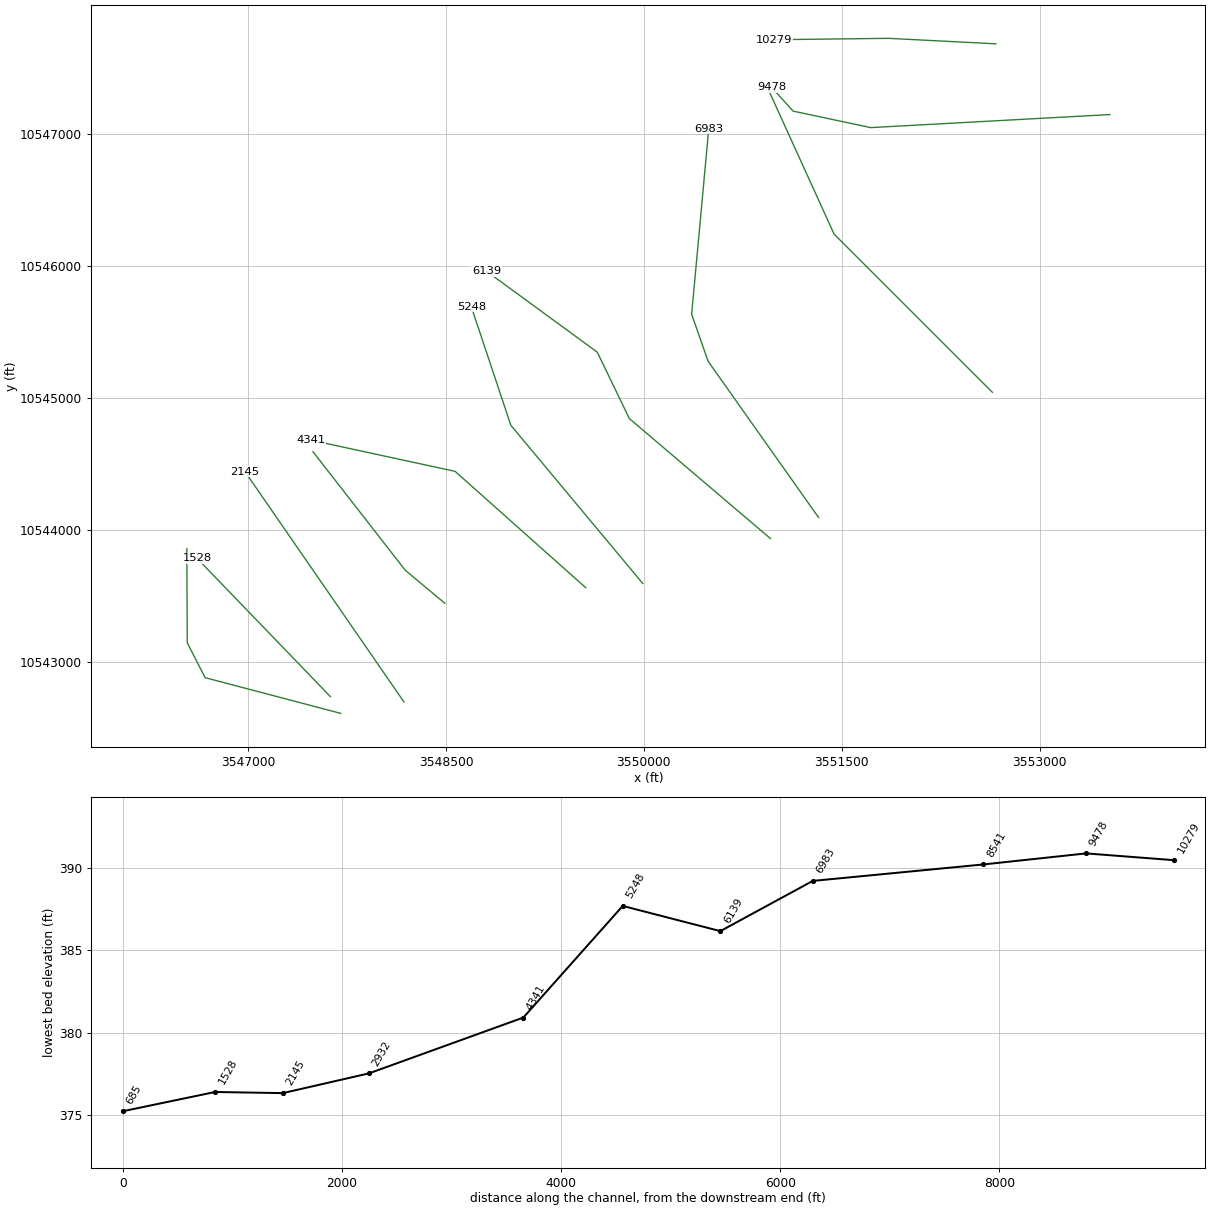
HEC-RAS study CEDAR CREEK 2.prj: CEDAR CREEK 2 Base Level Engineering

--- CEDAR CREEK 2.g01 (geometry) --- (continued)

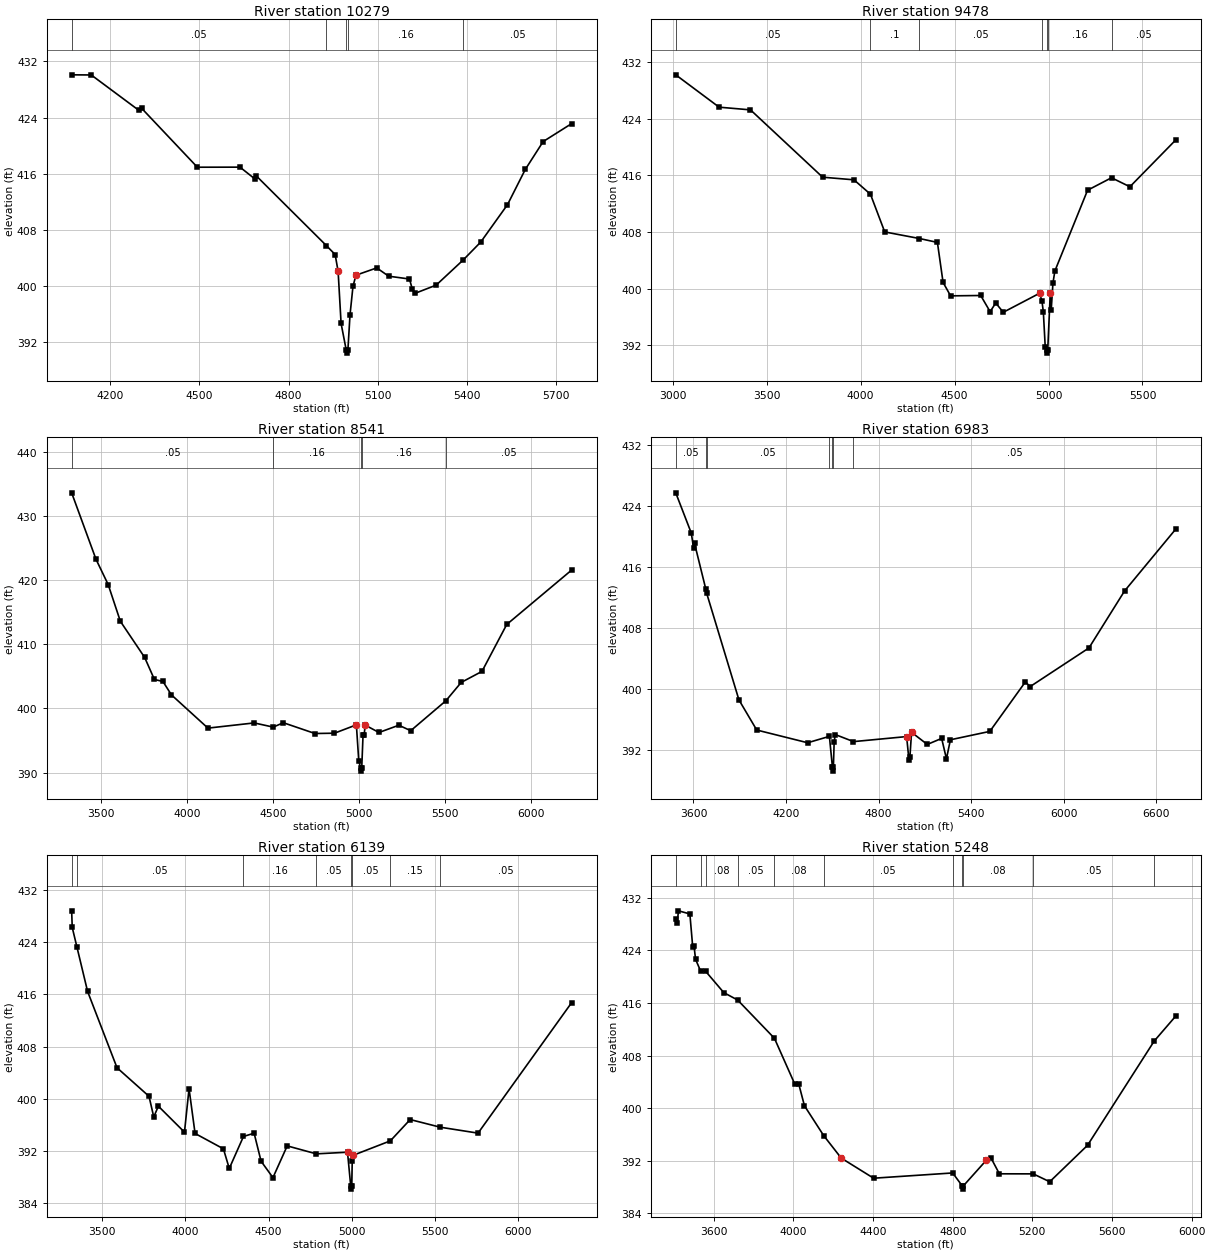
Type RM Length L Ch R = 1 ,10279   ,801,801,801
BEGIN DESCRIPTION:
CEDAR CREEK 2 20.0
END DESCRIPTION:
XS GIS Cut Line= 3
      3552667.97     10547684.89      3551855.47     10547726.55
       3550986.4     10547716.14
#Sta/Elev= 30
  4069.8  430.09  4135.8  430.07  4295.2  425.06    4306   425.3  4492.9  416.94
  4636.4  416.95  4685.7   415.3  4690.7  415.73  4927.5  405.77  4956.7  404.51
  4966.7  402.11  4976.7   394.7  4993.7  390.98  4996.5  390.48  4999.7  390.98
  5006.7  395.92  5016.7  399.98  5026.7  401.57  5096.7  402.61  5136.8  401.43
  5206.8  401.03  5216.8  399.54  5226.8  399.01  5296.8  400.16  5387.5  403.73
  5446.8  406.29  5536.8  411.61  5596.8  416.63  5656.8  420.59  5752.5  423.14
#Mann= 5 ,-1 , 0
  4069.8     .05       0  4927.5     .16       0  4993.7     .07       0
  4999.7     .16       0  5387.5     .05       0
Bank Sta=4966.7,5026.7
XS Rating Curve= 0 ,0
Exp/Cntr=0.3,0.1

Type RM Length L Ch R = 1 ,9478    ,937,937,937
BEGIN DESCRIPTION:
CEDAR CREEK 2 18.0
END DESCRIPTION:
XS GIS Cut Line= 5
      3553532.55     10547148.43      3551720.05     10547049.47
      3551131.51     10547174.47      3550985.68     10547335.93
       3550970.1      10547356.7
#Sta/Elev= 30
  3016.2   430.2    3247  425.63    3414  425.25  3797.8  415.74  3964.6  415.37
  4052.3  413.34  4128.3  408.01  4312.8  407.08  4408.7  406.53  4438.8  400.88
  4478.8  398.98  4639.1  399.03  4689.1  396.75  4719.2  397.97  4759.2  396.66
    4952  399.34  4964.7   398.3  4972.4  396.74  4982.6  391.71  4989.9  391.39
  4992.6  390.89  4995.9  391.39  5009.3  399.38  5014.4  397.01  5023.5  400.77
  5033.8  402.49  5207.8   413.9  5335.2  415.66  5433.1  414.39  5676.6  420.99
#Mann= 7 ,-1 , 0
  3016.2     .05       0  4052.3      .1       0  4312.8     .05       0
  4964.7     .16       0  4989.9     .07       0  4995.9     .16       0
  5335.2     .05       0
Bank Sta=4952,5009.3
XS Rating Curve= 0 ,0
Exp/Cntr=0.3,0.1

Type RM Length L Ch R = 1 ,8541    ,1558,1558,1558
BEGIN DESCRIPTION:
CEDAR CREEK 2 17.0
END DESCRIPTION:
XS GIS Cut Line= 3
      3552642.12     10545041.62      3551442.11     10546241.64
       3550942.1     10547341.65
#Sta/Elev= 30
  3330.1  433.58  3471.5  423.23  3542.3  419.29    3613  413.57  3754.4  407.93
    3811   404.5  3860.5  404.19    3910   402.1  4122.1  396.92  4390.8  397.73
  4501.4  397.08  4560.5  397.76  4744.3  396.08  4857.5  396.13  4984.8  397.43
  4998.9  391.74    5010  390.72  5012.8  390.22    5016  390.72  5023.6  395.86
  5029.9  395.86    5036  397.39  5116.2  396.24  5231.5  397.37  5300.7  396.52
  5504.9  401.18    5594  404.04  5714.8  405.76  5858.7  413.07  6235.5  421.54
#Mann= 5 ,-1 , 0
  3330.1     .05       0  4501.4     .16       0    5010     .07       0
    5016     .16       0  5504.9     .05       0
Bank Sta=4984.8,5036
XS Rating Curve= 0 ,0
Exp/Cntr=0.3,0.1

Type RM Length L Ch R = 1 ,6983    ,844,844,844
BEGIN DESCRIPTION:
CEDAR CREEK 2 14.0
END DESCRIPTION:
XS GIS Cut Line= 4
      3551324.25     10544092.83      3550487.41      10545276.9
      3550362.41     10545634.54      3550492.11     10547041.69
#Sta/Elev= 30
  3485.1  425.71  3585.9  420.43  3600.7  418.48  3606.8  419.09  3680.3  413.06
  3685.5  412.55  3894.9  398.56  4010.2  394.61  4340.6  392.94  4481.5  393.78
  4501.3  389.72    4504  389.22  4507.3  389.72  4512.3  392.99  4519.1  394.02
  4637.8  393.09  4982.4  393.75  4997.4  390.69  5003.6  391.05  5014.2  394.31
  5116.3  392.72  5209.5  393.51  5240.5  390.83  5266.3  393.33  5521.9  394.43
  5752.8  400.93    5783   400.3  6164.6  405.37  6395.6  412.84    6727  420.94
#Mann= 7 ,-1 , 0
  3485.1     .05       0  3680.3     .08       0  3685.5     .05       0
  4481.5     .16       0  4501.3     .03       0  4507.3     .16       0
  4637.8     .05       0
Bank Sta=4982.4,5014.2
XS Rating Curve= 0 ,0
Exp/Cntr=0.3,0.1

Type RM Length L Ch R = 1 ,6139    ,891,891,891
BEGIN DESCRIPTION:
CEDAR CREEK 2 12.0
END DESCRIPTION:
XS GIS Cut Line= 4
      3550958.64      10543933.6      3549890.19     10544842.87
      3549647.14     10545346.34      3548807.02     10545960.81
#Sta/Elev= 30
  3317.4  428.77  3320.8  426.23  3349.7  423.16    3413  416.44  3589.8  404.75
    3782  400.38  3810.6  397.21  3838.1  398.87    3995  394.89  4022.5  401.54
  4058.7  394.69  4228.9  392.34  4264.1  389.33  4349.4  394.23  4413.4  394.73
  4455.2  390.44  4526.5  387.93  4612.2  392.79  4786.8  391.57  4974.4  391.82
  4993.6  386.67  4996.4  386.17  4999.6  386.67  5002.8   390.4  5008.4  391.35
  5231.8  393.56  5350.8  396.82  5531.2  395.65  5758.5  394.74  6320.3   414.7
#Mann= 8 ,-1 , 0
  3317.4      .1       0  3349.7     .05       0  4349.4     .16       0
  4786.8     .05       0  4993.6     .03       0  4999.6     .05       0
  5231.8     .15       0  5531.2     .05       0
Bank Sta=4974.4,5008.4
XS Rating Curve= 0 ,0
Exp/Cntr=0.3,0.1

Type RM Length L Ch R = 1 ,5248    ,907,907,907
BEGIN DESCRIPTION:
CEDAR CREEK 2 10.0
END DESCRIPTION:
XS GIS Cut Line= 3
      3549992.08     10543591.67      3548992.11     10544791.64
       3548692.1     10545691.65
#Sta/Elev= 30
    3409  428.74  3416.1  428.12  3422.6  430.02  3479.9  429.55  3494.2  424.55
  3500.7   424.7  3508.5  422.65  3533.6  420.88  3558.7  420.84  3650.4  417.58
  3719.7  416.46  3904.6  410.64  4005.8  403.74  4026.6  403.71  4055.3  400.38
  4151.8  395.85  4240.1  392.42  4402.8  389.36  4799.8  390.16  4847.6   388.2
  4850.4   387.7  4853.6   388.2  4967.8  392.06  4992.1  392.45  5034.3  390.03
  5204.3  390.02  5287.2  388.82    5477  394.36    5812  410.22  5919.7     414
#Mann= 11 ,-1 , 0
    3409     .08       0  3533.6      .1       0  3558.7     .08       0
  3719.7     .05       0  3904.6     .08       0  4151.8     .05       0
  4799.8     .08       0  4847.6     .07       0  4853.6     .08       0
  5204.3     .05       0    5812     .08       0
Bank Sta=4240.1,4967.8
XS Rating Curve= 0 ,0
Exp/Cntr=0.3,0.1

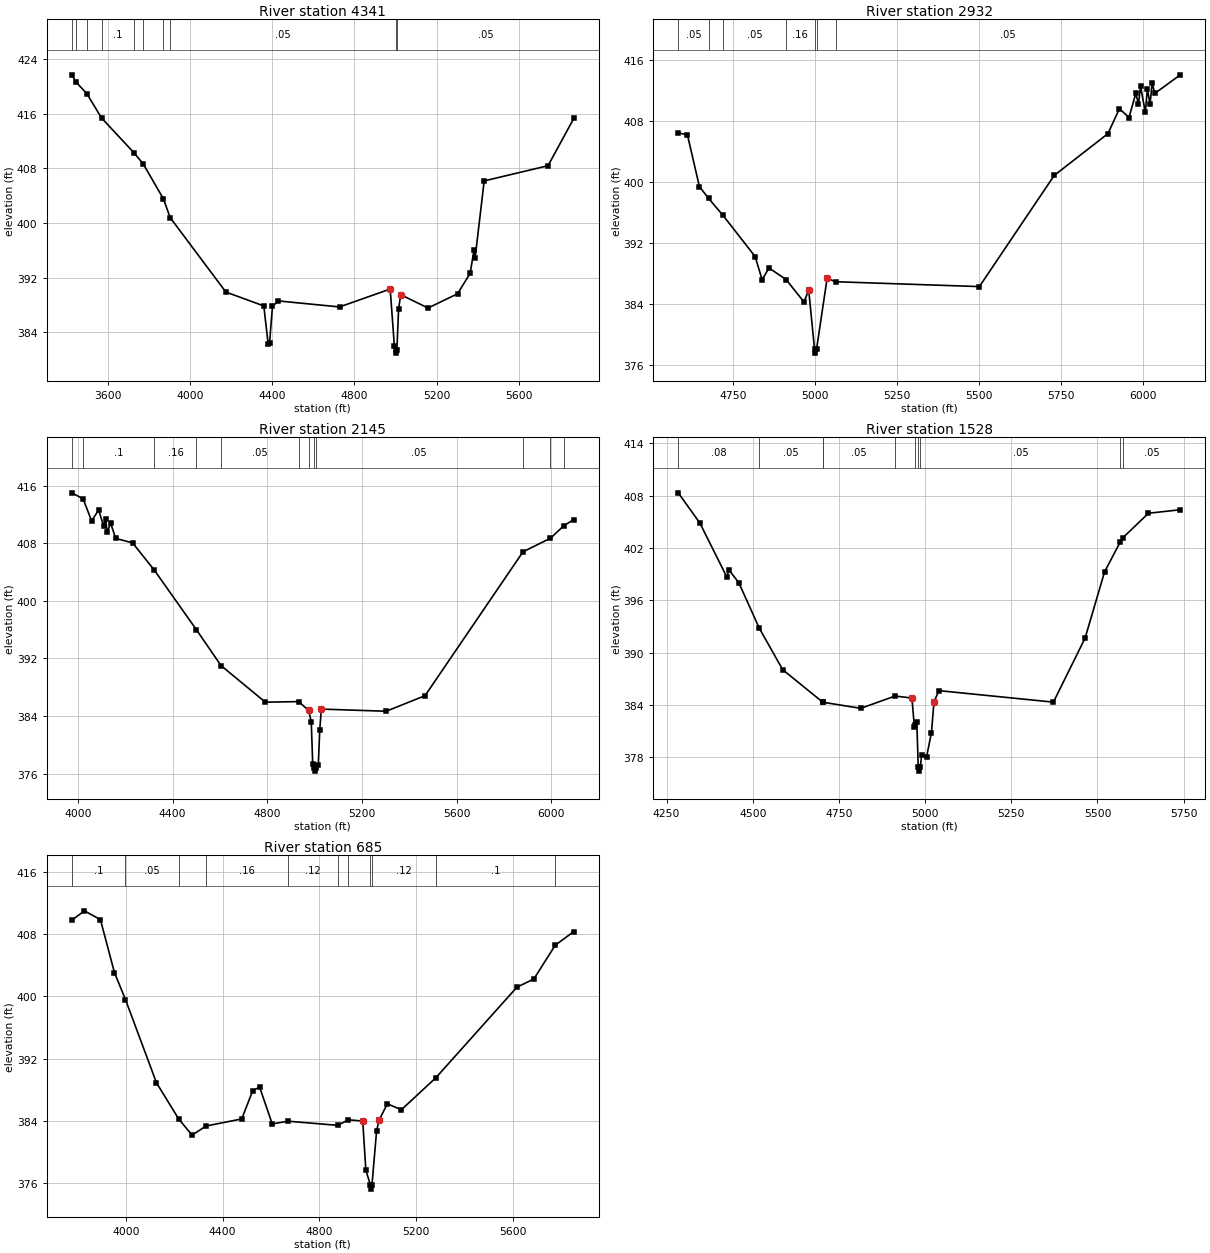
Type RM Length L Ch R = 1 ,4341    ,1409,1409,1409
BEGIN DESCRIPTION:
CEDAR CREEK 2 8.0
END DESCRIPTION:
XS GIS Cut Line= 3
      3549559.16     10543560.48      3548569.57     10544442.43
      3547479.31     10544678.54
#Sta/Elev= 30
  3426.2  421.71  3447.7  420.62  3499.4  418.96  3570.8  415.39  3730.1  410.24
    3774  408.63  3871.3  403.56  3904.7  400.78  4175.5  389.87  4359.9  387.84
  4381.2  382.21  4387.9  382.46  4402.1  387.78  4430.5  388.57  4728.2  387.69
  4974.3  390.31  4994.7  381.99  5000.9  381.42  5003.6  380.92  5006.9  381.42
  5015.2  387.35  5025.4  389.49  5158.4  387.53  5301.7  389.62  5363.1  392.61
  5382.1  396.08  5387.3  394.88  5431.3  406.16  5741.7  408.39  5867.3  415.33
#Mann= 10 ,-1 , 0
  3426.2     .05       0  3447.7      .1       0  3499.4     .05       0
  3570.8      .1       0  3730.1     .15       0    3774     .05       0
  3871.3     .15       0  3904.7     .05       0  5000.9     .03       0
  5006.9     .05       0
Bank Sta=4974.3,5025.4
XS Rating Curve= 0 ,0
Exp/Cntr=0.3,0.1

Type RM Length L Ch R = 1 ,2932    ,787,787,787
BEGIN DESCRIPTION:
CEDAR CREEK 2 6.0
END DESCRIPTION:
XS GIS Cut Line= 3
      3548492.14     10543441.61      3548192.11     10543691.64
      3547492.13     10544591.62
#Sta/Elev= 30
  4583.9  406.46  4611.9  406.21  4648.4  399.41  4676.5  397.85  4720.7  395.61
  4818.3  390.22  4839.7  387.17  4860.6  388.72  4912.8  387.19  4967.3  384.25
  4981.7  385.81  4999.5  378.03  5002.3  377.53  5005.5  378.03  5037.8  387.35
  5063.7  386.91    5502  386.27  5730.1  400.87  5893.8  406.36  5929.1  409.65
  5958.1  408.47  5978.9  411.65    5987  410.25  5993.4  412.58  6007.9  409.15
  6014.2  412.21  6022.3  410.24  6028.7     413  6036.8  411.65  6114.6  414.09
#Mann= 7 ,-1 , 0
  4583.9     .05       0  4676.5     .16       0  4720.7     .05       0
  4912.8     .16       0  4999.5     .07       0  5005.5     .16       0
  5063.7     .05       0
Bank Sta=4981.7,5037.8
XS Rating Curve= 0 ,0
Exp/Cntr=0.3,0.1

Type RM Length L Ch R = 1 ,2145    ,617,617,617
BEGIN DESCRIPTION:
CEDAR CREEK 2 5.0
END DESCRIPTION:
XS GIS Cut Line= 2
      3548181.84     10542693.59      3546977.04     10544440.03
#Sta/Elev= 30
  3974.1     415  4021.9  414.17  4057.9   411.1  4087.6  412.61  4108.6  410.42
  4117.4   411.4  4123.5  409.49  4138.3  410.82  4159.3  408.67    4231  408.05
  4323.3  404.24  4500.8  395.98  4604.7     391  4792.1  385.91  4932.9  385.99
  4974.7  384.78  4986.2   383.2  4992.3  377.28  4998.1  376.83  5000.8  376.33
  5004.1  376.83  5015.9  377.19    5022  382.03  5028.7  384.95  5302.6  384.65
  5466.9  386.81    5881  406.81    5997  408.69  6053.9  410.44  6095.8  411.29
#Mann= 12 ,-1 , 0
  3974.1     .05       0  4021.9      .1       0  4323.3     .16       0
  4500.8     .08       0  4604.7     .05       0  4932.9     .16       0
  4974.7     .05       0  4998.1     .03       0  5004.1     .05       0
    5881      .1       0    5997     .16       0  6053.9      .1       0
Bank Sta=4974.7,5028.7
XS Rating Curve= 0 ,0
Exp/Cntr=0.3,0.1

Type RM Length L Ch R = 1 ,1528    ,843,843,843
BEGIN DESCRIPTION:
CEDAR CREEK 2 3.0
END DESCRIPTION:
XS GIS Cut Line= 2
       3547623.6     10542734.62      3546613.18     10543783.23
#Sta/Elev= 30
    4284  408.31  4346.7  404.85  4424.4   398.7  4431.6  399.45  4459.9  397.98
  4519.3  392.77    4587  388.03  4703.3   384.3  4703.4   384.3  4813.3   383.6
    4913  385.01  4961.8  384.78    4969  381.42  4972.1  381.71  4975.9  382.06
  4980.1   376.9  4982.9   376.4  4986.1   376.9  4990.1  378.25  5004.2  378.03
  5018.4  380.81  5025.6  384.28  5039.7  385.63  5372.1  384.31    5464  391.65
  5520.6  399.26  5566.5  402.71  5573.1  403.14  5647.9  405.97  5740.2  406.37
#Mann= 10 ,-1 , 0
    4284     .08       0  4519.3     .05       0  4703.3     .15       0
  4703.4     .05       0    4913      .1       0  4972.1     .05       0
  4980.1     .03       0  4986.1     .05       0  5566.5      .1       0
  5573.1     .05       0
Bank Sta=4961.8,5025.6
XS Rating Curve= 0 ,0
Exp/Cntr=0.3,0.1

Type RM Length L Ch R = 1 ,685     ,0,0,0
BEGIN DESCRIPTION:
CEDAR CREEK 2 1.0
END DESCRIPTION:
XS GIS Cut Line= 4
      3547702.67     10542606.77      3546674.91     10542877.59
       3546539.5     10543141.48      3546536.02     10543856.73
#Sta/Elev= 30
  3776.6  409.75  3828.9  410.96    3895  409.83    3953  403.03  3998.5  399.57
  4126.5  388.89    4219  384.21  4273.6  382.17  4332.4  383.34  4478.9  384.24
  4524.3  387.86  4552.8  388.33    4605   383.6  4670.2  383.95  4875.4  383.42
  4919.7  384.13  4978.9  383.97  4991.8  377.67    5011  375.73  5013.8  375.23
    5017  375.73  5036.2   382.7  5046.3  384.08  5080.6  386.18  5138.6  385.42
  5280.2   389.5  5616.2  401.16  5686.2  402.21  5774.3  406.54  5851.3   408.3
#Mann= 11 ,-1 , 0
  3776.6      .1       0  3998.5     .05       0    4219     .08       0
  4332.4     .16       0  4670.2     .12       0  4875.4     .16       0
  4919.7     .12       0    5011     .07       0    5017     .12       0
  5280.2      .1       0  5774.3     .05       0
Bank Sta=4978.9,5046.3
XS Rating Curve= 0 ,0
Exp/Cntr=0.3,0.1

Chan Stop Cuts=-1
Use User Specified Reach Order=0
Composite Channel Slope=5