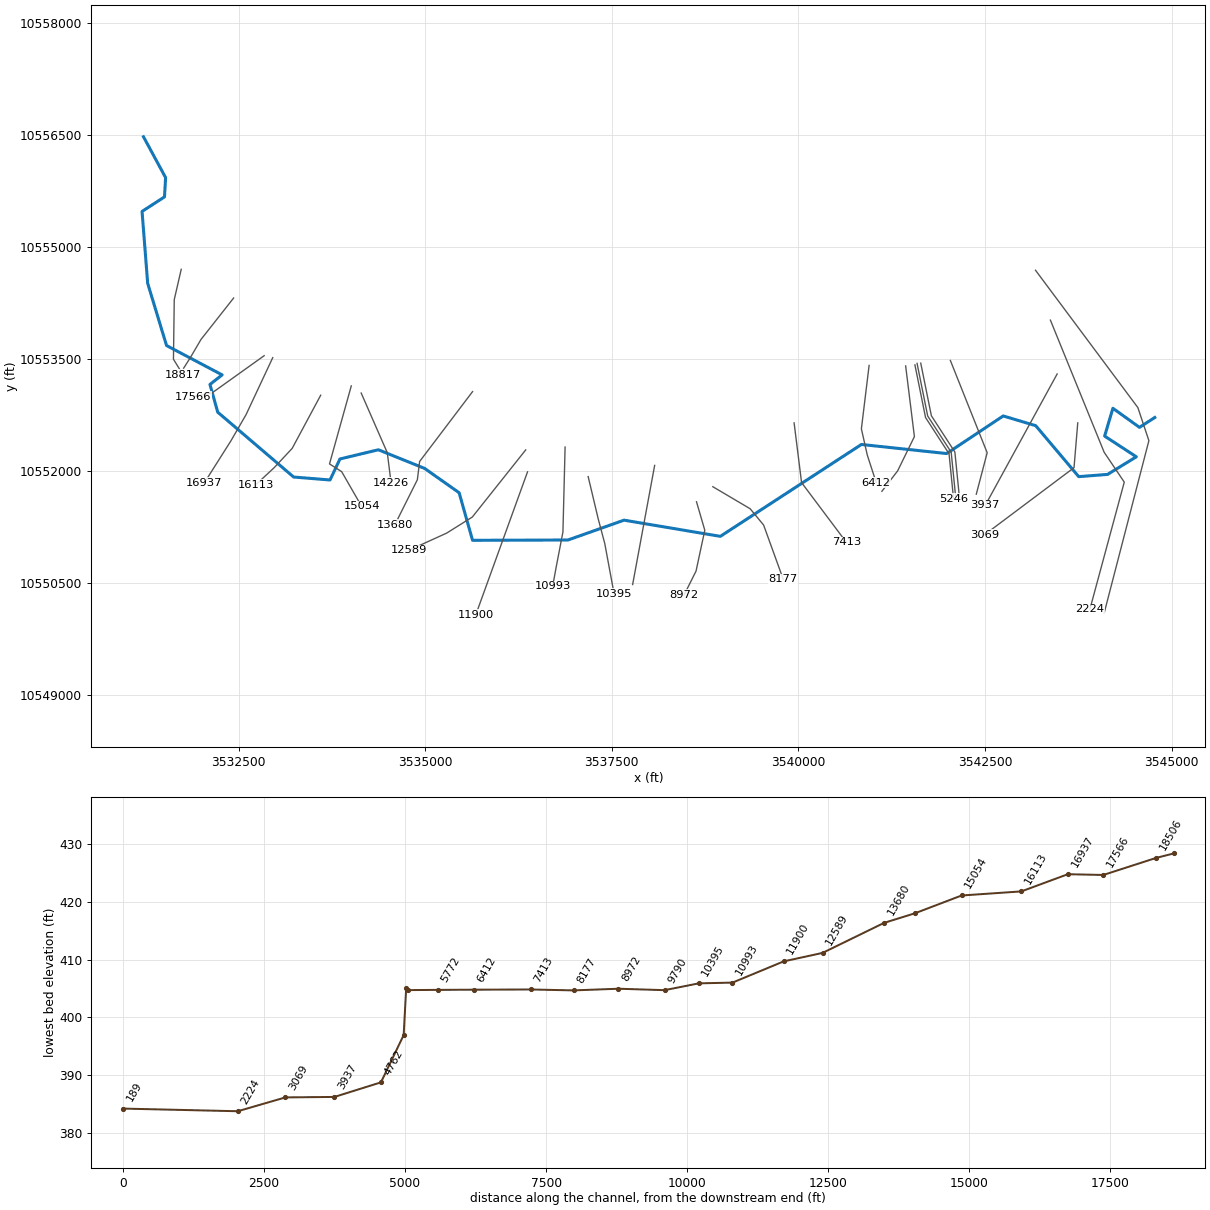
--- CHAMBERS CREEK.prj (project) ---

Proj Title=CHAMBERS CREEK Base Level Engineering
Current Plan=p01
Default Exp/Contr=0.3,0.1
English Units
Geom File=g01
Flow File=f01
Plan File=p01
Y Axis Title=Elevation
X Axis Title(PF)=Main Channel Distance
X Axis Title(XS)=Station
BEGIN DESCRIPTION:
CHAMBERS CREEK
END DESCRIPTION:
DSS Export Rating Curves= 0
DSS Export Rating Curve Sorted= 0
DSS Export Volume Flow Curves= 0
DXF OffsetX= 0
DXF OffsetY= 0
DXF ScaleX= 1
DXF ScaleY= 10

--- CHAMBERS CREEK.p01 (plan) ---

Plan Title=Multiple Run
Short Identifier=Multiple
Geom File=g01
Flow File=f01
Subcritical Flow
K Sum by GR= 0
Std Step Tol= 0.01
Critical Tol= 0.01
Num of Std Step Trials= 20
Max Error Tol= 0.3
Flow Tol Ratio= 0.001
Split Flow NTrial= 30
Split Flow Tol= 0.02
Split Flow Ratio= 0.02
Log Output Level= 0
Friction Slope Method= 1
Unsteady Friction Slope Method= 2
Unsteady Bridges Friction Slope Method= 1
Parabolic Critical Depth
Global Vel Dist=  1 , 1 , 1
Global Log Level= 0
CheckData=True
Encroach Param= -1, 0, 0, 0
BEGIN DESCRIPTION:
Multiple Run
END DESCRIPTION:

--- CHAMBERS CREEK.f01 (steady flow) ---

Flow Title=Multiple
Program Version=4.10
Number of Profiles= 7
Profile Names=10-year,25-year,50-year,1pct_min,100-year,1pct_plu,500-year
River Rch & RM=CHAMBERS CREEK,Reach-1         ,18817
    2162    3079    3861    3522    4763    6441    7234
River Rch & RM=CHAMBERS CREEK,Reach-1         ,10395
    2519    3597    4515    4120    5572    7536    8471
River Rch & RM=CHAMBERS CREEK,Reach-1         ,5772
    2588    3689    4626    4215    5700    7709    8641
River Rch & RM=CHAMBERS CREEK,Reach-1         ,5165
    2798    4008    5042    4610    6234    8431    9513
Boundary for River Rch & Prof#=CHAMBERS CREEK,Reach-1         , 1
Up Type= 0
Dn Type= 3
Dn Slope=0.005
Boundary for River Rch & Prof#=CHAMBERS CREEK,Reach-1         , 2
Up Type= 0
Dn Type= 3
Dn Slope=0.005
Boundary for River Rch & Prof#=CHAMBERS CREEK,Reach-1         , 3
Up Type= 0
Dn Type= 3
Dn Slope=0.005
Boundary for River Rch & Prof#=CHAMBERS CREEK,Reach-1         , 4
Up Type= 0
Dn Type= 3
Dn Slope=0.005
Boundary for River Rch & Prof#=CHAMBERS CREEK,Reach-1         , 5
Up Type= 0
Dn Type= 3
Dn Slope=0.005
Boundary for River Rch & Prof#=CHAMBERS CREEK,Reach-1         , 6
Up Type= 0
Dn Type= 3
Dn Slope=0.005
Boundary for River Rch & Prof#=CHAMBERS CREEK,Reach-1         , 7
Up Type= 0
Dn Type= 3
Dn Slope=0.005
DSS Import GetInterval= 0
DSS Import GetPeak= 0
DSS Import FillOption= 0

--- CHAMBERS CREEK.g01 (geometry) ---

Geom Title=Existing Conditions
Program Version=4.10

River Reach=CHAMBERS CREEK  ,Reach-1
Reach XY= 30
       3531225.4     10556474.94      3531521.88     10555927.36
      3531506.99     10555669.25      3531206.33     10555474.49
      3531281.78     10554510.94      3531534.45       10553678.
      3532279.22     10553284.79      3532116.11     10553156.75
      3532220.21     10552784.95      3533237.11      10551916.3
      3533724.89     10551876.74      3533857.66     10552158.24
      3534372.22     10552281.55      3534992.11     10552031.64
      3535454.14     10551705.86      3535634.24     10551068.56
      3536912.12     10551072.55      3537663.48     10551338.53
      3538953.48     10551121.36      3540843.67     10552352.59
      3541985.61     10552230.83      3542744.03     10552734.61
      3543178.75     10552604.41      3543755.13     10551921.42
      3544141.86     10551951.46      3544526.93     10552187.23
      3544102.28     10552464.66      3544213.04     10552837.17
      3544568.94     10552581.96      3544774.07     10552713.62

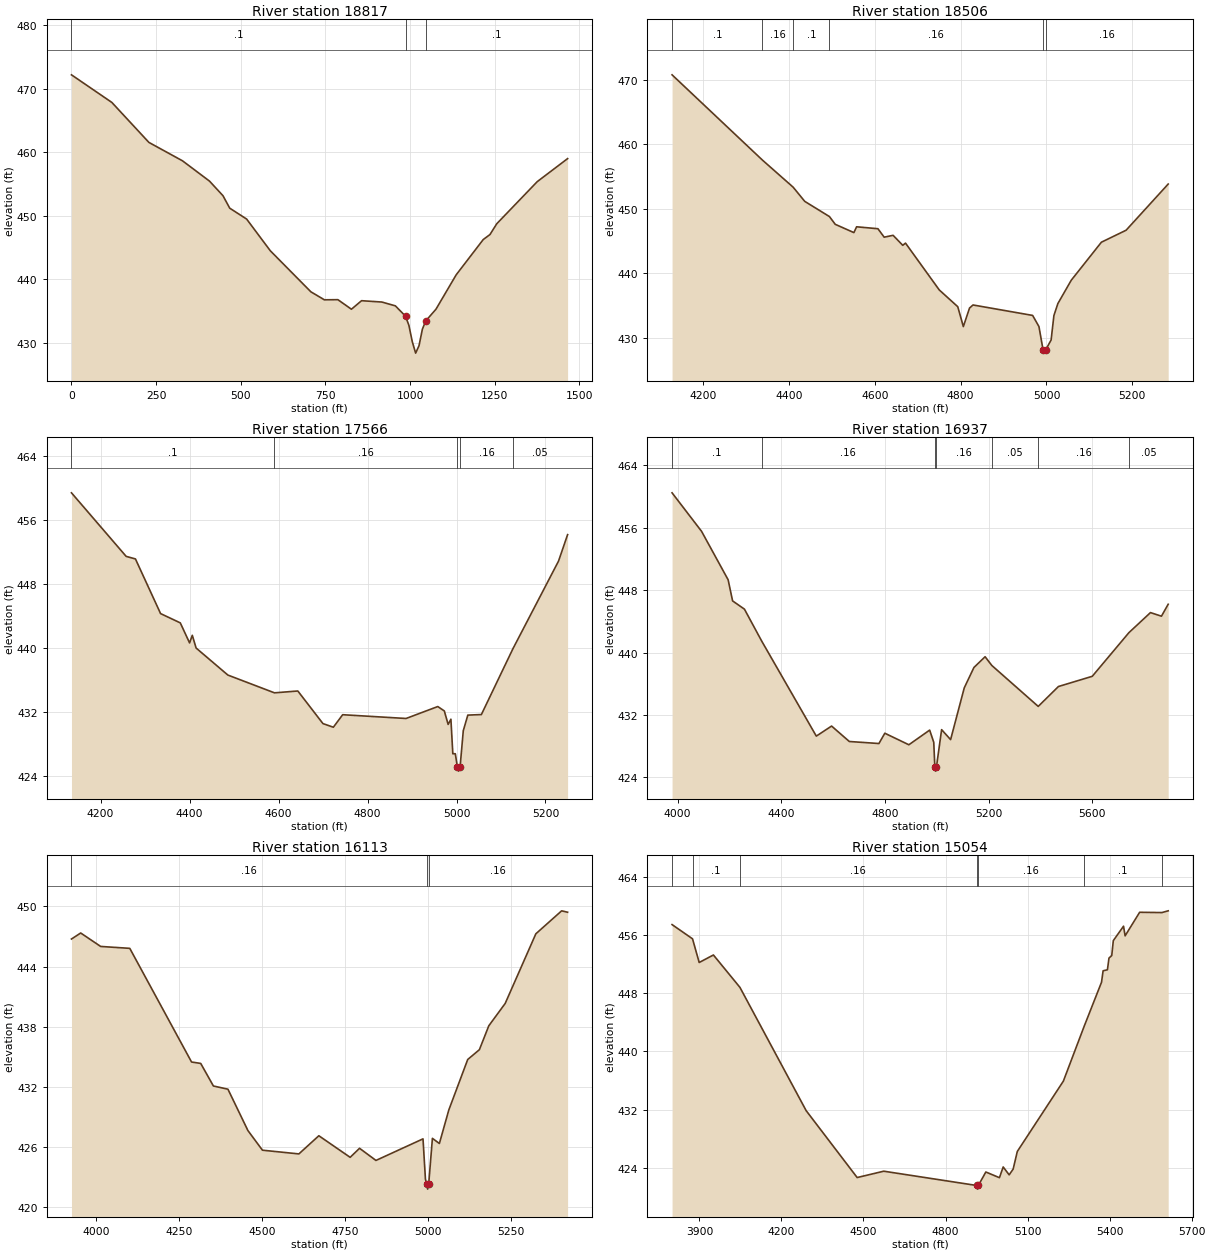
Type RM Length L Ch R = 1 ,18817   ,311,311,311
XS GIS Cut Line= 4
     3531731.119    10554699.179     3531637.803    10554293.363
     3531626.952    10553494.752     3531754.991    10553286.419
#Sta/Elev= 30
       0  472.15  119.31  467.81  228.67  461.53   328.1  458.63  407.63  455.45
  447.53  453.15   467.5  451.19  517.42  449.48   587.3   444.5  707.11  438.05
  747.05  436.79  786.98  436.81  826.92  435.31  856.87  436.65  916.77  436.44
  956.71  435.84  986.66  434.22  996.65  432.78 1006.63  430.23 1016.61  428.41
  1026.6  429.58 1036.58  432.18 1046.57  433.48 1076.52   435.3 1136.42  440.72
 1216.29  446.26 1236.23  447.05 1256.16  448.74 1375.77  455.36 1465.48  458.98
#Mann= 3 , 0 , 0
       0      .1       0  986.66     .05       0 1046.57      .1       0
Bank Sta=986.66,1046.57
XS Rating Curve= 0 ,0
Exp/Cntr=0.3,0.1

Type RM Length L Ch R = 1 ,18506   ,940,940,940
BEGIN DESCRIPTION:
CHAMBERS CREEK 37.0
END DESCRIPTION:
XS GIS Cut Line= 4
      3532433.03     10554314.37       3531995.5     10553758.78
      3531853.14     10553515.73       3531763.9     10553374.99
#Sta/Elev= 30
    4128  470.75  4338.5  457.54  4410.1  453.34    4437  451.15  4494.6  448.79
  4508.1  447.59  4551.5  446.31  4557.8  447.21  4607.5  446.91    4622   445.6
  4642.8  445.89  4665.3  444.34  4671.7  444.68  4750.3  437.43  4793.4  434.83
  4806.4  431.75  4820.8  434.62  4828.9   435.1  4967.8  433.48  4982.5  431.75
  4992.1  428.14  4994.9  427.64  4998.1  428.14  5010.8  429.67  5017.3  433.45
  5026.5  435.31  5057.8  438.94  5127.9  444.82  5185.5  446.68  5283.5  453.83
#Mann= 6 ,-1 , 0
    4128      .1       0  4338.5     .16       0  4410.1      .1       0
  4494.6     .16       0  4992.1     .07       0  4998.1     .16       0
Bank Sta=4992.1,4998.1
XS Rating Curve= 0 ,0
Exp/Cntr=0.3,0.1

Type RM Length L Ch R = 1 ,17566   ,629,629,629
BEGIN DESCRIPTION:
CHAMBERS CREEK 35.0
END DESCRIPTION:
XS GIS Cut Line= 3
      3532842.13     10553541.66      3532142.11     10553041.64
      3531892.11     10552991.64
#Sta/Elev= 30
  4134.5   459.4  4257.4  451.47  4278.3  451.15  4334.8  444.33  4379.1  443.17
    4400  440.67  4406.1  441.62  4414.7  440.03    4486  436.66  4590.8  434.44
  4643.3  434.67  4699.8   430.6  4723.2  430.15  4744.1  431.71  4886.6  431.24
  4957.9  432.73  4972.6  432.18  4981.2   430.5  4987.4  431.15  4991.7  426.84
  4997.3  426.84    5002  425.17  5004.7  424.67    5008  425.17  5015.2  429.71
  5025.4  431.66  5055.9  431.73  5126.6  439.92  5229.3  450.88  5249.7  454.18
#Mann= 5 ,-1 , 0
  4134.5      .1       0  4590.8     .16       0    5002     .07       0
    5008     .16       0  5126.6     .05       0
Bank Sta=5002,5008
XS Rating Curve= 0 ,0
Exp/Cntr=0.3,0.1

Type RM Length L Ch R = 1 ,16937   ,824,824,824
BEGIN DESCRIPTION:
CHAMBERS CREEK 34.0
END DESCRIPTION:
XS GIS Cut Line= 4
      3532957.32     10553515.74      3532599.67     10552751.84
      3532394.81     10552397.67      3532040.65     10551838.65
#Sta/Elev= 30
  3978.5  460.49  4092.4  455.55  4194.8  449.34  4212.1  446.63  4257.8  445.57
    4324   441.5  4535.1  429.29    4594  430.58  4662.5   428.6  4776.7  428.34
  4799.5  429.66  4892.2  428.18  4972.5  430.06  4988.3  428.49  4992.5   425.3
  4995.2   424.8  4998.5   425.3  5018.6  430.12  5053.3  428.84    5106  435.48
  5143.3  438.09  5186.4  439.47  5212.3  438.35  5391.4   433.1  5469.4  435.65
  5599.9  436.96  5741.1  442.55  5824.5  445.13  5866.9  444.67  5892.9   446.2
#Mann= 7 ,-1 , 0
  3978.5      .1       0    4324     .16       0  4992.5     .07       0
  4998.5     .16       0  5212.3     .05       0  5391.4     .16       0
  5741.1     .05       0
Bank Sta=4992.5,4998.5
XS Rating Curve= 0 ,0
Exp/Cntr=0.3,0.1

Type RM Length L Ch R = 1 ,16113   ,1059,1059,1059
BEGIN DESCRIPTION:
CHAMBERS CREEK 32.0
END DESCRIPTION:
XS GIS Cut Line= 4
      3533599.67     10553012.26      3533217.73     10552300.45
      3532978.14     10552043.51      3532732.87     10551815.51
#Sta/Elev= 30
  3926.2  446.75    3954  447.35  4014.1  446.01  4101.8  445.82  4287.8  434.49
  4315.4  434.35  4353.6   432.1  4397.4  431.78  4457.5  427.66  4501.3   425.7
    4611  425.33  4671.1  427.14  4765.4  424.99  4793.7  425.89  4843.1  424.68
  4984.8  426.83  4992.1  422.81  4995.9  422.32  4998.7  421.82  5001.9  422.32
  5013.1  426.88  5034.1  426.37  5062.4   429.7  5119.4  434.74  5154.6  435.72
  5182.9   438.1  5232.3  440.33  5324.6  447.27  5402.3  449.56  5420.2  449.42
#Mann= 3 ,-1 , 0
  3926.2     .16       0  4995.9     .07       0  5001.9     .16       0
Bank Sta=4995.9,5001.9
XS Rating Curve= 0 ,0
Exp/Cntr=0.3,0.1

Type RM Length L Ch R = 1 ,15054   ,828,828,828
BEGIN DESCRIPTION:
CHAMBERS CREEK 30.0
END DESCRIPTION:
XS GIS Cut Line= 4
      3534009.39     10553137.24      3533717.73     10552092.12
      3533880.92     10551987.95      3534147.69      10551523.7
#Sta/Elev= 30
  3800.1  457.41  3874.9  455.46  3899.3  452.21  3951.3  453.24  4048.2   448.8
  4290.4  431.88  4476.9   422.7  4574.2  423.57    4914  421.61  4916.7  421.11
    4920  421.61  4947.4  423.46  4997.1  422.68  5010.9  424.15  5032.7  423.07
  5047.3  423.86  5062.5  426.28  5230.9  435.93  5306.9  443.45  5370.4   449.5
  5376.2  451.07    5392  451.21  5397.7  452.82  5407.8  453.16  5413.5  455.21
  5450.9  457.19  5456.7  455.87  5509.8   459.1  5590.9  459.06  5614.2   459.3
#Mann= 7 ,-1 , 0
  3800.1     .16       0  3874.9      .1       0  4048.2     .16       0
    4914     .07       0    4920     .16       0  5306.9      .1       0
  5590.9     .08       0
Bank Sta=4914,4920
XS Rating Curve= 0 ,0
Exp/Cntr=0.3,0.1

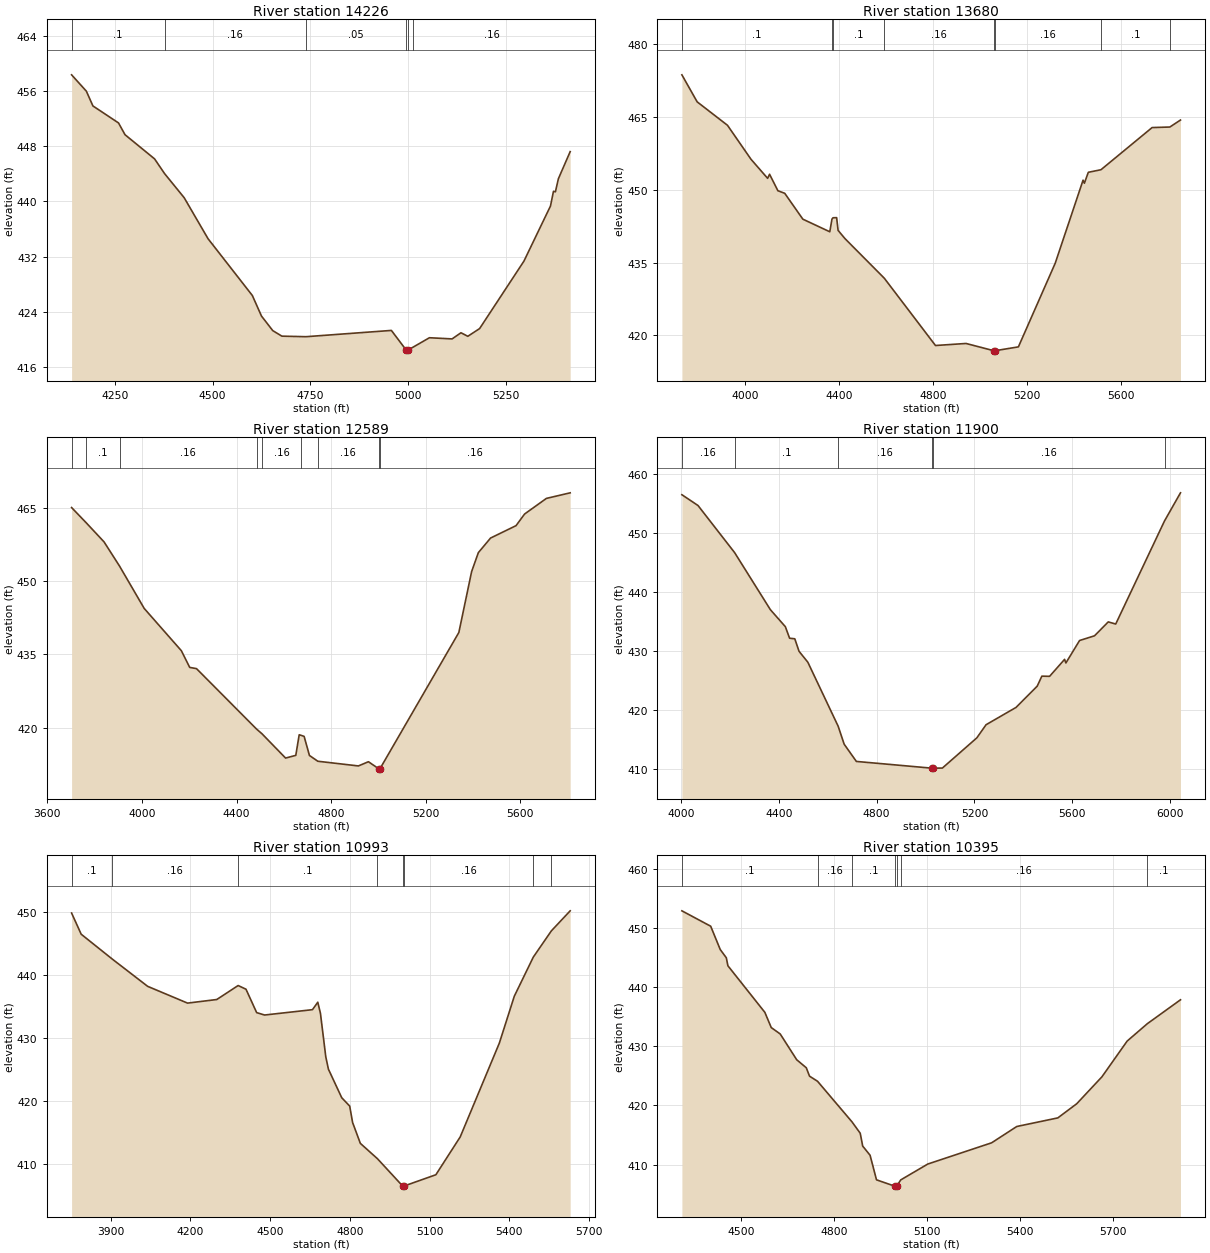
Type RM Length L Ch R = 1 ,14226   ,546,546,546
BEGIN DESCRIPTION:
CHAMBERS CREEK 28.0
END DESCRIPTION:
XS GIS Cut Line= 3
      3534142.11     10553041.64      3534492.11     10552241.64
       3534542.1     10551841.66
#Sta/Elev= 30
  4139.1  458.35  4176.9  455.98  4193.7  453.84  4259.2  451.38  4275.9  449.67
  4351.5  446.17  4377.2  444.03  4427.2  440.55  4488.4   434.6  4601.8  426.37
  4625.2  423.39  4654.1  421.28  4677.4  420.48  4738.9   420.4  4957.7  421.31
  4994.9  418.52  4997.6  418.02  5000.9  418.52  5012.5  418.86  5055.1  420.25
  5113.1  420.08  5135.8  420.97  5153.4  420.46  5183.6  421.58    5297  431.35
    5365  439.34  5372.6  441.47  5377.6   441.4  5385.2  443.29  5415.4  447.22
#Mann= 6 ,-1 , 0
  4139.1      .1       0  4377.2     .16       0  4738.9     .05       0
  4994.9    .033       0  5000.9     .05       0  5012.5     .16       0
Bank Sta=4994.9,5000.9
XS Rating Curve= 0 ,0
Exp/Cntr=0.3,0.1

Type RM Length L Ch R = 1 ,13680   ,1091,1091,1091
BEGIN DESCRIPTION:
CHAMBERS CREEK 27.0
END DESCRIPTION:
XS GIS Cut Line= 6
      3535634.38     10553060.85      3534924.95     10552124.48
      3534894.81     10551880.31      3534627.45     10551345.59
      3534637.87     10551342.12      3534592.87     10551276.36
#Sta/Elev= 30
  3732.6  473.72  3797.5  468.15  3926.4  463.32  4026.3  456.32  4097.1  452.38
  4105.3  453.23  4140.7  449.83  4169.8   449.3  4246.8  443.97  4361.3  441.37
  4370.5  443.97    4375  444.26  4390.4  444.28  4396.6  441.66  4425.7  439.97
  4593.2  431.79  4810.6  417.93  4940.5  418.35  5058.4  416.86  5061.1  416.36
  5064.4  416.86  5163.1  417.65  5319.6  434.89    5438  452.01  5443.6  451.38
  5460.3  453.63  5514.1  454.16  5731.5  462.85  5806.8  462.96  5852.1   464.4
#Mann= 8 ,-1 , 0
  3732.6      .1       0  4370.5     .16       0    4375      .1       0
  4593.2     .16       0  5058.4     .07       0  5064.4     .16       0
  5514.1      .1       0  5806.8     .16       0
Bank Sta=5058.4,5064.4
XS Rating Curve= 0 ,0
Exp/Cntr=0.3,0.1

Type RM Length L Ch R = 1 ,12589   ,689,689,689
BEGIN DESCRIPTION:
CHAMBERS CREEK 25.0
END DESCRIPTION:
XS GIS Cut Line= 4
      3536346.18     10552279.59      3535630.92     10551380.31
      3535287.17     10551165.03      3534783.71     10550935.87
#Sta/Elev= 30
  3702.6     465    3764  461.91  3839.9  457.98  3905.7  453.01  4009.7  444.38
  4166.7  435.75  4201.9  432.34  4230.7  432.09  4484.6  419.74  4507.3  418.79
  4607.2  413.82  4650.4  414.37  4664.8  418.58  4672.1  418.47  4685.6  418.25
  4708.1  414.35  4743.4  413.17  4915.1  412.21  4957.5  413.07  5000.5  411.65
  5003.3  411.15  5006.5  411.65  5339.7  439.47  5393.7  451.91  5422.2  455.79
  5473.8  458.77  5581.4   461.3  5617.7  463.68  5709.9  466.87  5810.4  468.01
#Mann= 9 ,-1 , 0
  3702.6     .16       0    3764      .1       0  3905.7     .16       0
  4484.6      .1       0  4507.3     .16       0  4672.1      .1       0
  4743.4     .16       0  5000.5     .07       0  5006.5     .16       0
Bank Sta=5000.5,5006.5
XS Rating Curve= 0 ,0
Exp/Cntr=0.3,0.1

Type RM Length L Ch R = 1 ,11900   ,907,907,907
BEGIN DESCRIPTION:
CHAMBERS CREEK 23.0
END DESCRIPTION:
XS GIS Cut Line= 2
      3536370.64     10551985.76      3535676.64      10550068.6
#Sta/Elev= 30
  4003.8  456.45  4069.8  454.62  4219.5  446.65  4365.6     437  4426.9  434.12
  4444.2  432.17  4465.5  432.07  4482.8  429.96  4518.8  428.11  4642.8  417.28
  4667.5  414.23  4717.3  411.32  5026.1  410.18  5028.9  409.68  5032.1  410.18
  5069.1   410.2  5209.9  415.31  5247.6  417.53  5370.2  420.46  5456.8  424.06
  5475.8  425.75  5507.5  425.72  5568.7  428.59  5574.1  427.98    5630  431.78
  5691.3  432.58  5747.3  434.93  5777.9  434.57  5977.5  452.02  6042.7  456.77
#Mann= 6 ,-1 , 0
  4003.8     .16       0  4219.5      .1       0  4642.8     .16       0
  5026.1     .07       0  5032.1     .16       0  5977.5      .1       0
Bank Sta=5026.1,5032.1
XS Rating Curve= 0 ,0
Exp/Cntr=0.3,0.1

Type RM Length L Ch R = 1 ,10993   ,598,598,598
BEGIN DESCRIPTION:
CHAMBERS CREEK 21.0
END DESCRIPTION:
XS GIS Cut Line= 4
      3536873.98     10552317.78      3536844.93     10551179.68
      3536755.92     10550717.12      3536707.63     10550454.94
#Sta/Elev= 30
    3753   449.8  3789.1  446.44  3905.7  442.51  4039.2  438.17  4189.3  435.51
  4299.3  436.08  4379.7   438.3  4409.3  437.71  4449.4     434  4479.4  433.62
  4659.4  434.47  4679.4  435.65  4689.4  433.89  4709.4  427.01  4719.4  425.03
  4769.5   420.5  4799.5  419.17  4810.3  416.58  4839.5  413.26    4904  410.82
  4998.5   406.5  5001.2     406  5004.5   406.5  5123.7  408.28  5215.3  414.28
  5362.5  429.16  5418.9  436.61  5490.5  442.82  5558.5  446.98  5629.1  450.15
#Mann= 8 ,-1 , 0
    3753      .1       0  3905.7     .16       0  4379.7      .1       0
    4904     .16       0  4998.5     .07       0  5004.5     .16       0
  5490.5      .1       0  5558.5     .16       0
Bank Sta=4998.5,5004.5
XS Rating Curve= 0 ,0
Exp/Cntr=0.3,0.1

Type RM Length L Ch R = 1 ,10395   ,605,605,605
BEGIN DESCRIPTION:
CHAMBERS CREEK 20.0
END DESCRIPTION:
XS GIS Cut Line= 4
        3537183.       10551922.      3537318.42     10551352.53
      3537405.23     10551026.15      3537530.23     10550352.52
#Sta/Elev= 30
  4308.4  452.88  4401.3  450.28  4432.1  446.34  4451.7  444.95  4456.8   443.6
    4576  435.73  4596.6  433.16  4625.5  432.08  4678.8  427.72  4709.6  426.37
  4720.1  424.95  4745.9  424.09  4857.1  417.23  4883.6  415.31  4891.6  413.14
  4915.4  411.59  4936.1  407.44  4995.1  406.37  4997.9  405.87  5001.1  406.37
  5014.4  407.43  5101.6  410.11  5307.3  413.69  5388.6  416.45  5520.9   417.9
  5581.9  420.29  5663.2  424.84  5744.6  430.88  5809.8  433.82  5916.6  437.85
#Mann= 7 ,-1 , 0
  4308.4      .1       0  4745.9     .16       0  4857.1      .1       0
  4995.1     .07       0  5001.1      .1       0  5014.4     .16       0
  5809.8      .1       0
Bank Sta=4995.1,5001.1
XS Rating Curve= 0 ,0
Exp/Cntr=0.3,0.1

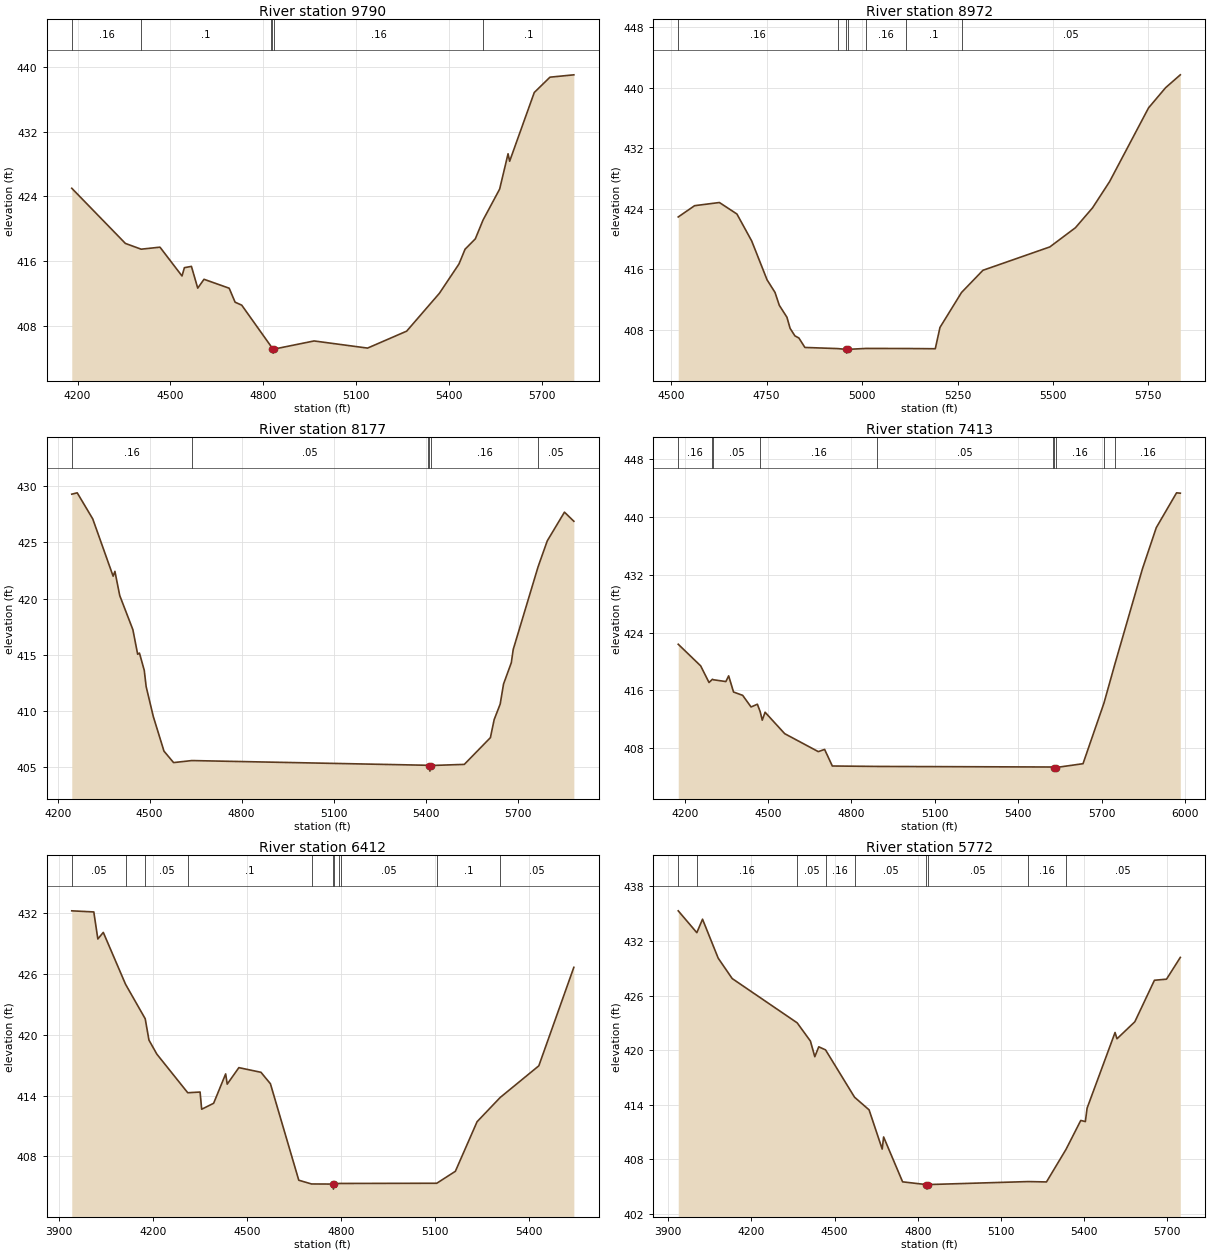
Type RM Length L Ch R = 1 ,9790    ,818,818,818
BEGIN DESCRIPTION:
CHAMBERS CREEK 18.0
END DESCRIPTION:
XS GIS Cut Line= 2
      3538073.77     10552072.13      3537778.78     10550475.76
#Sta/Elev= 30
  4181.1  425.01  4354.5  418.21  4405.5   417.5  4466.3  417.75  4537.5   414.2
  4545.3  415.22    4568  415.38  4588.4   412.7  4608.7  413.79  4690.1  412.69
  4709.2  410.97  4730.7   410.6    4824   405.6  4829.4  405.19  4832.2  404.69
  4835.4  405.19  4964.6  406.19  5137.5  405.31    5264   407.4  5369.9  412.07
    5433  415.67  5452.8   417.5  5485.9  418.77  5510.9  421.09  5564.6  424.91
  5591.8  429.26  5596.9  428.34  5676.5  436.81  5727.3   438.7  5804.5  438.99
#Mann= 6 ,-1 , 0
  4181.1     .16       0  4405.5      .1       0    4824     .16       0
  4829.4     .07       0  4835.4     .16       0  5510.9      .1       0
Bank Sta=4829.4,4835.4
XS Rating Curve= 0 ,0
Exp/Cntr=0.3,0.1

Type RM Length L Ch R = 1 ,8972    ,795,795,795
BEGIN DESCRIPTION:
CHAMBERS CREEK 17.0
END DESCRIPTION:
XS GIS Cut Line= 4
       3538634.4     10551585.14       3538745.5     10551203.23
      3538628.31     10550656.58      3538468.09     10550335.89
#Sta/Elev= 30
  4518.4  422.94  4561.2  424.43  4626.2  424.85  4672.2  423.33  4710.9  419.76
  4751.2  414.62    4772  412.96  4783.1  411.27  4803.2  409.68  4811.5  408.21
  4824.1  407.22  4834.5  406.94  4850.2  405.69  4936.1  405.54    4957  405.44
  4959.8  404.94    4963  405.44  5010.6  405.56  5115.8  405.55  5191.8  405.52
  5204.1  408.34  5260.6  412.96  5316.6  415.89  5491.9  418.98    5559  421.52
  5603.7  424.14  5648.4  427.61  5750.5  437.36  5795.2  440.03  5833.7  441.73
#Mann= 7 ,-1 , 0
  4518.4     .16       0  4936.1     .05       0    4957    .033       0
    4963     .05       0  5010.6     .16       0  5115.8      .1       0
  5260.6     .05       0
Bank Sta=4957,4963
XS Rating Curve= 0 ,0
Exp/Cntr=0.3,0.1

Type RM Length L Ch R = 1 ,8177    ,764,764,764
BEGIN DESCRIPTION:
CHAMBERS CREEK 15.0
END DESCRIPTION:
XS GIS Cut Line= 4
      3538853.16     10551786.55      3539353.14     10551491.42
       3539533.7     10551272.67      3539796.78     10550545.74
#Sta/Elev= 30
    4246   429.3  4263.8  429.42  4314.4   427.1  4380.9     422  4386.7  422.43
  4402.4  420.28  4445.3  417.24  4460.9  415.05  4466.7  415.16  4482.4  413.62
  4488.6  412.17  4511.9  409.51  4546.7  406.43    4578  405.41  4637.8  405.59
    5408  405.17  5411.3  405.15    5414  404.65  5417.3  405.15  5526.1  405.25
  5611.2  407.63  5623.4  409.23  5643.1  410.62  5654.1  412.41  5679.4   414.3
  5685.6  415.48  5766.7  422.84  5796.7  425.15  5852.7   427.7  5883.3  426.89
#Mann= 6 ,-1 , 0
    4246     .16       0  4637.8     .05       0    5408     .16       0
  5411.3    .033       0  5417.3     .16       0  5766.7     .05       0
Bank Sta=5411.3,5417.3
XS Rating Curve= 0 ,0
Exp/Cntr=0.3,0.1

Type RM Length L Ch R = 1 ,7413    ,1001,1001,1001
BEGIN DESCRIPTION:
CHAMBERS CREEK 13.0
END DESCRIPTION:
XS GIS Cut Line= 3
      3539942.11     10552641.64      3540042.11     10551841.64
      3540642.09     10551041.66
#Sta/Elev= 30
  4176.7  422.39  4257.3   419.4  4287.5  417.09  4299.8  417.54  4303.2  417.47
    4348  417.22  4358.1  418.01  4375.7  415.77  4408.5  415.31  4438.7   413.7
  4461.4  414.08  4471.4  413.06    4479  411.87  4489.1  412.97  4559.7     410
  4680.6  407.51  4703.3  407.82    4731  405.52  4893.5  405.46  5524.1  405.38
  5529.9  405.31  5532.7  404.81  5535.9  405.31  5632.9  405.84  5708.3  414.25
  5747.9  419.69  5846.5  432.82  5896.5  438.55  5969.4  443.37  5982.9  443.32
#Mann= 10 ,-1 , 0
  4176.7     .16       0  4299.8      .1       0  4303.2     .05       0
  4471.4     .16       0  4893.5     .05       0  5524.1     .16       0
  5529.9    .033       0  5535.9     .16       0  5708.3     .05       0
  5747.9     .16       0
Bank Sta=5529.9,5535.9
XS Rating Curve= 0 ,0
Exp/Cntr=0.3,0.1

Type RM Length L Ch R = 1 ,6412    ,640,640,640
BEGIN DESCRIPTION:
CHAMBERS CREEK 11.0
END DESCRIPTION:
XS GIS Cut Line= 4
      3540946.89     10553411.57      3540843.45      10552561.9
      3540922.59     10552210.17      3541042.11     10551841.63
#Sta/Elev= 30
  3940.5  432.26  4010.9  432.15  4023.8  429.48  4041.2  430.13  4112.4     425
  4175.1   421.6  4187.1  419.49  4212.4   418.1    4311  414.29  4350.4  414.36
  4355.5  412.66  4393.7  413.25  4432.1  416.15  4437.1  415.14  4474.3  416.77
  4544.9  416.31  4575.1  415.18  4665.7  405.65  4706.4  405.28  4773.6  405.27
  4776.3  404.77  4779.6  405.27  4792.9  405.33  4799.6  405.33  5106.5  405.35
  5165.9  406.53  5235.3  411.43    5309  413.82  5432.5  416.95  5544.4  426.68
#Mann= 11 ,-1 , 0
  3940.5     .05       0  4112.4      .1       0  4175.1     .05       0
    4311      .1       0  4706.4     .05       0  4773.6    .033       0
  4779.6     .05       0  4792.9     .16       0  4799.6     .05       0
  5106.5      .1       0    5309     .05       0
Bank Sta=4773.6,4779.6
XS Rating Curve= 0 ,0
Exp/Cntr=0.3,0.1

Type RM Length L Ch R = 1 ,5772    ,526,526,526
BEGIN DESCRIPTION:
CHAMBERS CREEK 9.0
END DESCRIPTION:
XS GIS Cut Line= 4
      3541436.47     10553404.65      3541553.72     10552457.82
      3541328.84     10551998.37      3541118.05     10551725.37
#Sta/Elev= 30
  3936.2  435.32  4003.3  432.92  4023.8   434.4  4080.3  430.12  4130.7  427.88
  4365.2  423.01  4412.8  421.01  4428.7  419.29    4443  420.38  4467.4  420.04
    4572  414.84  4624.4  413.45  4671.7  409.14  4676.8  410.47  4745.3  405.54
  4830.7  405.24  4833.4  404.74  4836.7  405.24  5198.1  405.57  5264.1  405.53
  5334.6  409.11  5387.8  412.29  5404.3  412.16  5410.6  413.64  5511.4  421.95
  5518.4  421.26  5582.7  423.13  5653.4  427.69  5696.9  427.81  5746.7   430.2
#Mann= 9 ,-1 , 0
  3936.2     .05       0  4003.3     .16       0  4365.2     .05       0
  4467.4     .16       0    4572     .05       0  4830.7    .033       0
  4836.7     .05       0  5198.1     .16       0  5334.6     .05       0
Bank Sta=4830.7,4836.7
XS Rating Curve= 0 ,0
Exp/Cntr=0.3,0.1

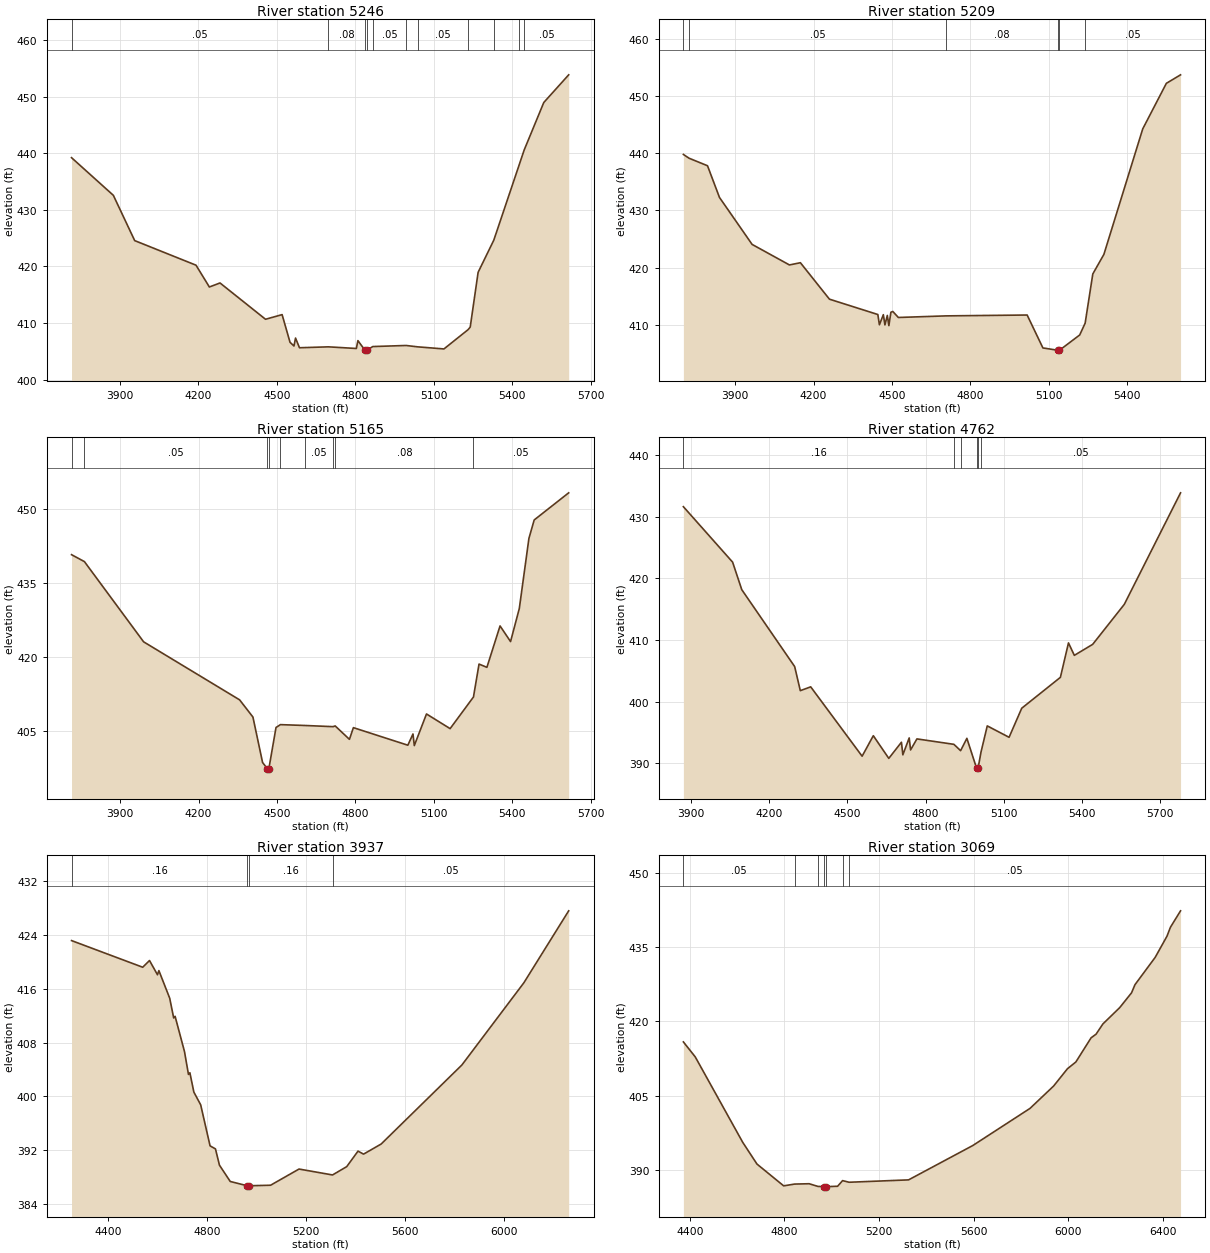
Type RM Length L Ch R = 1 ,5246    ,37,37,37
BEGIN DESCRIPTION:
CHAMBERS CREEK 8.02
END DESCRIPTION:
XS GIS Cut Line= 4
      3541560.61     10553418.52      3541702.97     10552713.65
      3542017.77     10552228.01      3542077.97     10551626.86
#Sta/Elev= 30
  3714.5  439.22  3874.5  432.57  3956.2  424.57  4190.8  420.23  4241.8  416.38
  4282.6  417.09  4456.7  410.68  4520.1   411.5  4550.4  406.62  4565.5  405.96
  4571.5  407.36  4586.6  405.65  4697.1  405.81  4804.2  405.52  4810.1  406.91
  4837.4   405.2  4840.2   404.7  4843.4   405.2  4867.1  405.86  4994.4  406.05
  5038.5  405.81  5139.3  405.44  5231.8  408.85  5239.8   409.3    5270  418.97
    5330  424.65  5428.2   438.1  5446.1  440.56  5521.2  448.96  5616.5  453.85
#Mann= 11 ,-1 , 0
  3714.5     .05       0  4697.1     .08       0  4837.4     .07       0
  4843.4     .08       0  4867.1     .05       0  4994.4     .08       0
  5038.5     .05       0  5231.8     .08       0    5330     .05       0
  5428.2     .16       0  5446.1     .05       0
Bank Sta=4837.4,4843.4
XS Rating Curve= 0 ,0
Exp/Cntr=0.3,0.1

Type RM Length L Ch R = 1 ,5209    ,44,44,44
BEGIN DESCRIPTION:
CHAMBERS CREEK 8.0
END DESCRIPTION:
XS GIS Cut Line= 4
      3541589.26     10553439.31      3541731.62     10552734.48
      3542046.42     10552248.85      3542106.62     10551647.65
#Sta/Elev= 30
  3702.2  439.82  3723.9  439.16  3794.5  437.84  3840.2  432.29  3965.1  424.05
  4107.9  420.45  4149.9  420.84  4260.9  414.45  4446.1  411.76  4452.1  409.96
  4467.2  411.73  4473.2  409.94  4482.4   411.6  4488.3  409.81  4496.1  412.16
  4503.5  412.29  4524.6  411.24  4707.7  411.52  5017.3  411.67  5077.6   405.9
  5134.9  405.49  5137.6  404.99  5140.9  405.49  5218.3  408.17  5239.2  410.24
  5268.5  418.87  5310.9   422.3  5459.5   444.3  5549.9  452.29  5604.2  453.78
#Mann= 6 ,-1 , 0
  3702.2     .16       0  3723.9     .05       0  4707.7     .08       0
  5134.9     .07       0  5140.9     .08       0  5239.2     .05       0
Bank Sta=5134.9,5140.9
XS Rating Curve= 0 ,0
Exp/Cntr=0.3,0.1

Type RM Length L Ch R = 1 ,5165    ,403,403,403
BEGIN DESCRIPTION:
CHAMBERS CREEK 8.03
END DESCRIPTION:
XS GIS Cut Line= 4
      3541638.73     10553441.96      3541781.09     10552737.08
       3542095.9     10552251.45      3542156.09     10551650.31
#Sta/Elev= 30
  3714.2  440.76  3763.6  439.35    3990   423.1  4357.3  411.34  4408.2  407.86
  4445.1  398.65  4463.2   397.4  4465.9   396.9  4469.2   397.4  4496.5  405.74
  4513.3  406.32  4606.5  406.15  4714.9  405.91  4722.8  406.06  4777.4  403.34
  4792.5  405.71  5000.9  402.15  5020.5  404.43  5025.6  402.08  5072.2  408.48
  5162.6  405.51  5251.9  411.92  5273.2  418.59  5303.3  417.93  5353.6  426.32
  5393.8  423.15  5427.3  429.85  5464.1  444.07  5484.2  447.79  5616.2  453.29
#Mann= 9 ,-1 , 0
  3714.2     .16       0  3763.6     .05       0  4463.2     .07       0
  4469.2     .05       0  4513.3     .16       0  4606.5     .05       0
  4714.9      .1       0  4722.8     .08       0  5251.9     .05       0
Bank Sta=4463.2,4469.2
XS Rating Curve= 0 ,0
Exp/Cntr=0.3,0.1

Type RM Length L Ch R = 1 ,4762    ,825,825,825
BEGIN DESCRIPTION:
CHAMBERS CREEK 7.0
END DESCRIPTION:
XS GIS Cut Line= 3
      3542035.57     10553477.72      3542528.63     10552241.59
      3542382.88     10551686.34
#Sta/Elev= 30
  3872.3  431.62  4060.9  422.62    4096  418.15  4298.7  405.67  4320.3  401.76
  4360.1  402.38  4557.1  391.12    4600  394.45  4659.3  390.77  4707.8  393.39
  4713.2  391.35  4737.5  394.09  4742.8  392.14  4767.1  393.93  4908.7  393.05
  4934.5  392.02  4958.5  394.02  4995.5   389.2  4998.3   388.7  5001.5   389.2
  5012.6  391.78  5036.6  396.04  5120.2  394.19  5168.7  398.91  5316.8  403.92
  5347.8  409.51  5370.2  407.49  5440.6  409.28  5561.7  415.77  5777.2  433.87
#Mann= 6 ,-1 , 0
  3872.3     .16       0  4908.7     .05       0  4934.5     .16       0
  4995.5     .07       0  5001.5     .16       0  5012.6     .05       0
Bank Sta=4995.5,5001.5
XS Rating Curve= 0 ,0
Exp/Cntr=0.3,0.1

Type RM Length L Ch R = 1 ,3937    ,868,868,868
BEGIN DESCRIPTION:
CHAMBERS CREEK 5.0
END DESCRIPTION:
XS GIS Cut Line= 2
      3543466.14     10553297.16      3542501.79     10551534.97
#Sta/Elev= 30
  4251.9  423.18  4539.5  419.21    4567  420.21  4599.2  418.09  4604.9  418.71
  4648.6   414.6  4664.7  411.66  4670.4   411.9  4708.3  406.66  4724.4  403.25
  4730.1   403.5  4746.2  400.62  4773.8  398.72  4811.7  392.61  4833.5  392.16
  4849.6  389.74  4893.2  387.31    4962  386.67  4964.7  386.17    4968  386.67
  5056.2  386.75  5171.1  389.16  5306.5  388.28  5363.9  389.52  5409.5  391.83
  5431.9  391.38  5503.1  392.89  5829.3  404.66  6079.7   416.9  6260.7  427.61
#Mann= 4 ,-1 , 0
  4251.9     .16       0    4962     .07       0    4968     .16       0
  5306.5     .05       0
Bank Sta=4962,4968
XS Rating Curve= 0 ,0
Exp/Cntr=0.3,0.1

Type RM Length L Ch R = 1 ,3069    ,845,845,845
BEGIN DESCRIPTION:
CHAMBERS CREEK 4.01
END DESCRIPTION:
XS GIS Cut Line= 3
       3543742.1     10552641.63      3543692.11     10552041.64
      3542492.08     10551141.62
#Sta/Elev= 30
  4373.1  415.85  4423.3  412.82  4623.9  395.56  4684.2  391.16  4797.1  386.75
    4843  387.11  4904.9  387.18  4941.7  386.64  4969.7  386.59  4972.4  386.09
  4975.7  386.59  5025.2  386.67  5046.2  387.81  5073.8  387.48  5325.2  387.96
    5597  394.91  5838.7  402.41  5938.7  406.94    5997  410.43  6032.5  411.79
    6097  416.68  6117.9  417.41    6147  419.49  6217.9  422.78  6267.9  425.77
  6282.5  427.42  6367.9  432.94  6417.9  437.23  6432.5  439.04  6475.2  442.35
#Mann= 7 ,-1 , 0
  4373.1     .05       0    4843      .1       0  4941.7     .16       0
  4969.7     .07       0  4975.7     .16       0  5046.2      .1       0
  5073.8     .05       0
Bank Sta=4969.7,4975.7
XS Rating Curve= 0 ,0
Exp/Cntr=0.3,0.1

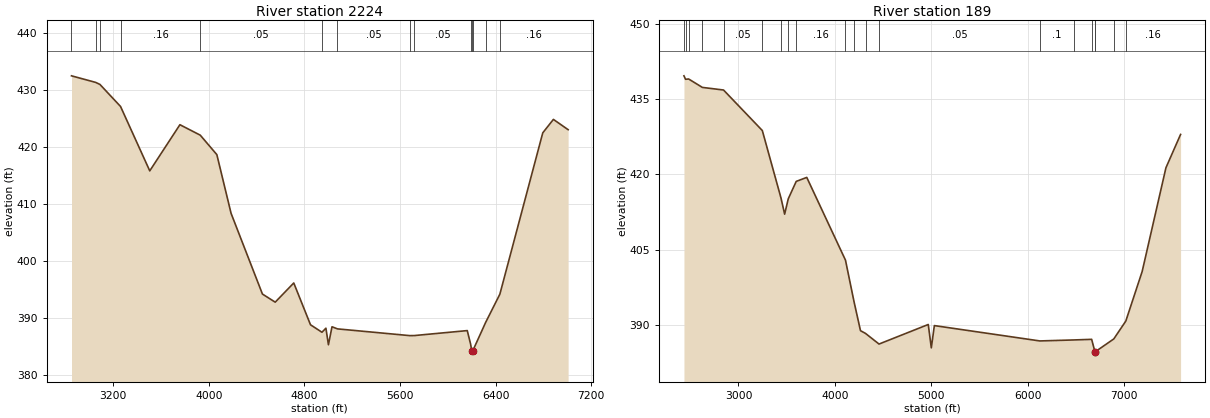
Type RM Length L Ch R = 1 ,2224    ,2035,2035,2035
BEGIN DESCRIPTION:
CHAMBERS CREEK 2.0
END DESCRIPTION:
XS GIS Cut Line= 4
      3543375.73      10554018.3       3544096.2      10552247.5
       3544365.3     10551848.19      3543905.22     10550146.77
#Sta/Elev= 30
  2850.8  432.42  3052.9  431.27  3088.5  430.92  3261.3  427.05  3505.7  415.78
    3758  423.86  3928.3  422.03  4067.1  418.62  4186.2  408.34  4448.5  394.21
  4555.5  392.79  4710.7  396.15  4850.8  388.83  4946.6  387.52  4979.8  388.23
  5000.8  385.33  5030.7  388.48  5076.5  388.11    5682  386.93  5719.2  386.94
  6162.5  387.81  6190.4  385.46  6200.9  384.19  6203.6  383.69  6206.9  384.19
  6316.1  389.23  6435.4  394.19  6794.4  422.44  6883.4  424.79  7006.6  422.99
#Mann= 14 ,-1 , 0
  2850.8      .1       0  3052.9     .16       0  3088.5      .1       0
  3261.3     .16       0  3928.3     .05       0  4946.6     .16       0
  5076.5     .05       0    5682      .1       0  5719.2     .05       0
  6190.4     .16       0  6200.9     .07       0  6206.9     .16       0
  6316.1     .05       0  6435.4     .16       0
Bank Sta=6200.9,6206.9
XS Rating Curve= 0 ,0
Exp/Cntr=0.3,0.1

Type RM Length L Ch R = 1 ,189     ,0,0,0
BEGIN DESCRIPTION:
CHAMBERS CREEK 1.01
END DESCRIPTION:
XS GIS Cut Line= 4
      3543176.03     10554686.77      3544547.59     10552846.46
      3544695.16     10552403.75       3544096.2     10550094.72
#Sta/Elev= 30
  2435.4  439.66  2452.2  438.97  2483.9  439.03  2626.3  437.35  2845.7  436.83
  3247.6  428.75  3441.1   415.3    3479  412.07  3516.6  415.13  3599.1   418.6
  3708.3   419.4  4109.7  402.89  4196.8  394.74  4265.1  388.83  4317.2  388.28
  4457.3  386.16  4967.6  390.06  4999.2   385.4  5030.8  389.84  6123.7  386.78
  6479.3  386.98    6661   387.1  6694.4  384.65  6697.2  384.15  6700.4  384.65
  6890.4  387.18  7015.2  390.75  7184.5  400.63  7430.9  421.32  7582.7  427.97
#Mann= 20 ,-1 , 0
  2435.4     .05       0  2452.2      .1       0  2483.9     .05       0
  2626.3      .1       0  2845.7     .05       0  3247.6     .05       0
  3441.1     .16       0  3516.6     .05       0  3599.1     .16       0
  4109.7     .05       0  4196.8     .08       0  4317.2     .05       0
  4457.3     .05       0  6123.7      .1       0  6479.3     .05       0
    6661     .16       0  6694.4     .03       0  6700.4     .16       0
  6890.4     .05       0  7015.2     .16       0
Bank Sta=6694.4,6700.4
XS Rating Curve= 0 ,0
Exp/Cntr=0.3,0.1

Chan Stop Cuts=-1
Use User Specified Reach Order=0
Composite Channel Slope=5