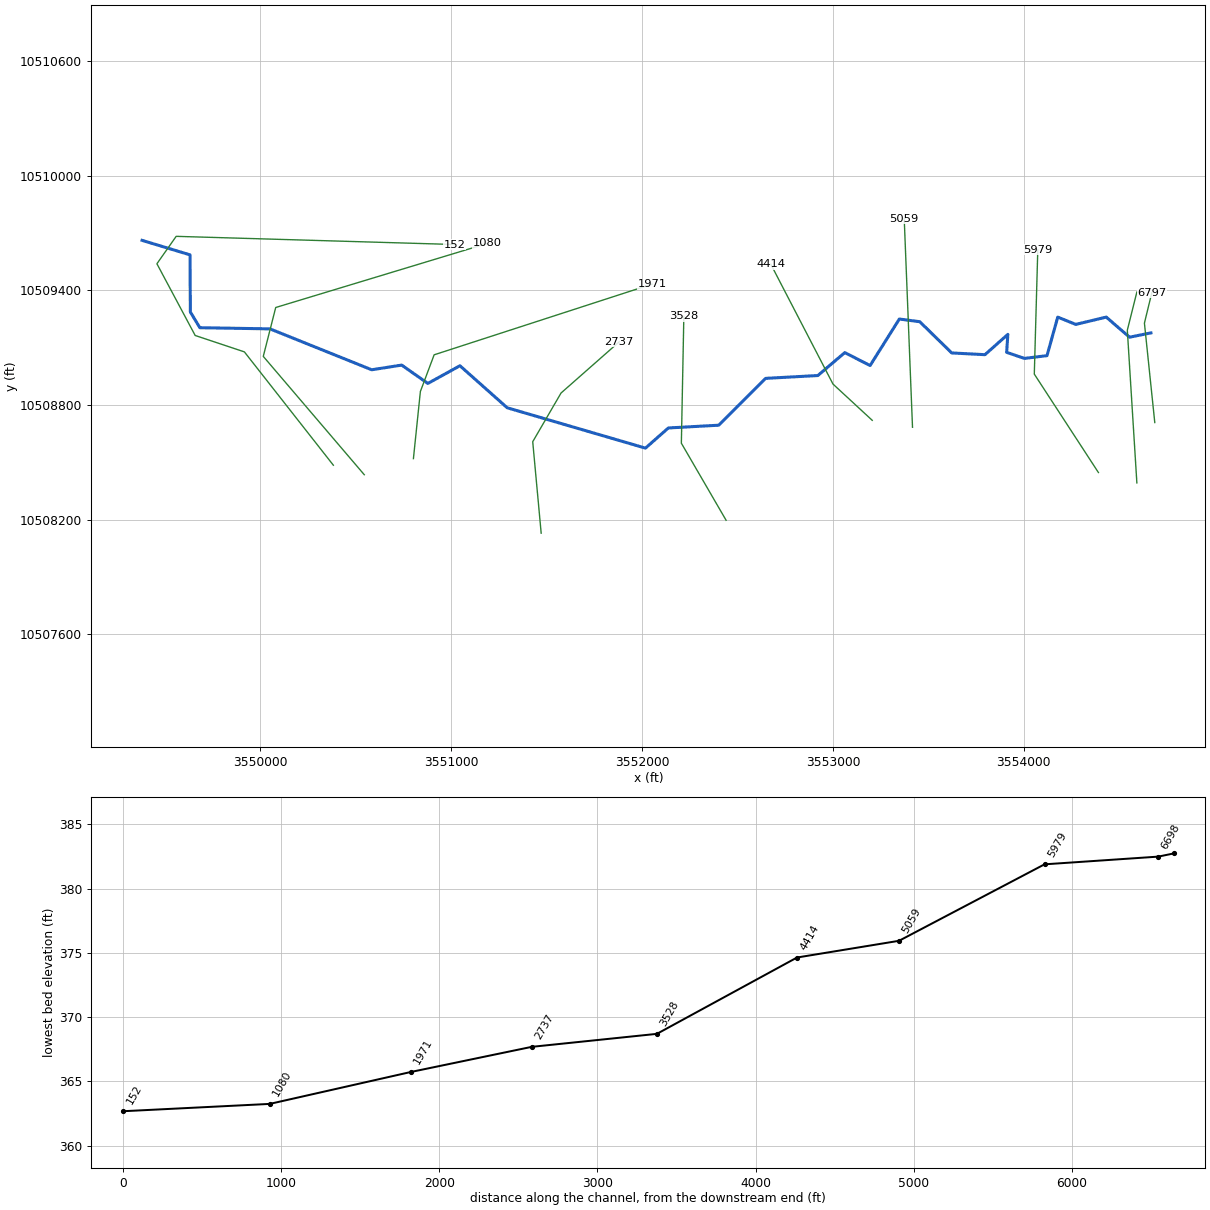
--- COOTS BRANCH.prj (project) ---

Proj Title=COOTS BRANCH Base Level Engineering
Current Plan=p01
Default Exp/Contr=0.3,0.1
English Units
Geom File=g01
Flow File=f01
Plan File=p01
Y Axis Title=Elevation
X Axis Title(PF)=Main Channel Distance
X Axis Title(XS)=Station
BEGIN DESCRIPTION:
COOTS BRANCH
END DESCRIPTION:
DSS Export Rating Curves= 0
DSS Export Rating Curve Sorted= 0
DSS Export Volume Flow Curves= 0
DXF OffsetX= 0
DXF OffsetY= 0
DXF ScaleX= 1
DXF ScaleY= 10

--- COOTS BRANCH.p01 (plan) ---

Plan Title=Multiple Run
Short Identifier=Multiple
Geom File=g01
Flow File=f01
Subcritical Flow
K Sum by GR= 0
Std Step Tol= 0.01
Critical Tol= 0.01
Num of Std Step Trials= 20
Max Error Tol= 0.3
Flow Tol Ratio= 0.001
Split Flow NTrial= 30
Split Flow Tol= 0.02
Split Flow Ratio= 0.02
Log Output Level= 0
Friction Slope Method= 1
Unsteady Friction Slope Method= 2
Unsteady Bridges Friction Slope Method= 1
Parabolic Critical Depth
Global Vel Dist=  1 , 1 , 1
Global Log Level= 0
CheckData=True
Encroach Param= -1, 0, 0, 0
BEGIN DESCRIPTION:
Multiple Run
END DESCRIPTION:

--- COOTS BRANCH.f01 (steady flow) ---

Flow Title=Multiple
Number of Profiles=7
Profile Names=10-year,25-year,50-year,1pct_min,100-year,1pct_plu,500-year
River Rch & RM= COOTS BRANCH,Reach-1,6797
    1007    1391    1710    1534    2075    2806    3048
River Rch & RM= COOTS BRANCH,Reach-1,6698
    1194    1657    2042    1834    2481    3355    3654
Boundary for River Rch & Prof#=COOTS BRANCH,Reach-1,1
Up Type=0
Dn Type=3
Dn Slope=0.005
Boundary for River Rch & Prof#=COOTS BRANCH,Reach-1,2
Up Type=0
Dn Type=3
Dn Slope=0.005
Boundary for River Rch & Prof#=COOTS BRANCH,Reach-1,3
Up Type=0
Dn Type=3
Dn Slope=0.005
Boundary for River Rch & Prof#=COOTS BRANCH,Reach-1,4
Up Type=0
Dn Type=3
Dn Slope=0.005
Boundary for River Rch & Prof#=COOTS BRANCH,Reach-1,5
Up Type=0
Dn Type=3
Dn Slope=0.005
Boundary for River Rch & Prof#=COOTS BRANCH,Reach-1,6
Up Type=0
Dn Type=3
Dn Slope=0.005
Boundary for River Rch & Prof#=COOTS BRANCH,Reach-1,7
Up Type=0
Dn Type=3
Dn Slope=0.005

--- COOTS BRANCH.g01 (geometry) ---

Geom Title=Existing Conditions
Program Version=4.10

River Reach=COOTS BRANCH    ,Reach-1
Reach XY= 30
      3554665.61     10509177.66      3554553.66     10509155.11
      3554431.77     10509260.34      3554272.03     10509222.18
      3554177.57     10509260.24      3554121.33     10509058.49
      3554002.92     10509043.98      3553909.95     10509075.81
      3553916.19     10509169.94      3553796.34     10509063.53
      3553622.14     10509072.62      3553454.79     10509236.28
      3553347.73     10509250.24      3553194.58     10509006.61
      3553062.07     10509074.42      3552920.86     10508954.29
      3552647.26     10508939.46      3552401.09     10508694.06
      3552137.64     10508679.61      3552017.77     10508573.98
      3551293.59     10508785.39      3551045.86     10509005.58
      3550877.87     10508912.81      3550740.91     10509008.95
      3550583.62     10508984.49      3550050.89     10509198.72
      3549683.31     10509204.87      3549633.67     10509287.26
      3549631.94     10509586.48       3549380.6     10509662.44

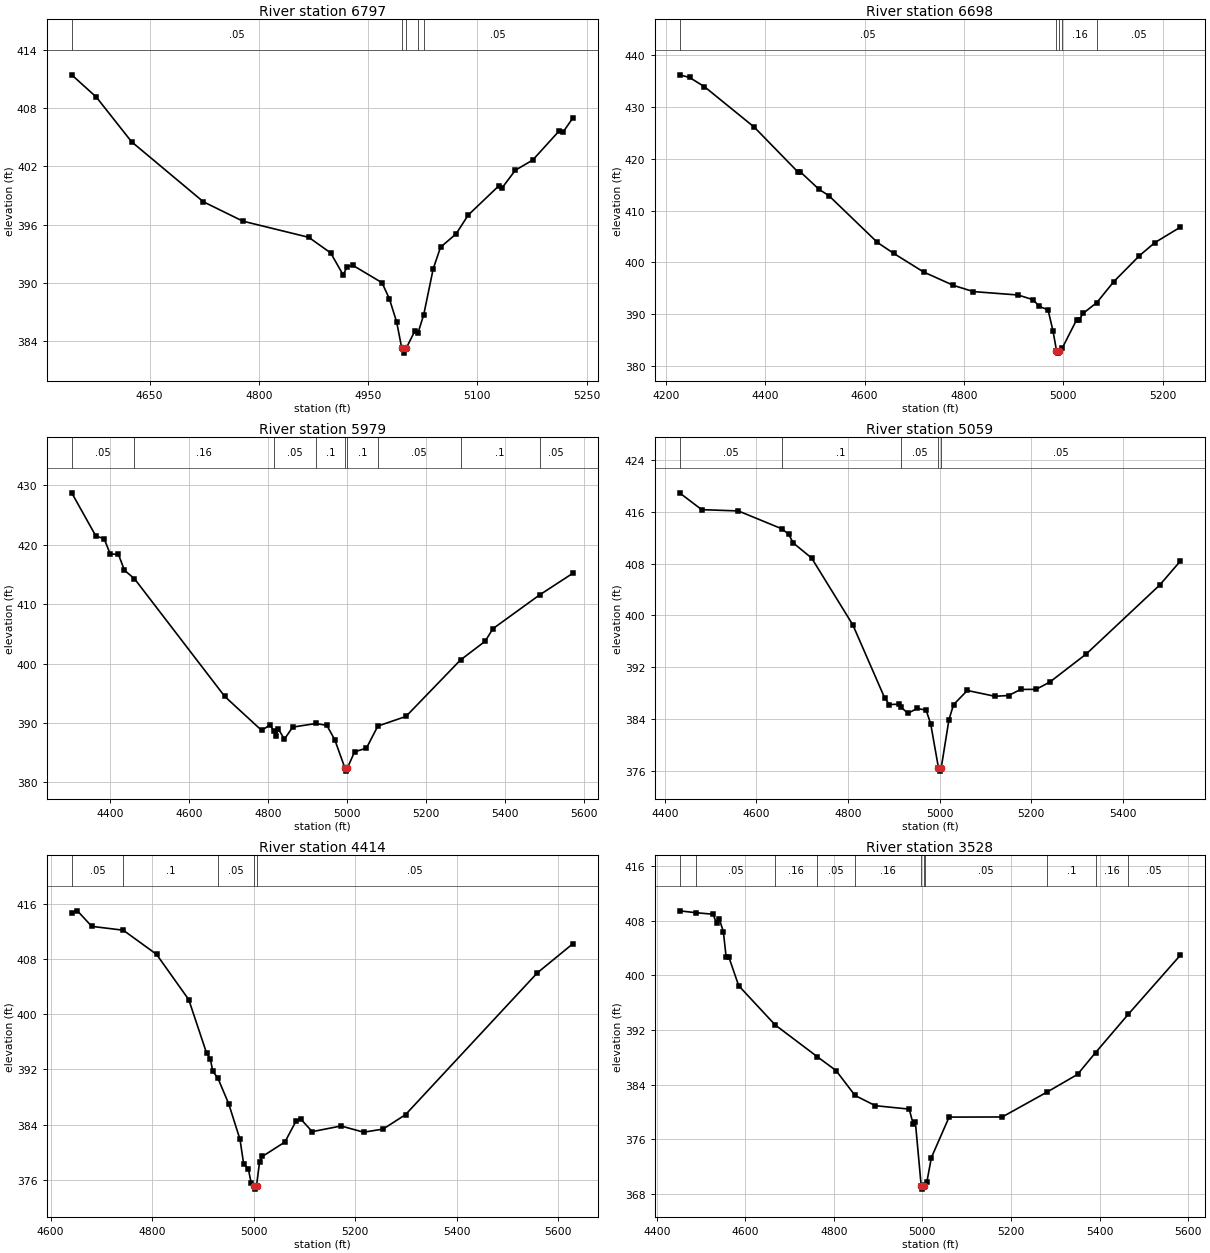
Type RM Length L Ch R = 1 ,6797    ,99,99,99
BEGIN DESCRIPTION:
COOTS BRANCH 12.1
END DESCRIPTION:
XS GIS Cut Line= 3
      3554685.94     10508708.02      3554631.69     10509228.87
      3554670.41     10509388.06
#Sta/Elev= 30
  4543.2  411.46    4577  409.16  4625.4  404.55  4723.9  398.36  4778.1  396.36
  4868.6  394.69  4898.7  393.08  4915.9   390.8    4921  391.64  4928.9  391.81
  4969.1  390.01  4979.2  388.36  4989.2  385.97  4996.3  383.24    4999  382.74
  5002.3  383.24  5014.5  385.06  5018.4  384.78  5026.4   386.7  5039.5  391.46
  5049.5  393.67  5070.9  395.05  5087.5  396.99  5129.2  399.98  5134.4  399.83
  5152.1  401.61  5176.1  402.67  5212.7   405.7  5217.8  405.56  5230.7  406.96
#Mann= 5 ,-1 , 0
  4543.2     .05       0  4996.3     .03       0  5002.3     .05       0
  5018.4     .16       0  5026.4     .05       0
Bank Sta=4996.3,5002.3
XS Rating Curve= 0 ,0
Exp/Cntr=0.3,0.1

Type RM Length L Ch R = 1 ,6698    ,719,719,719
BEGIN DESCRIPTION:
COOTS BRANCH 12.0
END DESCRIPTION:
XS GIS Cut Line= 3
      3554592.11     10508391.61      3554542.11     10509191.64
      3554592.12     10509391.69
#Sta/Elev= 30
  4227.7  436.22  4247.8  435.71  4277.8  433.93    4378  426.12  4465.7  417.49
  4470.7  417.49  4508.3  414.12  4528.3  412.88    4626  403.85  4658.6  401.75
  4718.7  398.16  4778.8  395.57  4818.9  394.37  4909.1  393.71  4939.1   392.8
  4951.6  391.51  4969.2  390.85  4979.2  386.78  4986.2  382.99    4989  382.49
  4992.2  382.99  4998.3  383.56  5026.8  388.93  5031.9  388.93  5039.6  390.16
  5067.2  392.23  5101.5  396.29    5153  401.29  5183.9  403.81  5235.5  406.81
#Mann= 5 ,-1 , 0
  4227.7     .05       0  4986.2     .07       0  4992.2     .05       0
  4998.3     .16       0  5067.2     .05       0
Bank Sta=4986.2,4992.2
XS Rating Curve= 0 ,0
Exp/Cntr=0.3,0.1

Type RM Length L Ch R = 1 ,5979    ,920,920,920
BEGIN DESCRIPTION:
COOTS BRANCH 11.0
END DESCRIPTION:
XS GIS Cut Line= 3
      3554390.73     10508446.11       3554054.8     10508961.73
      3554073.03     10509612.77
#Sta/Elev= 30
  4303.5  428.75  4364.5  421.48  4385.6  421.02  4400.7  418.47  4421.8  418.37
  4436.9  415.71  4462.3  414.28  4690.5  394.47    4784  388.74  4805.1  389.68
    4814  388.72  4820.2  387.83  4826.2  388.99  4841.3  387.26  4862.4   389.3
  4921.1  389.91  4948.8  389.59  4968.8  387.18  4994.6  382.39  4997.3  381.89
  5000.6  382.39  5018.9  385.14  5048.9  385.76  5077.8  389.48  5148.9   391.1
  5286.9  400.61    5349  403.75    5369  405.88  5486.7  411.55  5570.2  415.17
#Mann= 9 ,-1 , 0
  4303.5     .05       0  4462.3     .16       0    4814     .05       0
  4921.1      .1       0  4994.6     .07       0  5000.6      .1       0
  5077.8     .05       0  5286.9      .1       0  5486.7     .05       0
Bank Sta=4994.6,5000.6
XS Rating Curve= 0 ,0
Exp/Cntr=0.3,0.1

Type RM Length L Ch R = 1 ,5059    ,645,645,645
BEGIN DESCRIPTION:
COOTS BRANCH 9.0
END DESCRIPTION:
XS GIS Cut Line= 2
      3553416.73     10508683.28      3553373.34     10509776.82
#Sta/Elev= 30
  4431.9  418.96  4480.3  416.36  4560.4  416.16  4654.7  413.42  4670.1  412.58
  4680.5   411.2  4720.5  408.88  4810.6  398.54  4880.6  387.18  4890.6  386.23
  4910.6  386.29  4915.2  385.84  4931.3  384.88  4950.7  385.63  4970.7  385.37
  4980.7  383.25  4997.7  376.44  5000.5  375.94  5003.7  376.44  5020.7  383.92
  5030.7  386.22  5060.8  388.41  5120.8  387.51  5150.8  387.63  5177.5  388.57
  5210.9  388.58  5240.9   389.7    5321  394.07  5481.1   404.7  5526.3  408.41
#Mann= 5 ,-1 , 0
  4431.9     .05       0  4654.7      .1       0  4915.2     .05       0
  4997.7     .03       0  5003.7     .05       0
Bank Sta=4997.7,5003.7
XS Rating Curve= 0 ,0
Exp/Cntr=0.3,0.1

Type RM Length L Ch R = 1 ,4414    ,886,886,886
BEGIN DESCRIPTION:
COOTS BRANCH 8.0
END DESCRIPTION:
XS GIS Cut Line= 3
      3553205.83     10508719.55      3553000.11     10508909.65
      3552674.73     10509536.98
#Sta/Elev= 30
  4641.6  414.72  4652.8  414.97  4681.1  412.72  4743.2  412.16  4808.7  408.67
  4872.2   402.1  4907.4  394.34  4914.7  393.53  4919.5  391.73  4929.7  390.71
    4951  386.99  4973.2  381.84  4980.3  378.33  4989.6  377.57  4995.3  375.49
  4999.8  375.14  5002.6  374.64  5005.8  375.14  5011.8  378.62  5017.4  379.38
  5061.7  381.47  5083.8  384.53  5092.9   384.8  5115.5  382.97  5172.3  383.79
  5216.8  382.89  5255.1  383.34  5299.4  385.44  5559.3     406  5628.4  410.16
#Mann= 5 ,-1 , 0
  4641.6     .05       0  4743.2      .1       0  4929.7     .05       0
  4999.8     .03       0  5005.8     .05       0
Bank Sta=4999.8,5005.8
XS Rating Curve= 0 ,0
Exp/Cntr=0.3,0.1

Type RM Length L Ch R = 1 ,3528    ,791,791,791
BEGIN DESCRIPTION:
COOTS BRANCH 6.0
END DESCRIPTION:
XS GIS Cut Line= 3
      3552440.22      10508196.1      3552205.84     10508599.75
      3552218.86     10509263.86
#Sta/Elev= 30
  4451.6  409.43    4488  409.16  4527.4  408.93  4535.3  407.59  4541.1  408.27
  4550.5   406.4  4556.8  402.68  4562.6  402.72  4585.2  398.47  4667.4  392.74
  4763.1  388.06  4804.9  386.06  4847.9  382.41  4893.8  380.91  4970.3  380.41
  4979.1  378.24  4984.1  378.54  4997.3   369.2    5000   368.7  5003.3   369.2
  5005.2  369.37  5010.3  369.81  5020.3  373.31  5060.3  379.24  5180.3  379.26
  5282.5  382.94  5350.3  385.49  5391.2  388.69  5464.8  394.28  5582.6  402.94
#Mann= 11 ,-1 , 0
  4451.6      .1       0    4488     .05       0  4667.4     .16       0
  4763.1     .05       0  4847.9     .16       0  4997.3     .07       0
  5003.3     .16       0  5005.2     .05       0  5282.5      .1       0
  5391.2     .16       0  5464.8     .05       0
Bank Sta=4997.3,5003.3
XS Rating Curve= 0 ,0
Exp/Cntr=0.3,0.1

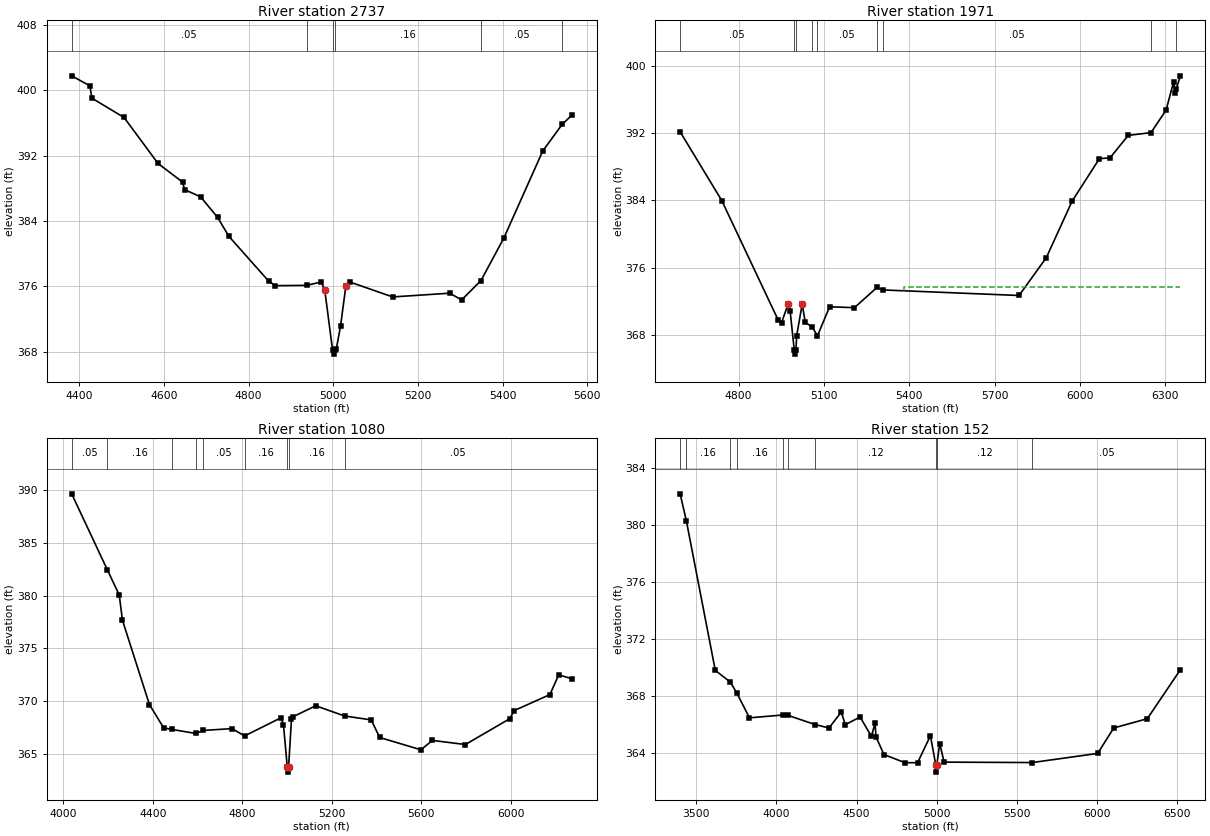
Type RM Length L Ch R = 1 ,2737    ,766,766,766
BEGIN DESCRIPTION:
COOTS BRANCH 4.0
END DESCRIPTION:
XS GIS Cut Line= 4
      3551471.47     10508128.38      3551427.19     10508607.57
      3551575.63     10508862.77      3551880.32     10509131.01
#Sta/Elev= 30
  4381.7  401.76  4424.6  400.54  4429.6  399.02  4505.5  396.66  4585.8  391.03
  4643.8  388.75  4648.8  387.82  4686.3  386.95  4726.4  384.44  4753.4   382.1
  4846.9  376.65  4862.5  376.07  4937.7  376.11  4971.8  376.53  4979.8  375.55
  4998.3  368.19  5001.1  367.69  5004.3  368.19  5007.1  368.32  5017.1  371.11
  5029.6  375.98  5038.6  376.53  5140.4  374.69    5275  375.15  5303.4  374.33
    5349  376.69    5403  381.89  5495.1  392.56  5541.3  395.84  5564.1  396.95
#Mann= 6 ,-1 , 0
  4381.7     .05       0  4937.7     .16       0  4998.3     .07       0
  5004.3     .16       0    5349     .05       0  5541.3     .16       0
Bank Sta=4979.8,5029.6
XS Rating Curve= 0 ,0
Exp/Cntr=0.3,0.1

Type RM Length L Ch R = 1 ,1971    ,891,891,891
BEGIN DESCRIPTION:
COOTS BRANCH 2.1
END DESCRIPTION:
XS GIS Cut Line= 4
      3550802.19       10508519.      3550838.65     10508870.59
      3550910.79     10509062.85      3552052.22      10509433.1
#Sta/Elev= 30
  4594.7  392.16  4741.2  383.98  4939.2   369.8  4951.4  369.46  4974.1  371.66
  4981.3  370.91    4996  366.23  4998.8  365.73    5002  366.23  5004.4  367.91
  5023.9  371.68  5034.7   369.5  5059.2  368.95  5077.6   367.9  5120.2  371.36
  5207.5  371.25  5286.6  373.65  5307.7  373.36  5786.3   372.7  5882.2   377.2
  5972.9  383.92  6068.8  388.97    6106  389.05    6170  391.73  6250.1  392.06
  6303.1  394.73  6329.8  398.11  6335.1  396.79    6339   397.3  6353.5  398.81
#Mann= 9 ,-1 , 0
  4594.7     .05       0    4996     .03       0    5002     .05       0
  5059.2     .16       0  5077.6     .05       0  5286.6     .16       0
  5307.7     .05       0  6250.1     .16       0    6339     .05       0
#XS Ineff= 2 , 0
                         5380.59          373.75
Permanent Ineff=
       F       F
Bank Sta=4974.1,5023.9
XS Rating Curve= 0 ,0
Exp/Cntr=0.3,0.1

Type RM Length L Ch R = 1 ,1080    ,928,928,928
BEGIN DESCRIPTION:
COOTS BRANCH 2.0
END DESCRIPTION:
XS GIS Cut Line= 4
      3550544.82     10508434.57      3550015.65      10509054.6
      3550080.84     10509310.69      3551188.65     10509646.16
#Sta/Elev= 30
  4036.6  389.67  4195.5  382.48  4249.2  380.07  4263.5  377.68  4384.3  369.66
  4447.9  367.45  4483.3  367.31  4591.9  366.92  4625.7  367.21  4753.2  367.38
    4810  366.69  4972.5  368.41  4983.6  367.74  5000.5  363.75  5003.2  363.25
  5006.5  363.75  5019.4  368.29  5024.5  368.49  5127.8  369.55  5256.7  368.58
  5375.7  368.21  5413.8  366.54    5598  365.37  5649.5  366.26  5796.9  365.87
  5994.5  368.31  6015.9   369.1  6174.8  370.61  6214.4  372.49  6273.5  372.11
#Mann= 9 ,-1 , 0
  4036.6     .05       0  4195.5     .16       0  4483.3      .1       0
  4591.9     .16       0  4625.7     .05       0    4810     .16       0
  5000.5     .07       0  5006.5     .16       0  5256.7     .05       0
Bank Sta=5000.5,5006.5
XS Rating Curve= 0 ,0
Exp/Cntr=0.3,0.1

Type RM Length L Ch R = 1 ,152     ,0,0,0
BEGIN DESCRIPTION:
COOTS BRANCH 1.0
END DESCRIPTION:
XS GIS Cut Line= 6
       3550382.8     10508484.48      3549916.67      10509078.2
      3549658.86     10509164.14      3549458.44     10509539.86
      3549559.43     10509683.48      3551017.71     10509640.72
#Sta/Elev= 30
  3399.1  382.16  3437.7  380.29  3618.4   369.8  3712.4  368.98  3753.9  368.19
  3831.7  366.48  4040.2  366.68  4072.8  366.65    4241  366.01  4327.4  365.77
  4404.2  366.89  4428.7     366  4521.5  366.54    4592  365.18  4614.4   366.1
  4620.8  365.14  4670.4  363.91    4801  363.34  4880.1  363.34  4959.8  365.23
  4993.5  363.18  4996.3  362.68  4999.5  363.18    5018  364.68  5045.4  363.38
  5595.4  363.35    6003  363.99    6103  365.77  6312.4  366.42  6518.8  369.85
#Mann= 10 ,-1 , 0
  3399.1     .05       0  3437.7     .16       0  3712.4      .1       0
  3753.9     .16       0  4040.2     .05       0  4072.8     .16       0
    4241     .12       0  4993.5     .07       0  4999.5     .12       0
  5595.4     .05       0
Bank Sta=4993.5,4999.5
XS Rating Curve= 0 ,0
Exp/Cntr=0.3,0.1

Chan Stop Cuts=-1
Use User Specified Reach Order=0
Composite Channel Slope=5