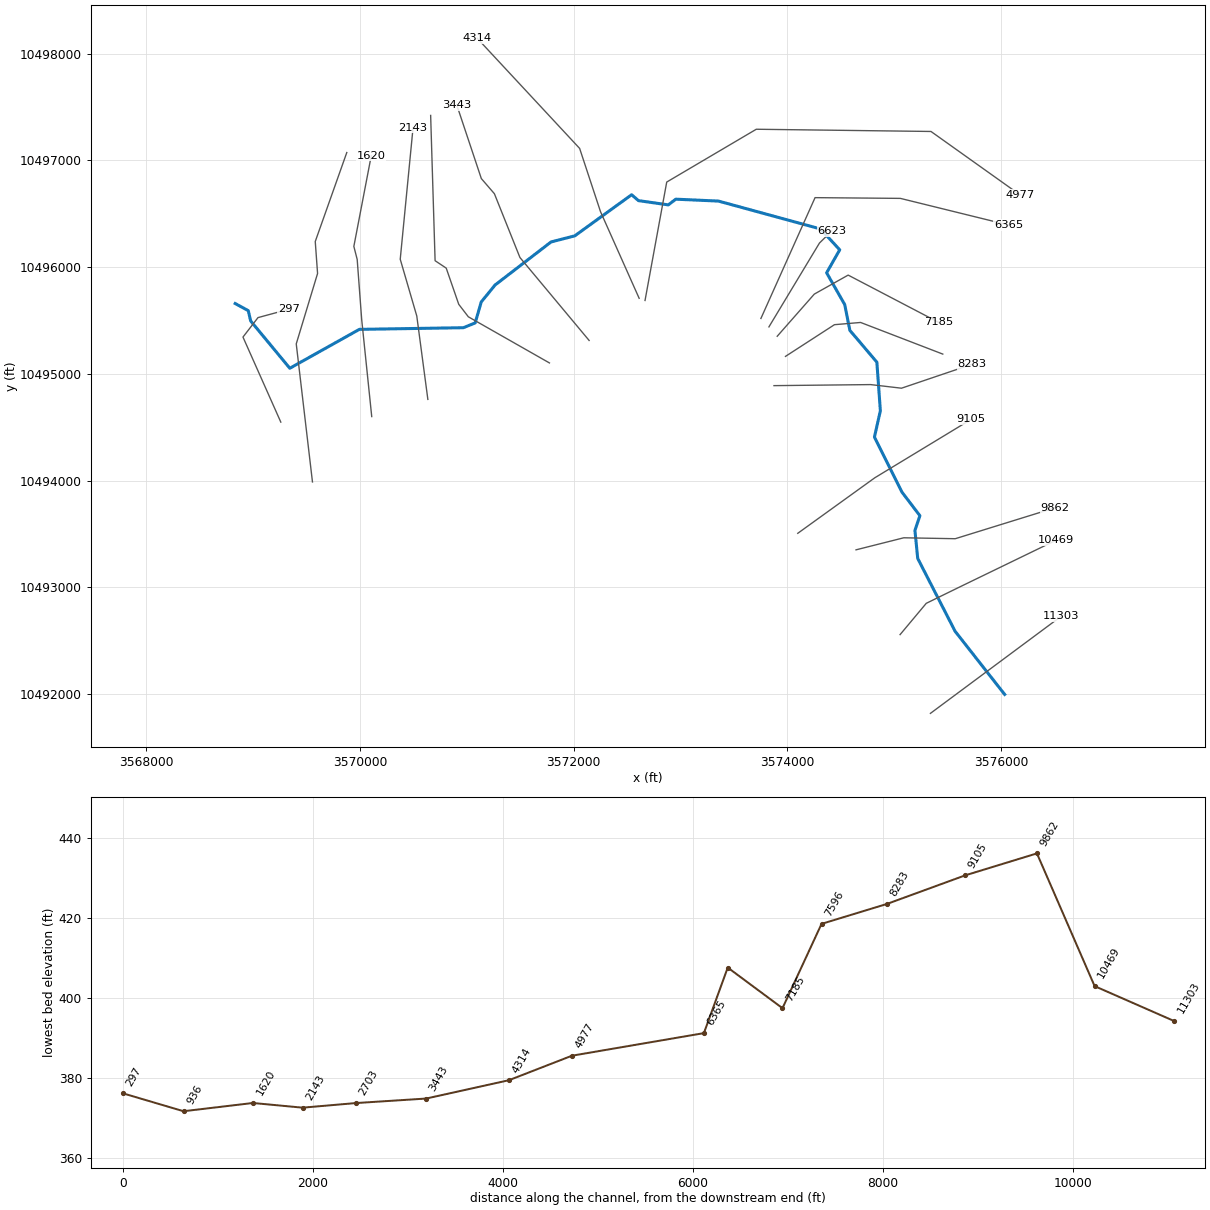
--- COTTONWOOD SPRING BRANCH.prj (project) ---

Proj Title=COTTONWOOD SPRING BRANCH Base Level Engineering
Current Plan=p01
Default Exp/Contr=0.3,0.1
English Units
Geom File=g01
Flow File=f01
Plan File=p01
Y Axis Title=Elevation
X Axis Title(PF)=Main Channel Distance
X Axis Title(XS)=Station
BEGIN DESCRIPTION:
COTTONWOOD SPRING BRANCH
END DESCRIPTION:
DSS Export Rating Curves= 0
DSS Export Rating Curve Sorted= 0
DSS Export Volume Flow Curves= 0
DXF OffsetX= 0
DXF OffsetY= 0
DXF ScaleX= 1
DXF ScaleY= 10

--- COTTONWOOD SPRING BRANCH.p01 (plan) ---

Plan Title=Multiple Run
Short Identifier=Multiple
Geom File=g01
Flow File=f01
Subcritical Flow
K Sum by GR= 0
Std Step Tol= 0.01
Critical Tol= 0.01
Num of Std Step Trials= 20
Max Error Tol= 0.3
Flow Tol Ratio= 0.001
Split Flow NTrial= 30
Split Flow Tol= 0.02
Split Flow Ratio= 0.02
Log Output Level= 0
Friction Slope Method= 1
Unsteady Friction Slope Method= 2
Unsteady Bridges Friction Slope Method= 1
Parabolic Critical Depth
Global Vel Dist=  1 , 1 , 1
Global Log Level= 0
CheckData=True
Encroach Param= -1, 0, 0, 0
BEGIN DESCRIPTION:
Multiple Run
END DESCRIPTION:

--- COTTONWOOD SPRING BRANCH.f01 (steady flow) ---

Flow Title=Multiple
Number of Profiles=7
Profile Names=10-year,25-year,50-year,1pct_min,100-year,1pct_plu,500-year
River Rch & RM= COTTONWOOD SPRIN,Reach-1,11303
    1237    1741    2167    1970    2665    3604    4016
River Rch & RM= COTTONWOOD SPRIN,Reach-1,10469
    1272    1779    2204    1992    2694    3643    4014
River Rch & RM= COTTONWOOD SPRIN,Reach-1,4977
    1817    2585    3239    2956    3998    5407    6078
River Rch & RM= COTTONWOOD SPRIN,Reach-1,2703
    2036    2909    3655    3343    4521    6114    6904
River Rch & RM= COTTONWOOD SPRIN,Reach-1,297
    2445    3532    4473    4121    5573    7537    8637
Boundary for River Rch & Prof#=COTTONWOOD SPRIN,Reach-1,1
Up Type=0
Dn Type=3
Dn Slope=0.005
Boundary for River Rch & Prof#=COTTONWOOD SPRIN,Reach-1,2
Up Type=0
Dn Type=3
Dn Slope=0.005
Boundary for River Rch & Prof#=COTTONWOOD SPRIN,Reach-1,3
Up Type=0
Dn Type=3
Dn Slope=0.005
Boundary for River Rch & Prof#=COTTONWOOD SPRIN,Reach-1,4
Up Type=0
Dn Type=3
Dn Slope=0.005
Boundary for River Rch & Prof#=COTTONWOOD SPRIN,Reach-1,5
Up Type=0
Dn Type=3
Dn Slope=0.005
Boundary for River Rch & Prof#=COTTONWOOD SPRIN,Reach-1,6
Up Type=0
Dn Type=3
Dn Slope=0.005
Boundary for River Rch & Prof#=COTTONWOOD SPRIN,Reach-1,7
Up Type=0
Dn Type=3
Dn Slope=0.005

--- COTTONWOOD SPRING BRANCH.g01 (geometry) ---

Geom Title=Existing Conditions
Program Version=4.10

River Reach=COTTONWOOD SPRIN,Reach-1
Reach XY= 30
      3576035.77     10491997.71      3575572.23     10492588.85
      3575221.67     10493272.18       3575195.8     10493534.72
      3575242.26      10493672.1      3575074.66     10493892.69
      3574816.66     10494408.67      3574872.13     10494655.73
      3574839.33     10495110.49      3574586.48     10495408.75
      3574538.46     10495650.13      3574368.97     10495947.86
      3574491.72     10496163.19      3574311.09     10496358.86
      3573356.33     10496619.77      3572957.15     10496637.53
      3572887.01     10496584.27      3572607.86     10496623.87
      3572543.54     10496679.12      3572011.15     10496293.96
      3571789.37     10496236.87      3571265.57     10495833.76
      3571135.78     10495674.83      3571078.77     10495478.11
      3570968.55      10495433.5      3569994.59     10495417.87
      3569343.66     10495053.52      3568977.34     10495496.64
      3568954.77     10495592.99      3568832.59     10495659.77

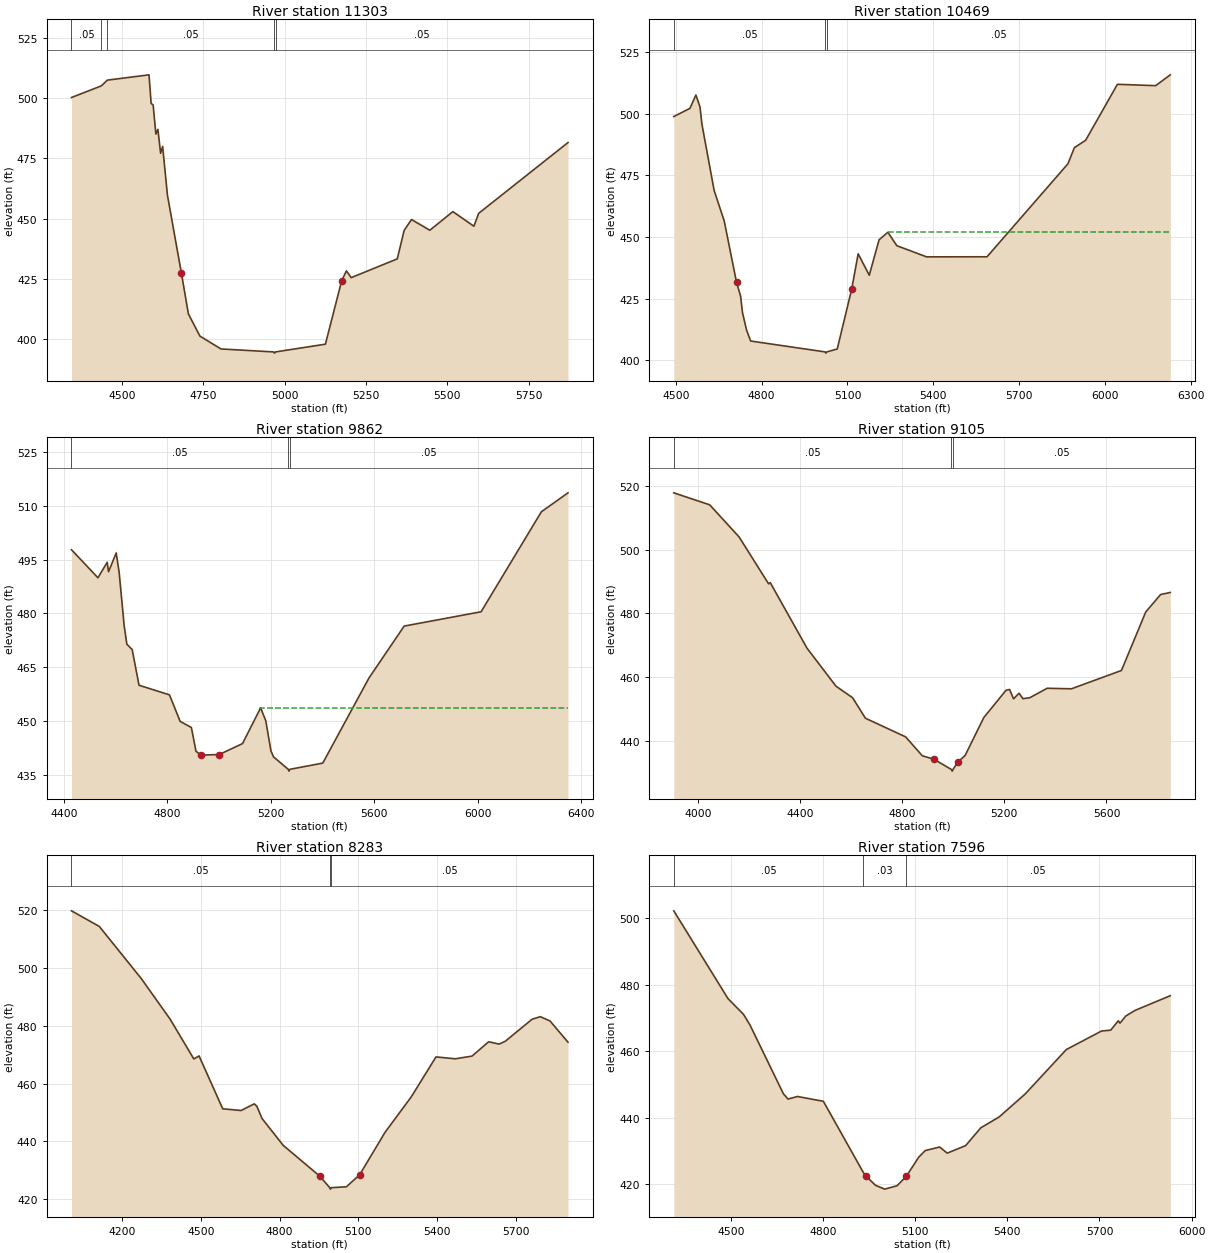
Type RM Length L Ch R = 1 ,11303   ,834,834,834
BEGIN DESCRIPTION:
COTTONWOOD SPRING BRANCH 11.01
END DESCRIPTION:
XS GIS Cut Line= 2
       3575340.7     10491820.33       3576566.6     10492731.44
#Sta/Elev= 30
  4344.1  500.27  4435.9   505.1  4454.4  507.48  4582.6  509.68  4589.1  497.85
  4595.3  497.15  4603.7  485.12  4609.9  487.06  4618.3  477.15  4624.5  480.01
  4639.2  459.85  4682.3  427.38  4703.8  410.51  4739.3  401.32    4804  396.01
  4965.8  394.78  4968.5  394.28  4971.8  394.78  5125.2  397.99  5175.3  424.31
  5189.9   428.4  5204.5  425.58  5346.3  433.36  5367.5   445.2  5390.1  449.69
  5446.4  445.23  5517.3  452.96    5582   446.9  5596.6  452.23  5871.5   481.6
#Mann= 5 ,-1 , 0
  4344.1     .05       0  4435.9      .1       0  4454.4     .05       0
  4965.8    .035       0  4971.8     .05       0
Bank Sta=4682.3,5175.3
XS Rating Curve= 0 ,0
Exp/Cntr=0.3,0.1

Type RM Length L Ch R = 1 ,10469   ,607,607,607
BEGIN DESCRIPTION:
COTTONWOOD SPRING BRANCH 11.0
END DESCRIPTION:
XS GIS Cut Line= 4
      3575056.74     10492558.21      3575301.83     10492851.37
      3575634.02     10493013.97      3576518.24     10493443.07
#Sta/Elev= 30
  4493.1  498.88  4549.6  502.21  4570.4  507.61  4584.8  502.74  4591.3  495.87
  4634.2  468.88  4669.4  456.53  4712.3   431.7  4726.6  426.09  4733.1  419.41
  4747.4  412.33  4761.7  407.88  5021.8  403.47  5024.5  402.97  5027.8  403.47
  5064.2  404.64  5114.8  428.94  5137.3  443.23  5176.1  434.56  5210.4  448.92
  5241.2  451.97  5272.4  446.53  5376.3     442  5587.5  442.03  5870.3  479.74
  5892.8  486.27  5932.1  489.26  6043.2  511.96  6176.6   511.4  6227.9   515.8
#Mann= 3 ,-1 , 0
  4493.1     .05       0  5021.8    .035       0  5027.8     .05       0
#XS Ineff= 2 , 0
                          5241.4          451.99
Permanent Ineff=
       F       F
Bank Sta=4712.3,5114.8
XS Rating Curve= 0 ,0
Exp/Cntr=0.3,0.1

Type RM Length L Ch R = 1 ,9862    ,757,757,757
BEGIN DESCRIPTION:
COTTONWOOD SPRING BRANCH 9.0
END DESCRIPTION:
XS GIS Cut Line= 4
      3574644.41      10493352.5      3575091.49     10493465.36
      3575573.26     10493456.67      3576507.59     10493746.49
#Sta/Elev= 30
  4428.6  497.73  4530.9  489.92  4566.8  494.23  4571.9   491.6  4601.6  496.83
    4613  491.46  4632.5  476.56  4642.8  471.46  4663.4  469.94  4689.9  460.02
  4807.8  457.34    4849  449.96  4892.5  448.26  4910.3  441.64  4930.3  440.57
  5000.3  440.74  5090.4  443.78  5160.4  453.73  5180.4  450.14  5200.4  441.75
  5210.4  440.08  5267.4  436.62  5270.1  436.12  5273.4  436.62  5400.9  438.35
  5579.7  462.04  5715.9  476.48  6013.5  480.46  6246.8  508.29  6349.8  513.56
#Mann= 3 ,-1 , 0
  4428.6     .05       0  5267.4    .035       0  5273.4     .05       0
#XS Ineff= 2 , 0
                         5158.91          453.71
Permanent Ineff=
       F       F
Bank Sta=4930.3,5000.3
XS Rating Curve= 0 ,0
Exp/Cntr=0.3,0.1

Type RM Length L Ch R = 1 ,9105    ,822,822,822
BEGIN DESCRIPTION:
COTTONWOOD SPRING BRANCH 8.0
END DESCRIPTION:
XS GIS Cut Line= 3
      3574098.88     10493507.22        3574820.     10494027.44
      3575722.18     10494574.95
#Sta/Elev= 30
  3905.6  517.77  4046.4  514.01  4161.7  503.92    4277  489.26  4283.2  489.67
  4427.5  469.11  4540.8  457.22  4605.8  453.61  4656.1  447.19  4813.7  441.34
  4879.1  435.42  4924.1  434.36  4993.1  431.12  4995.8  430.62  4999.1  431.12
  5019.1  433.56  5046.3  435.48  5119.9  447.41  5206.7  455.93  5220.7  456.19
  5236.2  453.25  5257.6  455.02  5273.1   453.3  5300.2  453.62    5368  456.57
    5463   456.4  5658.8  462.14  5753.8  480.44  5811.9  485.91  5850.1  486.57
#Mann= 3 ,-1 , 0
  3905.6     .05       0  4993.1     .03       0  4999.1     .05       0
Bank Sta=4924.1,5019.1
XS Rating Curve= 0 ,0
Exp/Cntr=0.3,0.1

Type RM Length L Ch R = 1 ,8283    ,687,687,687
BEGIN DESCRIPTION:
COTTONWOOD SPRING BRANCH 7.0
END DESCRIPTION:
XS GIS Cut Line= 4
      3573876.26      10494890.7      3574780.96     10494900.57
      3575069.79     10494866.64      3575728.29     10495089.94
#Sta/Elev= 30
  4007.3  519.84  4113.2  514.44  4273.2  496.37  4383.2   482.3  4473.2  468.56
  4493.2   469.6  4583.2   451.3  4653.2  450.71  4703.2  453.01  4713.2  452.19
  4733.2  447.92  4813.2  438.68  4953.5  427.93  4990.8  423.99  4993.5  423.49
  4996.8  423.99  5054.2   424.3  5104.5  428.43  5201.5  443.17    5301  455.39
  5395.4  469.26  5469.3  468.61  5532.7  469.55    5596  474.51  5635.9   473.7
  5659.4  474.68  5761.5  482.32  5792.9  483.19  5829.6  481.72  5898.2  474.36
#Mann= 3 ,-1 , 0
  4007.3     .05       0  4990.8     .03       0  4996.8     .05       0
Bank Sta=4953.5,5104.5
XS Rating Curve= 0 ,0
Exp/Cntr=0.3,0.1

Type RM Length L Ch R = 1 ,7596    ,411,411,411
BEGIN DESCRIPTION:
COTTONWOOD SPRING BRANCH 7.09
END DESCRIPTION:
XS GIS Cut Line= 4
      3573983.94     10495164.86      3574442.31     10495461.76
       3574687.1     10495482.59      3575456.32     10495186.34
#Sta/Elev= 30
  4314.4   502.3  4490.9  475.87  4541.5  471.12  4562.6   467.9  4671.4  447.19
  4686.5  445.63  4716.9  446.41  4801.3  444.96  4930.6  423.66  4940.6  422.38
  4970.7  419.69  5000.6  418.52    5041  419.53  5071.1  422.35  5111.6  428.13
    5133  430.13  5179.8   431.2  5204.4  429.35  5264.4  431.62  5313.7  436.98
  5373.6  440.26  5458.2  447.17  5592.1  460.54  5706.7  466.12  5736.7  466.38
  5761.3  469.21  5766.7  468.47  5785.9  470.66  5815.9  472.33  5930.5  476.75
#Mann= 3 ,-1 , 0
  4314.4     .05       0  4930.6     .03       0  5071.1     .05       0
Bank Sta=4940.6,5071.1
XS Rating Curve= 0 ,0
Exp/Cntr=0.3,0.1

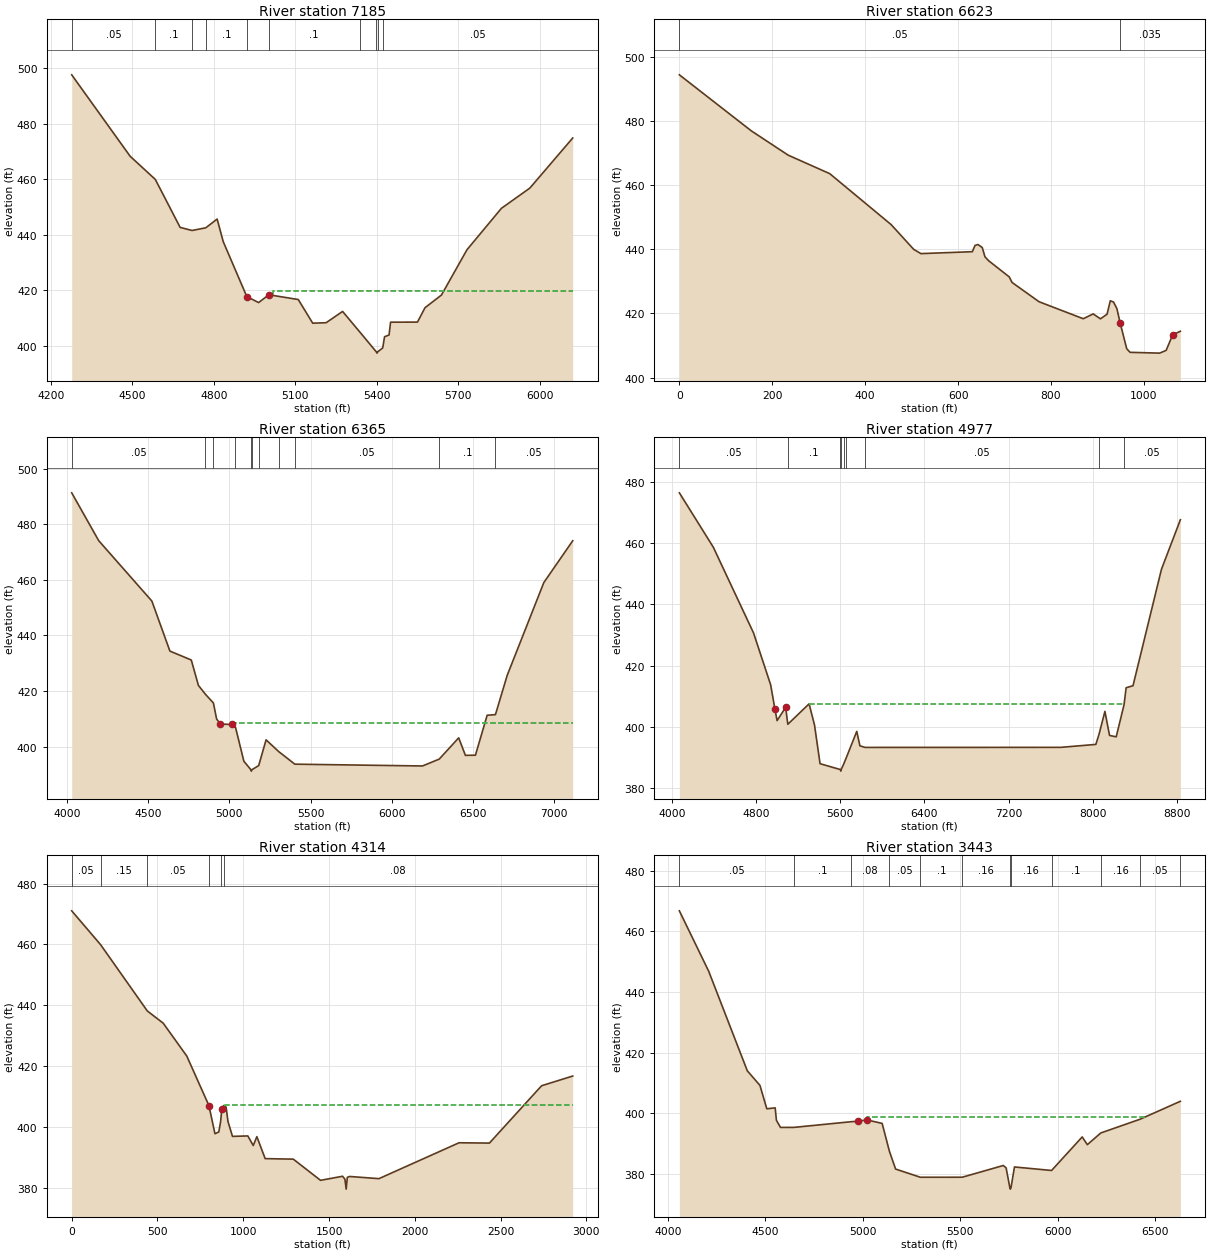
Type RM Length L Ch R = 1 ,7185    ,576,576,576
BEGIN DESCRIPTION:
COTTONWOOD SPRING BRANCH 4.0
END DESCRIPTION:
XS GIS Cut Line= 4
      3573906.57     10495353.34      3574253.82     10495748.34
      3574570.66     10495926.29      3575417.03     10495483.57
#Sta/Elev= 30
  4276.4  497.56  4491.5  468.27  4584.2  459.94  4675.6  442.68  4719.6  441.57
    4770  442.54  4811.8  445.68  4834.4  437.52  4921.1  417.79  4964.5  415.65
  5002.1  418.45  5110.5  416.74  5163.7  408.23  5213.1   408.4  5273.7  412.46
  5336.4  405.14  5397.5  397.96  5400.3  397.46  5403.5  397.96  5421.4  399.34
  5428.2  403.35  5444.7  403.97  5450.3  408.59  5549.4  408.62  5577.1  413.79
  5637.7  418.36  5731.6  434.64  5858.4  449.54  5963.1  456.82  6120.9  474.83
#Mann= 10 ,-1 , 0
  4276.4     .05       0  4584.2      .1       0  4719.6     .05       0
    4770      .1       0  4921.1     .05       0  5002.1      .1       0
  5336.4     .16       0  5397.5    .035       0  5403.5     .16       0
  5421.4     .05       0
#XS Ineff= 2 , 0
       0                 5017.05       0  419.65
Permanent Ineff=
       F       T
Bank Sta=4921.1,5002.1
XS Rating Curve= 0 ,0
Exp/Cntr=0.3,0.1

Type RM Length L Ch R = 1 ,6623    ,251,251,251
XS GIS Cut Line= 3
      3573828.97     10495441.16      3574302.06     10496226.75
      3574417.51     10496339.82
#Sta/Elev= 30
       0  494.33   154.8  476.87   234.4  469.28   323.7  463.53   455.8  447.66
   504.4  439.94   519.9  438.61   630.6  439.21   636.4  441.15   642.6  441.45
   651.9  440.52   657.8  437.61   665.9  436.37   710.2  431.34     716  429.64
   774.3  423.61   869.4  418.32   890.8  419.82   906.3  418.29   920.6  419.72
   927.6  423.91   934.6  423.51   941.8  421.46   948.8  417.01   962.9  408.98
   970.1  407.85  1033.7   407.6  1047.8  408.45  1061.9  413.32  1078.4  414.41
#Mann= 2 ,-1 , 0
       0     .05       0   948.8    .035       0
Bank Sta=948.8,1061.9
XS Rating Curve= 0 ,0
Exp/Cntr=0.3,0.1

Type RM Length L Ch R = 1 ,6365    ,1388,1388,1388
BEGIN DESCRIPTION:
COTTONWOOD SPRING BRANCH 2.0
END DESCRIPTION:
XS GIS Cut Line= 4
      3573753.87     10495520.01      3574260.82     10496651.97
      3575059.43     10496645.03      3576073.32     10496395.03
#Sta/Elev= 30
    4030  491.26  4196.1  474.07  4523.3  452.36  4634.4  434.37  4765.9  431.17
  4809.7  422.05  4852.4  418.89    4902  415.73  4921.7  409.98  4944.9  408.16
  5014.5  407.99  5037.9  407.02  5089.5  394.78  5132.9  391.73  5135.7  391.23
  5138.9  391.73  5180.8  393.23  5226.1  402.48  5304.3  398.23  5403.2  393.73
  6188.8  393.08  6291.9  395.56  6411.6   403.2  6452.8   396.9  6514.6  396.95
  6586.7  411.31  6637.7  411.54  6710.3  425.69  6935.5  459.01  7113.2  474.02
#Mann= 11 ,-1 , 0
    4030     .05       0  4852.4      .1       0    4902     .05       0
  5037.9     .16       0  5132.9    .035       0  5138.9     .16       0
  5180.8      .1       0  5304.3     .16       0  5403.2     .05       0
  6291.9      .1       0  6637.7     .05       0
#XS Ineff= 2 , 0
       0                 5028.86       0  408.44
Permanent Ineff=
       F       T
Bank Sta=4944.9,5014.5
XS Rating Curve= 0 ,0
Exp/Cntr=0.3,0.1

Type RM Length L Ch R = 1 ,4977    ,663,663,663
BEGIN DESCRIPTION:
COTTONWOOD SPRING BRANCH 2.21
END DESCRIPTION:
XS GIS Cut Line= 5
      3572669.02     10495688.61      3572872.14     10496797.94
      3573710.68     10497292.73       3575346.1      10497271.9
       3576178.3     10496678.95
#Sta/Elev= 30
  4072.8  476.42  4395.7  458.64  4777.4  430.68    4940  413.75  4980.7  405.76
    5001  402.08  5082.3   406.4  5102.8  400.88    5305  407.55  5356.4  400.65
  5409.1  388.02  5603.2  386.09  5605.9  385.59  5609.2  386.09  5632.2  387.78
  5654.7  389.66  5757.9  398.56  5787.6  393.85  5836.6  393.33  7695.8  393.35
  8028.8  394.31  8058.9   397.6  8114.9  405.09  8159.1  397.23  8222.3  396.79
  8296.5  407.24  8316.5  412.81  8381.7  413.46  8652.1  451.47  8831.6  467.64
#Mann= 9 ,-1 , 0
  4072.8     .05       0  5102.8      .1       0  5603.2     .03       0
  5609.2      .1       0  5632.2     .16       0  5654.7      .1       0
  5836.6     .05       0  8058.9     .16       0  8296.5     .05       0
#XS Ineff= 1 ,-1
 5303.54 8299.81  407.61
Permanent Ineff=
       T
Bank Sta=4980.7,5082.3
XS Rating Curve= 0 ,0
Exp/Cntr=0.3,0.1

Type RM Length L Ch R = 1 ,4314    ,871,871,871
BEGIN DESCRIPTION:
COTTONWOOD SPRING BRANCH 2.22
END DESCRIPTION:
XS GIS Cut Line= 4
      3572614.03     10495708.91      3572252.26     10496520.65
      3572056.87     10497113.18      3571098.54     10498144.43
#Sta/Elev= 30
       0  471.07   168.5  459.92   440.9   438.1   533.4  434.09   670.8  423.27
   799.9  406.96     835   397.7   857.3  398.28   867.9  401.64   875.1  405.92
   886.5  406.99   900.1  406.45   910.8  401.75   937.1  396.83  1026.6  396.98
  1058.2  393.82  1079.3  396.74  1127.7  389.51  1291.7  389.34  1450.5  382.36
  1578.8  383.71  1592.5  382.77  1599.8  379.47  1606.7  383.36  1620.8  383.63
  1790.9  382.92    2258  394.73  2434.9  394.62  2739.1   413.5  2920.4  416.69
#Mann= 6 ,-1 , 0
       0     .05       0   168.5     .15       0   440.9     .05       0
   799.9     .08       0   867.9     .07       0   886.5     .08       0
#XS Ineff= 2 , 0
       0                  893.18       0  407.01
Permanent Ineff=
       F       T
Bank Sta=799.9,875.1
XS Rating Curve= 0 ,0
Exp/Cntr=0.3,0.1

Type RM Length L Ch R = 1 ,3443    ,740,740,740
BEGIN DESCRIPTION:
COTTONWOOD SPRING BRANCH 2.23
END DESCRIPTION:
XS GIS Cut Line= 5
      3572145.73     10495313.93        3571498.     10496091.07
      3571258.92     10496688.77      3571136.52      10496830.7
      3570906.57     10497520.55
#Sta/Elev= 30
  4059.9  466.81  4210.3  446.86  4408.4  413.97  4473.2  409.16  4508.4  401.43
  4551.3  401.73  4557.8  397.62  4578.7  395.27    4647  395.28  4940.2  397.15
    4977   397.3  5019.9  397.76    5100  396.61  5137.5  387.37  5169.1  381.52
  5296.2  378.81  5510.8  378.82  5721.9   382.7  5736.2  381.89  5755.1  375.39
  5757.8  374.89  5761.1  375.39  5778.9  382.21  5969.2  381.05  6126.3  392.13
  6152.7  389.58  6221.8  393.44  6424.2     398  6628.4  403.86  6629.9  403.89
#Mann= 12 ,-1 , 0
  4059.9     .05       0    4647      .1       0  4940.2     .08       0
  5137.5     .05       0  5296.2      .1       0  5510.8     .16       0
  5755.1     .07       0  5761.1     .16       0  5969.2      .1       0
  6221.8     .16       0  6424.2     .05       0  6628.4     .16       0
#XS Ineff= 1 ,-1
 5024.43 6442.61  398.75
Permanent Ineff=
       T
Bank Sta=4977,5019.9
XS Rating Curve= 0 ,0
Exp/Cntr=0.3,0.1

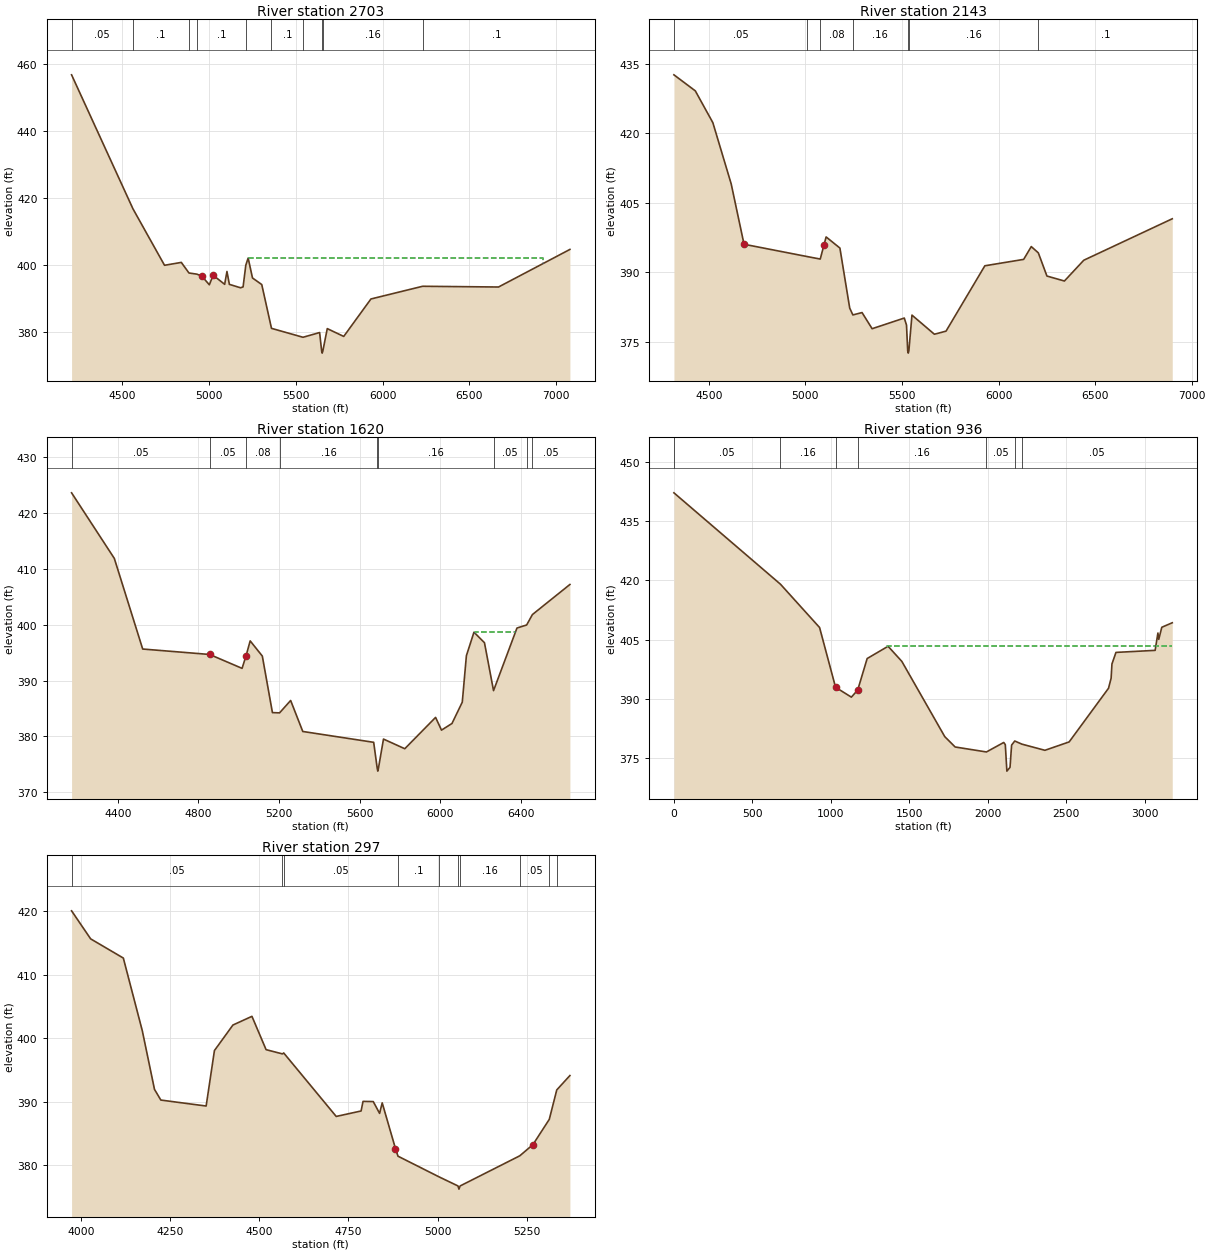
Type RM Length L Ch R = 1 ,2703    ,560,560,560
BEGIN DESCRIPTION:
COTTONWOOD SPRING BRANCH 2.24
END DESCRIPTION:
XS GIS Cut Line= 6
      3571774.05     10495103.39      3571014.93     10495535.69
      3570925.08     10495652.88      3570807.96     10495991.64
       3570703.8     10496061.08      3570662.13     10497422.17
#Sta/Elev= 30
  4211.3  456.77  4564.6  416.78    4746  399.96  4842.5  400.82  4886.6  397.66
  4932.9  397.31  4960.7   396.7  5003.9  394.14  5025.5     397  5091.9  394.28
    5105  398.11    5119  394.27  5183.4  393.25  5197.9  393.51  5213.6     400
    5227  402.12    5252  396.18  5305.3  394.21  5361.3  381.15  5542.6  378.49
  5638.1   379.9  5650.1  374.26  5652.8  373.76  5656.1  374.26  5682.2  381.07
  5776.8  378.74  5933.3  389.91  6230.6   393.7  6667.2  393.48  7077.9  404.69
#Mann= 10 ,-1 , 0
  4211.3     .05       0  4564.6      .1       0  4886.6     .05       0
  4932.9      .1       0  5213.6     .08       0  5361.3      .1       0
  5542.6     .16       0  5650.1     .07       0  5656.1     .16       0
  6230.6      .1       0
#XS Ineff= 1 ,-1
 5226.99  6923.3  402.05
Permanent Ineff=
       T
Bank Sta=4960.7,5025.5
XS Rating Curve= 0 ,0
Exp/Cntr=0.3,0.1

Type RM Length L Ch R = 1 ,2143    ,523,523,523
BEGIN DESCRIPTION:
COTTONWOOD SPRING BRANCH 2.25
END DESCRIPTION:
XS GIS Cut Line= 4
      3570636.02     10494761.84      3570532.32     10495543.07
      3570377.41     10496074.97      3570497.46     10497307.45
#Sta/Elev= 30
  4319.1  432.58  4429.9  429.12  4520.7  422.27  4615.7  409.07  4682.1  396.07
  5007.6  393.43  5076.8  392.88  5095.7  395.86  5107.2  397.65  5178.6  395.25
  5229.3  382.32  5245.7  380.84  5293.2  381.35  5345.4  377.87  5511.9  380.17
  5523.4  378.67  5529.7  373.11  5532.5  372.61  5535.7  373.11  5551.7   380.8
  5667.9  376.68  5728.2  377.35  5929.1  391.43  6130.1  392.81  6169.5  395.57
  6206.1  394.21  6250.6  389.22  6341.1  388.15  6441.5  392.63  6899.5  401.56
#Mann= 7 ,-1 , 0
  4319.1     .05       0  5007.6      .1       0  5076.8     .08       0
  5245.7     .16       0  5529.7    .033       0  5535.7     .16       0
  6206.1      .1       0
#XS Ineff= 2 , 0
       0                 5111.49       0  392.78
Permanent Ineff=
       F       T
Bank Sta=4682.1,5095.7
XS Rating Curve= 0 ,0
Exp/Cntr=0.3,0.1

Type RM Length L Ch R = 1 ,1620    ,730,730,730
BEGIN DESCRIPTION:
COTTONWOOD SPRING BRANCH 2.26
END DESCRIPTION:
XS GIS Cut Line= 5
      3570110.59     10494600.87      3570016.84     10495507.12
       3569974.4     10496073.47      3569943.15     10496194.99
      3570106.34     10497045.68
#Sta/Elev= 30
  4171.4  423.61  4383.3  411.87    4524  395.64  4855.8  394.67  5016.7  392.18
  5036.8  394.47  5056.9   397.1  5117.1  394.38  5167.2  384.26  5202.6  384.21
  5257.5  386.43  5317.7  380.88  5669.2  378.94  5686.8  374.28  5689.6  373.78
  5692.8  374.28  5717.8  379.52  5823.4  377.79  5976.1   383.4  6005.4  381.12
  6057.4  382.31  6108.5  386.13  6128.9  394.45  6166.5  398.66  6218.5  396.77
  6263.5  388.19  6379.6   399.4  6427.7  399.95  6456.1  401.81  6642.1   407.2
#Mann= 9 ,-1 , 0
  4171.4     .05       0  4855.8     .05       0  5036.8     .08       0
  5202.6     .16       0  5686.8     .07       0  5692.8     .16       0
  6263.5     .05       0  6427.7     .16       0  6456.1     .05       0
#XS Ineff= 2 ,-1
 5055.85 6150.17 392.117  6173.3 6374.43  398.69
Permanent Ineff=
       T       F
Bank Sta=4855.8,5036.8
XS Rating Curve= 0 ,0
Exp/Cntr=0.3,0.1

Type RM Length L Ch R = 1 ,936     ,640,640,640
XS GIS Cut Line= 5
      3569555.83     10493988.45      3569403.92     10495281.85
      3569603.57     10495941.57      3569581.87     10496241.05
      3569877.01     10497074.39
#Sta/Elev= 30
       0  442.14   678.9  419.02   928.3  408.06  1030.2  392.93  1130.9  390.44
  1171.2  392.23  1231.6  400.21  1364.8  403.31  1452.5  399.49  1726.4  380.43
  1792.3  377.83  1991.6  376.57  2101.9  378.97  2111.9  378.42    2122  371.72
    2142  372.67  2152.1   378.3  2172.1  379.34  2218.3  378.54  2364.4  376.99
  2518.9  379.11  2769.8  392.69  2786.3  395.24  2791.6  398.83  2817.2  401.76
  3066.9  402.28  3084.6  406.67  3089.9  405.05  3109.3  408.12  3175.9  409.26
#Mann= 7 ,-1 , 0
       0     .05       0   678.9     .16       0  1030.2     .07       0
  1171.2     .16       0  1991.6     .05       0  2172.1     .16       0
  2218.3     .05       0
#XS Ineff= 2 , 0
       0                 1356.71       0   403.3
Permanent Ineff=
       F       T
Bank Sta=1030.2,1171.2
XS Rating Curve= 0 ,0
Exp/Cntr=0.3,0.1

Type RM Length L Ch R = 1 ,297     ,0,0,0
BEGIN DESCRIPTION:
COTTONWOOD SPRING BRANCH 2.2
END DESCRIPTION:
XS GIS Cut Line= 4
      3569259.43     10494548.89      3568905.25     10495345.79
      3569045.87     10495528.08      3569332.31     10495605.85
#Sta/Elev= 30
  3972.6  420.05  4026.2  415.63  4117.9  412.61  4171.2  401.15  4205.4  391.92
  4223.2  390.24  4350.4   389.3  4373.7  398.04  4425.6  402.06    4479  403.43
  4518.7  398.18  4564.7  397.51  4568.2  397.66  4715.6  387.66  4785.4  388.52
  4790.9  390.03  4819.6     390  4837.4  388.14  4844.7   389.8    4882  382.59
    4889   381.4    5004  378.15  5057.5  376.71  5060.2  376.21  5063.5  376.71
    5231  381.46  5267.9  383.22  5313.8   387.2  5334.8  391.84  5371.7   394.1
#Mann= 10 ,-1 , 0
  3972.6     .05       0  4564.7      .1       0  4568.2     .05       0
    4889      .1       0    5004     .16       0  5057.5     .07       0
  5063.5     .16       0    5231     .05       0  5313.8     .16       0
  5334.8     .05       0
Bank Sta=4882,5267.9
XS Rating Curve= 0 ,0
Exp/Cntr=0.3,0.1

Chan Stop Cuts=-1
Use User Specified Reach Order=0
Composite Channel Slope=5