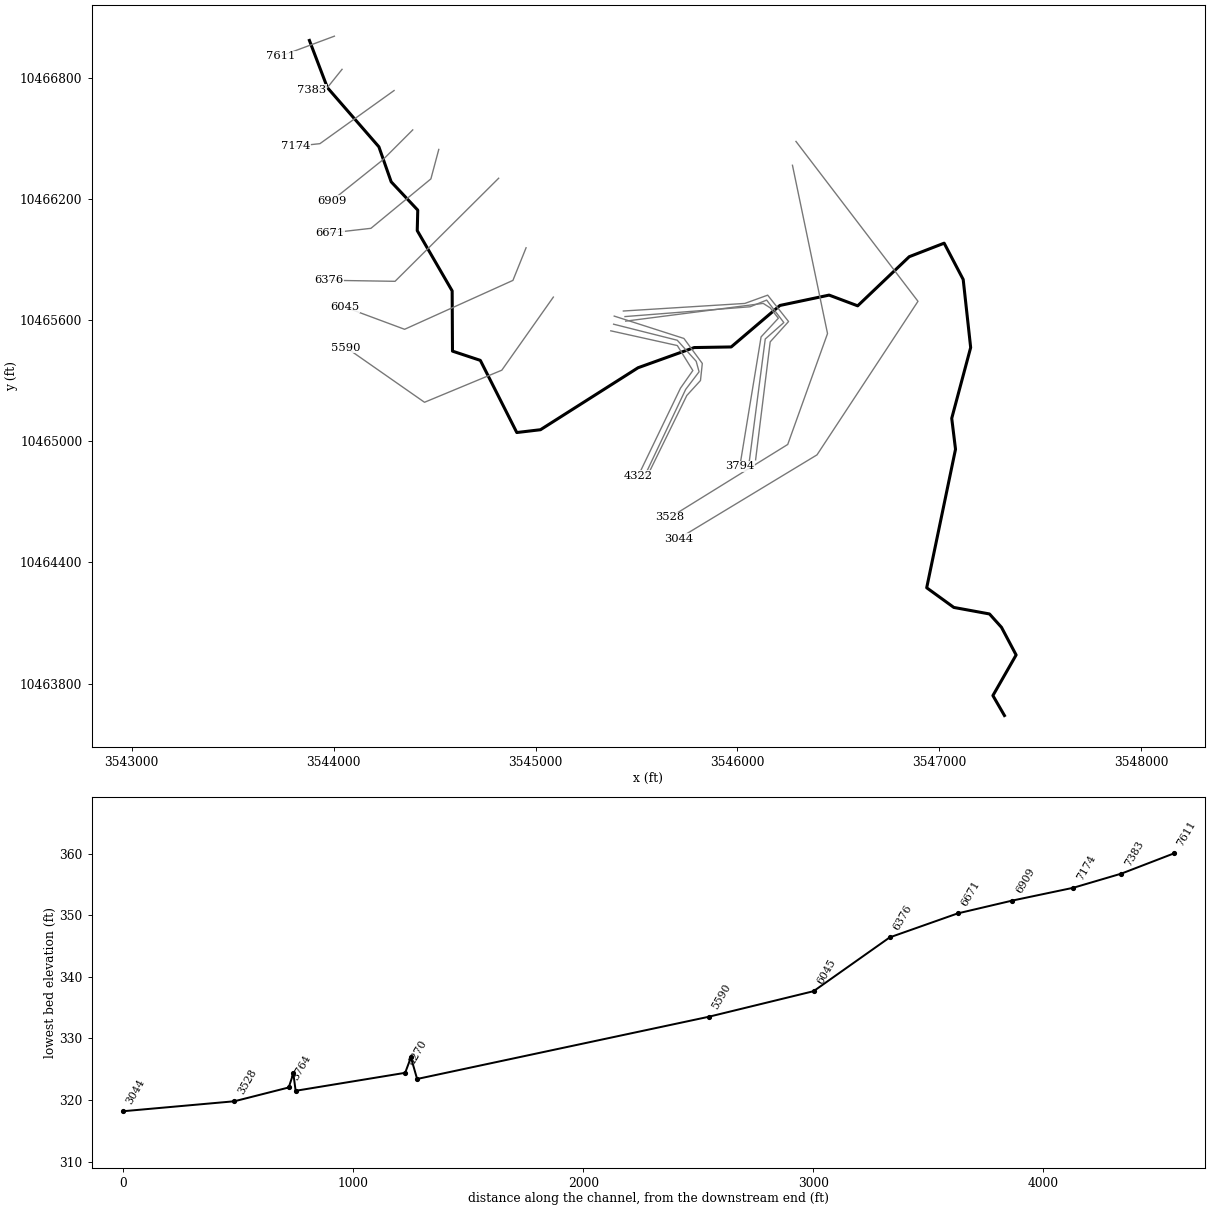
--- DOGWOODCRETRB11.prj (project) ---

Proj Title=DOGWOOD CRETRIB 1 1 Base Level Engineeri
Current Plan=p01
Default Exp/Contr=0.3,0.1
English Units
Geom File=g01
Flow File=f01
Plan File=p01
Y Axis Title=Elevation
X Axis Title(PF)=Main Channel Distance
X Axis Title(XS)=Station
BEGIN DESCRIPTION:
UNT02166 IN SAND CR
END DESCRIPTION:
DSS Export Rating Curves= 0
DSS Export Rating Curve Sorted= 0
DSS Export Volume Flow Curves= 0
DXF OffsetX= 0
DXF OffsetY= 0
DXF ScaleX= 1
DXF ScaleY= 10

--- DOGWOODCRETRB11.p01 (plan) ---

Plan Title=Multiple Run
Short Identifier=Multiple
Geom File=g01
Flow File=f01
Subcritical Flow
K Sum by GR= 0
Std Step Tol= 0.01
Critical Tol= 0.01
Num of Std Step Trials= 20
Max Error Tol= 0.3
Flow Tol Ratio= 0.001
Split Flow NTrial= 30
Split Flow Tol= 0.02
Split Flow Ratio= 0.02
Log Output Level= 0
Friction Slope Method= 1
Unsteady Friction Slope Method= 2
Unsteady Bridges Friction Slope Method= 1
Parabolic Critical Depth
Global Vel Dist=  1 , 1 , 1
Global Log Level= 0
CheckData=True
Encroach Param= -1, 0, 0, 0
BEGIN DESCRIPTION:
Multiple Run
END DESCRIPTION:

--- DOGWOODCRETRB11.f01 (steady flow) ---

Flow Title=Multiple
Program Version=4.10
Number of Profiles= 7
Profile Names=10-year,25-year,50-year,1pct_min,100-year,1pct_plu,500-year
River Rch & RM=UNT02166 IN SAND,Reach-1         ,7611
     343     441     518     445     602     815     811
River Rch & RM=UNT02166 IN SAND,Reach-1         ,3528
     751    1015    1229    1088    1471    1989    2099
River Rch & RM=DOGWOODCRETRB11,Reach-1         ,7611
     343     441     518     445     602     815     811
River Rch & RM=DOGWOODCRETRB11,Reach-1         ,3528
     751    1015    1229    1088    1471    1989    2099
Boundary for River Rch & Prof#=DOGWOODCRETRB11,Reach-1         , 1
Up Type= 0
Dn Type= 3
Dn Slope=0.005
Boundary for River Rch & Prof#=DOGWOODCRETRB11,Reach-1         , 2
Up Type= 0
Dn Type= 3
Dn Slope=0.005
Boundary for River Rch & Prof#=DOGWOODCRETRB11,Reach-1         , 3
Up Type= 0
Dn Type= 3
Dn Slope=0.005
Boundary for River Rch & Prof#=DOGWOODCRETRB11,Reach-1         , 4
Up Type= 0
Dn Type= 3
Dn Slope=0.005
Boundary for River Rch & Prof#=DOGWOODCRETRB11,Reach-1         , 5
Up Type= 0
Dn Type= 3
Dn Slope=0.005
Boundary for River Rch & Prof#=DOGWOODCRETRB11,Reach-1         , 6
Up Type= 0
Dn Type= 3
Dn Slope=0.005
Boundary for River Rch & Prof#=DOGWOODCRETRB11,Reach-1         , 7
Up Type= 0
Dn Type= 3
Dn Slope=0.005
DSS Import GetInterval= 0
DSS Import GetPeak= 0
DSS Import FillOption= 0

--- DOGWOODCRETRB11.g01 (geometry) ---

Geom Title=Existing Conditions
Program Version=4.10

River Reach=DOGWOODCRETRB11 ,Reach-1
Reach XY= 30
      3543880.45     10466984.55      3543969.42     10466751.05
       3544224.5     10466457.83      3544285.39     10466284.47
      3544416.95     10466144.31      3544414.36     10466042.87
      3544587.28     10465744.52      3544588.92     10465446.07
      3544726.81     10465400.35      3544907.34     10465043.01
      3545024.62     10465056.94       3545507.7     10465363.79
      3545785.83     10465463.79      3545969.03     10465466.82
      3546210.36      10465672.3      3546453.93     10465723.55
      3546595.34     10465670.42      3546850.55     10465913.65
      3547023.53     10465980.69      3547117.82     10465800.89
       3547154.8     10465463.91      3547061.05     10465113.39
       3547079.8     10464960.26      3546937.09     10464274.33
      3547071.47     10464176.93      3547248.03     10464144.64
       3547307.4     10464078.49      3547379.92     10463941.56
      3547264.91     10463740.46      3547322.11     10463641.64

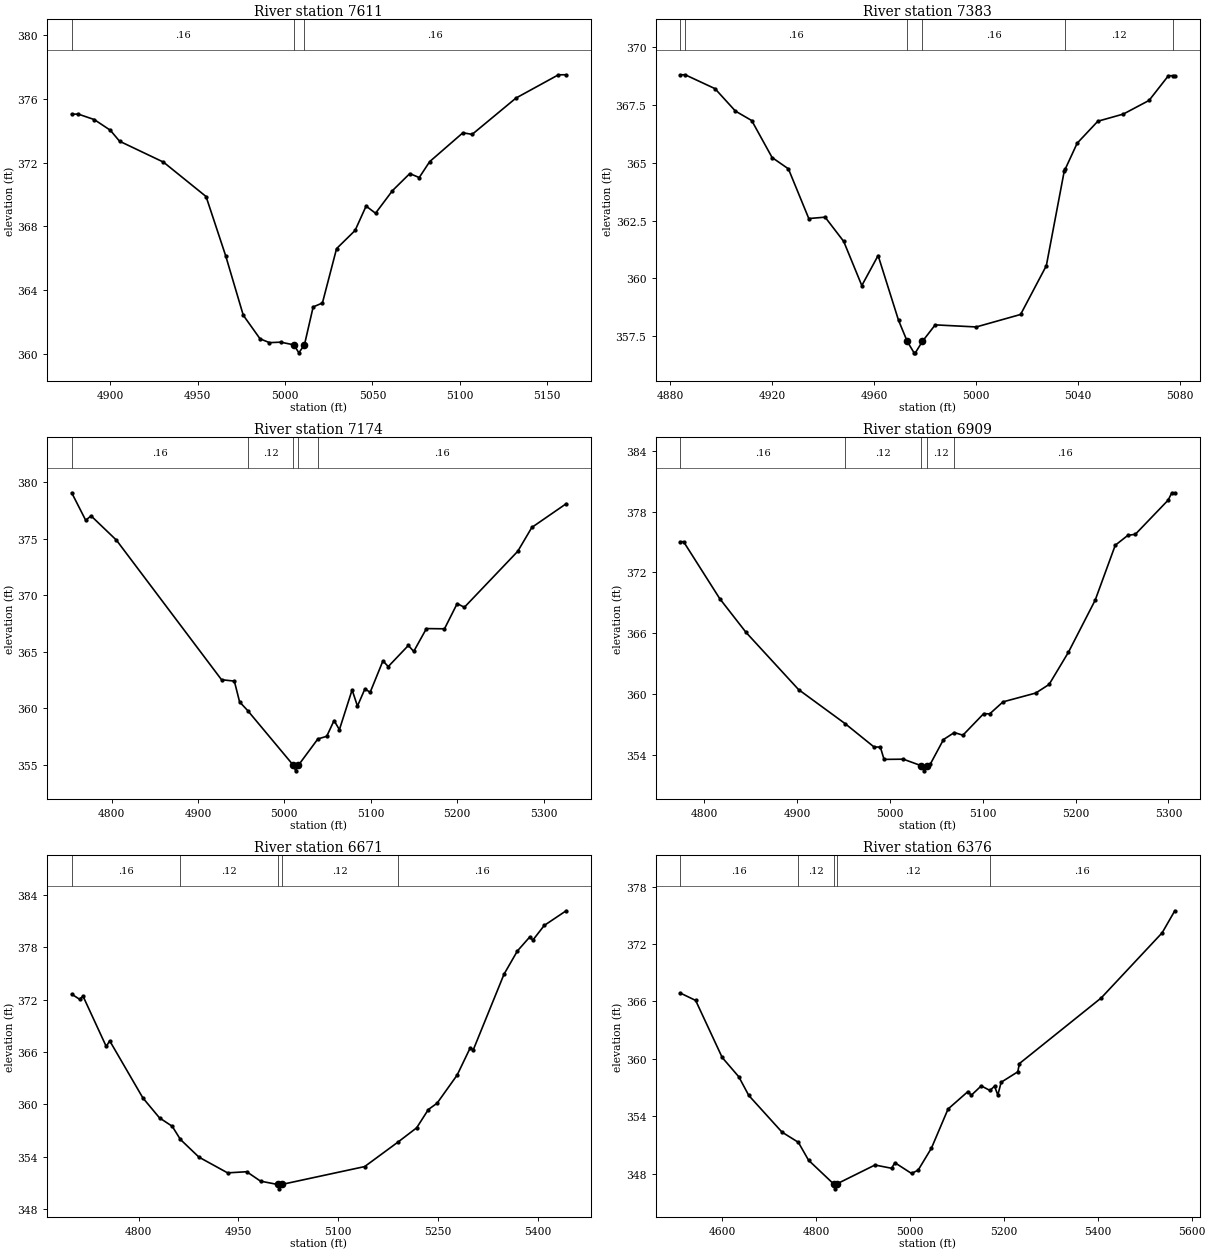
Type RM Length L Ch R = 1 ,7611    ,228,228,228
BEGIN DESCRIPTION:
UNT02166 IN SAND CR 8.1
END DESCRIPTION:
XS GIS Cut Line= 2
      3544004.17      10467005.7      3543738.91     10466907.09
#Sta/Elev= 30
  4877.9  375.04  4881.7  375.04  4890.8   374.7    4900  374.03  4905.3  373.34
  4930.4  372.03  4954.8  369.87    4966  366.16  4976.1  362.42  4985.7  360.94
  4991.1   360.7  4997.5  360.73  5005.1  360.56  5007.9  360.06  5011.1  360.56
  5016.1  362.94  5021.4  363.19  5029.5   366.6  5040.1  367.74  5046.4  369.27
  5051.8  368.82  5061.5  370.24  5071.4  371.31  5076.8  371.06  5082.8  372.06
  5101.8  373.87  5107.1  373.77  5132.2  376.05  5156.5  377.51  5160.9  377.51
#Mann= 3 ,-1 , 0
  4877.9     .16       0  5005.1     .07       0  5011.1     .16       0
Bank Sta=5005.1,5011.1
XS Rating Curve= 0 ,0
Exp/Cntr=0.3,0.1

Type RM Length L Ch R = 1 ,7383    ,209,209,209
BEGIN DESCRIPTION:
UNT02166 IN SAND CR 8.0
END DESCRIPTION:
XS GIS Cut Line= 3
      3544042.07      10466841.6      3543969.42     10466751.05
      3543892.09     10466741.64
#Sta/Elev= 30
  4883.9  368.81  4885.8  368.81  4897.5  368.21  4905.5  367.24  4911.9  366.83
  4919.9  365.23  4926.3  364.74  4934.3  362.59  4940.7  362.65    4948   361.6
  4955.1  359.69  4961.5  360.99  4969.5  358.19  4972.9  357.28  4975.6  356.78
  4976.1  356.78  4978.9  357.28  4983.9  357.99    5000   357.9  5017.4  358.44
  5027.5  360.55  5034.5  364.63    5035  364.75  5039.6  365.85  5047.7   366.8
  5057.7  367.11  5067.8   367.7  5075.4  368.77  5077.3  368.77  5077.9  368.77
#Mann= 6 ,-1 , 0
  4883.9     .12       0  4885.8     .16       0  4972.9     .07       0
  4978.9     .16       0    5035     .12       0  5077.3     .16       0
Bank Sta=4972.9,4978.9
XS Rating Curve= 0 ,0
Exp/Cntr=0.3,0.1

Type RM Length L Ch R = 1 ,7174    ,265,265,265
BEGIN DESCRIPTION:
UNT02166 IN SAND CR 7.1
END DESCRIPTION:
XS GIS Cut Line= 3
      3544299.69     10466736.52      3543932.48     10466473.48
      3543812.68     10466460.46
#Sta/Elev= 30
  4753.9  379.05  4770.1  376.62  4776.3  377.01  4805.7  374.86  4927.3  362.53
  4942.1  362.41  4948.2  360.57  4957.5  359.81  5010.3  354.98  5013.1  354.48
  5016.3  354.98  5038.8   357.3    5049  357.53  5057.5  358.92  5063.7  358.12
  5078.4  361.63  5084.6   360.2  5093.2  361.72  5099.3  361.42  5114.1   364.2
  5120.2  363.69  5143.5  365.56  5149.7  365.03  5164.4  367.05  5185.3  367.03
    5200  369.26  5208.3  368.93  5270.1  373.88  5286.4  375.99  5326.1  378.08
#Mann= 5 ,-1 , 0
  4753.9     .16       0  4957.5     .12       0  5010.3     .07       0
  5016.3     .12       0  5038.8     .16       0
Bank Sta=5010.3,5016.3
XS Rating Curve= 0 ,0
Exp/Cntr=0.3,0.1

Type RM Length L Ch R = 1 ,6909    ,238,238,238
BEGIN DESCRIPTION:
UNT02166 IN SAND CR 7.0
END DESCRIPTION:
XS GIS Cut Line= 3
      3544392.09     10466541.62      3544242.11     10466391.64
      3543992.08     10466191.62
#Sta/Elev= 30
  4774.5  375.02    4778  375.02  4816.9   369.4  4845.2  366.07  4901.8  360.42
  4951.9  357.06  4983.1  354.75  4989.8  354.75  4993.8  353.53  5014.6  353.55
    5034   352.9  5036.8   352.4    5040   352.9  5043.4  353.03  5057.8  355.49
  5069.4  356.18  5078.7  355.92  5101.1  358.05  5107.5  358.02  5121.9  359.21
  5157.1  360.08  5171.5  360.93  5192.3  364.11  5221.1  369.25  5242.7  374.67
  5256.3  375.65  5264.3  375.75  5299.6  379.12  5303.6  379.85  5306.8  379.85
#Mann= 5 ,-1 , 0
  4774.5     .16       0  4951.9     .12       0    5034     .07       0
    5040     .12       0  5069.4     .16       0
Bank Sta=5034,5040
XS Rating Curve= 0 ,0
Exp/Cntr=0.3,0.1

Type RM Length L Ch R = 1 ,6671    ,295,295,295
BEGIN DESCRIPTION:
UNT02166 IN SAND CR 7.2
END DESCRIPTION:
XS GIS Cut Line= 4
      3544521.03     10466444.87      3544481.96       10466299.
      3544185.09     10466054.21       3543979.4     10466030.78
#Sta/Elev= 30
  4699.5  372.62  4711.3  372.03  4716.5  372.39  4751.4  366.62  4756.6  367.27
  4806.4  360.73  4831.4  358.44  4850.5  357.48  4862.8  355.97  4890.7  353.94
  4933.7  352.14  4962.4  352.27  4983.2  351.19  5008.9  350.81  5011.6  350.31
  5014.9  350.81  5139.6  352.86  5189.9  355.68  5217.7   357.3  5235.3   359.4
  5248.4  360.12  5278.5  363.34  5297.9  366.42  5302.9  366.26    5349  374.91
  5369.1  377.57  5387.4  379.15  5392.4  378.82  5409.4  380.49  5442.3  382.17
#Mann= 5 ,-1 , 0
  4699.5     .16       0  4862.8     .12       0  5008.9     .07       0
  5014.9     .12       0  5189.9     .16       0
Bank Sta=5008.9,5014.9
XS Rating Curve= 0 ,0
Exp/Cntr=0.3,0.1

Type RM Length L Ch R = 1 ,6376    ,331,331,331
BEGIN DESCRIPTION:
UNT02166 IN SAND CR 6.0
END DESCRIPTION:
XS GIS Cut Line= 3
      3544817.55     10466302.25       3544304.5     10465791.81
      3543975.46     10465796.99
#Sta/Elev= 30
  4511.3  366.88  4543.9  366.11  4600.4  360.15  4635.8  358.13    4657  356.18
  4727.7  352.35  4762.6  351.28  4784.3  349.41  4837.9  346.92  4840.6  346.42
  4843.9  346.92  4925.7  348.91  4961.1  348.57  4968.1  349.15  5003.5  348.03
  5017.6  348.37  5045.9  350.67  5081.3  354.76  5123.7  356.59  5130.8   356.2
    5152  357.18  5170.5   356.7  5180.3  357.15  5187.3  356.22  5194.4  357.56
  5229.8  358.65  5233.2  359.51  5407.4  366.37  5537.2  373.18  5564.1  375.48
#Mann= 5 ,-1 , 0
  4511.3     .16       0  4762.6     .12       0  4837.9     .07       0
  4843.9     .12       0  5170.5     .16       0
Bank Sta=4837.9,4843.9
XS Rating Curve= 0 ,0
Exp/Cntr=0.3,0.1

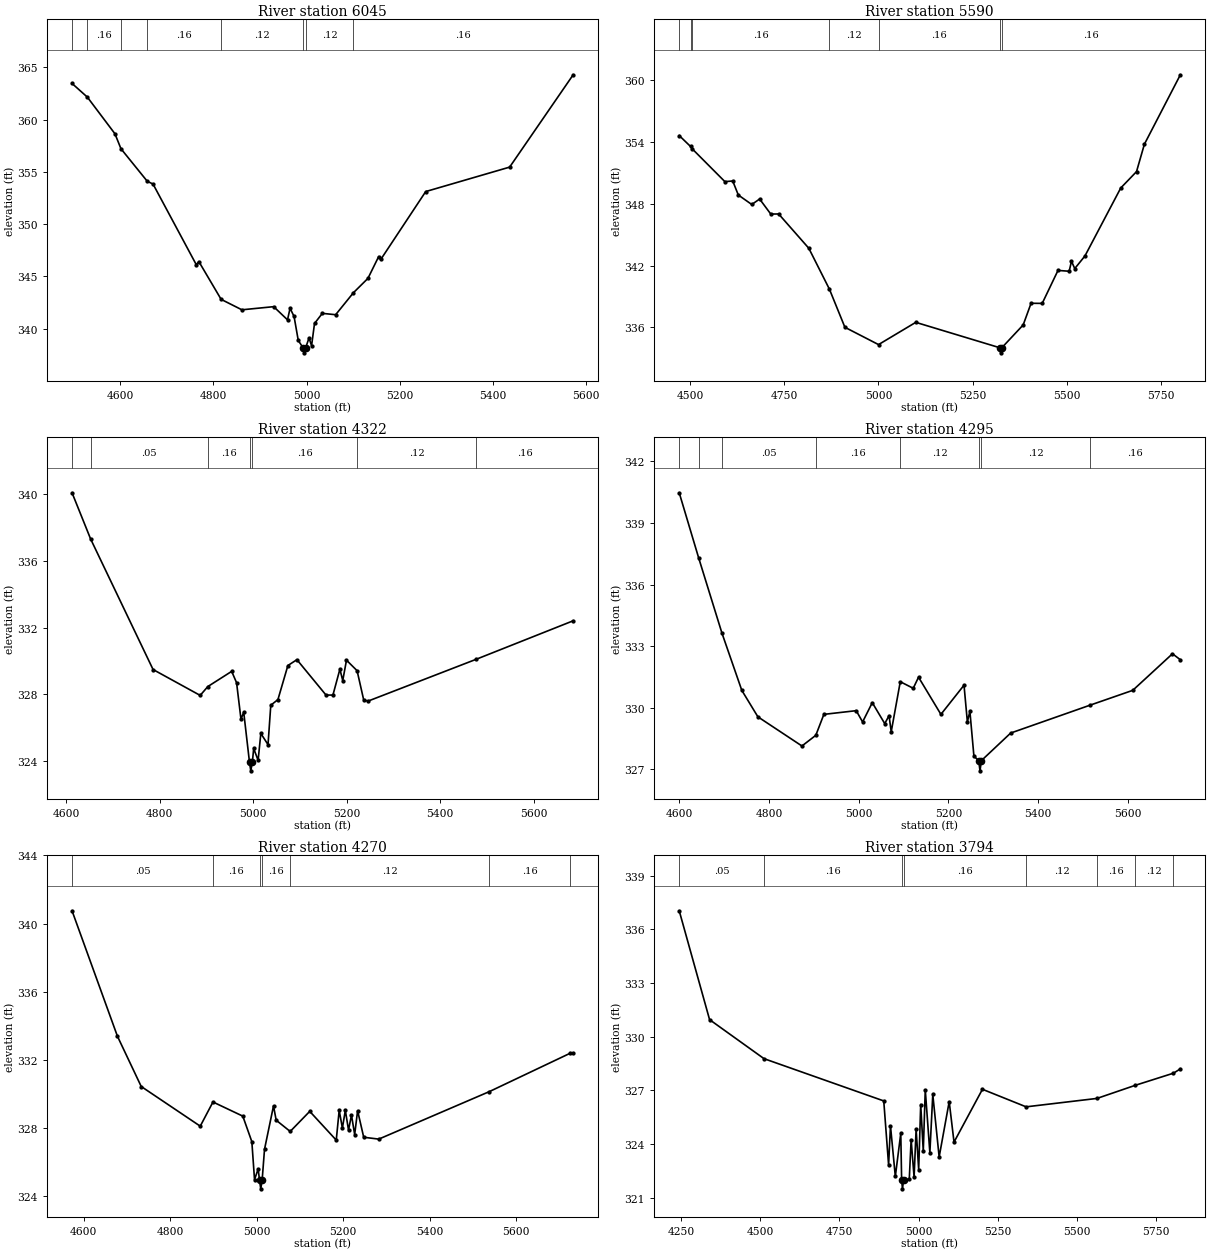
Type RM Length L Ch R = 1 ,6045    ,455,455,455
BEGIN DESCRIPTION:
UNT02166 IN SAND CR 7.3
END DESCRIPTION:
XS GIS Cut Line= 4
      3544953.32     10465957.88      3544888.21      10465796.4
      3544351.75     10465554.21      3544057.52     10465663.57
#Sta/Elev= 30
  4496.1  363.47    4529  362.16  4588.3  358.65  4601.2  357.22  4657.8   354.1
  4670.1  353.84    4763  346.12  4768.5  346.42  4816.4   342.8    4861   341.8
  4929.3   342.1    4959  340.84  4964.5  341.95  4973.1  341.16  4982.1  338.87
  4992.1  338.18  4994.8  337.68  4998.1  338.18  5005.2   339.1  5010.7  338.36
    5017  340.49  5033.8  341.46  5062.4  341.33  5100.7  343.44  5131.8  344.81
  5154.9   346.9  5160.4  346.69  5255.9  353.12  5436.2  355.46  5572.7   364.3
#Mann= 8 ,-1 , 0
  4496.1     .05       0    4529     .16       0  4601.2      .1       0
  4657.8     .16       0  4816.4     .12       0  4992.1     .07       0
  4998.1     .12       0  5100.7     .16       0
Bank Sta=4992.1,4998.1
XS Rating Curve= 0 ,0
Exp/Cntr=0.3,0.1

Type RM Length L Ch R = 1 ,5590    ,1268,1268,1268
BEGIN DESCRIPTION:
UNT02166 IN SAND CR 5.0
END DESCRIPTION:
XS GIS Cut Line= 4
      3545088.36     10465713.69      3544833.15     10465351.71
      3544450.33     10465192.85      3544062.29      10465463.7
#Sta/Elev= 30
    4471  354.62  4501.1  353.56  4506.1  353.31  4592.2  350.15  4613.1  350.21
  4627.9  348.85  4663.6  347.93  4684.5  348.46  4714.1     347    4735  347.01
  4815.1  343.68  4869.8  339.71  4910.9  336.01  5000.2  334.33  5099.1  336.49
  5321.7  334.03  5324.5  333.53  5327.7  334.03  5384.3  336.24  5405.2  338.34
  5434.8  338.33  5476.7  341.53  5506.4  341.45  5512.5  342.42  5521.2  341.71
  5548.2  342.93  5643.3  349.53  5685.2  351.12  5706.1  353.78  5801.6  360.52
#Mann= 7 ,-1 , 0
    4471     .16       0  4501.1      .1       0  4506.1     .16       0
  4869.8     .12       0  5000.2     .16       0  5321.7     .07       0
  5327.7     .16       0
Bank Sta=5321.7,5327.7
XS Rating Curve= 0 ,0
Exp/Cntr=0.3,0.1

Type RM Length L Ch R = 1 ,4322    ,27,27,27
BEGIN DESCRIPTION:
UNT02166 IN SAND CR 4.1
END DESCRIPTION:
XS GIS Cut Line= 5
      3545372.82     10465546.65      3545702.29     10465473.72
      3545779.11     10465350.02      3545717.91     10465262.78
      3545508.28     10464827.89
#Sta/Elev= 30
  4612.2  340.08    4652  337.31  4785.6  329.49  4886.4  327.94  4902.8  328.47
  4953.8  329.38  4964.3   328.7  4973.7  326.52  4979.6  326.93    4992  323.92
  4994.7  323.42    4998  323.92  5000.9  324.76  5010.4  324.05  5016.2  325.66
  5031.6  324.99  5037.5  327.35  5052.8  327.69  5074.1  329.73  5093.4  330.08
  5155.7  327.96  5170.5  327.96  5185.4  329.51  5191.5  328.83  5199.5  330.05
  5222.2  329.42  5236.4  327.66  5245.8   327.6  5476.7   330.1  5684.6  332.41
#Mann= 7 ,-1 , 0
  4612.2      .1       0    4652     .05       0  4902.8     .16       0
    4992     .07       0    4998     .16       0  5222.2     .12       0
  5476.7     .16       0
Bank Sta=4992,4998
XS Rating Curve= 0 ,0
Exp/Cntr=0.3,0.1

Type RM Length L Ch R = 1 ,4295    ,25,25,25
BEGIN DESCRIPTION:
UNT02166 IN SAND CR 4.0
END DESCRIPTION:
XS GIS Cut Line= 6
      3545386.81     10465579.45       3545701.9     10465500.02
      3545795.65     10465395.86      3545809.97     10465343.77
      3545743.56     10465256.53      3545534.73     10464815.73
#Sta/Elev= 30
  4600.1  340.47  4643.3  337.31  4695.3  333.64  4739.6  330.85  4775.5  329.56
  4873.7  328.14  4904.6  328.66  4922.6  329.68  4994.7  329.86  5008.9  329.31
  5030.5  330.25  5058.3  329.23  5067.9  329.62  5072.7  328.83  5092.9  331.27
  5121.8  330.95  5133.6  331.49  5183.5  329.68    5235   331.1  5242.5  329.31
  5248.1  329.83  5257.1  327.64  5267.8  327.43  5270.6  326.93  5273.8  327.43
    5339  328.77    5515  330.12  5611.2  330.85  5699.7  332.63  5717.3  332.34
#Mann= 8 ,-1 , 0
  4600.1     .05       0  4643.3      .1       0  4695.3     .05       0
  4904.6     .16       0  5092.9     .12       0  5267.8     .07       0
  5273.8     .12       0    5515     .16       0
Bank Sta=5267.8,5273.8
XS Rating Curve= 0 ,0
Exp/Cntr=0.3,0.1

Type RM Length L Ch R = 1 ,4270    ,476,476,476
BEGIN DESCRIPTION:
UNT02166 IN SAND CR 4.2
END DESCRIPTION:
XS GIS Cut Line= 6
      3545389.79     10465619.55      3545734.84     10465508.88
      3545825.98     10465385.18      3545816.87     10465300.54
      3545749.16     10465226.32      3545547.78     10464815.76
#Sta/Elev= 30
  4572.7  340.75  4677.7  333.38  4732.7  330.43  4869.2   328.1  4898.6  329.52
  4967.6  328.69  4988.5  327.19  4994.7  324.96  5003.1  325.59  5006.3  324.92
  5009.1  324.42  5012.3  324.92  5017.8  326.74  5038.6  329.29  5044.8  328.45
  5077.2  327.79  5122.4  328.97  5183.7  327.28  5190.5  329.03  5197.9  327.99
  5204.7  329.03  5212.1  327.87  5218.9  328.75  5226.3  327.61  5233.1  329.01
  5247.2  327.45    5282  327.34  5537.7  330.13  5724.4  332.38  5731.6   332.4
#Mann= 7 ,-1 , 0
  4572.7     .05       0  4898.6     .16       0  5006.3     .07       0
  5012.3     .16       0  5077.2     .12       0  5537.7     .16       0
  5724.4     .12       0
Bank Sta=5006.3,5012.3
XS Rating Curve= 0 ,0
Exp/Cntr=0.3,0.1

Type RM Length L Ch R = 1 ,3794    ,10,10,10
BEGIN DESCRIPTION:
UNT02166 IN SAND CR 3.1
END DESCRIPTION:
XS GIS Cut Line= 6
      3545446.61     10465594.66      3546127.47     10465682.55
      3546162.19     10465660.33      3546202.47     10465608.94
      3546117.05     10465516.58       3546011.7     10464875.45
#Sta/Elev= 30
  4244.6  337.03  4340.4  330.95  4512.2  328.77    4890  326.41  4905.3  322.83
  4911.2  325.02  4926.5  322.19  4943.7   324.6  4946.4     322  4949.1   321.5
  4952.4     322  4970.5  322.03  4976.4  324.25  4985.7  322.15  4992.1  324.83
  5000.2  322.58  5006.6  326.21  5014.7  323.61    5021  327.03  5035.5  323.52
  5044.7  326.77  5064.8  323.28  5096.5  326.37  5111.7  324.11  5201.4  327.06
  5339.2  326.08  5562.9  326.55  5683.3  327.28  5804.2  327.96  5825.9   328.2
#Mann= 8 ,-1 , 0
  4244.6     .05       0  4512.2     .16       0  4946.4     .07       0
  4952.4     .16       0  5339.2     .12       0  5562.9     .16       0
  5683.3     .12       0  5804.2     .16       0
Bank Sta=4946.4,4952.4
XS Rating Curve= 0 ,0
Exp/Cntr=0.3,0.1

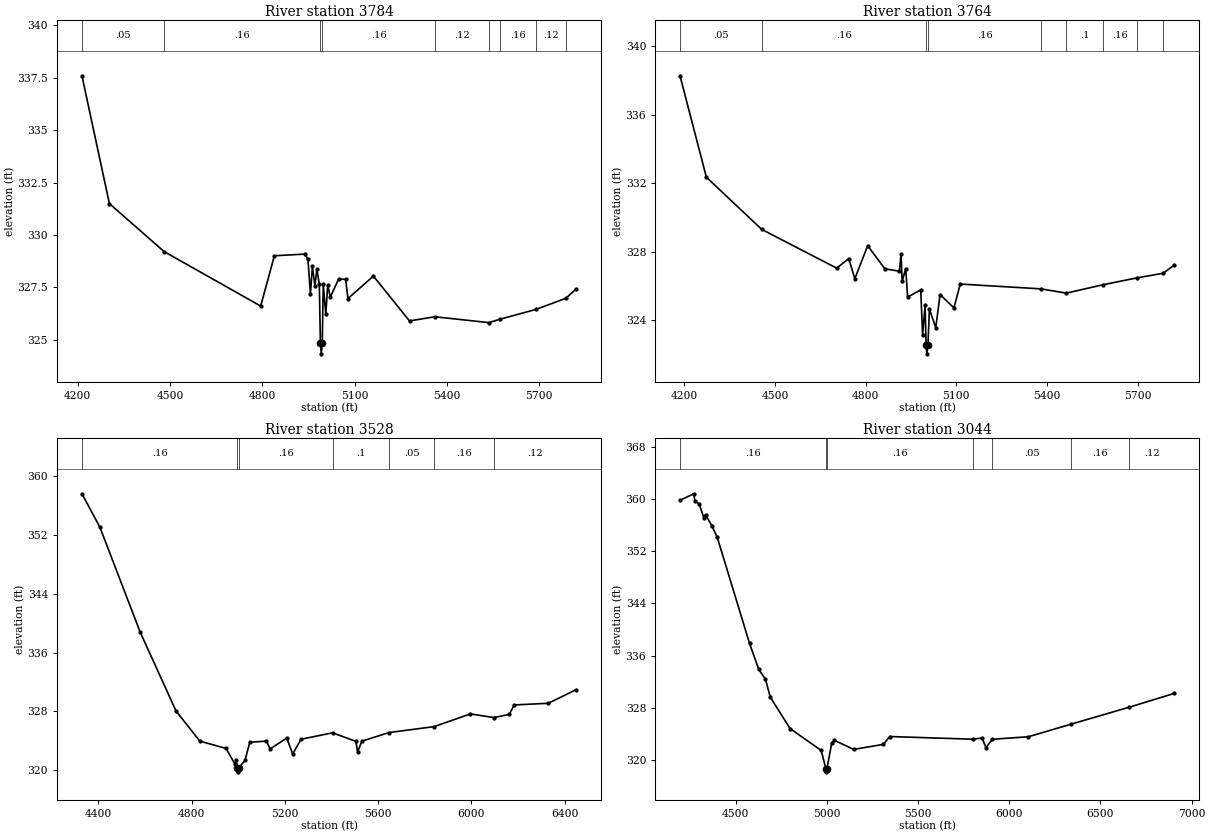
Type RM Length L Ch R = 1 ,3784    ,20,20,20
BEGIN DESCRIPTION:
UNT02166 IN SAND CR 3.0
END DESCRIPTION:
XS GIS Cut Line= 6
      3545443.18     10465617.23      3546062.98     10465665.84
      3546144.57     10465698.83      3546229.64     10465587.72
      3546137.63     10465506.12      3546057.99     10464894.97
#Sta/Elev= 30
  4213.9   337.6  4303.1   331.5  4480.8  329.21  4794.6  326.61  4839.1  329.01
  4938.3  329.09  4948.1  328.84  4956.3   327.2  4962.6   328.5  4970.8  327.57
  4977.1  328.37  4985.1  327.65  4988.6  324.83  4991.4  324.33  4994.6  324.83
  4997.9  327.65  5006.1  326.21  5012.4  327.62  5020.7  327.03  5048.1  327.91
  5070.5  327.88  5078.2  326.97  5160.8  328.04  5278.1   325.9  5360.1   326.1
  5535.7  325.82  5571.7  325.98  5688.9  326.45  5785.7  326.98  5819.3  327.42
#Mann= 9 ,-1 , 0
  4213.9     .05       0  4480.8     .16       0  4988.6     .07       0
  4994.6     .16       0  5360.1     .12       0  5535.7      .1       0
  5571.7     .16       0  5688.9     .12       0  5785.7     .16       0
Bank Sta=4988.6,4994.6
XS Rating Curve= 0 ,0
Exp/Cntr=0.3,0.1

Type RM Length L Ch R = 1 ,3764    ,236,236,236
BEGIN DESCRIPTION:
UNT02166 IN SAND CR 3.2
END DESCRIPTION:
XS GIS Cut Line= 6
        3545435.     10465644.76      3546036.44     10465682.26
      3546149.63     10465723.24       3546253.1     10465592.68
      3546162.13     10465491.99      3546089.91     10464907.97
#Sta/Elev= 30
    4186  338.26  4273.3  332.34  4456.3   329.3  4704.1  327.04  4744.2  327.59
  4764.2  326.42  4806.9  328.35  4863.5     327  4911.6  326.86  4917.2  327.85
  4920.9  326.27  4932.6  327.01  4938.9  325.35  4982.2  325.77  4988.6  323.16
  4996.7  324.86    5000  322.54  5002.8  322.04    5006  322.54  5011.1  324.66
  5031.9  323.56  5046.3   325.5  5092.1  324.72    5113  326.11  5380.3  325.83
  5463.8  325.58  5585.2  326.07  5697.2  326.47  5783.9  326.74  5820.6  327.21
#Mann= 9 ,-1 , 0
    4186     .05       0  4456.3     .16       0    5000     .07       0
    5006     .16       0  5380.3     .12       0  5463.8      .1       0
  5585.2     .16       0  5697.2     .12       0  5783.9     .16       0
Bank Sta=5000,5006
XS Rating Curve= 0 ,0
Exp/Cntr=0.3,0.1

Type RM Length L Ch R = 1 ,3528    ,484,484,484
BEGIN DESCRIPTION:
UNT02166 IN SAND CR 1.1
END DESCRIPTION:
XS GIS Cut Line= 4
      3546272.39     10466366.43      3546445.99     10465533.13
      3546248.94     10464983.95      3545666.87      10464623.3
#Sta/Elev= 30
  4329.6  357.57  4406.4  353.05  4579.6  338.76  4732.9  328.08    4835  323.98
  4947.4  322.98  4986.6  320.81  4991.7  321.41  4995.4   320.3  4998.2   319.8
  5001.4   320.3  5029.1  321.36  5049.5  323.82    5121  323.97  5136.8  322.92
    5208  324.38  5233.5  322.23  5269.5  324.23  5404.4   325.1  5504.8  323.94
  5511.7  322.49  5530.2  323.97  5647.2  325.14  5839.8  325.94  5995.8  327.67
  6096.3  327.17  6162.1   327.6    6184  328.89  6329.9  329.11    6449  330.96
#Mann= 7 ,-1 , 0
  4329.6     .16       0  4995.4     .07       0  5001.4     .16       0
  5404.4      .1       0  5647.2     .05       0  5839.8     .16       0
  6096.3     .12       0
Bank Sta=4995.4,5001.4
XS Rating Curve= 0 ,0
Exp/Cntr=0.3,0.1

Type RM Length L Ch R = 1 ,3044    ,0,0,0
BEGIN DESCRIPTION:
UNT02166 IN SAND CR 1.0
END DESCRIPTION:
XS GIS Cut Line= 4
      3546289.76     10466484.49      3546893.91     10465692.85
      3546393.91     10464932.43      3545706.89     10464516.76
#Sta/Elev= 30
  4195.2   359.8  4270.6   360.8  4276.9  359.69  4299.4  359.28  4326.8  357.06
    4335  357.62  4370.4  355.86  4399.4  354.12  4576.2  337.89  4626.5   333.9
  4663.4  332.38  4690.5  329.61  4798.5  324.82    4969  321.46    4995  318.68
  4997.8  318.18    5001  318.68  5027.1  322.62  5041.6     323  5147.7  321.62
  5309.4  322.39  5345.6  323.59  5801.5  323.18  5850.7  323.37  5872.8  321.89
  5906.8  323.17  6105.1  323.56  6339.4  325.49  6658.2  328.09  6904.1   330.2
#Mann= 7 ,-1 , 0
  4195.2     .16       0    4995     .07       0    5001     .16       0
  5801.5      .1       0  5906.8     .05       0  6339.4     .16       0
  6658.2     .12       0
Bank Sta=4995,5001
XS Rating Curve= 0 ,0
Exp/Cntr=0.3,0.1

Chan Stop Cuts=-1
Use User Specified Reach Order=0
Composite Channel Slope=5