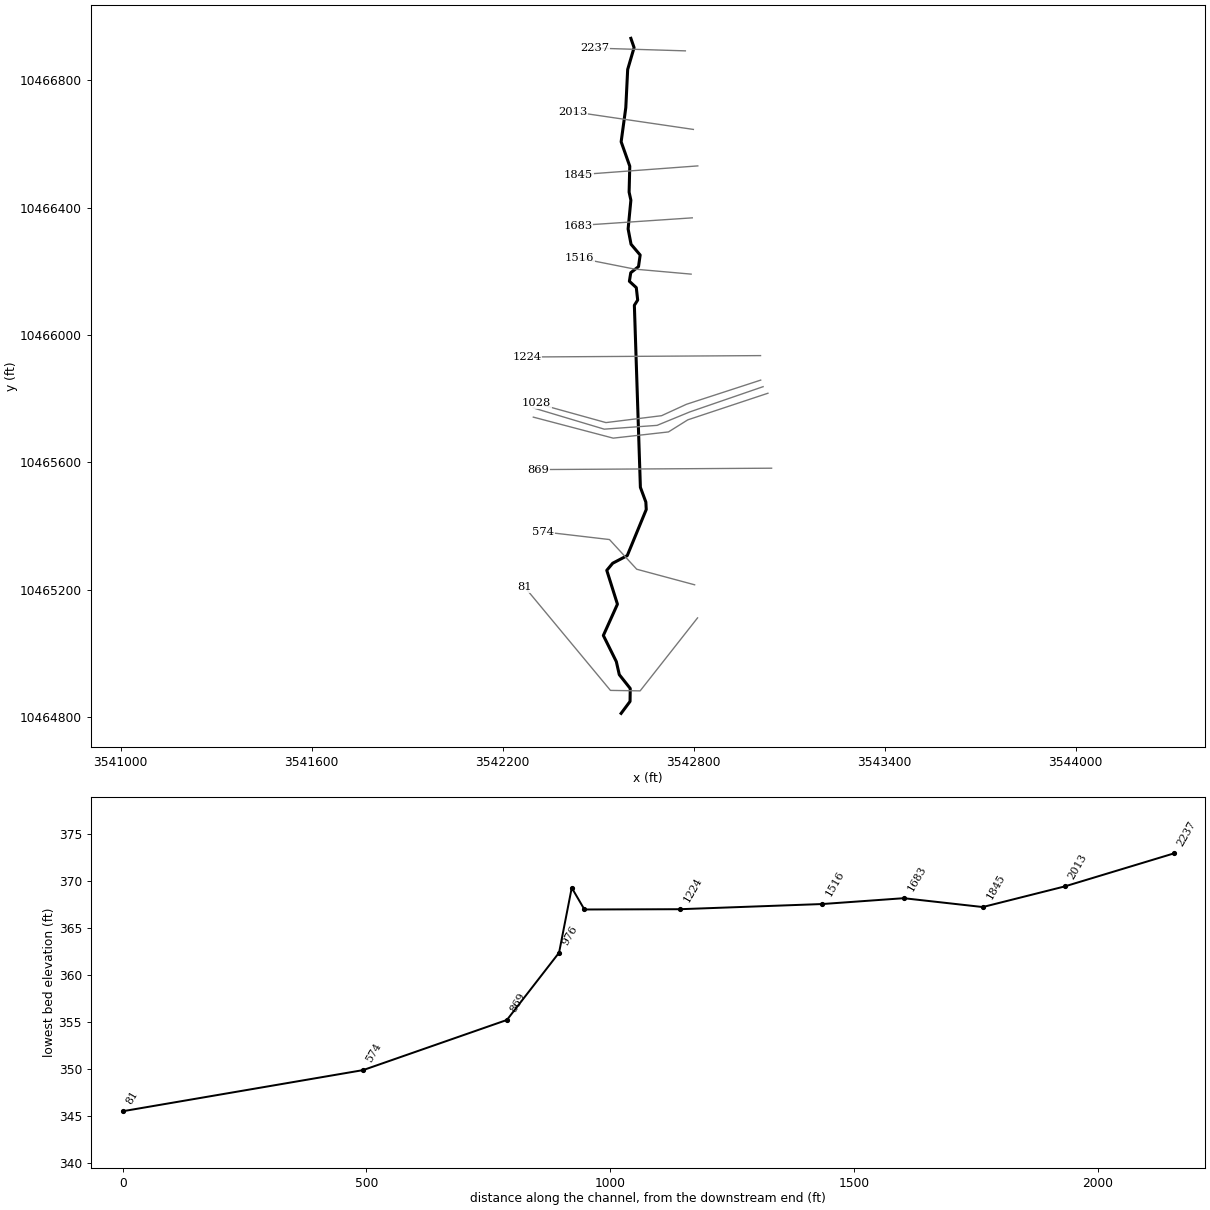
--- DOGWOODCRETRB21.prj (project) ---

Proj Title=DOGWOOD CRETRIB 21 Base Level Engineeri
Current Plan=p01
Default Exp/Contr=0.3,0.1
English Units
Geom File=g01
Flow File=f01
Plan File=p01
Y Axis Title=Elevation
X Axis Title(PF)=Main Channel Distance
X Axis Title(XS)=Station
BEGIN DESCRIPTION:
UNT02165 IN SAND CR
END DESCRIPTION:
DSS Export Rating Curves= 0
DSS Export Rating Curve Sorted= 0
DSS Export Volume Flow Curves= 0
DXF OffsetX= 0
DXF OffsetY= 0
DXF ScaleX= 1
DXF ScaleY= 10

--- DOGWOODCRETRB21.p01 (plan) ---

Plan Title=Multiple Run
Short Identifier=Multiple
Geom File=g01
Flow File=f01
Subcritical Flow
K Sum by GR= 0
Std Step Tol= 0.01
Critical Tol= 0.01
Num of Std Step Trials= 20
Max Error Tol= 0.3
Flow Tol Ratio= 0.001
Split Flow NTrial= 30
Split Flow Tol= 0.02
Split Flow Ratio= 0.02
Log Output Level= 0
Friction Slope Method= 1
Unsteady Friction Slope Method= 2
Unsteady Bridges Friction Slope Method= 1
Parabolic Critical Depth
Global Vel Dist=  1 , 1 , 1
Global Log Level= 0
CheckData=True
Encroach Param= -1, 0, 0, 0
BEGIN DESCRIPTION:
Multiple Run
END DESCRIPTION:

--- DOGWOODCRETRB21.f01 (steady flow) ---

Flow Title=Multiple
Program Version=4.10
Number of Profiles= 7
Profile Names=10-year,25-year,50-year,1pct_min,100-year,1pct_plu,500-year
River Rch & RM=UNT02165 IN SAND,Reach-1         ,2237
     198     245     279     234     317     429     405
River Rch & RM=DOGWOODCRETRB21,Reach-1         ,2237
     198     245     279     234     317     429     405
Boundary for River Rch & Prof#=DOGWOODCRETRB21,Reach-1         , 1
Up Type= 0
Dn Type= 3
Dn Slope=0.005
Boundary for River Rch & Prof#=DOGWOODCRETRB21,Reach-1         , 2
Up Type= 0
Dn Type= 3
Dn Slope=0.005
Boundary for River Rch & Prof#=DOGWOODCRETRB21,Reach-1         , 3
Up Type= 0
Dn Type= 3
Dn Slope=0.005
Boundary for River Rch & Prof#=DOGWOODCRETRB21,Reach-1         , 4
Up Type= 0
Dn Type= 3
Dn Slope=0.005
Boundary for River Rch & Prof#=DOGWOODCRETRB21,Reach-1         , 5
Up Type= 0
Dn Type= 3
Dn Slope=0.005
Boundary for River Rch & Prof#=DOGWOODCRETRB21,Reach-1         , 6
Up Type= 0
Dn Type= 3
Dn Slope=0.005
Boundary for River Rch & Prof#=DOGWOODCRETRB21,Reach-1         , 7
Up Type= 0
Dn Type= 3
Dn Slope=0.005
DSS Import GetInterval= 0
DSS Import GetPeak= 0
DSS Import FillOption= 0

--- DOGWOODCRETRB21.g01 (geometry) ---

Geom Title=Existing Conditions
Program Version=4.10

River Reach=DOGWOODCRETRB21 ,Reach-1
Reach XY= 30
      3542602.79     10466932.45      3542612.86     10466903.28
      3542592.72     10466834.53      3542586.82     10466714.74
      3542572.23     10466607.45      3542599.32     10466530.72
      3542597.23     10466449.25      3542602.79      10466423.9
      3542594.11     10466333.62      3542603.31     10466285.53
      3542631.95     10466251.68      3542626.75     10466215.22
      3542602.44     10466196.12       3542598.1     10466169.21
       3542619.8     10466149.25      3542624.14     10466110.18
      3542613.72     10466093.69      3542632.67     10465521.83
      3542649.82     10465475.49      3542651.08     10465452.12
      3542591.43     10465307.34      3542545.61     10465283.32
      3542527.05     10465260.99      3542560.57     10465154.66
      3542516.31     10465056.41      3542557.08     10464974.28
      3542566.36      10464933.3       3542600.8     10464889.86
      3542600.18     10464849.23      3542572.11     10464811.64

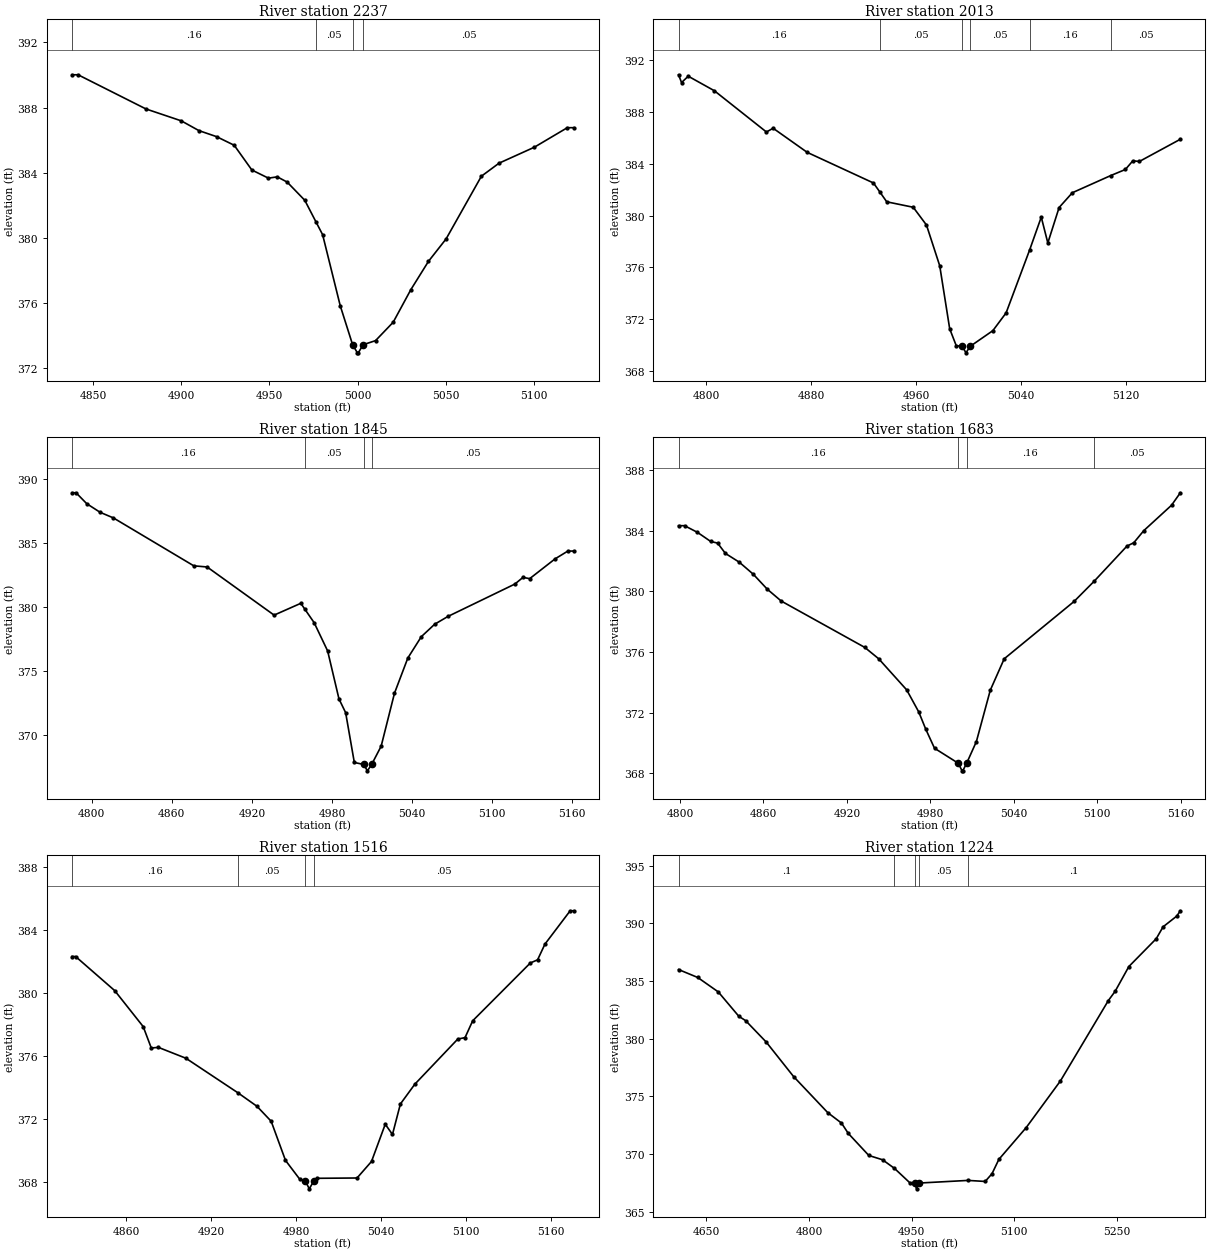
Type RM Length L Ch R = 1 ,2237    ,224,224,224
BEGIN DESCRIPTION:
UNT02165 IN SAND CR 3.4
END DESCRIPTION:
XS GIS Cut Line= 2
      3542773.99     10466893.11      3542489.72     10466901.79
#Sta/Elev= 29
  4838.2  390.01  4841.6  390.01  4880.1  387.91  4900.1  387.18  4910.1  386.58
  4920.1  386.21  4930.1  385.68  4940.1  384.16  4949.5  383.66  4954.5  383.74
  4960.1  383.42  4970.1   382.3  4976.5  380.96  4980.2  380.19  4990.2  375.82
  4997.2  373.43  4999.9  372.93  5000.4  372.93  5003.2  373.43  5010.2  373.68
  5020.2  374.81  5030.2  376.81  5040.2  378.55  5050.2  379.93  5070.2  383.78
  5080.2  384.58  5100.2  385.56  5118.9  386.76  5122.6  386.76
#Mann= 4 ,-1 , 0
  4838.2     .16       0  4976.5     .05       0  4997.2     .03       0
  5003.2     .05       0
Bank Sta=4997.2,5003.2
XS Rating Curve= 0 ,0
Exp/Cntr=0.3,0.1

Type RM Length L Ch R = 1 ,2013    ,168,168,168
BEGIN DESCRIPTION:
UNT02165 IN SAND CR 3.3
END DESCRIPTION:
XS GIS Cut Line= 2
      3542799.12     10466646.27      3542420.68     10466701.82
#Sta/Elev= 30
  4778.9  390.85  4781.2  390.25  4786.3  390.74  4806.2  389.62  4845.9  386.44
    4851  386.73    4877  384.87  4927.5  382.51  4932.4  381.81  4937.6  381.06
  4957.8  380.64  4967.9  379.27    4978  376.13  4985.6  371.27  4990.6  369.97
  4995.2  369.92    4998  369.42  5001.2  369.92  5018.5  371.13  5028.6   372.5
  5046.5  377.34  5055.4  379.88  5060.4  377.89    5069  380.62  5079.1  381.76
  5108.3  383.08  5119.5  383.55  5125.2  384.22  5130.2  384.17  5161.4  385.88
#Mann= 6 ,-1 , 0
  4778.9     .16       0  4932.4     .05       0  4995.2     .03       0
  5001.2     .05       0  5046.5     .16       0  5108.3     .05       0
Bank Sta=4995.2,5001.2
XS Rating Curve= 0 ,0
Exp/Cntr=0.3,0.1

Type RM Length L Ch R = 1 ,1845    ,162,162,162
BEGIN DESCRIPTION:
UNT02165 IN SAND CR 3.2
END DESCRIPTION:
XS GIS Cut Line= 2
      3542813.05     10466531.68      3542438.08      10466503.9
#Sta/Elev= 30
  4785.3  388.89  4788.3  388.89  4796.3  388.04  4806.3  387.37  4816.3  386.93
  4876.5   383.2  4886.5  383.11  4936.7  379.36  4956.7  380.28  4959.6  379.84
  4966.7  378.77  4976.8  376.57  4985.3  372.83  4990.3  371.76  4996.8  367.88
  5003.8  367.73  5006.6  367.23  5009.8  367.73  5016.9  369.15  5026.9  373.28
  5036.9  376.02    5047  377.68    5057  378.65    5067  379.26  5117.1  381.78
  5123.2   382.3  5128.2   382.2  5147.2  383.74  5156.8  384.35  5161.3  384.35
#Mann= 4 ,-1 , 0
  4785.3     .16       0  4959.6     .05       0  5003.8     .03       0
  5009.8     .05       0
Bank Sta=5003.8,5009.8
XS Rating Curve= 0 ,0
Exp/Cntr=0.3,0.1

Type RM Length L Ch R = 1 ,1683    ,167,167,167
BEGIN DESCRIPTION:
UNT02165 IN SAND CR 3.1
END DESCRIPTION:
XS GIS Cut Line= 2
      3542795.71     10466368.49      3542435.83     10466344.26
#Sta/Elev= 30
    4799  384.34  4803.3  384.34  4812.6   383.9  4822.1   383.3  4827.1  383.19
  4832.7  382.51  4842.7  381.93  4852.7  381.14  4862.8  380.15  4872.8  379.37
  4932.9  376.31  4942.9  375.56    4963  373.51  4971.7  372.05  4976.7  370.92
    4983  369.66  5000.1  368.67  5002.8  368.17  5003.3  368.17  5006.1  368.67
  5013.1   370.1  5023.1  373.49  5033.1  375.56  5083.3  379.34  5097.6  380.66
  5121.3  382.99  5126.3  383.22  5133.4  384.01  5153.4  385.69  5159.7  386.51
#Mann= 4 ,-1 , 0
    4799     .16       0  5000.1     .07       0  5006.1     .16       0
  5097.6     .05       0
Bank Sta=5000.1,5006.1
XS Rating Curve= 0 ,0
Exp/Cntr=0.3,0.1

Type RM Length L Ch R = 1 ,1516    ,292,292,292
BEGIN DESCRIPTION:
UNT02165 IN SAND CR 3.0
END DESCRIPTION:
XS GIS Cut Line= 3
      3542792.09     10466191.64      3542614.59     10466207.41
      3542442.06     10466241.65
#Sta/Elev= 30
  4821.8  382.33  4824.3  382.33  4851.9  380.16    4872  377.87  4877.7  376.51
  4882.7  376.55  4902.1  375.86    4939  373.65  4952.3   372.8  4962.3  371.85
  4972.4  369.36  4982.4  368.17  4986.4  368.05  4989.2  367.55  4992.4  368.05
  4994.4  368.22  5022.9  368.24  5033.1  369.29  5042.8  371.66  5047.9  371.01
  5053.5  372.95  5063.7  374.21    5094  377.08  5099.1  377.17  5104.5  378.24
  5145.2  381.92  5150.3  382.12  5155.5  383.12  5173.3  385.24  5175.9  385.24
#Mann= 4 ,-1 , 0
  4821.8     .16       0    4939     .05       0  4986.4    .033       0
  4992.4     .05       0
Bank Sta=4986.4,4992.4
XS Rating Curve= 0 ,0
Exp/Cntr=0.3,0.1

Type RM Length L Ch R = 1 ,1224    ,196,196,196
BEGIN DESCRIPTION:
UNT02165 IN SAND CR 2.1
END DESCRIPTION:
XS GIS Cut Line= 2
      3543010.18     10465935.65      3542276.89     10465931.31
#Sta/Elev= 30
  4609.5     386  4637.6  385.31  4667.6  384.06  4697.6  381.95  4707.6  381.57
  4737.6  379.72  4777.6  376.73  4827.6   373.6  4847.6   372.7  4857.6   371.8
  4887.6  369.89  4907.6  369.52  4925.1  368.77  4947.6  367.52  4954.6   367.5
  4957.3     367  4960.6   367.5  5032.6  367.73  5057.6  367.64  5067.6  368.31
  5077.6  369.55  5117.6  372.31  5167.6  376.35  5237.6  383.31  5247.6  384.12
  5267.6  386.26  5307.6  388.67  5317.6   389.7  5337.6  390.63  5342.8  391.09
#Mann= 5 ,-1 , 0
  4609.5      .1       0  4925.1     .05       0  4954.6    .033       0
  4960.6     .05       0  5032.6      .1       0
Bank Sta=4954.6,4960.6
XS Rating Curve= 0 ,0
Exp/Cntr=0.3,0.1

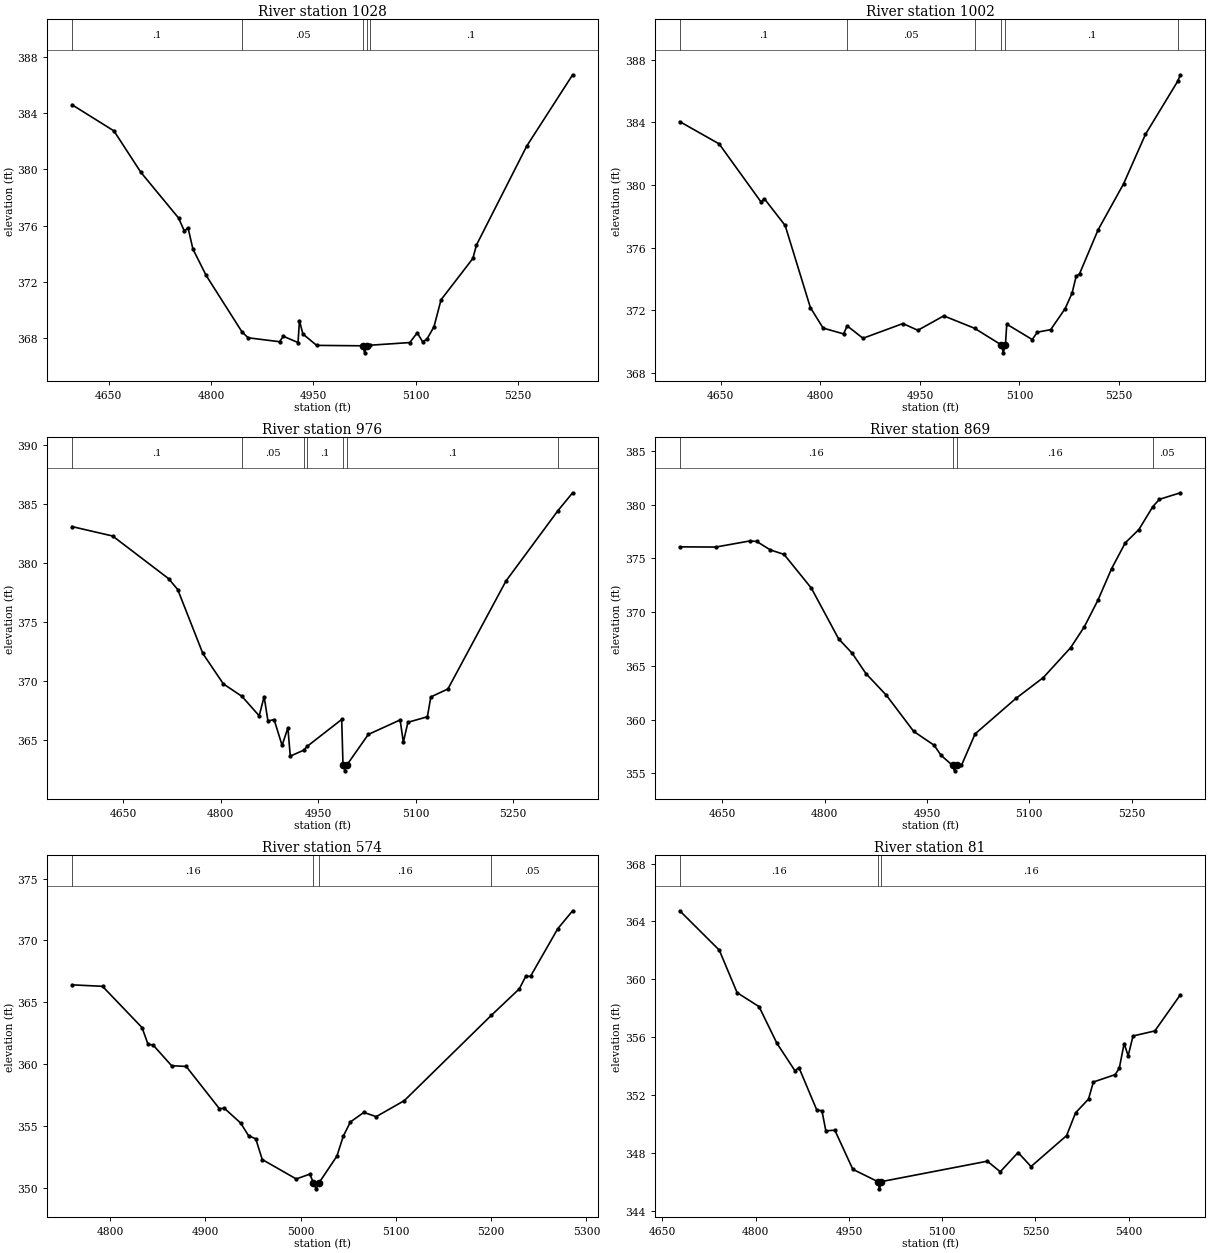
Type RM Length L Ch R = 1 ,1028    ,26,26,26
BEGIN DESCRIPTION:
UNT02165 IN SAND CR 2.4
END DESCRIPTION:
XS GIS Cut Line= 5
      3543010.61     10465858.66      3542777.32      10465782.7
      3542699.19     10465746.89      3542524.49     10465725.19
      3542306.25     10465785.69
#Sta/Elev= 30
  4596.1   384.6  4657.6  382.74    4697   379.8  4752.3  376.55  4760.8  375.62
  4766.1  375.87  4773.3  374.35  4792.7  372.47  4845.5  368.44  4854.3  368.04
  4900.3  367.76  4905.8  368.15  4927.4   367.7  4929.5  369.26  4934.5  368.31
  4954.7   367.5  5022.2  367.47    5025  366.97  5028.2  367.47  5032.4  367.51
  5091.2   367.7  5102.1  368.39    5110  367.76  5116.3  367.94  5126.7  368.83
    5137  370.74  5183.7  373.68  5188.9  374.63  5262.7  381.67  5329.9  386.73
#Mann= 5 ,-1 , 0
  4596.1      .1       0  4845.5     .05       0  5022.2    .033       0
  5028.2     .05       0  5032.4      .1       0
Bank Sta=5022.2,5028.2
XS Rating Curve= 0 ,0
Exp/Cntr=0.3,0.1

Type RM Length L Ch R = 1 ,1002    ,26,26,26
BEGIN DESCRIPTION:
UNT02165 IN SAND CR 2.2
END DESCRIPTION:
XS GIS Cut Line= 5
      3543018.21     10465838.04      3542788.17     10465758.83
      3542685.08     10465716.51      3542519.07     10465704.58
      3542295.74     10465771.46
#Sta/Elev= 30
  4588.2  384.04  4647.5  382.62  4710.5  378.92  4715.8  379.11    4747  377.41
    4785  372.17  4804.2  370.86    4835  370.49  4840.5     371  4864.3  370.21
  4924.5  371.15  4946.9  370.72    4986  371.64  5032.3  370.85  5072.9  369.78
  5075.6  369.28  5078.9  369.78  5080.9  371.11  5119.2  370.13  5127.1   370.6
  5147.1  370.76  5168.8   372.1  5179.3  373.09  5185.4  374.16  5190.6  374.33
  5218.5  377.13  5256.8  380.06  5289.9  383.23  5338.5  386.62  5342.5  387.03
#Mann= 6 ,-1 , 0
  4588.2      .1       0  4840.5     .05       0  5032.3      .1       0
  5072.9    .033       0  5078.9      .1       0  5338.5     .05       0
Bank Sta=5072.9,5078.9
XS Rating Curve= 0 ,0
Exp/Cntr=0.3,0.1

Type RM Length L Ch R = 1 ,976     ,107,107,107
BEGIN DESCRIPTION:
UNT02165 IN SAND CR 2.3
END DESCRIPTION:
XS GIS Cut Line= 5
      3543033.37     10465817.41      3542781.66     10465733.87
      3542720.89     10465695.89      3542547.28     10465676.36
      3542296.29     10465742.36
#Sta/Elev= 30
  4570.9  383.11  4633.5  382.31  4719.7  378.69  4733.8  377.76  4772.4  372.34
    4804  369.76  4832.7   368.7  4859.2  367.05  4866.8  368.68  4872.7  366.61
  4882.2  366.73  4894.5  364.54  4903.4  366.03  4907.1  363.63  4927.7  364.13
  4933.6  364.48  4986.3  366.74  4988.3  362.88  4991.1  362.38  4994.3  362.88
  5027.3  365.47  5076.3   366.7  5081.2  364.81  5088.3   366.5  5118.3  366.97
  5123.5  368.65  5149.9  369.33  5239.3  378.49  5319.3  384.46    5342  385.98
#Mann= 7 ,-1 , 0
  4570.9      .1       0  4832.7     .05       0  4927.7     .16       0
  4933.6      .1       0  4988.3     .07       0  4994.3      .1       0
  5319.3     .05       0
Bank Sta=4988.3,4994.3
XS Rating Curve= 0 ,0
Exp/Cntr=0.3,0.1

Type RM Length L Ch R = 1 ,869     ,295,295,295
BEGIN DESCRIPTION:
UNT02165 IN SAND CR 2.0
END DESCRIPTION:
XS GIS Cut Line= 2
      3543044.91     10465581.92      3542311.33     10465577.58
#Sta/Elev= 30
  4587.7  376.07  4640.5  376.05  4690.5  376.62  4700.5  376.57  4720.5  375.78
  4740.5  375.37  4780.5  372.23  4820.5  367.51  4840.5  366.16  4860.5  364.28
  4890.5  362.26  4930.5   358.9  4960.5  357.61  4970.5  356.68  4987.5  355.73
  4990.3  355.23  4993.5  355.73  5000.5  355.74  5020.5  358.67  5080.5  361.98
  5120.5  363.91  5160.5  366.69  5180.5  368.63  5200.5  371.11  5220.5  374.04
  5240.5  376.44  5260.5  377.68  5280.9  379.81  5290.5  380.49  5321.3   381.1
#Mann= 4 ,-1 , 0
  4587.7     .16       0  4987.5     .07       0  4993.5     .16       0
  5280.9     .05       0
Bank Sta=4987.5,4993.5
XS Rating Curve= 0 ,0
Exp/Cntr=0.3,0.1

Type RM Length L Ch R = 1 ,574     ,493,493,493
BEGIN DESCRIPTION:
UNT02165 IN SAND CR 1.0
END DESCRIPTION:
XS GIS Cut Line= 4
      3542803.05      10465215.6      3542621.15     10465264.51
      3542535.54     10465357.77      3542326.61     10465382.17
#Sta/Elev= 30
  4760.2   366.4  4792.2  366.28  4833.7  362.94    4840  361.58  4845.2  361.54
  4864.7  359.86    4880   359.8  4914.8  356.39    4920  356.42  4937.2  355.22
  4945.5  354.19    4953  353.95  4959.8  352.27  4995.5   350.7  5009.7  351.09
  5013.5   350.4  5016.3   349.9  5019.5   350.4  5038.1  352.54  5044.9  354.17
  5052.3  355.31  5066.4  356.08  5079.4  355.74  5108.8  357.03    5200  363.92
  5229.6  366.08  5236.3  367.09  5241.3  367.09  5269.9  370.94  5285.5  372.39
#Mann= 4 ,-1 , 0
  4760.2     .16       0  5013.5     .07       0  5019.5     .16       0
    5200     .05       0
Bank Sta=5013.5,5019.5
XS Rating Curve= 0 ,0
Exp/Cntr=0.3,0.1

Type RM Length L Ch R = 1 ,81      ,0,0,0
BEGIN DESCRIPTION:
UNT02165 IN SAND CR 1.1
END DESCRIPTION:
XS GIS Cut Line= 4
      3542812.24     10465111.61      3542631.85     10464882.31
       3542538.6     10464883.84      3542270.08     10465207.28
#Sta/Elev= 30
  4677.8  364.74  4741.4  362.02  4770.1  359.08  4805.3  358.12  4834.2  355.58
  4863.1  353.69  4869.5  353.91  4898.4  350.96  4906.5  350.93  4912.8  349.54
  4927.3  349.58  4956.2  346.88  4996.3  346.03  4999.1  345.53  5002.3  346.03
  5172.6  347.44  5193.4  346.71  5222.1  348.04  5242.9  347.07  5300.2  349.21
  5314.5  350.78  5335.4  351.73  5343.2  352.91  5378.3  353.42  5384.9  353.86
  5392.7  355.57  5399.2  354.72    5407  356.09  5442.1  356.44  5483.2  358.94
#Mann= 3 ,-1 , 0
  4677.8     .16       0  4996.3     .07       0  5002.3     .16       0
Bank Sta=4996.3,5002.3
XS Rating Curve= 0 ,0
Exp/Cntr=0.3,0.1

Chan Stop Cuts=-1
Use User Specified Reach Order=0
Composite Channel Slope=5