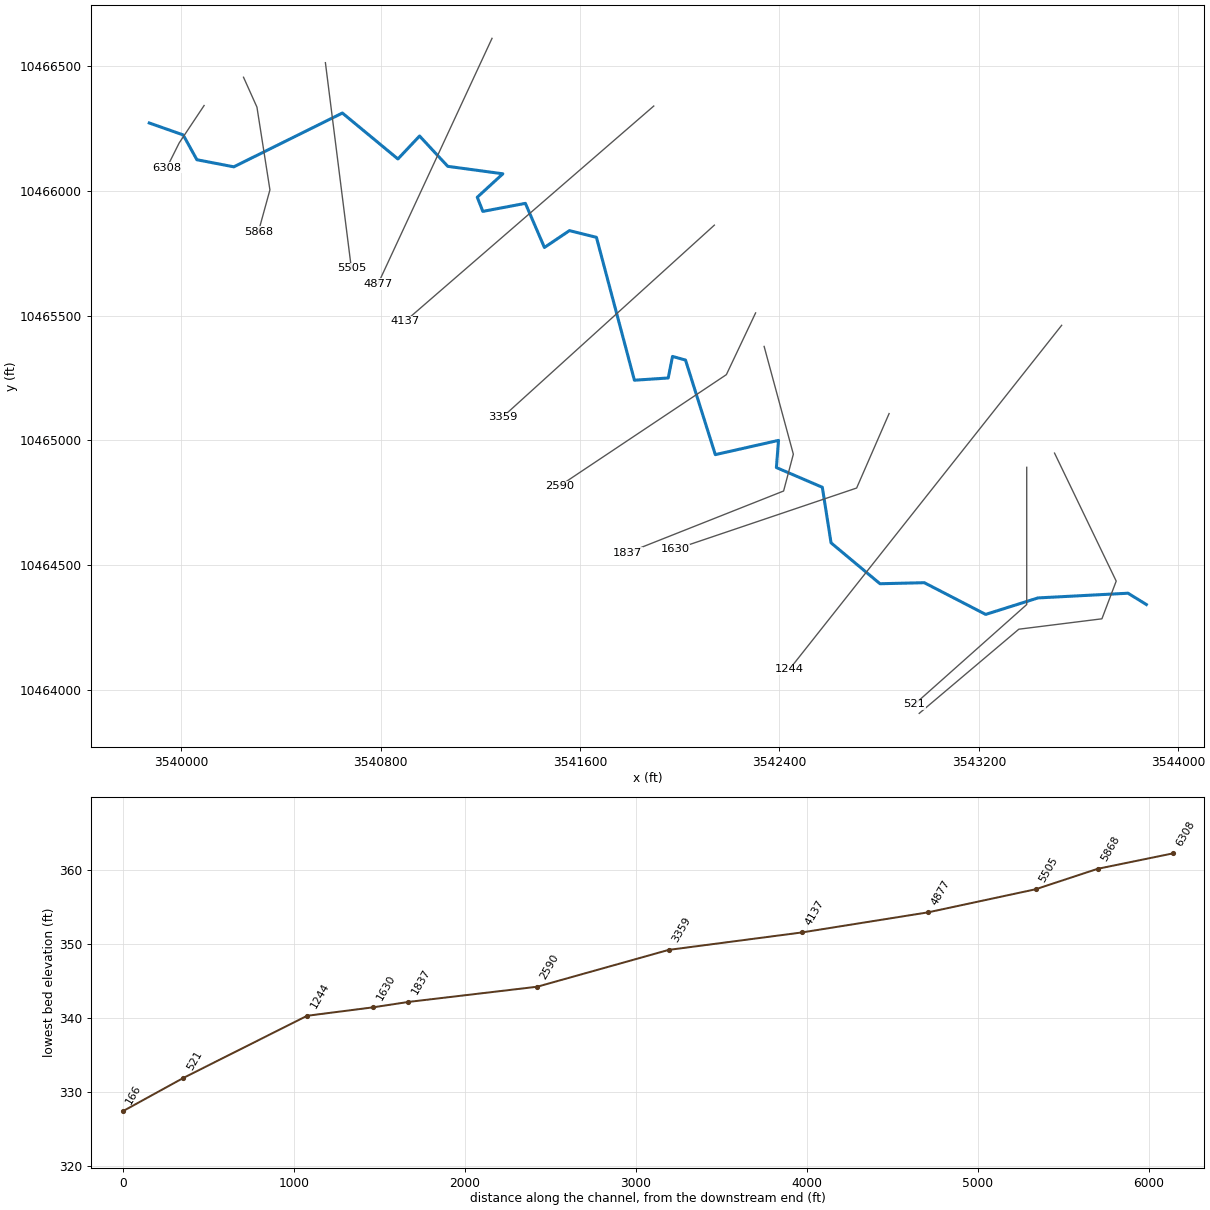
--- DOGWOODCRETRIB2.prj (project) ---

Proj Title=DOGWOOD CR E TRIB 2 Base Level Engineeri
Current Plan=p01
Default Exp/Contr=0.3,0.1
English Units
Geom File=g01
Flow File=f01
Plan File=p01
Y Axis Title=Elevation
X Axis Title(PF)=Main Channel Distance
X Axis Title(XS)=Station
BEGIN DESCRIPTION:
UNT02162 IN SAND CR
END DESCRIPTION:
DSS Export Rating Curves= 0
DSS Export Rating Curve Sorted= 0
DSS Export Volume Flow Curves= 0
DXF OffsetX= 0
DXF OffsetY= 0
DXF ScaleX= 1
DXF ScaleY= 10

--- DOGWOODCRETRIB2.p01 (plan) ---

Plan Title=Multiple Run
Short Identifier=Multiple
Geom File=g01
Flow File=f01
Subcritical Flow
K Sum by GR= 0
Std Step Tol= 0.01
Critical Tol= 0.01
Num of Std Step Trials= 20
Max Error Tol= 0.3
Flow Tol Ratio= 0.001
Split Flow NTrial= 30
Split Flow Tol= 0.02
Split Flow Ratio= 0.02
Log Output Level= 0
Friction Slope Method= 1
Unsteady Friction Slope Method= 2
Unsteady Bridges Friction Slope Method= 1
Parabolic Critical Depth
Global Vel Dist=  1 , 1 , 1
Global Log Level= 0
CheckData=True
Encroach Param= -1, 0, 0, 0
BEGIN DESCRIPTION:
Multiple Run
END DESCRIPTION:

--- DOGWOODCRETRIB2.f01 (steady flow) ---

Flow Title=Multiple
Program Version=4.10
Number of Profiles= 7
Profile Names=10-year,25-year,50-year,1pct_min,100-year,1pct_plu,500-year
River Rch & RM=UNT02162 IN SAND,Reach-1         ,6308
     747    1009    1222    1081    1462    1978    2086
River Rch & RM=UNT02162 IN SAND,Reach-1         ,1630
     921    1262    1543    1378    1863    2520    2706
River Rch & RM=DOGWOODCRETRIB2,Reach-1         ,6308
     747    1009    1222    1081    1462    1978    2086
River Rch & RM=DOGWOODCRETRIB2,Reach-1         ,1630
     921    1262    1543    1378    1863    2520    2706
Boundary for River Rch & Prof#=DOGWOODCRETRIB2,Reach-1         , 1
Up Type= 0
Dn Type= 3
Dn Slope=0.005
Boundary for River Rch & Prof#=DOGWOODCRETRIB2,Reach-1         , 2
Up Type= 0
Dn Type= 3
Dn Slope=0.005
Boundary for River Rch & Prof#=DOGWOODCRETRIB2,Reach-1         , 3
Up Type= 0
Dn Type= 3
Dn Slope=0.005
Boundary for River Rch & Prof#=DOGWOODCRETRIB2,Reach-1         , 4
Up Type= 0
Dn Type= 3
Dn Slope=0.005
Boundary for River Rch & Prof#=DOGWOODCRETRIB2,Reach-1         , 5
Up Type= 0
Dn Type= 3
Dn Slope=0.005
Boundary for River Rch & Prof#=DOGWOODCRETRIB2,Reach-1         , 6
Up Type= 0
Dn Type= 3
Dn Slope=0.005
Boundary for River Rch & Prof#=DOGWOODCRETRIB2,Reach-1         , 7
Up Type= 0
Dn Type= 3
Dn Slope=0.005
DSS Import GetInterval= 0
DSS Import GetPeak= 0
DSS Import FillOption= 0

--- DOGWOODCRETRIB2.g01 (geometry) ---

Geom Title=Existing Conditions
Program Version=4.10

River Reach=DOGWOODCRETRIB2 ,Reach-1
Reach XY= 30
      3539872.11     10466271.64      3540008.11     10466223.77
      3540063.15     10466124.38      3540211.26     10466095.89
      3540646.76     10466311.53      3540869.58     10466127.41
      3540956.44     10466219.39      3541069.53     10466097.86
       3541290.6     10466067.99      3541187.94     10465974.03
      3541210.31     10465917.28      3541380.98     10465949.51
      3541457.35     10465772.72      3541557.63      10465840.2
      3541665.95     10465813.38       3541818.3     10465240.68
      3541953.99     10465249.66      3541971.15     10465336.04
      3542023.32     10465321.41      3542142.88     10464942.42
      3542396.46      10464999.6      3542387.89     10464890.63
      3542572.11     10464811.64      3542607.16     10464588.95
      3542803.52     10464425.05      3542981.24     10464429.18
       3543227.5      10464302.1      3543437.08     10464368.16
      3543798.53     10464387.05      3543872.11     10464341.64

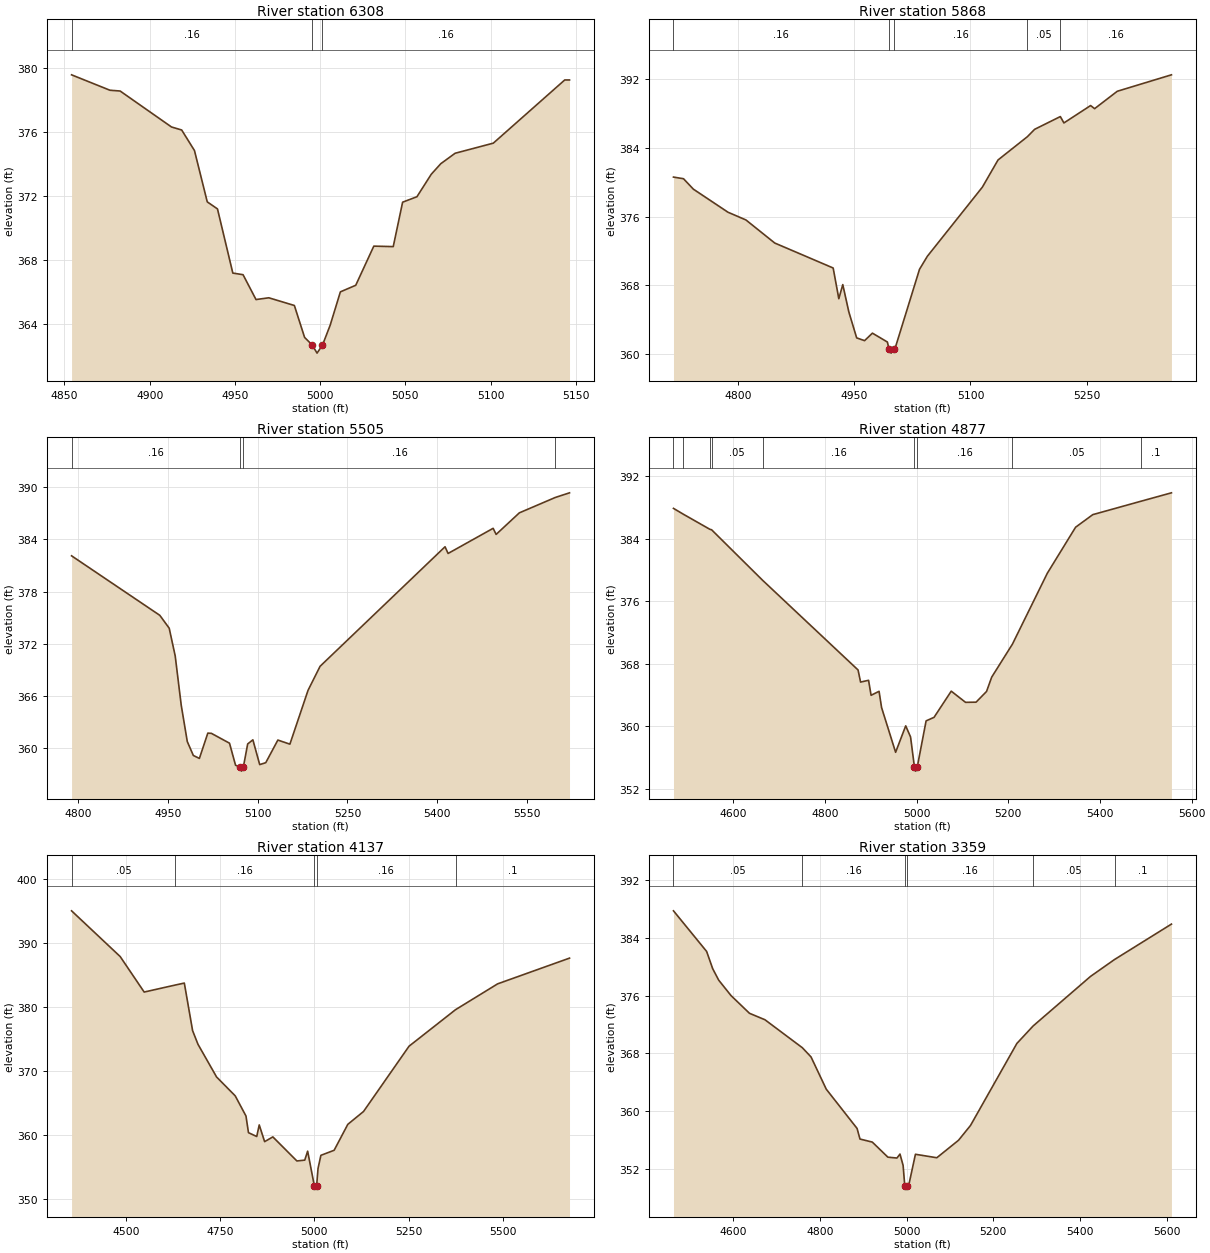
Type RM Length L Ch R = 1 ,6308    ,440,440,440
BEGIN DESCRIPTION:
UNT0752 IN SAND CR 9.0
END DESCRIPTION:
XS GIS Cut Line= 3
       3540092.1     10466341.63      3539992.11     10466191.64
      3539942.09     10466091.62
#Sta/Elev= 30
  4854.2  379.56  4876.7   378.6  4882.7  378.55  4912.8  376.31  4918.8  376.12
  4926.3  374.84  4933.8  371.64  4939.8   371.2  4948.8   367.2  4954.8   367.1
  4962.4  365.55  4969.9  365.66  4984.9  365.18  4990.9  363.19  4995.4  362.71
  4998.2  362.21  5001.4  362.71  5005.9  363.95  5011.9  366.03  5020.9  366.44
  5031.5  368.88  5042.9  368.85  5048.4  371.62  5056.8  371.96  5065.2  373.36
  5070.8  374.02  5079.2  374.67  5101.6   375.3  5143.5  379.24  5146.3  379.24
#Mann= 3 ,-1 , 0
  4854.2     .16       0  4995.4     .07       0  5001.4     .16       0
Bank Sta=4995.4,5001.4
XS Rating Curve= 0 ,0
Exp/Cntr=0.3,0.1

Type RM Length L Ch R = 1 ,5868    ,363,363,363
BEGIN DESCRIPTION:
UNT0752 IN SAND CR 7.1
END DESCRIPTION:
XS GIS Cut Line= 4
      3540250.24     10466454.97      3540304.07     10466335.16
      3540356.15     10466003.56      3540309.73     10465835.05
#Sta/Elev= 30
  4717.2  380.58  4730.1  380.39  4742.8  379.18  4787.4   376.5  4810.6   375.6
  4847.7  372.92    4923  370.02  4930.3  366.45  4935.4  368.09  4943.2  364.92
  4953.3   361.9  4963.5  361.58  4973.6  362.45  4992.9  361.42  4994.9  360.63
  4997.7  360.13  5000.9  360.63  5003.9     361  5034.3  369.87  5044.4  371.38
  5115.3  379.41  5135.5  382.57  5173.3  385.27  5182.7  386.13  5215.8  387.61
  5220.4  386.87  5254.8  388.89    5260  388.53  5289.2  390.55    5359  392.46
#Mann= 5 ,-1 , 0
  4717.2     .16       0  4994.9     .07       0  5000.9     .16       0
  5173.3     .05       0  5215.8     .16       0
Bank Sta=4994.9,5000.9
XS Rating Curve= 0 ,0
Exp/Cntr=0.3,0.1

Type RM Length L Ch R = 1 ,5505    ,628,628,628
BEGIN DESCRIPTION:
UNT0752 IN SAND CR 7.0
END DESCRIPTION:
XS GIS Cut Line= 2
      3540578.71     10466513.31      3540682.89     10465688.57
#Sta/Elev= 30
  4789.5  382.12  4936.8  375.28  4952.5   373.8  4962.5  370.62  4972.6  364.94
  4982.7  360.77  4992.8  359.17  5002.9  358.83    5017  361.74    5023  361.71
  5053.2  360.58  5063.3  358.04  5070.4  357.87  5073.2  357.37  5076.4  357.87
  5083.5  360.49  5092.2  360.97  5103.6  358.12  5113.7  358.34  5133.9  360.94
    5154  360.47  5184.3  366.66  5204.4  369.42    5413  383.16  5418.1  382.39
  5493.3  385.28  5498.3  384.58  5537.1  387.06  5597.2  388.83  5620.8  389.36
#Mann= 4 ,-1 , 0
  4789.5     .16       0  5070.4     .07       0  5076.4     .16       0
  5597.2     .05       0
Bank Sta=5070.4,5076.4
XS Rating Curve= 0 ,0
Exp/Cntr=0.3,0.1

Type RM Length L Ch R = 1 ,4877    ,740,740,740
BEGIN DESCRIPTION:
UNT0752 IN SAND CR 6.0
END DESCRIPTION:
XS GIS Cut Line= 2
       3541247.1     10466610.88      3540789.44     10465626.13
#Sta/Elev= 30
    4470  387.87  4491.6  387.12  4549.2   385.2  4553.2  385.13  4664.2  378.68
  4872.5   367.2    4878  365.65  4895.4  365.88  4900.9  363.96  4918.3  364.47
  4923.8  362.39  4954.4  356.67  4976.4  360.05    4987  358.63  4995.5  354.76
  4998.2  354.26  5001.5  354.76  5020.9  360.69  5038.2  361.14  5075.7  364.49
  5106.9  363.06  5129.8  363.08  5152.7  364.45  5163.9  366.28  5209.2  370.51
  5285.2  379.57  5346.9  385.46  5384.4  387.07  5489.2  388.78  5555.9  389.86
#Mann= 9 ,-1 , 0
    4470     .16       0  4491.6     .05       0  4549.2     .16       0
  4553.2     .05       0  4664.2     .16       0  4995.5     .07       0
  5001.5     .16       0  5209.2     .05       0  5489.2      .1       0
Bank Sta=4995.5,5001.5
XS Rating Curve= 0 ,0
Exp/Cntr=0.3,0.1

Type RM Length L Ch R = 1 ,4137    ,778,778,778
BEGIN DESCRIPTION:
UNT0752 IN SAND CR 4.0
END DESCRIPTION:
XS GIS Cut Line= 2
      3541895.96     10466339.62      3540898.11     10465476.27
#Sta/Elev= 30
  4356.5  395.02  4485.3  387.88  4548.9  382.33  4630.9  383.42  4655.3  383.73
  4677.2  376.31  4691.4  374.18  4740.8  369.06  4790.2  366.11  4818.7  362.96
  4825.3  360.36  4847.2  359.76  4853.8  361.57  4868.1  358.96  4889.9   359.7
  4953.6  355.94  4974.4  356.07  4982.1  357.47  4999.9  352.04  5002.7  351.54
  5005.9  352.04  5009.6  354.76  5017.2  356.82  5052.3  357.61  5088.5  361.66
  5130.2  363.67  5250.8  373.87  5373.9  379.57  5485.5  383.61    5676  387.63
#Mann= 5 ,-1 , 0
  4356.5     .05       0  4630.9     .16       0  4999.9     .07       0
  5005.9     .16       0  5373.9      .1       0
Bank Sta=4999.9,5005.9
XS Rating Curve= 0 ,0
Exp/Cntr=0.3,0.1

Type RM Length L Ch R = 1 ,3359    ,769,769,769
BEGIN DESCRIPTION:
UNT0752 IN SAND CR 3.0
END DESCRIPTION:
XS GIS Cut Line= 2
      3542139.02     10465862.19      3541288.39     10465091.85
#Sta/Elev= 30
  4462.8  387.76  4539.2  382.13  4553.1  379.75  4566.9  378.16  4595.3  376.02
  4637.9  373.56  4673.7  372.66  4759.9  368.78  4779.8  367.51  4814.9  363.04
  4885.9   357.6  4892.6  356.13    4921  355.71  4956.9  353.62  4977.8   353.5
  4984.8  354.05    4992  352.47  4995.8  349.69  4998.5  349.19  5001.8  349.69
  5006.2  350.07  5020.4  354.02  5069.7  353.54  5119.7  355.96  5147.4  358.02
  5254.2  369.38  5291.8  371.81  5423.9  378.67  5479.2  381.01  5610.4  385.92
#Mann= 6 ,-1 , 0
  4462.8     .05       0  4759.9     .16       0  4995.8     .07       0
  5001.8     .16       0  5291.8     .05       0  5479.2      .1       0
Bank Sta=4995.8,5001.8
XS Rating Curve= 0 ,0
Exp/Cntr=0.3,0.1

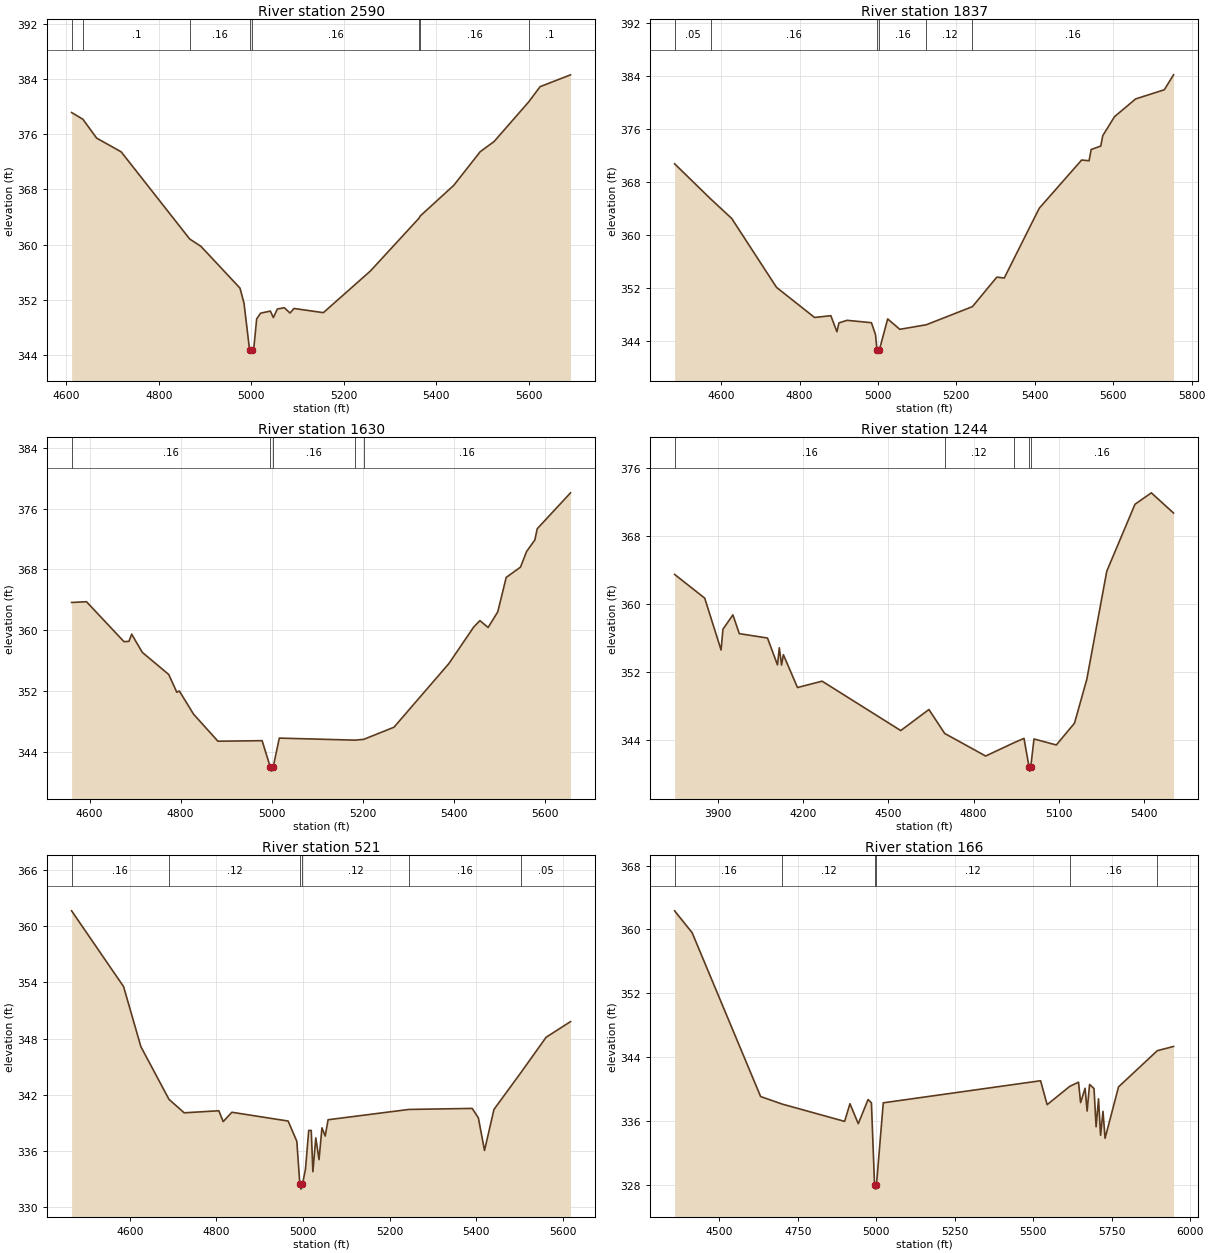
Type RM Length L Ch R = 1 ,2590    ,753,753,753
BEGIN DESCRIPTION:
UNT0752 IN SAND CR 2.0
END DESCRIPTION:
XS GIS Cut Line= 3
      3542304.46     10465510.46      3542187.26     10465263.04
      3541517.35     10464816.44
#Sta/Elev= 30
  4611.2  379.18  4635.7   378.2  4665.2  375.47  4718.4  373.47  4866.6   360.8
  4890.8  359.74  4975.3  353.67    4984  351.48    4996  344.72  4998.8  344.22
    5002  344.72    5005  344.83  5011.4   349.2    5020  350.03  5041.1  350.33
  5047.4  349.38  5056.1  350.63  5071.1  350.82  5083.5  350.05  5092.1  350.71
  5155.6   350.1  5257.4  356.16  5362.6  363.84  5364.8  364.13  5437.7  368.61
  5494.8  373.49  5524.8  374.97  5599.8  380.74  5624.3  382.94  5690.1  384.66
#Mann= 8 ,-1 , 0
  4611.2     .05       0  4635.7      .1       0  4866.6     .16       0
    4996     .07       0    5002     .16       0  5362.6      .1       0
  5364.8     .16       0  5599.8      .1       0
Bank Sta=4996,5002
XS Rating Curve= 0 ,0
Exp/Cntr=0.3,0.1

Type RM Length L Ch R = 1 ,1837    ,207,207,207
BEGIN DESCRIPTION:
UNT0752 IN SAND CR 1.0
END DESCRIPTION:
XS GIS Cut Line= 4
       3542338.7     10465376.13      3542455.89     10464944.25
      3542416.83     10464796.69      3541791.85      10464549.3
#Sta/Elev= 30
  4481.5  370.79  4573.1   365.5  4627.1  362.53  4741.4  352.11  4838.4  347.56
  4879.9  347.83  4895.4   345.4  4900.6  346.74  4921.3  347.13  4983.4  346.77
  4993.8  344.97  4997.7  342.67  5000.4  342.17  5003.7  342.67  5024.8  347.34
  5055.8  345.77  5123.4  346.46    5241   349.2  5303.2  353.66  5322.1  353.52
  5411.3  364.07  5519.4  371.36  5538.4  371.25  5543.7  372.95  5568.1  373.47
  5573.4  375.05  5603.2  377.91  5657.2   380.6  5730.2  381.98  5753.8  384.24
#Mann= 6 ,-1 , 0
  4481.5     .05       0  4573.1     .16       0  4997.7     .07       0
  5003.7     .16       0  5123.4     .12       0    5241     .16       0
Bank Sta=4997.7,5003.7
XS Rating Curve= 0 ,0
Exp/Cntr=0.3,0.1

Type RM Length L Ch R = 1 ,1630    ,386,386,386
BEGIN DESCRIPTION:
UNT02162 IN SAND CR 3.0
END DESCRIPTION:
XS GIS Cut Line= 3
      3542840.02     10465107.04       3542709.8     10464808.62
      3541980.67     10464562.32
#Sta/Elev= 30
  4560.6  363.65  4593.3  363.75  4675.6  358.49  4686.5  358.53  4692.4  359.48
  4715.8  357.08  4773.8  354.17  4791.5  351.83    4797     352  4828.3  348.94
  4881.8  345.38  4978.8  345.45  4996.9  341.94  4999.6  341.44  5002.9  341.94
  5016.5  345.79  5182.5  345.52  5201.6  345.62  5268.2  347.22  5388.7   355.6
  5443.2  360.41  5456.9  361.26  5474.9  360.36    5496  362.41  5514.6  366.95
    5546  368.31  5559.3  370.36  5577.5  371.89  5582.7  373.36  5655.8  378.09
#Mann= 5 ,-1 , 0
  4560.6     .16       0  4996.9     .07       0  5002.9     .16       0
  5182.5     .12       0  5201.6     .16       0
Bank Sta=4996.9,5002.9
XS Rating Curve= 0 ,0
Exp/Cntr=0.3,0.1

Type RM Length L Ch R = 1 ,1244    ,723,723,723
BEGIN DESCRIPTION:
UNT02162 IN SAND CR 2.0
END DESCRIPTION:
XS GIS Cut Line= 2
      3543532.26     10465460.73      3542440.68     10464082.68
#Sta/Elev= 30
  3746.4  363.48  3852.5  360.68  3910.2  354.57  3916.6  357.01  3951.8  358.71
  3974.3   356.5  4073.7  355.98  4108.9  352.82  4115.3  354.83  4123.3   352.8
  4129.7  354.02  4179.4  350.15    4266   350.9  4543.2  345.08  4642.5  347.56
    4698  344.74  4842.4  342.08  4941.2  343.63  4977.5  344.16  4995.3   340.8
  4998.1   340.3  5001.3   340.8  5012.7  344.09  5091.3  343.38  5155.4  345.95
  5198.7   351.1  5269.1  363.85  5368.5  371.74  5426.2  373.09  5504.4  370.71
#Mann= 5 ,-1 , 0
  3746.4     .16       0    4698     .12       0  4941.2     .16       0
  4995.3     .07       0  5001.3     .16       0
Bank Sta=4995.3,5001.3
XS Rating Curve= 0 ,0
Exp/Cntr=0.3,0.1

Type RM Length L Ch R = 1 ,521     ,355,355,355
BEGIN DESCRIPTION:
UNT02162 IN SAND CR 1.0
END DESCRIPTION:
XS GIS Cut Line= 3
      3543392.11      10464891.6      3543392.11     10464341.64
      3542942.14     10463941.67
#Sta/Elev= 30
  4465.7  361.64  4585.7  353.55  4625.7  347.13  4690.5  341.51  4725.7  340.07
  4805.7  340.29  4815.7  339.13  4835.7  340.13  4965.7  339.19  4985.7  337.03
  4992.7  332.42  4995.4  331.92  4998.7  332.42  5005.7  334.07  5013.2  338.19
    5019  338.19  5022.8  333.78  5029.5  337.39    5037  335.07  5043.7  338.47
  5051.2  337.59  5057.9  339.33  5244.5  340.43  5390.7  340.54  5404.9  339.53
  5419.1  336.05  5440.9  340.43  5503.8  344.41  5561.3  348.14  5617.7  349.81
#Mann= 6 ,-1 , 0
  4465.7     .16       0  4690.5     .12       0  4992.7     .07       0
  4998.7     .12       0  5244.5     .16       0  5503.8     .05       0
Bank Sta=4992.7,4998.7
XS Rating Curve= 0 ,0
Exp/Cntr=0.3,0.1

Type RM Length L Ch R = 1 ,166     ,0,0,0
BEGIN DESCRIPTION:
UNT02162 IN SAND CR 1.01
END DESCRIPTION:
XS GIS Cut Line= 5
      3543503.69     10464948.56      3543751.08     10464435.54
      3543693.79      10464284.5      3543360.46     10464242.84
      3542960.82     10463905.48
#Sta/Elev= 30
  4357.4  362.34  4413.2   359.6  4631.5  339.04  4701.1  338.08  4899.2  335.92
  4916.2  338.14  4942.7  335.63  4973.9  338.66  4984.6  338.25  4994.6  327.92
  4997.3  327.42  5000.6  327.92  5022.4  338.25  5523.7  341.02  5544.6  338.02
  5616.9  340.32  5644.6  340.84  5651.2  338.28  5665.5  340.08    5672  337.22
  5679.8  340.55    5694  340.04  5700.6  335.24  5708.3  338.75  5714.9  334.17
  5722.6  337.18  5729.2   333.8  5772.1  340.25  5895.6  344.79  5947.4  345.32
#Mann= 6 ,-1 , 0
  4357.4     .16       0  4701.1     .12       0  4994.6     .07       0
  5000.6     .12       0  5616.9     .16       0  5895.6     .05       0
Bank Sta=4994.6,5000.6
XS Rating Curve= 0 ,0
Exp/Cntr=0.3,0.1

Chan Stop Cuts=-1
Use User Specified Reach Order=0
Composite Channel Slope=5