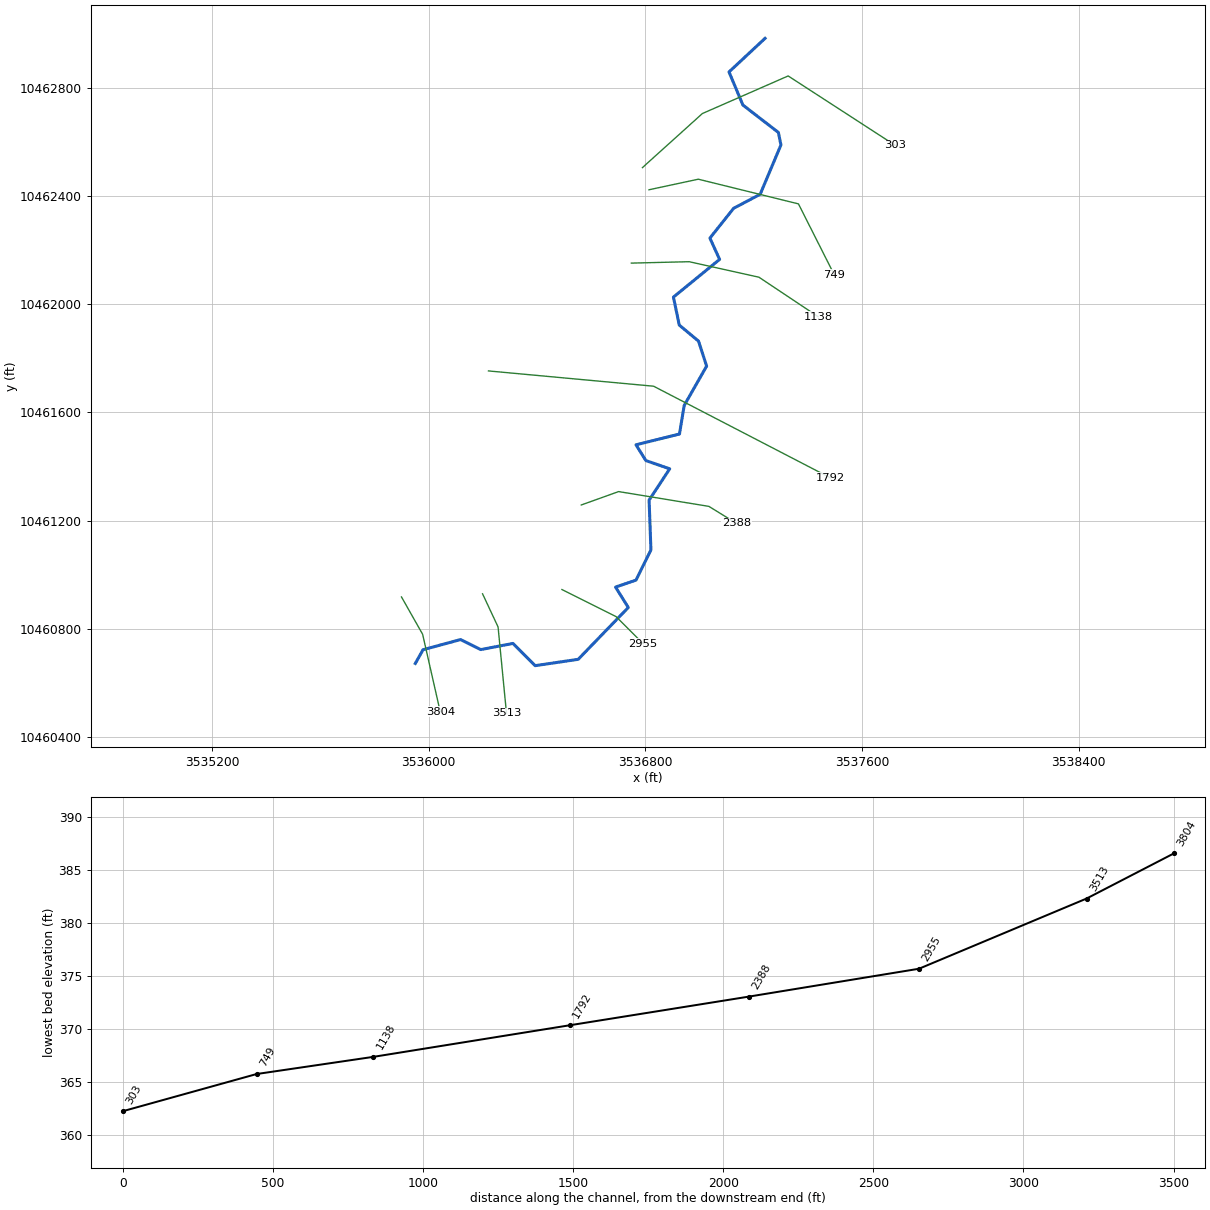
--- DOGWOODCRETRIB4.prj (project) ---

Proj Title=DOGWOOD CR E TRIB4  Base Level Engineeri
Current Plan=p01
Default Exp/Contr=0.3,0.1
English Units
Geom File=g01
Flow File=f01
Plan File=p01
Y Axis Title=Elevation
X Axis Title(PF)=Main Channel Distance
X Axis Title(XS)=Station
BEGIN DESCRIPTION:
UNT02159 IN SAND CR
END DESCRIPTION:
DSS Export Rating Curves= 0
DSS Export Rating Curve Sorted= 0
DSS Export Volume Flow Curves= 0
DXF OffsetX= 0
DXF OffsetY= 0
DXF ScaleX= 1
DXF ScaleY= 10

--- DOGWOODCRETRIB4.p01 (plan) ---

Plan Title=Multiple Run
Short Identifier=Multiple
Geom File=g01
Flow File=f01
Subcritical Flow
K Sum by GR= 0
Std Step Tol= 0.01
Critical Tol= 0.01
Num of Std Step Trials= 20
Max Error Tol= 0.3
Flow Tol Ratio= 0.001
Split Flow NTrial= 30
Split Flow Tol= 0.02
Split Flow Ratio= 0.02
Log Output Level= 0
Friction Slope Method= 1
Unsteady Friction Slope Method= 2
Unsteady Bridges Friction Slope Method= 1
Parabolic Critical Depth
Global Vel Dist=  1 , 1 , 1
Global Log Level= 0
CheckData=True
Encroach Param= -1, 0, 0, 0
BEGIN DESCRIPTION:
Multiple Run
END DESCRIPTION:

--- DOGWOODCRETRIB4.f01 (steady flow) ---

Flow Title=Multiple
Program Version=4.10
Number of Profiles= 7
Profile Names=10-year,25-year,50-year,1pct_min,100-year,1pct_plu,500-year
River Rch & RM=UNT02159 IN SAND,Reach-1         ,3804
     406     528     623     539     729     986     992
River Rch & RM=EAST TRIBUTARY 4,Reach-1         ,3804
     406     528     623     539     729     986     992
River Rch & RM=GWOOD CR E TRIB4,Reach-1         ,3804
     406     528     623     539     729     986     992
River Rch & RM=DOGWOOD E TRB 4,Reach-1         ,3804
     406     528     623     539     729     986     992
Boundary for River Rch & Prof#=DOGWOOD E TRB 4,Reach-1         , 1
Up Type= 0
Dn Type= 3
Dn Slope=0.005
Boundary for River Rch & Prof#=DOGWOOD E TRB 4,Reach-1         , 2
Up Type= 0
Dn Type= 3
Dn Slope=0.005
Boundary for River Rch & Prof#=DOGWOOD E TRB 4,Reach-1         , 3
Up Type= 0
Dn Type= 3
Dn Slope=0.005
Boundary for River Rch & Prof#=DOGWOOD E TRB 4,Reach-1         , 4
Up Type= 0
Dn Type= 3
Dn Slope=0.005
Boundary for River Rch & Prof#=DOGWOOD E TRB 4,Reach-1         , 5
Up Type= 0
Dn Type= 3
Dn Slope=0.005
Boundary for River Rch & Prof#=DOGWOOD E TRB 4,Reach-1         , 6
Up Type= 0
Dn Type= 3
Dn Slope=0.005
Boundary for River Rch & Prof#=DOGWOOD E TRB 4,Reach-1         , 7
Up Type= 0
Dn Type= 3
Dn Slope=0.005
DSS Import GetInterval= 0
DSS Import GetPeak= 0
DSS Import FillOption= 0

--- DOGWOODCRETRIB4.g01 (geometry) ---

Geom Title=Existing Conditions
Program Version=4.10

River Reach=DOGWOOD E TRB 4 ,Reach-1
Reach XY= 30
      3535950.41     10460672.95        3535979.     10460723.65
      3536117.39     10460761.21      3536192.17      10460724.2
       3536311.2     10460746.88      3536393.03      10460664.8
      3536552.03     10460688.26      3536736.98     10460879.61
      3536689.92     10460955.02      3536765.48     10460980.74
      3536820.62     10461092.37      3536813.87     10461276.14
      3536890.01     10461391.79      3536801.89     10461422.26
      3536765.47     10461480.45      3536926.08     10461520.29
       3536943.6       10461626.      3537026.33     10461771.08
      3536996.41     10461863.42      3536925.18     10461922.71
      3536903.78     10462026.01      3537074.25     10462165.19
      3537038.45     10462243.92      3537126.07     10462353.91
      3537224.08     10462405.69      3537300.74     10462587.83
      3537291.31     10462634.09      3537160.31     10462735.24
      3537109.02     10462857.51      3537242.11     10462981.64

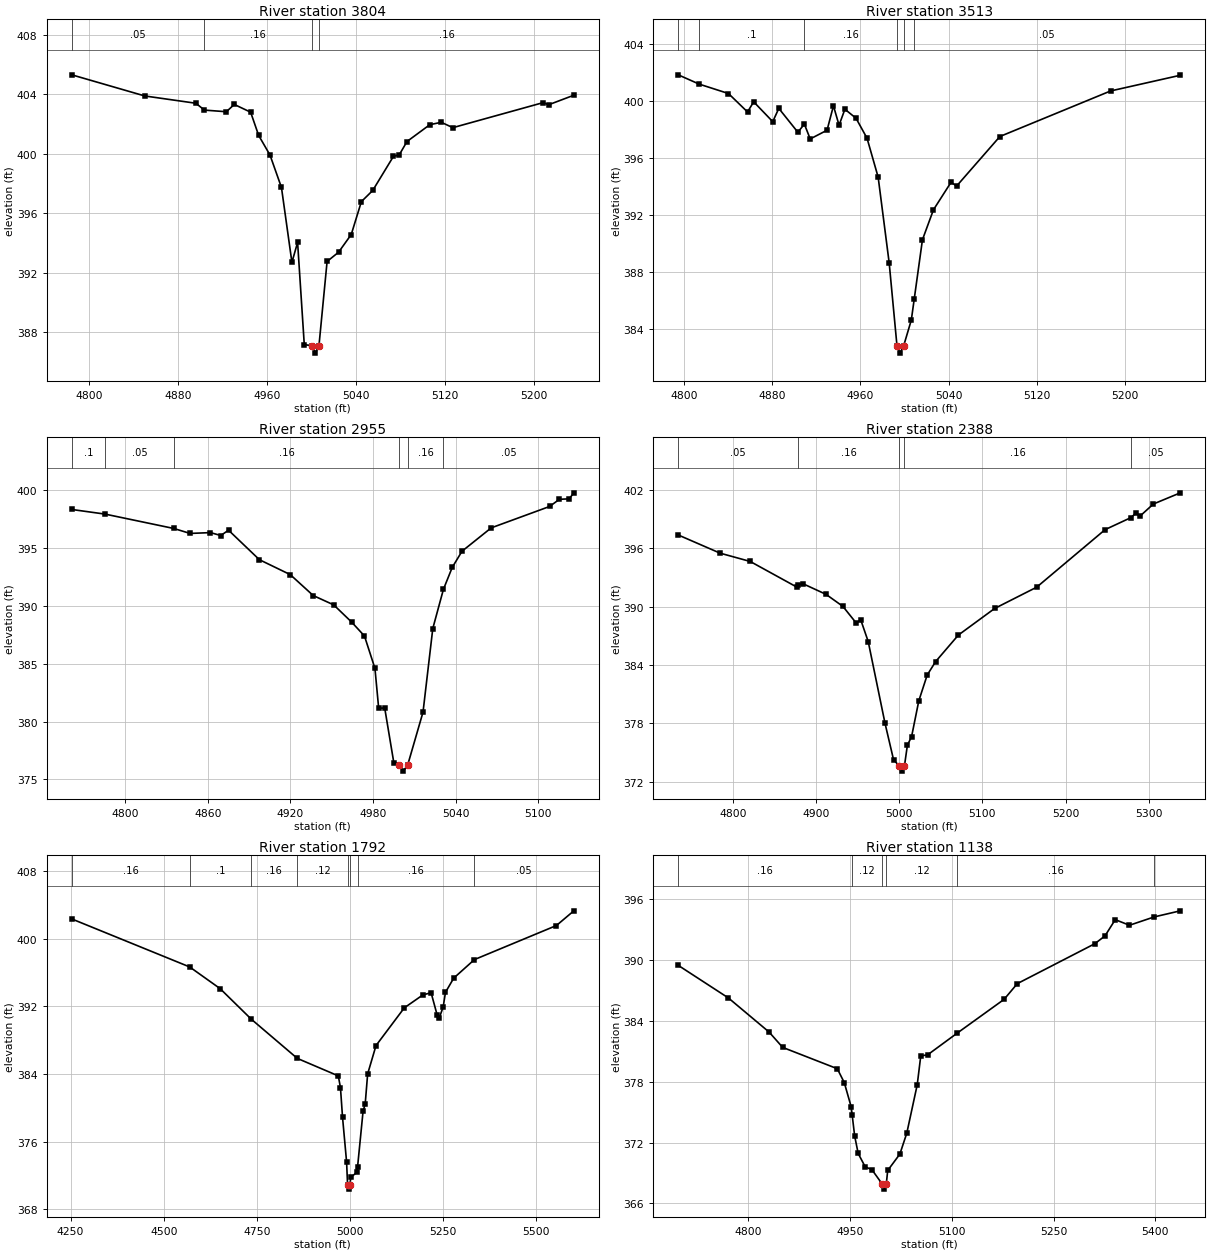
Type RM Length L Ch R = 1 ,3804    ,291,291,291
BEGIN DESCRIPTION:
UNT02159 IN SAND CR 7.1
END DESCRIPTION:
XS GIS Cut Line= 3
      3535899.35      10460918.7      3535977.48     10460780.67
       3536042.3     10460495.46
#Sta/Elev= 30
  4784.7   405.3  4850.3  403.88  4896.2  403.39  4903.9  402.93  4923.6  402.82
  4930.7  403.31  4945.4  402.79  4952.6  401.23  4962.8  399.91  4973.1  397.73
  4982.5   392.7  4987.6  394.04  4993.6  387.17  5000.8   387.1  5003.6   386.6
  5006.8   387.1  5014.1  392.76  5024.4  393.38  5035.8  394.57  5044.9  396.78
  5055.1  397.53  5073.7  399.82  5078.9  399.92  5085.9  400.82  5106.4  401.95
  5116.7  402.11  5127.1  401.75  5208.1  403.43  5213.2  403.29  5235.8  403.93
#Mann= 4 ,-1 , 0
  4784.7     .05       0  4903.9     .16       0  5000.8     .07       0
  5006.8     .16       0
Bank Sta=5000.8,5006.8
XS Rating Curve= 0 ,0
Exp/Cntr=0.3,0.1

Type RM Length L Ch R = 1 ,3513    ,558,558,558
BEGIN DESCRIPTION:
UNT02159 IN SAND CR 7.0
END DESCRIPTION:
XS GIS Cut Line= 3
      3536198.79     10460930.15      3536256.09     10460807.75
      3536287.22     10460488.61
#Sta/Elev= 30
  4794.6  401.83  4813.6  401.18  4840.2  400.52  4857.5  399.23  4863.1  399.94
  4880.4  398.55  4885.9  399.48  4903.2  397.81  4909.1  398.38  4914.4  397.34
  4929.7  397.95  4935.5  399.66  4940.6   398.3  4945.9  399.42    4956  398.79
    4966  397.39  4976.1  394.66  4986.1  388.66  4993.2  382.84  4995.9  382.34
  4999.2  382.84  5006.2  384.66  5008.9  386.16  5016.3  390.28  5026.3  392.38
  5042.3  394.31  5047.3  394.04  5086.6  397.51  5187.1   400.7  5250.4   401.8
#Mann= 6 ,-1 , 0
  4794.6     .05       0  4813.6      .1       0  4909.1     .16       0
  4993.2     .07       0  4999.2     .16       0  5008.9     .05       0
Bank Sta=4993.2,4999.2
XS Rating Curve= 0 ,0
Exp/Cntr=0.3,0.1

Type RM Length L Ch R = 1 ,2955    ,567,567,567
BEGIN DESCRIPTION:
UNT02159 IN SAND CR 6.0
END DESCRIPTION:
XS GIS Cut Line= 3
        3536492.     10460945.91      3536692.02      10460845.9
      3536791.63     10460746.29
#Sta/Elev= 30
  4761.3  398.34  4785.5  397.94  4835.3   396.7  4847.2  396.27    4862  396.34
  4869.5  396.09  4875.1  396.55  4897.5     394  4919.9  392.71  4936.6   390.9
  4951.5  390.09  4964.6  388.59  4973.8   387.4  4981.4   384.6  4984.1  381.17
  4988.5  381.17  4995.1  376.45  4999.1  376.22  5001.9  375.72  5005.1  376.22
  5016.3  380.82  5023.4  388.05  5031.1  391.43  5037.5  393.33  5044.6  394.73
  5065.8  396.75  5108.2   398.6  5115.3  399.22  5122.4  399.26  5125.8  399.78
#Mann= 6 ,-1 , 0
  4761.3      .1       0  4785.5     .05       0  4835.3     .16       0
  4999.1     .07       0  5005.1     .16       0  5031.1     .05       0
Bank Sta=4999.1,5005.1
XS Rating Curve= 0 ,0
Exp/Cntr=0.3,0.1

Type RM Length L Ch R = 1 ,2388    ,596,596,596
BEGIN DESCRIPTION:
UNT02159 IN SAND CR 4.0
END DESCRIPTION:
XS GIS Cut Line= 4
      3536563.42     10461258.29       3536701.4     10461307.75
      3537034.73     10461253.07      3537136.27     10461190.58
#Sta/Elev= 30
  4734.3  397.35  4784.7  395.48  4820.8  394.63    4877  391.99  4878.3  392.21
  4883.8  392.36    4912  391.25  4932.3  390.01  4948.5  388.28  4953.6  388.66
  4962.7   386.4  4982.9     378  4993.1  374.28  5000.2  373.59    5003  373.09
  5006.2  373.59  5009.8  375.76  5014.8  376.62  5023.5  380.31  5033.6  382.96
  5043.7  384.34  5071.1  387.07  5114.7   389.8  5165.3  391.99  5247.5   397.9
  5278.7  399.14  5284.2  399.58    5290  399.33  5305.5  400.53  5337.9  401.68
#Mann= 5 ,-1 , 0
  4734.3     .05       0  4878.3     .16       0  5000.2     .07       0
  5006.2     .16       0  5278.7     .05       0
Bank Sta=5000.2,5006.2
XS Rating Curve= 0 ,0
Exp/Cntr=0.3,0.1

Type RM Length L Ch R = 1 ,1792    ,654,654,654
BEGIN DESCRIPTION:
UNT02159 IN SAND CR 3.0
END DESCRIPTION:
XS GIS Cut Line= 3
      3536220.61     10461753.32      3536830.46      10461696.9
      3537483.69     10461358.34
#Sta/Elev= 30
  4253.1  402.36  4569.7  396.68  4651.3  394.12  4735.1   390.5  4858.7  385.86
  4968.8  383.79  4974.6   382.4  4980.2  378.88  4991.1  373.59  4993.7  370.89
  4996.5  370.39  4999.7  370.89  5002.6   371.8  5018.8  372.38  5020.5     373
  5035.3   379.6    5041  380.46  5047.6  384.02  5070.1  387.38    5146  391.84
  5195.9  393.37    5218  393.63  5234.5  390.95  5240.1  390.68  5250.4  391.94
  5256.6  393.68  5278.8  395.36  5334.3  397.55  5554.5  401.58  5601.3  403.32
#Mann= 8 ,-1 , 0
  4253.1     .16       0  4569.7      .1       0  4735.1     .16       0
  4858.7     .12       0  4993.7     .07       0  4999.7     .12       0
  5020.5     .16       0  5334.3     .05       0
Bank Sta=4993.7,4999.7
XS Rating Curve= 0 ,0
Exp/Cntr=0.3,0.1

Type RM Length L Ch R = 1 ,1138    ,389,389,389
BEGIN DESCRIPTION:
UNT02159 IN SAND CR 2.0
END DESCRIPTION:
XS GIS Cut Line= 4
      3536748.26      10462151.5      3536961.82     10462156.71
      3537219.63     10462099.42      3537437.77     10461953.99
#Sta/Elev= 30
  4696.8  389.45  4770.7  386.24  4830.7  382.88  4850.7  381.37  4931.2  379.27
  4941.5   377.9  4951.7  375.51  4953.2  374.67  4956.8  372.64    4962  370.92
  4972.2  369.62  4982.4  369.31  4997.4  367.91  5000.1  367.41  5003.4  367.91
  5005.5  369.25  5023.4  370.86  5033.6  372.92    5049  377.69  5054.2  380.53
  5064.4  380.64  5107.8  382.77    5177   386.1  5196.5  387.65  5310.7  391.58
  5325.7  392.35  5340.8  393.95  5361.8   393.4  5398.2  394.22  5436.7  394.82
#Mann= 6 ,-1 , 0
  4696.8     .16       0  4953.2     .12       0  4997.4     .07       0
  5003.4     .12       0  5107.8     .16       0  5398.2     .05       0
Bank Sta=4997.4,5003.4
XS Rating Curve= 0 ,0
Exp/Cntr=0.3,0.1

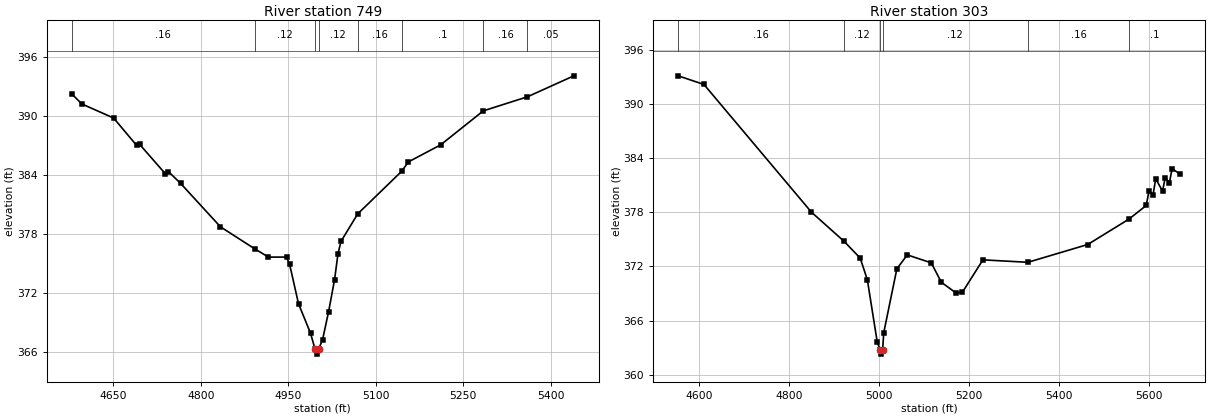
Type RM Length L Ch R = 1 ,749     ,446,446,446
BEGIN DESCRIPTION:
UNT02159 IN SAND CR 1.1
END DESCRIPTION:
XS GIS Cut Line= 4
      3536813.39     10462422.34      3536995.67      10462461.4
      3537365.46     10462370.25      3537497.67     10462108.42
#Sta/Elev= 30
  4578.9  392.23  4596.2  391.21  4650.7  389.78  4689.9  387.01    4695  387.12
  4739.4  384.11  4744.5  384.34  4765.3  383.15  4833.7  378.73  4892.2   376.5
  4916.1  375.65    4947  375.65  4952.3  374.91  4967.6   370.9  4988.2  367.91
  4995.9  366.29  4998.7  365.79  5001.9  366.29  5008.8  367.26  5019.1   370.1
  5029.4  373.37  5035.2  375.99  5040.4  377.25    5069  380.04  5144.4  384.37
  5155.8  385.32  5211.3  387.06  5284.3  390.51    5360  391.94  5439.5  394.07
#Mann= 8 ,-1 , 0
  4578.9     .16       0  4892.2     .12       0  4995.9     .07       0
  5001.9     .12       0    5069     .16       0  5144.4      .1       0
  5284.3     .16       0    5360     .05       0
Bank Sta=4995.9,5001.9
XS Rating Curve= 0 ,0
Exp/Cntr=0.3,0.1

Type RM Length L Ch R = 1 ,303     ,0,0,0
BEGIN DESCRIPTION:
UNT02159 IN SAND CR 1.0
END DESCRIPTION:
XS GIS Cut Line= 4
      3536789.21     10462504.17      3537010.58     10462703.84
      3537327.42     10462842.73      3537722.41     10462586.64
#Sta/Elev= 30
    4554   393.1  4611.2  392.14  4849.8     378  4922.5  374.76  4958.1  372.91
  4973.9  370.51  4995.7  363.67  5001.9  362.78  5004.6  362.28  5007.9  362.78
  5010.3  364.65  5039.4  371.72  5062.5  373.27  5115.8  372.39  5138.1  370.24
  5170.4  369.07  5184.8  369.12  5230.5  372.72  5330.4  372.45  5463.2  374.42
  5554.7  377.23  5593.1  378.74  5599.1  380.31  5608.3  379.95  5614.2  381.69
  5629.4  380.34  5635.3  381.84  5644.5  381.25  5650.5  382.81  5668.8  382.21
#Mann= 6 ,-1 , 0
    4554     .16       0  4922.5     .12       0  5001.9     .07       0
  5007.9     .12       0  5330.4     .16       0  5554.7      .1       0
Bank Sta=5001.9,5007.9
XS Rating Curve= 0 ,0
Exp/Cntr=0.3,0.1

Chan Stop Cuts=-1
Use User Specified Reach Order=0
Composite Channel Slope=5