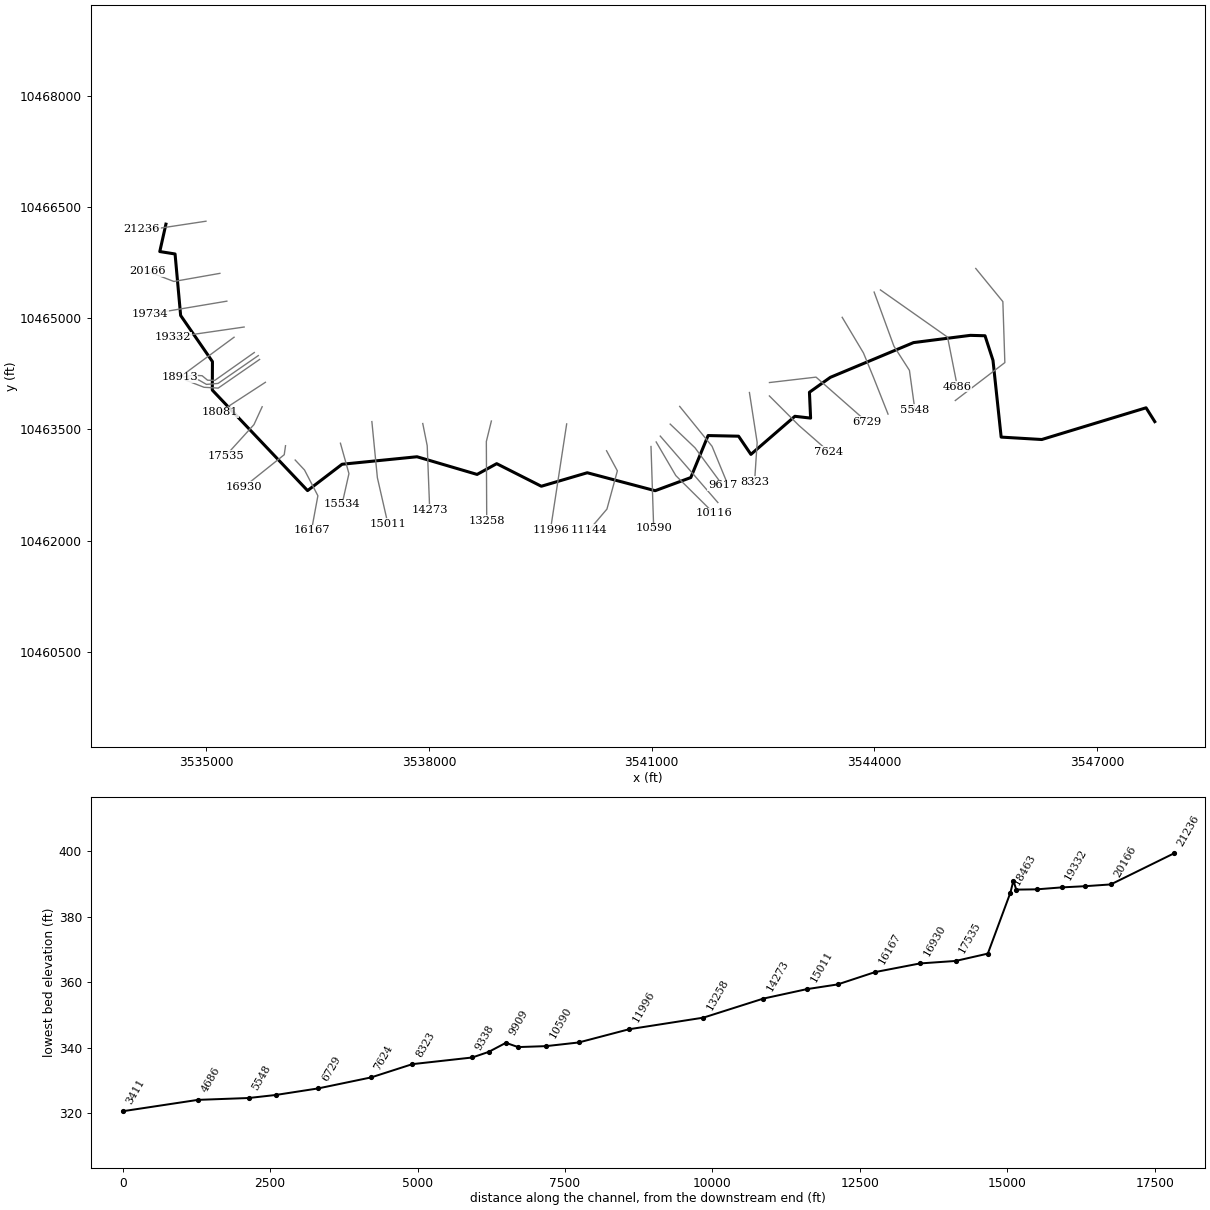
--- DOGWOOD CREEKEAST.prj (project) ---

Proj Title=DOGWOOD CREEK EASTBase Level Engineering
Current Plan=p01
Default Exp/Contr=0.3,0.1
English Units
Geom File=g01
Flow File=f01
Plan File=p01
Y Axis Title=Elevation
X Axis Title(PF)=Main Channel Distance
X Axis Title(XS)=Station
BEGIN DESCRIPTION:
DOGWOOD CREEK
END DESCRIPTION:
DSS Export Rating Curves= 0
DSS Export Rating Curve Sorted= 0
DSS Export Volume Flow Curves= 0
DXF OffsetX= 0
DXF OffsetY= 0
DXF ScaleX= 1
DXF ScaleY= 10

--- DOGWOOD CREEKEAST.p01 (plan) ---

Plan Title=Multiple Run
Short Identifier=Multiple
Geom File=g01
Flow File=f01
Subcritical Flow
K Sum by GR= 0
Std Step Tol= 0.01
Critical Tol= 0.01
Num of Std Step Trials= 20
Max Error Tol= 0.3
Flow Tol Ratio= 0.001
Split Flow NTrial= 30
Split Flow Tol= 0.02
Split Flow Ratio= 0.02
Log Output Level= 0
Friction Slope Method= 1
Unsteady Friction Slope Method= 2
Unsteady Bridges Friction Slope Method= 1
Parabolic Critical Depth
Global Vel Dist=  1 , 1 , 1
Global Log Level= 0
CheckData=True
Encroach Param= -1, 0, 0, 0
BEGIN DESCRIPTION:
Multiple Run
END DESCRIPTION:

--- DOGWOOD CREEKEAST.f01 (steady flow) ---

Flow Title=Multiple
Program Version=4.10
Number of Profiles= 7
Profile Names=10-year,25-year,50-year,1pct_min,100-year,1pct_plu,500-year
River Rch & RM=DOGWOOD CREEK,Reach-1         ,21236
     924    1267    1549    1383    1870    2529    2717
River Rch & RM=DOGWOOD CREEK,Reach-1         ,15011
    1455    2036    2522    2277    3079    4164    4576
River Rch & RM=DOGWOOD CREEK,Reach-1         ,9617
    1543    2163    2683    2423    3277    4432    4881
River Rch & RM=DOGWOOD CREEK,Reach-1         ,6005
    1962    2777    3466    3148    4257    5757    6408
River Rch & RM=DOGWOOD CREEK EA,Reach-1         ,21236
     924    1267    1549    1383    1870    2529    2717
River Rch & RM=DOGWOOD CREEK EA,Reach-1         ,15011
    1455    2036    2522    2277    3079    4164    4576
River Rch & RM=DOGWOOD CREEK EA,Reach-1         ,9617
    1543    2163    2683    2423    3277    4432    4881
River Rch & RM=DOGWOOD CREEK EA,Reach-1         ,6005
    1962    2777    3466    3148    4257    5757    6408
Boundary for River Rch & Prof#=DOGWOOD CREEK EA,Reach-1         , 1
Up Type= 0
Dn Type= 3
Dn Slope=0.005
Boundary for River Rch & Prof#=DOGWOOD CREEK EA,Reach-1         , 2
Up Type= 0
Dn Type= 3
Dn Slope=0.005
Boundary for River Rch & Prof#=DOGWOOD CREEK EA,Reach-1         , 3
Up Type= 0
Dn Type= 3
Dn Slope=0.005
Boundary for River Rch & Prof#=DOGWOOD CREEK EA,Reach-1         , 4
Up Type= 0
Dn Type= 3
Dn Slope=0.005
Boundary for River Rch & Prof#=DOGWOOD CREEK EA,Reach-1         , 5
Up Type= 0
Dn Type= 3
Dn Slope=0.005
Boundary for River Rch & Prof#=DOGWOOD CREEK EA,Reach-1         , 6
Up Type= 0
Dn Type= 3
Dn Slope=0.005
Boundary for River Rch & Prof#=DOGWOOD CREEK EA,Reach-1         , 7
Up Type= 0
Dn Type= 3
Dn Slope=0.005
DSS Import GetInterval= 0
DSS Import GetPeak= 0
DSS Import FillOption= 0

--- DOGWOOD CREEKEAST.g01 (geometry) ---

Geom Title=Existing Conditions
Program Version=4.10

River Reach=DOGWOOD CREEK EA,Reach-1
Reach XY= 30
      3534453.76     10466267.28      3534371.08     10465897.68
      3534576.98     10465865.04       3534652.1     10465035.95
       3535080.8     10464413.54      3535078.71     10464029.69
      3536362.63      10462674.3      3536827.85     10463029.73
      3537837.34     10463130.73      3538646.73     10462892.41
      3538911.04     10463037.47      3539512.68     10462732.94
      3540131.61     10462915.06       3541046.7     10462673.01
      3541526.85     10462850.23      3541759.86     10463416.56
      3542170.56      10463407.9      3542336.91     10463162.74
      3542929.41     10463676.25      3543141.26     10463651.92
      3543125.67     10464000.23      3543407.21      10464201.4
      3544528.34       10464670.      3545294.01      10464767.7
      3545491.57     10464762.26      3545599.14     10464430.47
      3545709.27     10463395.64      3546256.36     10463363.17
      3547661.81      10463790.8      3547779.16     10463604.47

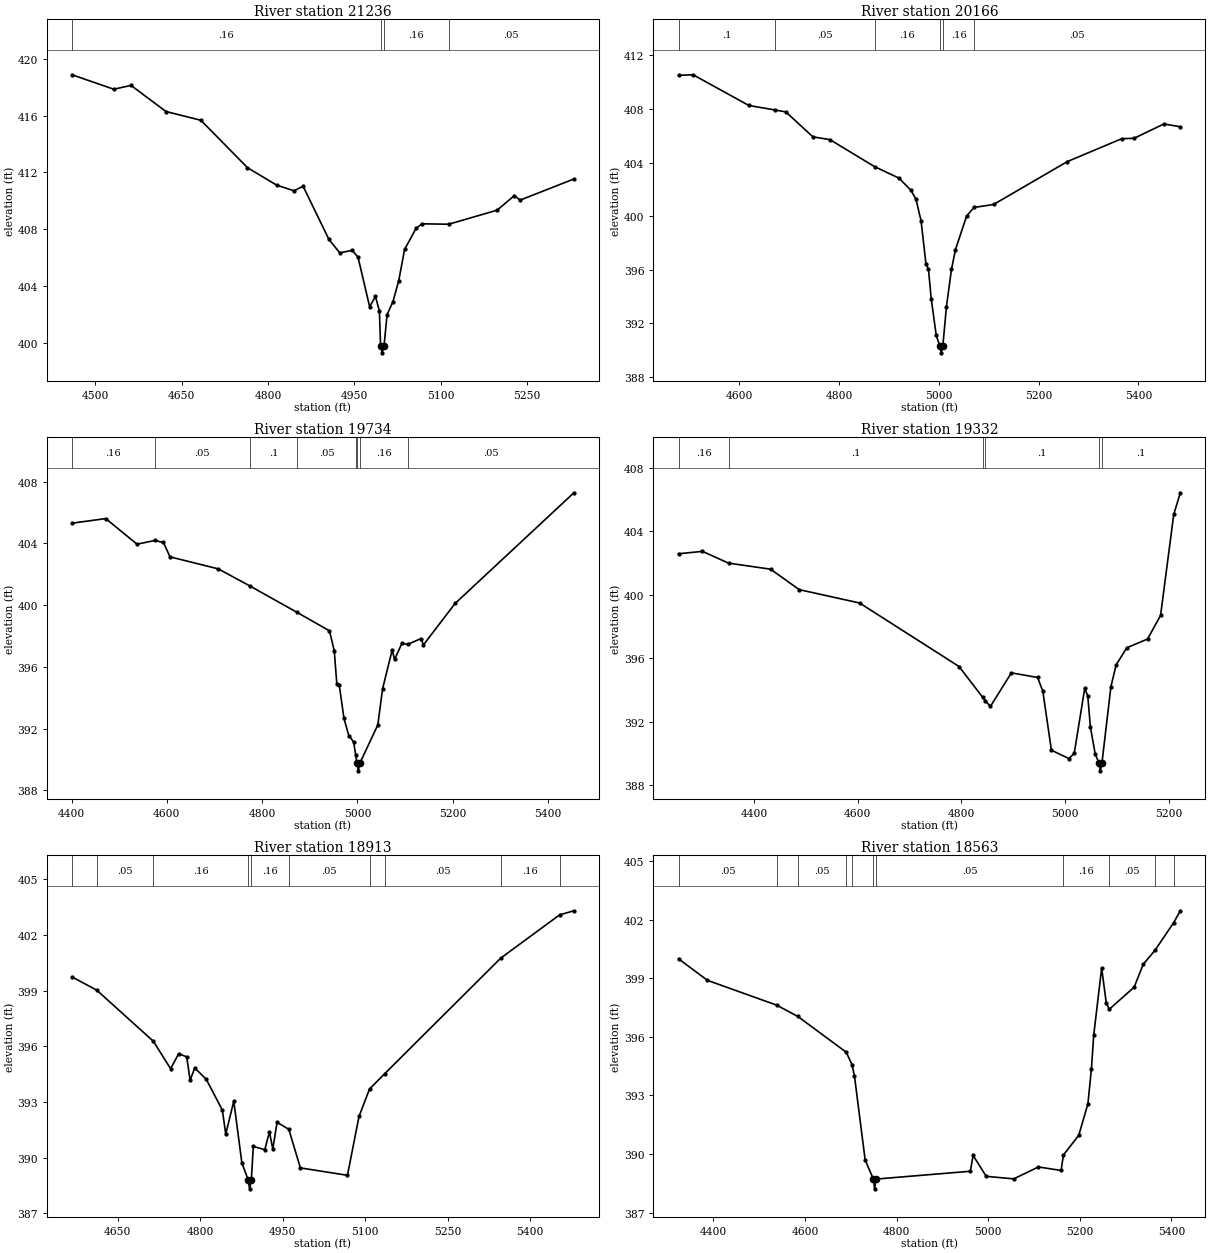
Type RM Length L Ch R = 1 ,21236   ,1070,1070,1070
BEGIN DESCRIPTION:
DOGWOOD CREEK 30.3
END DESCRIPTION:
XS GIS Cut Line= 3
      3534993.48     10466306.78      3534373.68     10466213.03
      3534128.93     10466197.41
#Sta/Elev= 30
  4459.4  418.89  4531.9  417.87  4561.9  418.14  4622.6   416.3  4683.3  415.68
  4764.2  412.34  4814.8  411.11  4845.1  410.71  4860.9  411.03  4905.8  407.28
  4924.7  406.33  4946.3  406.51  4956.4  406.02  4976.6  402.53  4986.7  403.26
  4993.5  402.24  4995.6  399.78  4998.3  399.28  5001.6  399.78  5006.9  401.98
  5017.1  402.89  5027.2  404.38  5037.3  406.57  5057.3  408.06  5067.6  408.38
    5114  408.35  5198.1  409.34  5228.1  410.37  5238.1  410.05  5331.5  411.54
#Mann= 4 ,-1 , 0
  4459.4     .16       0  4995.6     .07       0  5001.6     .16       0
    5114     .05       0
Bank Sta=4995.6,5001.6
XS Rating Curve= 0 ,0
Exp/Cntr=0.3,0.1

Type RM Length L Ch R = 1 ,20166   ,432,432,432
BEGIN DESCRIPTION:
DOGWOOD CREEK 30.2
END DESCRIPTION:
XS GIS Cut Line= 3
      3535180.99     10465603.66      3534561.18     10465494.28
      3534209.65     10465629.69
#Sta/Elev= 30
    4478  410.52  4507.3  410.56    4619  408.27  4671.9  407.93  4693.1  407.79
  4747.3  405.93  4781.5  405.72  4871.3   403.7  4919.9  402.85    4944  401.94
  4954.1  401.27  4964.3  399.66    4974  396.47  4979.1  396.05  4984.6  393.86
  4994.7  391.11  5001.9  390.31  5004.7  389.81  5007.9  390.31  5015.1  393.24
  5025.2  396.03  5033.3  397.52  5055.7  400.03  5070.6  400.66  5109.6  400.88
  5257.4  404.08  5366.6  405.79  5391.3  405.82  5451.2  406.89  5484.1  406.68
#Mann= 6 ,-1 , 0
    4478      .1       0  4671.9     .05       0  4871.3     .16       0
  5001.9     .07       0  5007.9     .16       0  5070.6     .05       0
Bank Sta=5001.9,5007.9
XS Rating Curve= 0 ,0
Exp/Cntr=0.3,0.1

Type RM Length L Ch R = 1 ,19734   ,402,402,402
BEGIN DESCRIPTION:
DOGWOOD CREEK 30.1
END DESCRIPTION:
XS GIS Cut Line= 2
      3535274.74     10465228.66      3534236.38      10465054.3
#Sta/Elev= 30
  4401.1  405.31  4471.7  405.61  4537.4  403.95  4574.7  404.19  4592.9  404.06
  4606.6  403.13    4708  402.35  4773.9  401.25  4873.4  399.53  4941.2  398.34
  4951.3  397.04  4956.6   394.9  4961.6  394.85  4971.6  392.67  4981.8  391.55
  4991.9  391.14  4996.3  390.29    4999  389.77  5001.8  389.27    5005  389.77
  5042.6  392.24  5052.7  394.59  5072.7  397.09  5077.8  396.49  5093.3  397.53
  5105.4  397.46  5133.3  397.84  5138.4  397.43  5204.8  400.11    5454  407.28
#Mann= 8 ,-1 , 0
  4401.1     .16       0  4574.7     .05       0  4773.9      .1       0
  4873.4     .05       0  4996.3     .16       0    4999     .07       0
    5005     .16       0  5105.4     .05       0
Bank Sta=4999,5005
XS Rating Curve= 0 ,0
Exp/Cntr=0.3,0.1

Type RM Length L Ch R = 1 ,19332   ,419,419,419
BEGIN DESCRIPTION:
DOGWOOD CREEK 30.0
END DESCRIPTION:
XS GIS Cut Line= 2
      3535507.81     10464880.03      3534549.52     10464741.15
#Sta/Elev= 30
    4254  402.57  4300.2  402.72  4350.5  401.98  4431.5   401.6    4487  400.31
  4603.3  399.47  4795.3  395.47  4840.9  393.53  4846.1   393.3  4855.9  392.96
  4896.3  395.07  4946.9  394.78    4957  393.91  4973.5   390.2  5007.5  389.67
  5017.6  390.01  5037.8  394.09  5043.7  393.62  5048.8  391.65    5058  389.97
  5065.1   389.4  5067.9   388.9  5071.1   389.4  5088.3  394.19  5098.4  395.57
    5119  396.65  5159.1   397.2  5184.2  398.69  5209.6  405.05  5222.3  406.41
#Mann= 6 ,-1 , 0
    4254     .16       0  4350.5      .1       0  4840.9     .16       0
  4846.1      .1       0  5065.1     .07       0  5071.1      .1       0
Bank Sta=5065.1,5071.1
XS Rating Curve= 0 ,0
Exp/Cntr=0.3,0.1

Type RM Length L Ch R = 1 ,18913   ,350,350,350
BEGIN DESCRIPTION:
DOGWOOD CREEK 29.0
END DESCRIPTION:
XS GIS Cut Line= 2
      3535372.13     10464742.47      3534637.69     10464200.76
#Sta/Elev= 30
  4566.7  399.74  4611.5  399.03  4714.6  396.27  4745.9  394.79  4760.6   395.6
  4775.2  395.43  4781.4  394.17  4789.8  394.83  4810.7  394.22    4840  392.56
  4846.2  391.26  4860.8  393.04  4875.5  389.71  4886.8  388.81  4889.6  388.31
  4892.8  388.81  4896.3   390.6  4917.2  390.42  4925.6  391.38  4931.8  390.46
  4939.5   391.9  4960.9  391.52  4981.9  389.44  5067.5  389.04  5088.6  392.22
  5107.8   393.7  5135.6  394.53  5346.5  400.76  5453.4  403.09  5479.3  403.31
#Mann= 10 ,-1 , 0
  4566.7     .16       0  4611.5     .05       0  4714.6     .16       0
  4886.8    .033       0  4892.8     .16       0  4960.9     .05       0
  5107.8     .16       0  5135.6     .05       0  5346.5     .16       0
  5453.4     .05       0
Bank Sta=4886.8,4892.8
XS Rating Curve= 0 ,0
Exp/Cntr=0.3,0.1

Type RM Length L Ch R = 1 ,18563   ,48,48,48
BEGIN DESCRIPTION:
DOGWOOD CREEK 28.01
END DESCRIPTION:
XS GIS Cut Line= 6
      3535644.46     10464536.12      3535112.77     10464160.68
      3535015.12     10464162.85      3534941.33     10464223.61
      3534813.29     10464230.12        3534693.     10464205.44
#Sta/Elev= 30
  4324.2  399.99  4387.3  398.89  4538.5  397.62  4584.7  397.04  4690.3  395.21
  4702.7  394.58  4708.2  393.99  4731.5   389.7  4749.4  388.72  4752.2  388.22
  4755.4  388.72  4961.1  389.12  4967.1  389.93  4995.8  388.86  5055.8  388.73
  5109.7  389.34  5159.2  389.16  5164.2  389.95  5197.7  390.96  5217.7  392.57
  5225.4  394.37  5230.4  396.09  5247.7  399.52  5257.7  397.74  5264.4  397.41
  5318.6  398.54  5338.6  399.72  5364.2  400.43  5404.8  401.84  5419.4  402.45
#Mann= 11 ,-1 , 0
  4324.2     .05       0  4538.5      .1       0  4584.7     .05       0
  4690.3      .1       0  4702.7     .05       0  4749.4    .033       0
  4755.4     .05       0  5164.2     .16       0  5264.4     .05       0
  5364.2     .16       0  5404.8     .05       0
Bank Sta=4749.4,4755.4
XS Rating Curve= 0 ,0
Exp/Cntr=0.3,0.1

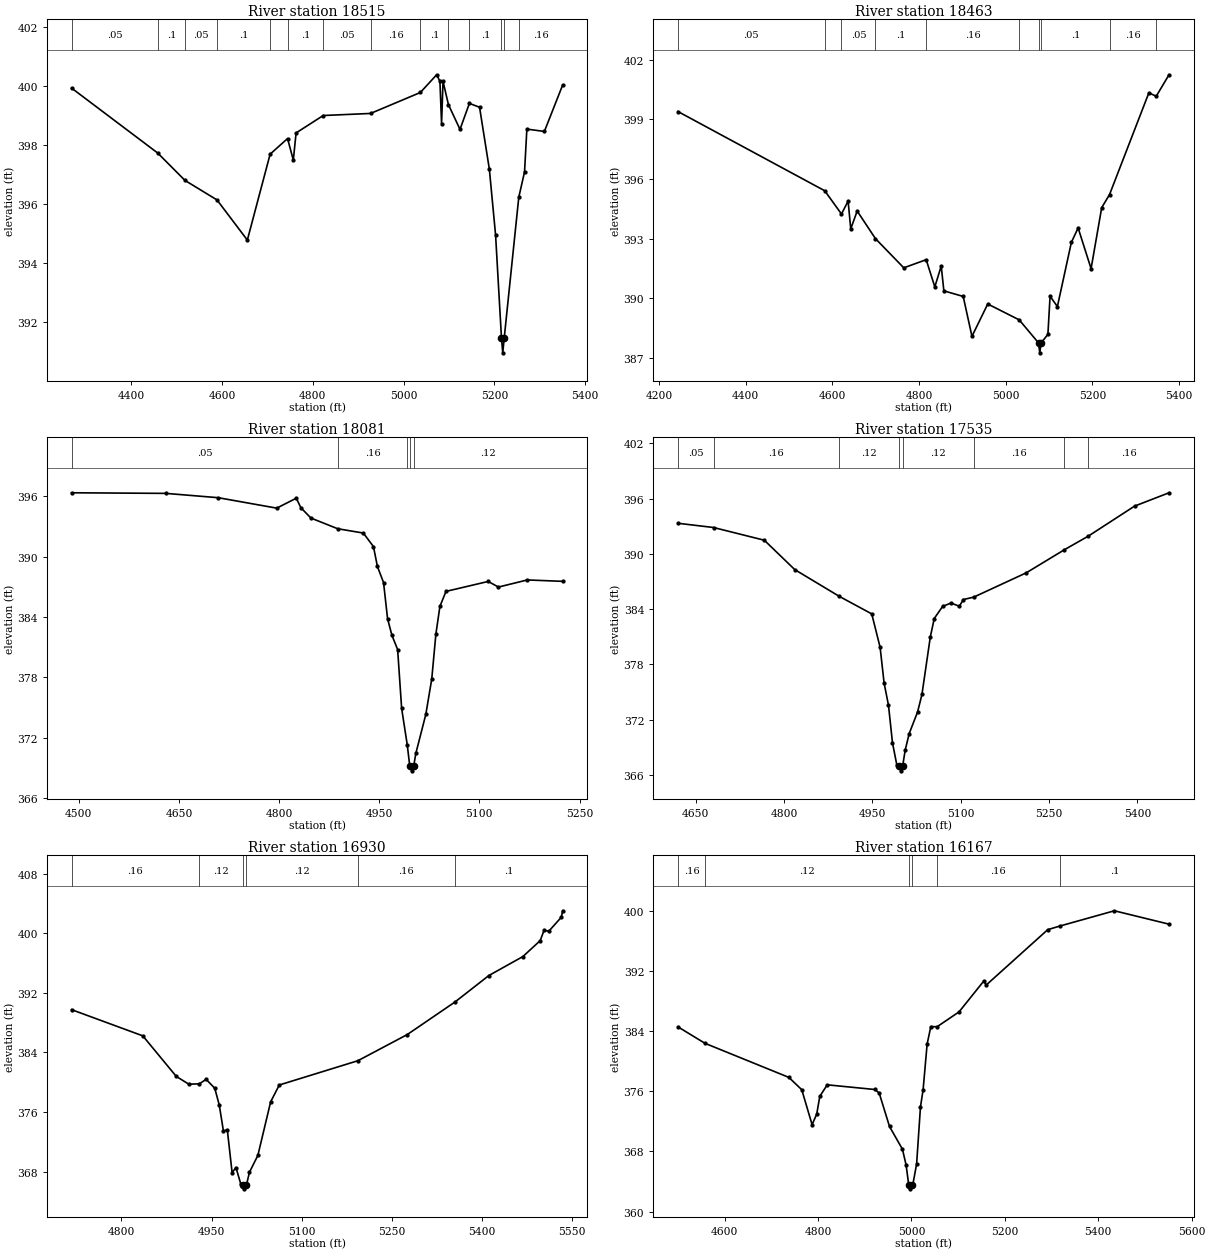
Type RM Length L Ch R = 1 ,18515   ,52,52,52
BEGIN DESCRIPTION:
DOGWOOD CREEK 28.0
END DESCRIPTION:
XS GIS Cut Line= 5
      3535698.69     10464494.87      3535156.17     10464119.44
      3534999.92     10464106.42      3534897.93     10464165.02
      3534752.51     10464191.06
#Sta/Elev= 30
  4268.4  399.93  4458.2  397.73  4518.4   396.8  4588.9  396.14  4655.7  394.78
  4705.9  397.69  4744.3  398.22    4757  397.49  4763.1  398.41  4822.9     399
  4927.2  399.07  5036.9  399.78  5072.7  400.38    5080  400.16  5083.6  398.72
  5086.8  400.16  5098.7  399.37  5124.2  398.53  5144.9  399.41  5167.3  399.28
  5188.9  397.18  5202.6  394.95  5215.6  391.46  5218.4  390.96  5221.6  391.46
  5253.7  396.23  5266.4  397.09  5271.5  398.54  5310.1  398.46  5350.3  400.03
#Mann= 14 ,-1 , 0
  4268.4     .05       0  4458.2      .1       0  4518.4     .05       0
  4588.9      .1       0  4705.9     .05       0  4744.3      .1       0
  4822.9     .05       0  4927.2     .16       0  5036.9      .1       0
  5098.7     .05       0  5144.9      .1       0  5215.6     .07       0
  5221.6      .1       0  5253.7     .16       0
Bank Sta=5215.6,5221.6
XS Rating Curve= 0 ,0
Exp/Cntr=0.3,0.1

Type RM Length L Ch R = 1 ,18463   ,382,382,382
BEGIN DESCRIPTION:
DOGWOOD CREEK 27.0
END DESCRIPTION:
XS GIS Cut Line= 4
      3535716.06     10464442.79      3535158.34     10464056.51
      3534967.37     10464067.36      3534722.12     10464162.86
#Sta/Elev= 30
    4244   399.4  4582.7  395.41  4621.3  394.24  4636.6  394.89  4642.7  393.49
  4657.5  394.39  4699.7     393    4765  391.53  4816.7  391.94  4836.6  390.57
  4851.4  391.62  4857.5  390.37  4902.1  390.09  4922.3  388.08  4958.7  389.71
  5031.3  388.91  5075.9  387.75  5078.7  387.25  5081.9  387.75  5097.5  388.18
  5102.5   390.1  5119.4  389.58  5151.6  392.81  5167.2  393.54  5197.1  391.49
  5221.6  394.56  5239.7  395.22  5330.4  400.34  5347.4  400.17  5376.9  401.25
#Mann= 10 ,-1 , 0
    4244     .05       0  4582.7      .1       0  4621.3     .05       0
  4699.7      .1       0  4816.7     .16       0  5031.3      .1       0
  5075.9     .07       0  5081.9      .1       0  5239.7     .16       0
  5347.4     .05       0
Bank Sta=5075.9,5081.9
XS Rating Curve= 0 ,0
Exp/Cntr=0.3,0.1

Type RM Length L Ch R = 1 ,18081   ,546,546,546
BEGIN DESCRIPTION:
DOGWOOD CREEK 27.01
END DESCRIPTION:
XS GIS Cut Line= 2
      3535794.17     10464134.62      3535177.89     10463733.17
#Sta/Elev= 30
  4489.2  396.37  4630.5  396.31  4708.9  395.88  4796.5  394.84  4825.8  395.83
  4832.7  394.88  4847.8  393.85  4887.8  392.79  4926.2  392.36  4941.4  391.01
  4947.3  389.03  4956.5  387.43  4962.5  383.84    4969  382.18  4977.6  380.76
  4983.6  374.89    4992  371.27  4995.7  369.18  4998.4  368.68  5001.7  369.18
  5004.9  370.43  5019.8   374.3  5028.7  377.83  5034.9  382.31  5040.9  385.05
    5050  386.55  5113.3  387.54  5128.5  386.98  5171.9  387.69  5224.7  387.55
#Mann= 5 ,-1 , 0
  4489.2     .05       0  4887.8     .16       0    4992     .12       0
  4995.7     .07       0  5001.7     .12       0
Bank Sta=4995.7,5001.7
XS Rating Curve= 0 ,0
Exp/Cntr=0.3,0.1

Type RM Length L Ch R = 1 ,17535   ,605,605,605
BEGIN DESCRIPTION:
DOGWOOD CREEK 26.0
END DESCRIPTION:
XS GIS Cut Line= 3
      3535750.81     10463804.82      3535640.12     10463563.89
      3535258.16     10463142.87
#Sta/Elev= 30
  4620.1  393.32  4680.5  392.86  4766.7  391.48  4818.4  388.29  4894.1  385.38
  4949.1  383.48  4963.3  379.85  4970.1  375.96  4977.5  373.57  4984.3  369.48
  4991.7  367.07  4995.5  366.94  4998.2  366.44  5001.5  366.94  5005.9   368.7
  5012.7  370.49  5026.9  372.83  5034.3  374.73  5048.5  380.97  5055.2  382.98
  5069.4  384.29  5083.6  384.66  5097.8  384.31  5104.6  385.04  5122.2   385.3
  5211.4  387.94  5276.2  390.45  5316.6  391.92  5395.2  395.18  5453.7  396.63
#Mann= 8 ,-1 , 0
  4620.1     .05       0  4680.5     .16       0  4894.1     .12       0
  4995.5     .07       0  5001.5     .12       0  5122.2     .16       0
  5276.2      .1       0  5316.6     .16       0
Bank Sta=4995.5,5001.5
XS Rating Curve= 0 ,0
Exp/Cntr=0.3,0.1

Type RM Length L Ch R = 1 ,16930   ,763,763,763
BEGIN DESCRIPTION:
DOGWOOD CREEK 25.0
END DESCRIPTION:
XS GIS Cut Line= 3
      3536065.47     10463279.62       3536048.1     10463158.07
      3535506.32     10462724.65
#Sta/Elev= 30
  4717.2  389.75  4835.7  386.23  4891.4  380.78  4912.2  379.74  4929.7  379.78
    4941  380.39  4955.4  379.19  4962.9  376.92  4969.8  373.43  4976.2  373.63
  4984.2  367.86  4990.6  368.54  4998.6  366.35    5002  366.18  5004.8  365.68
    5008  366.18  5013.1  367.92    5027  370.16  5048.3  377.37  5062.7  379.63
  5193.4  382.89  5275.6  386.41  5354.7  390.77  5411.1  394.33  5467.7  396.88
  5496.5  399.02  5502.9   400.4  5510.9  400.29  5531.7  402.17  5533.8  403.03
#Mann= 6 ,-1 , 0
  4717.2     .16       0  4929.7     .12       0    5002     .07       0
    5008     .12       0  5193.4     .16       0  5354.7      .1       0
Bank Sta=5002,5008
XS Rating Curve= 0 ,0
Exp/Cntr=0.3,0.1

Type RM Length L Ch R = 1 ,16167   ,633,633,633
BEGIN DESCRIPTION:
DOGWOOD CREEK 23.0
END DESCRIPTION:
XS GIS Cut Line= 4
       3536195.7     10463086.43      3536321.54     10462951.91
      3536501.66     10462604.69      3536414.93     10462136.32
#Sta/Elev= 30
  4499.8  384.57  4557.7  382.38  4737.3  377.85    4765  376.21  4787.1  371.57
    4797  372.95  4803.6  375.32  4819.5  376.86  4920.9  376.24  4930.7  375.79
  4952.9  371.32  4980.6   368.3  4988.5  366.19  4994.1  363.53  4996.9  363.03
  5000.1  363.53  5002.8  363.57    5011  366.35  5019.2  373.91  5024.9  376.22
  5033.5  382.29  5041.4   384.6  5054.8  384.58  5101.9  386.56  5154.8  390.66
  5159.9  390.12  5291.8  397.49  5317.2  397.96  5434.5     400  5551.5  398.22
#Mann= 6 ,-1 , 0
  4499.8     .16       0  4557.7     .12       0  4994.1     .07       0
  5000.1     .12       0  5054.8     .16       0  5317.2      .1       0
Bank Sta=4994.1,5000.1
XS Rating Curve= 0 ,0
Exp/Cntr=0.3,0.1

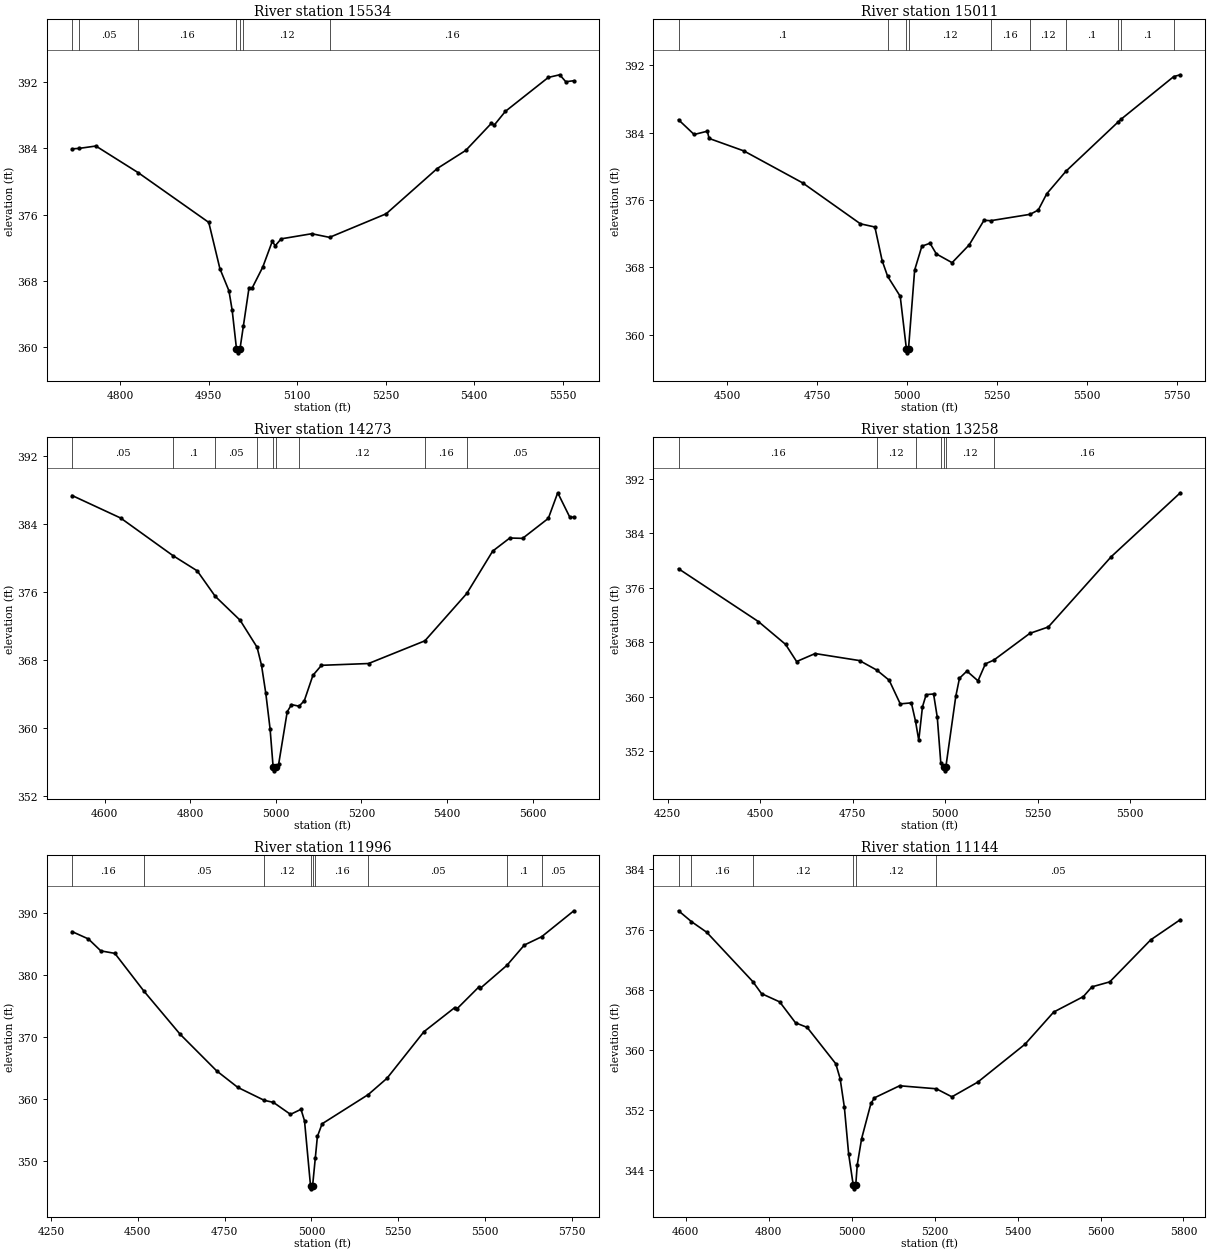
Type RM Length L Ch R = 1 ,15534   ,523,523,523
BEGIN DESCRIPTION:
DOGWOOD CREEK 22.0
END DESCRIPTION:
XS GIS Cut Line= 3
      3536805.55     10463313.07      3536920.14     10462903.33
      3536826.75     10462488.26
#Sta/Elev= 30
  4718.3  383.95  4729.8     384  4758.7  384.29  4830.6  381.06  4950.1  375.05
    4969  369.45  4984.3  366.78  4989.8  364.42  4997.1  359.77  4999.9  359.27
  5003.1  359.77  5008.9  362.57  5018.4  367.16  5023.6   367.1  5041.7  369.65
  5057.7  372.74  5062.9  372.23  5072.8  373.06  5124.7  373.68  5154.9  373.24
  5250.9  376.09  5337.5  381.57  5385.9  383.76  5429.1  387.02  5434.3  386.83
    5453  388.48  5525.9  392.59  5545.2  392.91  5555.5  392.07  5569.2  392.19
#Mann= 7 ,-1 , 0
  4718.3     .16       0  4729.8     .05       0  4830.6     .16       0
  4997.1     .07       0  5003.1     .16       0  5008.9     .12       0
  5154.9     .16       0
Bank Sta=4997.1,5003.1
XS Rating Curve= 0 ,0
Exp/Cntr=0.3,0.1

Type RM Length L Ch R = 1 ,15011   ,738,738,738
BEGIN DESCRIPTION:
DOGWOOD CREEK 21.0
END DESCRIPTION:
XS GIS Cut Line= 3
      3537229.16     10463604.76      3537303.34     10462848.09
      3537444.45     10462229.68
#Sta/Elev= 30
  4364.9  385.54  4408.2  383.79  4444.9  384.18  4449.9  383.32  4546.3  381.84
  4709.7  378.04  4870.4  373.17  4910.6  372.79  4930.7   368.8    4946  366.93
    4981  364.55  4998.1  358.33  5000.8  357.83  5004.1  358.33  5021.1  367.67
  5041.2  370.51  5063.8  370.86  5081.4  369.59  5125.2  368.55  5172.8  370.67
  5213.9  373.59  5232.2  373.54  5342.2   374.3  5364.7  374.81  5388.2  376.74
    5442  379.44  5587.4  385.31  5595.2  385.62  5741.3  390.68  5759.5  390.89
#Mann= 10 ,-1 , 0
  4364.9      .1       0    4946     .12       0  4998.1     .07       0
  5004.1     .12       0  5232.2     .16       0  5342.2     .12       0
    5442      .1       0  5587.4     .16       0  5595.2      .1       0
  5741.3     .16       0
Bank Sta=4998.1,5004.1
XS Rating Curve= 0 ,0
Exp/Cntr=0.3,0.1

Type RM Length L Ch R = 1 ,14273   ,1015,1015,1015
BEGIN DESCRIPTION:
DOGWOOD CREEK 20.0
END DESCRIPTION:
XS GIS Cut Line= 3
      3537914.94     10463578.58      3537974.84     10463279.11
      3538008.69     10462411.97
#Sta/Elev= 30
  4523.5  387.32  4637.1  384.67  4759.1  380.26  4816.1  378.46  4858.1  375.47
  4916.4  372.65  4956.1  369.47  4966.5  367.34  4976.5  364.04  4986.5  359.86
  4993.5  355.44  4996.2  354.94  4999.5  355.44  5006.5  355.72  5026.5  361.88
  5036.5  362.73  5054.2  362.54  5066.5  363.19  5086.6  366.17  5106.6  367.35
  5216.7  367.56  5348.4  370.23  5446.4   375.8  5506.9  380.78  5546.9  382.32
  5576.9  382.28    5637  384.63    5659  387.64    5687  384.79  5696.7  384.76
#Mann= 9 ,-1 , 0
  4523.5     .05       0  4759.1      .1       0  4858.1     .05       0
  4956.1     .16       0  4993.5     .07       0  4999.5     .16       0
  5054.2     .12       0  5348.4     .16       0  5446.4     .05       0
Bank Sta=4993.5,4999.5
XS Rating Curve= 0 ,0
Exp/Cntr=0.3,0.1

Type RM Length L Ch R = 1 ,13258   ,1262,1262,1262
BEGIN DESCRIPTION:
DOGWOOD CREEK 18.0
END DESCRIPTION:
XS GIS Cut Line= 3
      3538839.43     10463612.48      3538771.71      10463336.4
      3538776.91     10462265.08
#Sta/Elev= 30
  4279.6  378.77  4495.4  371.02  4568.7  367.68  4598.6  365.16  4648.6  366.33
  4768.6   365.3  4815.1  363.91  4848.6  362.42  4878.6  358.95  4908.6   359.1
  4919.8  356.41  4928.6  353.61  4938.6  358.52  4948.6  360.31  4968.6   360.4
  4978.6  356.99  4988.2  350.22  4995.6  349.63  4998.4  349.13  5001.6  349.63
  5028.6  360.06  5038.6  362.71  5058.6  363.76  5088.6  362.33  5108.6  364.82
  5131.3  365.37  5228.6  369.29  5278.6  370.23  5448.6  380.54  5635.2  389.91
#Mann= 7 ,-1 , 0
  4279.6     .16       0  4815.1     .12       0  4919.8     .16       0
  4988.2     .12       0  4995.6     .07       0  5001.6     .12       0
  5131.3     .16       0
Bank Sta=4995.6,5001.6
XS Rating Curve= 0 ,0
Exp/Cntr=0.3,0.1

Type RM Length L Ch R = 1 ,11996   ,852,852,852
BEGIN DESCRIPTION:
DOGWOOD CREEK 16.0
END DESCRIPTION:
XS GIS Cut Line= 2
      3539854.17     10463573.48       3539635.7     10462144.78
#Sta/Elev= 30
  4310.7  386.96  4357.7  385.78  4393.5  383.86  4433.9  383.46    4518  377.36
  4621.6  370.47  4727.3  364.55    4788   361.9  4864.1  359.82  4890.5  359.49
  4939.8  357.56  4970.1  358.37  4980.2  356.53  4997.5  346.08  5000.2  345.58
  5003.5  346.08  5011.2  350.48  5017.3     354  5030.8  356.04  5163.7  360.74
  5217.7  363.36  5324.2  370.86    5413  374.74  5418.1  374.47  5481.5  378.01
  5486.6  377.84  5563.3  381.54  5613.4   384.8  5663.1  386.13    5756  390.31
#Mann= 9 ,-1 , 0
  4310.7     .16       0    4518     .05       0  4864.1     .12       0
  4997.5     .07       0  5003.5     .12       0  5011.2     .16       0
  5163.7     .05       0  5563.3      .1       0  5663.1     .05       0
Bank Sta=4997.5,5003.5
XS Rating Curve= 0 ,0
Exp/Cntr=0.3,0.1

Type RM Length L Ch R = 1 ,11144   ,554,554,554
BEGIN DESCRIPTION:
DOGWOOD CREEK 14.0
END DESCRIPTION:
XS GIS Cut Line= 4
      3540391.52     10463211.36      3540537.34     10462940.57
      3540396.71     10462424.94      3540158.41      10462145.2
#Sta/Elev= 30
  4582.9  378.51    4614  377.07  4650.7  375.66  4761.9   369.1  4782.9   367.5
  4826.7   366.4  4864.9  363.62  4892.9  363.01  4961.9  358.18  4972.4   356.2
  4982.6   352.4    4993  346.15    5004  342.05  5006.7  341.55    5010  342.05
  5013.7  344.73  5024.1   348.2  5046.7  352.91  5055.2  353.65  5115.8  355.25
  5204.3  354.85  5241.8  353.78    5304  355.73    5418  360.77  5487.2  365.05
  5558.6   367.1  5579.4   368.4  5622.3  369.06  5721.1  374.65  5792.4  377.33
#Mann= 6 ,-1 , 0
  4582.9      .1       0    4614     .16       0  4761.9     .12       0
    5004     .07       0    5010     .12       0  5204.3     .05       0
Bank Sta=5004,5010
XS Rating Curve= 0 ,0
Exp/Cntr=0.3,0.1

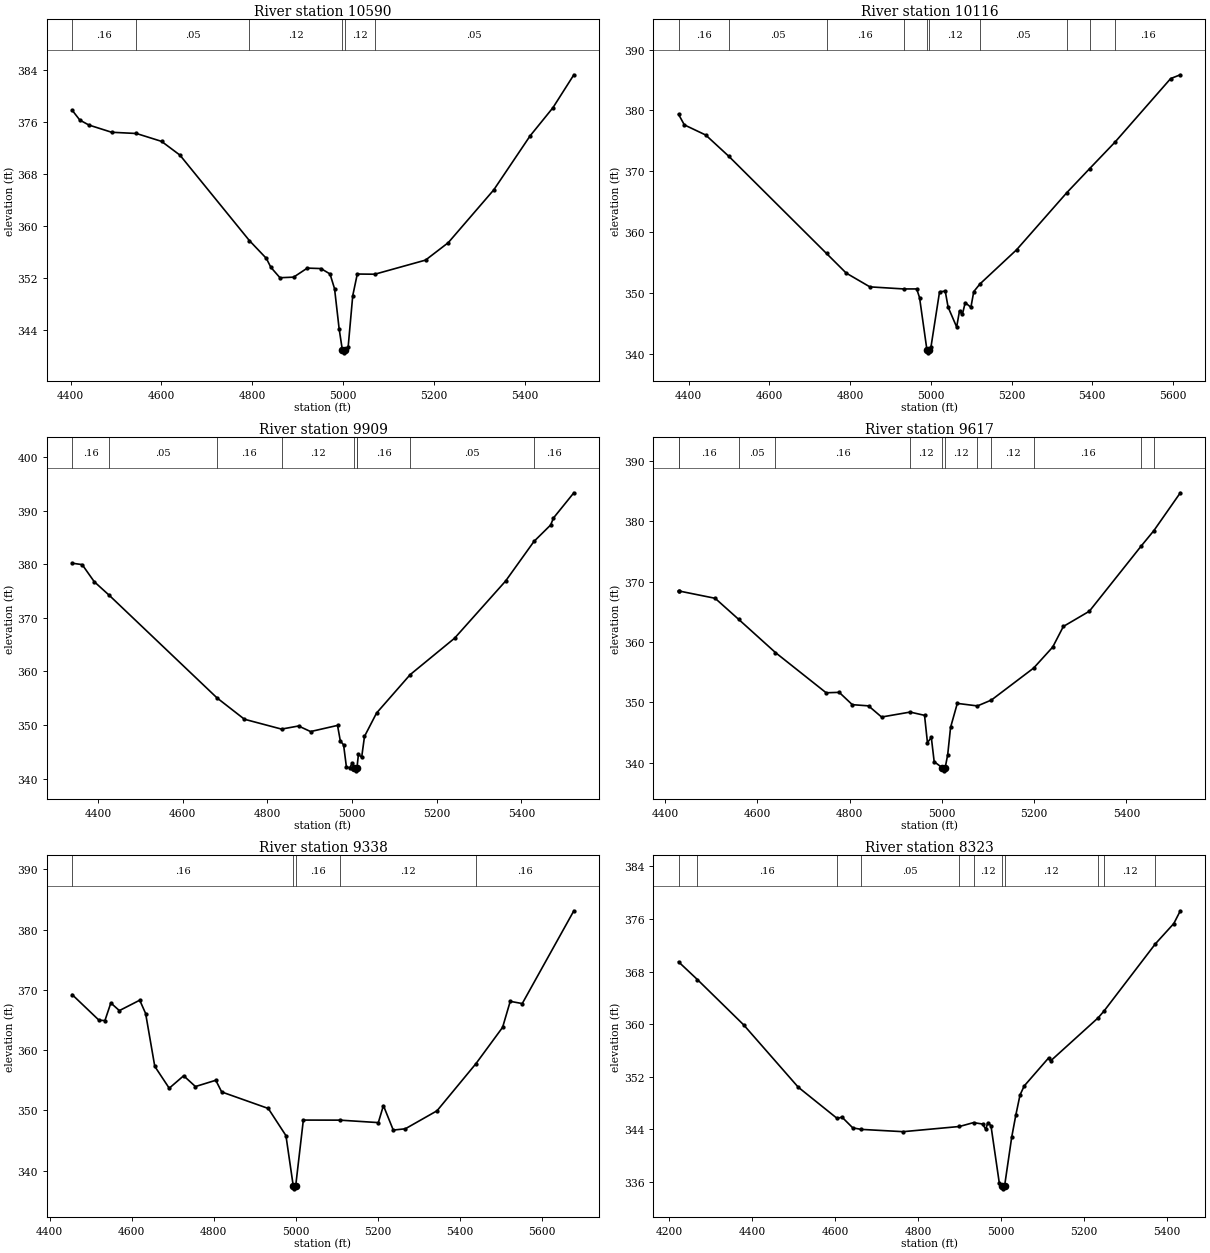
Type RM Length L Ch R = 1 ,10590   ,474,474,474
BEGIN DESCRIPTION:
DOGWOOD CREEK 13.01
END DESCRIPTION:
XS GIS Cut Line= 2
      3540990.46     10463268.73      3541026.89     10462165.54
#Sta/Elev= 30
  4403.3  377.76  4420.4  376.22  4440.4  375.46  4490.4  374.35  4544.9  374.16
  4600.1  372.95  4640.5  370.84  4793.4  357.69  4830.6  354.96  4840.6  353.58
  4860.6  351.98  4890.7  352.07  4920.7  353.46  4950.7  353.39  4970.7  352.56
  4980.7  350.29  4990.7  344.17  4997.7  340.93  5000.5  340.43  5003.7  340.93
  5010.7   341.4  5020.7  349.22  5030.7  352.55  5069.2  352.52  5180.8  354.69
  5230.8  357.37  5330.9  365.49  5410.9   373.8    5461  378.12  5507.1  383.19
#Mann= 6 ,-1 , 0
  4403.3     .16       0  4544.9     .05       0  4793.4     .12       0
  4997.7     .07       0  5003.7     .12       0  5069.2     .05       0
Bank Sta=4997.7,5003.7
XS Rating Curve= 0 ,0
Exp/Cntr=0.3,0.1

Type RM Length L Ch R = 1 ,10116   ,207,207,207
BEGIN DESCRIPTION:
DOGWOOD CREEK 13.0
END DESCRIPTION:
XS GIS Cut Line= 3
      3541060.33     10463329.98      3541325.09     10462876.42
      3541835.04     10462370.81
#Sta/Elev= 30
  4374.8  379.37  4389.2  377.63  4442.2  375.96  4499.3  372.47  4741.5  356.48
  4790.2  353.26  4848.9  350.99  4932.4  350.65  4964.9  350.65    4972  349.21
  4990.2  340.64    4993  340.14  4996.2  340.64  5000.2  341.07  5021.5  350.17
  5035.6  350.29  5042.7  347.66  5063.9  344.39    5071  347.06  5078.1  346.48
  5085.1  348.39  5099.2  347.63  5106.3  350.21  5121.5  351.46  5212.4  357.09
  5336.8  366.48  5393.6  370.45  5455.9  374.77  5594.2  385.25  5618.1  385.87
#Mann= 10 ,-1 , 0
  4374.8     .16       0  4499.3     .05       0  4741.5     .16       0
  4932.4     .12       0  4990.2     .07       0  4996.2     .12       0
  5121.5     .05       0  5336.8     .16       0  5393.6     .05       0
  5455.9     .16       0
Bank Sta=4990.2,4996.2
XS Rating Curve= 0 ,0
Exp/Cntr=0.3,0.1

Type RM Length L Ch R = 1 ,9909    ,292,292,292
BEGIN DESCRIPTION:
DOGWOOD CREEK 12.0
END DESCRIPTION:
XS GIS Cut Line= 2
      3541115.46     10463409.32      3541891.49     10462513.51
#Sta/Elev= 30
  4338.9   380.2  4362.8  379.93  4391.3  376.74  4426.5  374.22  4681.6  355.03
    4746  351.07  4833.6  349.23  4873.8  349.81  4902.3  348.77  4965.9  349.92
  4972.5  347.02  4980.2  346.29  4986.8  342.21  4994.4  341.99  5001.1   342.9
  5005.7  341.94  5008.4  341.44  5011.7  341.94  5011.9  342.08  5015.3  344.52
  5022.9  343.96  5029.6  347.87  5058.1  352.23  5137.4  359.39  5242.3  366.19
  5362.9  376.87  5429.9  384.26  5469.3  387.33  5475.9  388.63  5524.1  393.34
#Mann= 9 ,-1 , 0
  4338.9     .16       0  4426.5     .05       0  4681.6     .16       0
  4833.6     .12       0  5005.7     .07       0  5011.7     .12       0
  5011.9     .16       0  5137.4     .05       0  5429.9     .16       0
Bank Sta=5005.7,5011.7
XS Rating Curve= 0 ,0
Exp/Cntr=0.3,0.1

Type RM Length L Ch R = 1 ,9617    ,279,279,279
BEGIN DESCRIPTION:
DOGWOOD CREEK 11.0
END DESCRIPTION:
XS GIS Cut Line= 3
      3541249.17     10463570.83      3541583.33     10463251.85
      3541954.41      10462748.4
#Sta/Elev= 30
  4429.4  368.48  4430.4  368.48  4508.7  367.27  4559.4   363.8  4639.5  358.27
  4749.3  351.61  4777.6  351.68  4805.9  349.64  4841.1  349.44  4869.4  347.59
  4931.3  348.41  4962.5  347.87  4968.8  343.35  4977.2   344.2  4983.4  340.18
  5001.2  339.17    5004  338.67  5007.2  339.17  5012.7  341.35  5018.9  345.87
  5033.5  349.85  5077.1  349.43  5107.3   350.4    5199  355.71  5240.2  359.18
  5263.3   362.6  5319.7  365.13  5432.5  375.98  5459.4  378.48  5516.8  384.76
#Mann= 12 ,-1 , 0
  4429.4     .05       0  4430.4     .16       0  4559.4     .05       0
  4639.5     .16       0  4931.3     .12       0  5001.2     .07       0
  5007.2     .12       0  5077.1     .05       0  5107.3     .12       0
    5199     .16       0  5432.5     .05       0  5459.4     .16       0
Bank Sta=5001.2,5007.2
XS Rating Curve= 0 ,0
Exp/Cntr=0.3,0.1

Type RM Length L Ch R = 1 ,9338    ,1015,1015,1015
BEGIN DESCRIPTION:
DOGWOOD CREEK 10.0
END DESCRIPTION:
XS GIS Cut Line= 3
      3541377.19     10463809.55      3541813.37     10463271.39
       3542015.2     10462780.92
#Sta/Elev= 30
  4454.5  369.23  4520.2  364.96  4534.6  364.91    4549  367.83  4569.8  366.56
  4619.4  368.29  4633.8  366.08  4656.1   357.3  4691.3  353.67  4726.5  355.74
  4755.2  353.95  4804.8  354.99  4819.2  353.05  4932.7  350.31  4975.8   345.8
  4993.6  337.46  4996.4  336.96  4999.6  337.46  5018.2  348.38  5107.3  348.37
    5201  347.96  5213.4  350.79  5237.4  346.72  5266.7  346.93    5344  349.92
  5438.9  357.75  5503.9  363.78  5522.5   368.1  5551.8  367.73  5677.6  383.14
#Mann= 5 ,-1 , 0
  4454.5     .16       0  4993.6     .07       0  4999.6     .16       0
  5107.3     .12       0  5438.9     .16       0
Bank Sta=4993.6,4999.6
XS Rating Curve= 0 ,0
Exp/Cntr=0.3,0.1

Type RM Length L Ch R = 1 ,8323    ,699,699,699
BEGIN DESCRIPTION:
DOGWOOD CREEK 9.0
END DESCRIPTION:
XS GIS Cut Line= 3
      3542316.99     10463996.77      3542421.15     10463323.18
      3542386.47     10462796.01
#Sta/Elev= 30
    4222  369.48  4267.5  366.78    4379  359.89  4510.5  350.41  4604.6  345.64
  4616.1  345.85  4642.1  344.21  4662.3  343.98  4763.5  343.63  4899.4  344.42
  4933.3  345.01  4955.2  344.79  4962.7  343.98  4967.7     345  4975.3  344.55
  4995.3  335.86  5002.3  335.43  5005.1  334.93  5008.3  335.43  5025.4  342.82
  5035.4   346.2  5045.4  349.22  5055.5  350.59  5114.1  354.84  5119.1   354.4
  5233.6  360.95  5247.9  361.99  5371.9  372.23  5416.2  375.31  5431.9  377.25
#Mann= 11 ,-1 , 0
    4222     .05       0  4267.5     .16       0  4604.6      .1       0
  4662.3     .05       0  4899.4     .16       0  4933.3     .12       0
  5002.3     .07       0  5008.3     .12       0  5233.6     .16       0
  5247.9     .12       0  5371.9     .16       0
Bank Sta=5002.3,5008.3
XS Rating Curve= 0 ,0
Exp/Cntr=0.3,0.1

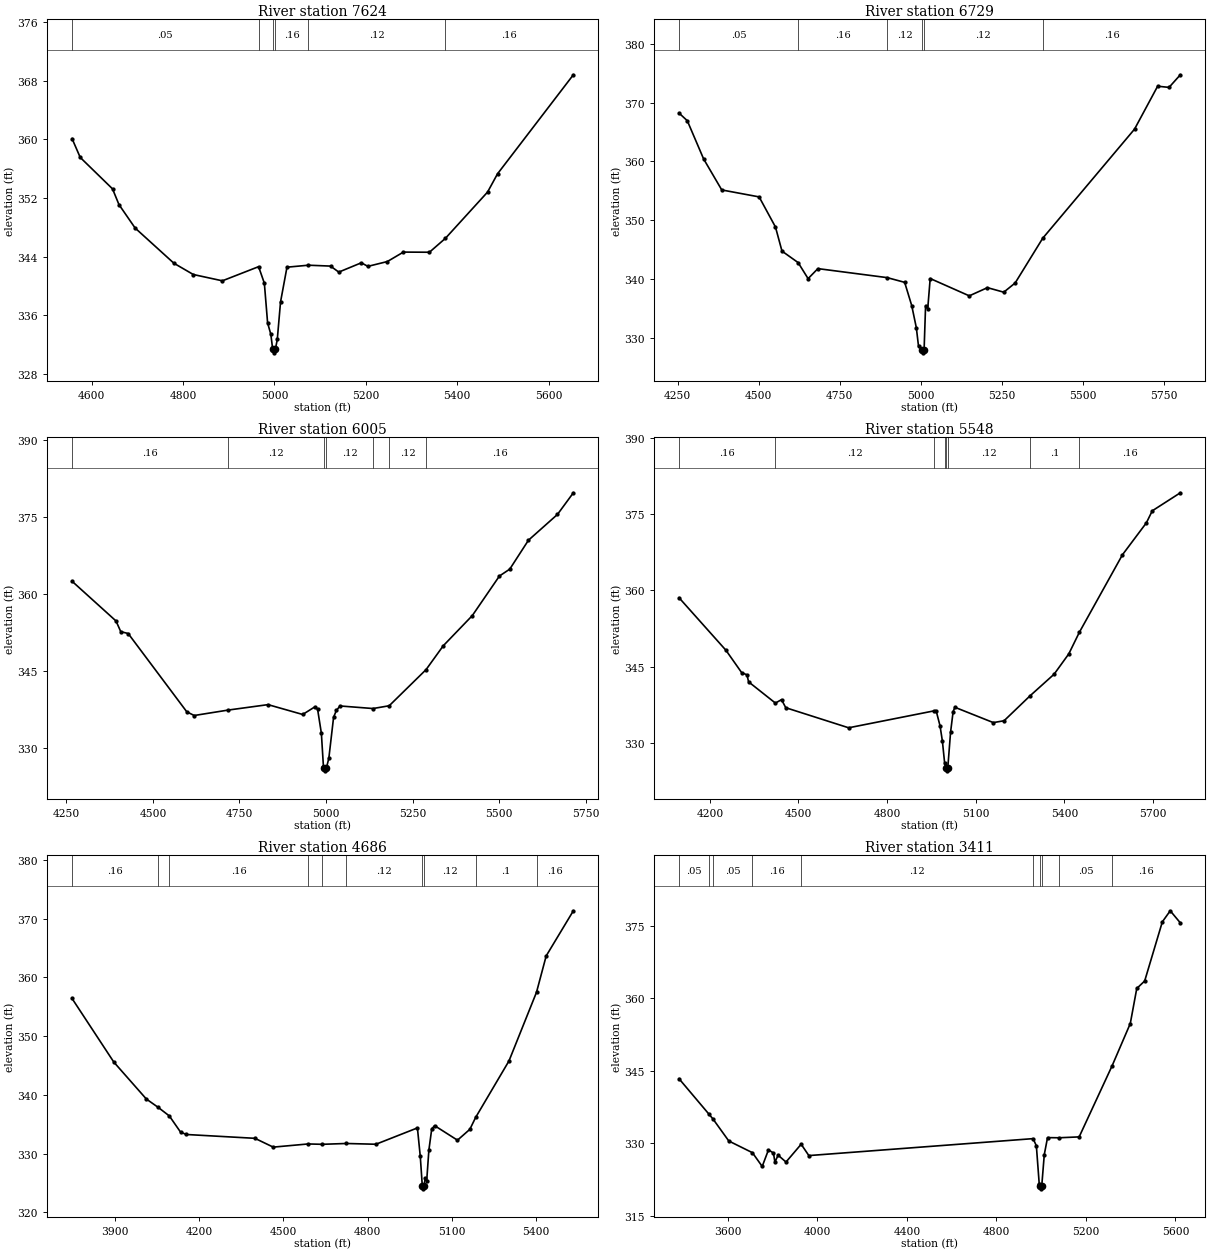
Type RM Length L Ch R = 1 ,7624    ,895,895,895
BEGIN DESCRIPTION:
DOGWOOD CREEK 8.0
END DESCRIPTION:
XS GIS Cut Line= 3
      3542585.86     10463950.67      3542985.86     10463550.67
      3543385.87     10463200.66
#Sta/Elev= 30
  4557.1  360.12    4575  357.55  4645.7  353.26  4659.8  351.11  4695.2  347.91
    4780  343.11  4822.5  341.57  4886.1  340.71  4965.4  342.64    4978  340.38
  4985.1  334.97  4992.2   333.4  4996.2  331.38    4999  330.88  5002.2  331.38
  5006.3  332.71  5013.4  337.82  5027.5  342.57  5074.4  342.84  5122.8  342.72
  5140.9   341.9  5190.3  343.17  5204.5  342.68  5247.2  343.34  5282.3  344.63
  5339.3  344.61  5374.3  346.51  5466.5  352.82  5488.3  355.31  5654.3  368.83
#Mann= 6 ,-1 , 0
  4557.1     .05       0  4965.4     .16       0  4996.2     .07       0
  5002.2     .16       0  5074.4     .12       0  5374.3     .16       0
Bank Sta=4996.2,5002.2
XS Rating Curve= 0 ,0
Exp/Cntr=0.3,0.1

Type RM Length L Ch R = 1 ,6729    ,724,724,724
BEGIN DESCRIPTION:
DOGWOOD CREEK 6.0
END DESCRIPTION:
XS GIS Cut Line= 3
      3542586.84     10464131.32      3543214.46     10464204.51
      3543900.33     10463600.94
#Sta/Elev= 30
  4254.6  368.21    4280  366.92  4330.4  360.43  4386.3  355.17  4501.5  353.99
  4551.9  348.88    4572  344.79  4621.8  342.84  4652.5  340.12  4682.7  341.82
  4896.5  340.29  4950.2  339.49    4972  335.54  4986.2  331.78  4992.9  328.65
  5004.1  328.03  5006.9  327.53  5010.1  328.03  5014.7  335.55  5021.3  335.02
  5028.9  340.14  5149.4   337.2  5205.4  338.59  5255.7  337.82  5290.8  339.38
  5375.9  346.98  5658.9  365.49  5730.1  372.77  5765.2  372.57  5800.1  374.71
#Mann= 6 ,-1 , 0
  4254.6     .05       0  4621.8     .16       0  4896.5     .12       0
  5004.1     .07       0  5010.1     .12       0  5375.9     .16       0
Bank Sta=5004.1,5010.1
XS Rating Curve= 0 ,0
Exp/Cntr=0.3,0.1

Type RM Length L Ch R = 1 ,6005    ,457,457,457
BEGIN DESCRIPTION:
DOGWOOD CREEK 5.0
END DESCRIPTION:
XS GIS Cut Line= 4
      3543566.97     10465010.71      3543853.71     10464530.04
      3543987.12     10464205.12      3544184.75     10463705.85
#Sta/Elev= 30
  4266.5  362.48  4393.5  354.73  4407.2  352.65  4428.6  352.29  4597.9  337.02
  4619.3   336.3  4717.4  337.36  4832.5  338.42  4932.6   336.5  4968.6  338.02
  4975.8  337.48  4986.6  332.84  4992.6  326.28    4995  326.01  4997.7  325.51
    5001  326.01  5008.2  327.99  5021.9  335.96  5029.9  337.28  5040.5  338.16
  5135.7  337.66  5182.5   338.2  5288.9  345.24  5338.8  349.91  5422.5  355.78
  5500.9   363.5  5530.7  364.84  5584.7  370.48  5668.5  375.51  5714.4  379.73
#Mann= 7 ,-1 , 0
  4266.5     .16       0  4717.4     .12       0    4995     .07       0
    5001     .12       0  5135.7     .16       0  5182.5     .12       0
  5288.9     .16       0
Bank Sta=4995,5001
XS Rating Curve= 0 ,0
Exp/Cntr=0.3,0.1

Type RM Length L Ch R = 1 ,5548    ,862,862,862
BEGIN DESCRIPTION:
DOGWOOD CREEK 4.0
END DESCRIPTION:
XS GIS Cut Line= 4
      3543997.53     10465350.98      3544263.99     10464621.72
      3544473.23      10464295.4      3544546.16     10463767.58
#Sta/Elev= 30
  4095.7  358.57  4254.7  348.24  4307.9  343.85  4325.7  343.44  4331.1  342.06
  4421.9  337.89  4442.6  338.57    4457  336.98  4669.9  333.04  4958.7  336.36
  4965.9   336.4  4979.1  333.44  4987.1  330.45  4994.6  326.19  4999.3  325.09
    5002  324.59  5005.3  325.09  5014.8  332.16  5023.4  336.19  5029.3  337.07
  5159.5  334.06  5195.9  334.42  5284.3  339.34  5365.3  343.56    5415  347.55
  5450.7  351.78  5596.7  367.01  5677.5  373.26  5697.6  375.63  5792.6  379.17
#Mann= 8 ,-1 , 0
  4095.7     .16       0  4421.9     .12       0  4958.7     .16       0
  4994.6     .12       0  4999.3     .07       0  5005.3     .12       0
  5284.3      .1       0  5450.7     .16       0
Bank Sta=4999.3,5005.3
XS Rating Curve= 0 ,0
Exp/Cntr=0.3,0.1

Type RM Length L Ch R = 1 ,4686    ,1275,1275,1275
BEGIN DESCRIPTION:
DOGWOOD CREEK 2.0
END DESCRIPTION:
XS GIS Cut Line= 3
      3544082.32     10465380.24      3544987.12     10464743.32
      3545119.07     10464076.64
#Sta/Elev= 30
  3747.1  356.42    3896  345.59  4011.8  339.31  4054.2  337.88  4093.7  336.43
  4133.8  333.67  4154.7  333.27  4398.6  332.62  4463.9  331.12  4588.2  331.66
  4638.8   331.6  4723.9  331.74  4829.8  331.61  4977.6  334.39  4987.8  329.53
    4995  324.52  4997.8  324.02    5001  324.52  5005.6  325.84  5010.7  325.41
  5018.4   330.6  5028.6  334.22  5038.8  334.78  5120.3   332.3  5164.4  334.15
    5185  336.17  5303.8  345.79  5401.9  357.48  5436.4  363.67  5533.2  371.35
#Mann= 10 ,-1 , 0
  3747.1     .16       0  4054.2     .12       0  4093.7     .16       0
  4588.2     .12       0  4638.8     .16       0  4723.9     .12       0
    4995     .07       0    5001     .12       0    5185      .1       0
  5401.9     .16       0
Bank Sta=4995,5001
XS Rating Curve= 0 ,0
Exp/Cntr=0.3,0.1

Type RM Length L Ch R = 1 ,3411    ,1282,1282,1282
BEGIN DESCRIPTION:
DOGWOOD CREEK 1.1
END DESCRIPTION:
XS GIS Cut Line= 4
       3545366.9     10465669.62      3545732.07     10465222.58
      3545758.92     10464400.34      3545091.26     10463889.13
#Sta/Elev= 30
  3381.3  343.36  3514.3  336.06  3533.4     335  3603.8  330.46  3709.3  328.04
  3753.1  325.19  3781.1  328.63  3803.4  327.96  3809.8  326.08  3824.2  327.52
  3859.4   326.1  3927.2  329.79  3961.5  327.44  4963.8  330.95  4978.5  329.47
  4991.3  321.56  4996.4  321.05  4999.1  320.55  5002.4  321.05  5013.9  327.64
  5028.4  331.16  5080.3  331.13  5169.8  331.31  5317.3  346.06  5398.3  354.79
  5427.3  362.06  5462.6   363.6  5541.6  375.86  5576.9  378.15  5622.1  375.64
#Mann= 10 ,-1 , 0
  3381.3     .05       0  3514.3      .1       0  3533.4     .05       0
  3709.3     .16       0  3927.2     .12       0  4963.8     .16       0
  4996.4     .07       0  5002.4     .16       0  5080.3     .05       0
  5317.3     .16       0
Bank Sta=4996.4,5002.4
XS Rating Curve= 0 ,0
Exp/Cntr=0.3,0.1