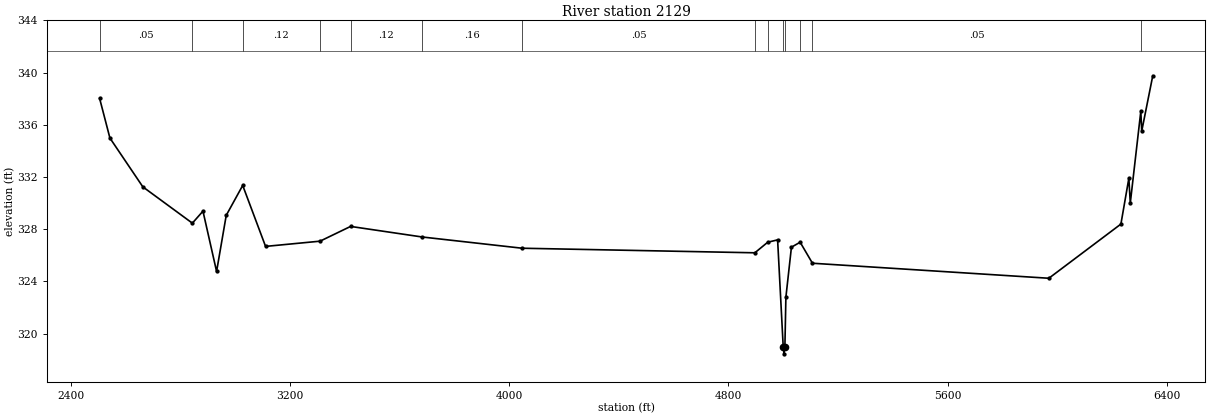
HEC-RAS study DOGWOOD CREEKEAST.prj: DOGWOOD CREEK EASTBase Level Engineering

--- DOGWOOD CREEKEAST.g01 (geometry) --- (continued)

Type RM Length L Ch R = 1 ,2129    ,0,0,0
BEGIN DESCRIPTION:
DOGWOOD CREEK 1.0
END DESCRIPTION:
XS GIS Cut Line= 5
       3545441.4     10465744.02      3545823.37     10465340.35
      3546075.11     10464059.97      3545962.26     10463148.51
      3544929.25     10462896.77
#Sta/Elev= 30
    2506  338.01  2543.5  334.98  2663.7  331.24  2844.3  328.46    2883  329.38
  2932.7  324.76  2967.9  329.06    3028  331.35  3111.4  326.68  3310.1  327.08
  3421.6  328.21  3683.1   327.4  4047.6  326.54  4896.5  326.19  4943.5     327
  4979.6  327.18  5000.1  318.95  5002.9  318.45  5006.1  318.95  5009.8  322.79
    5030  326.62  5061.8     327  5106.7  325.39  5969.2  324.24  6232.1  328.39
  6261.1   331.9  6266.3     330  6304.7  337.03    6308  335.51  6348.3  339.75
#Mann= 14 ,-1 , 0
    2506     .05       0  2844.3     .16       0    3028     .12       0
  3310.1     .16       0  3421.6     .12       0  3683.1     .16       0
  4047.6     .05       0  4896.5     .16       0  4943.5     .05       0
  5000.1     .03       0  5006.1     .05       0  5061.8     .16       0
  5106.7     .05       0  6304.7     .16       0
Bank Sta=5000.1,5006.1
XS Rating Curve= 0 ,0
Exp/Cntr=0.3,0.1

Chan Stop Cuts=-1
Use User Specified Reach Order=0
Composite Channel Slope=5