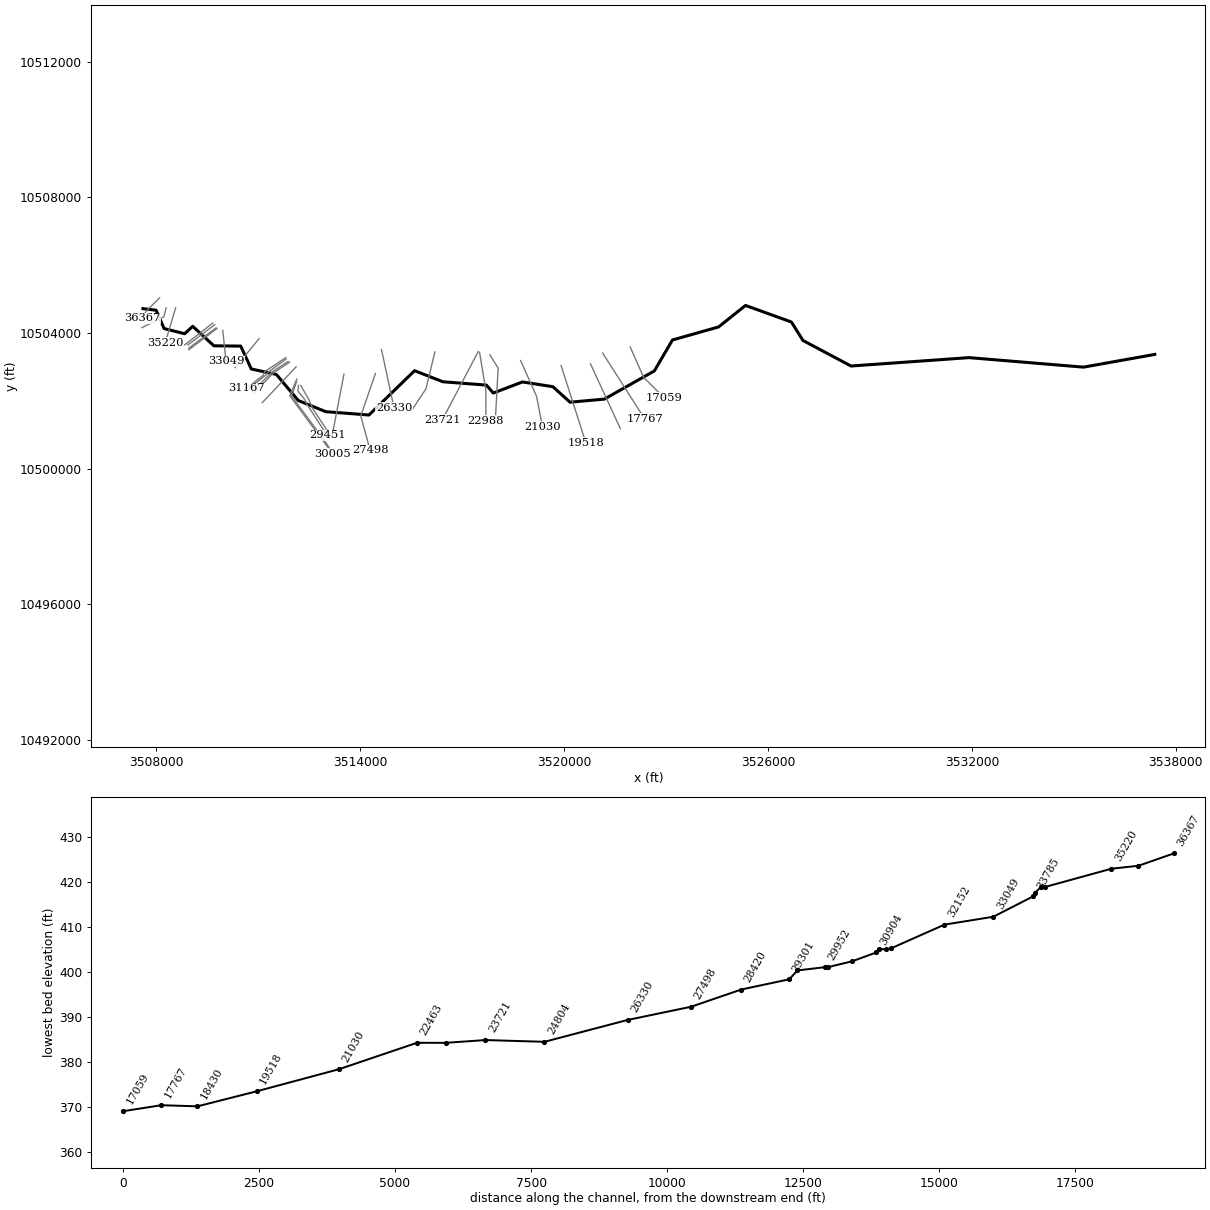
--- DOOLEY CREEK.prj (project) ---

Proj Title=DOOLEY CREEK Base Level Engineering
Current Plan=p01
Default Exp/Contr=0.3,0.1
English Units
Geom File=g01
Flow File=f01
Plan File=p01
Y Axis Title=Elevation
X Axis Title(PF)=Main Channel Distance
X Axis Title(XS)=Station
BEGIN DESCRIPTION:
DOOLEY CREEK
END DESCRIPTION:
DSS Export Rating Curves= 0
DSS Export Rating Curve Sorted= 0
DSS Export Volume Flow Curves= 0
DXF OffsetX= 0
DXF OffsetY= 0
DXF ScaleX= 1
DXF ScaleY= 10

--- DOOLEY CREEK.p01 (plan) ---

Plan Title=Multiple Run
Short Identifier=Multiple
Geom File=g01
Flow File=f01
Subcritical Flow
K Sum by GR= 0
Std Step Tol= 0.01
Critical Tol= 0.01
Num of Std Step Trials= 20
Max Error Tol= 0.3
Flow Tol Ratio= 0.001
Split Flow NTrial= 30
Split Flow Tol= 0.02
Split Flow Ratio= 0.02
Log Output Level= 0
Friction Slope Method= 1
Unsteady Friction Slope Method= 2
Unsteady Bridges Friction Slope Method= 1
Parabolic Critical Depth
Global Vel Dist=  1 , 1 , 1
Global Log Level= 0
CheckData=True
Encroach Param= -1, 0, 0, 0
BEGIN DESCRIPTION:
Multiple Run
END DESCRIPTION:

--- DOOLEY CREEK.f01 (steady flow) ---

Flow Title=Multiple
Program Version=4.10
Number of Profiles= 7
Profile Names=10-year,25-year,50-year,1pct_min,100-year,1pct_plu,500-year
River Rch & RM=DOOLEY CREEK,Reach-1         ,36367
    1687    2395    2997    2733    3696    4999    5609
River Rch & RM=DOOLEY CREEK,Reach-1         ,30005
    3990    5880    7545    7033    9512   12863   15094
River Rch & RM=DOOLEY CREEK,Reach-1         ,21030
    4301    6336    8129    7573   10242   13851   16233
River Rch & RM=DOOLEY CREEK,Reach-1         ,15309
    4375    6427    8226    7645   10339   13983   16306
River Rch & RM=DOOLEY CREEK,Reach-1         ,9238
    4574    6690    8538    7906   10692   14460   16742
Boundary for River Rch & Prof#=DOOLEY CREEK,Reach-1         , 1
Up Type= 0
Dn Type= 3
Dn Slope=0.001
Boundary for River Rch & Prof#=DOOLEY CREEK,Reach-1         , 2
Up Type= 0
Dn Type= 3
Dn Slope=0.001
Boundary for River Rch & Prof#=DOOLEY CREEK,Reach-1         , 3
Up Type= 0
Dn Type= 3
Dn Slope=0.001
Boundary for River Rch & Prof#=DOOLEY CREEK,Reach-1         , 4
Up Type= 0
Dn Type= 3
Dn Slope=0.001
Boundary for River Rch & Prof#=DOOLEY CREEK,Reach-1         , 5
Up Type= 0
Dn Type= 3
Dn Slope=0.001
Boundary for River Rch & Prof#=DOOLEY CREEK,Reach-1         , 6
Up Type= 0
Dn Type= 3
Dn Slope=0.001
Boundary for River Rch & Prof#=DOOLEY CREEK,Reach-1         , 7
Up Type= 0
Dn Type= 3
Dn Slope=0.001
DSS Import GetInterval= 0
DSS Import GetPeak= 0
DSS Import FillOption= 0

--- DOOLEY CREEK.g01 (geometry) ---

Geom Title=Existing Conditions
Program Version=4.10

River Reach=DOOLEY CREEK    ,Reach-1
Reach XY= 30
      3507602.11     10504721.64      3507988.74     10504675.03
       3508223.5     10504134.86      3508827.44     10503981.75
      3509066.29     10504200.16      3509689.11     10503625.94
      3510479.86     10503616.99       3510790.6     10502942.67
      3511527.79     10502781.61      3512174.04     10502012.15
      3512982.68     10501682.98       3514253.3     10501584.66
      3515596.41     10502891.37      3516433.01     10502564.77
      3517711.49     10502467.14      3517912.94      10502232.1
      3518771.37     10502559.85      3519666.48     10502420.13
      3520171.96     10501962.83      3521182.21     10502053.17
      3522655.28     10502885.46      3523186.94     10503797.45
      3524544.23     10504181.82       3525338.5     10504815.67
       3526688.5     10504327.65      3527029.12     10503782.86
      3528443.67     10503029.56      3531915.03     10503276.96
      3535286.12     10502996.58      3537384.62      10503371.7

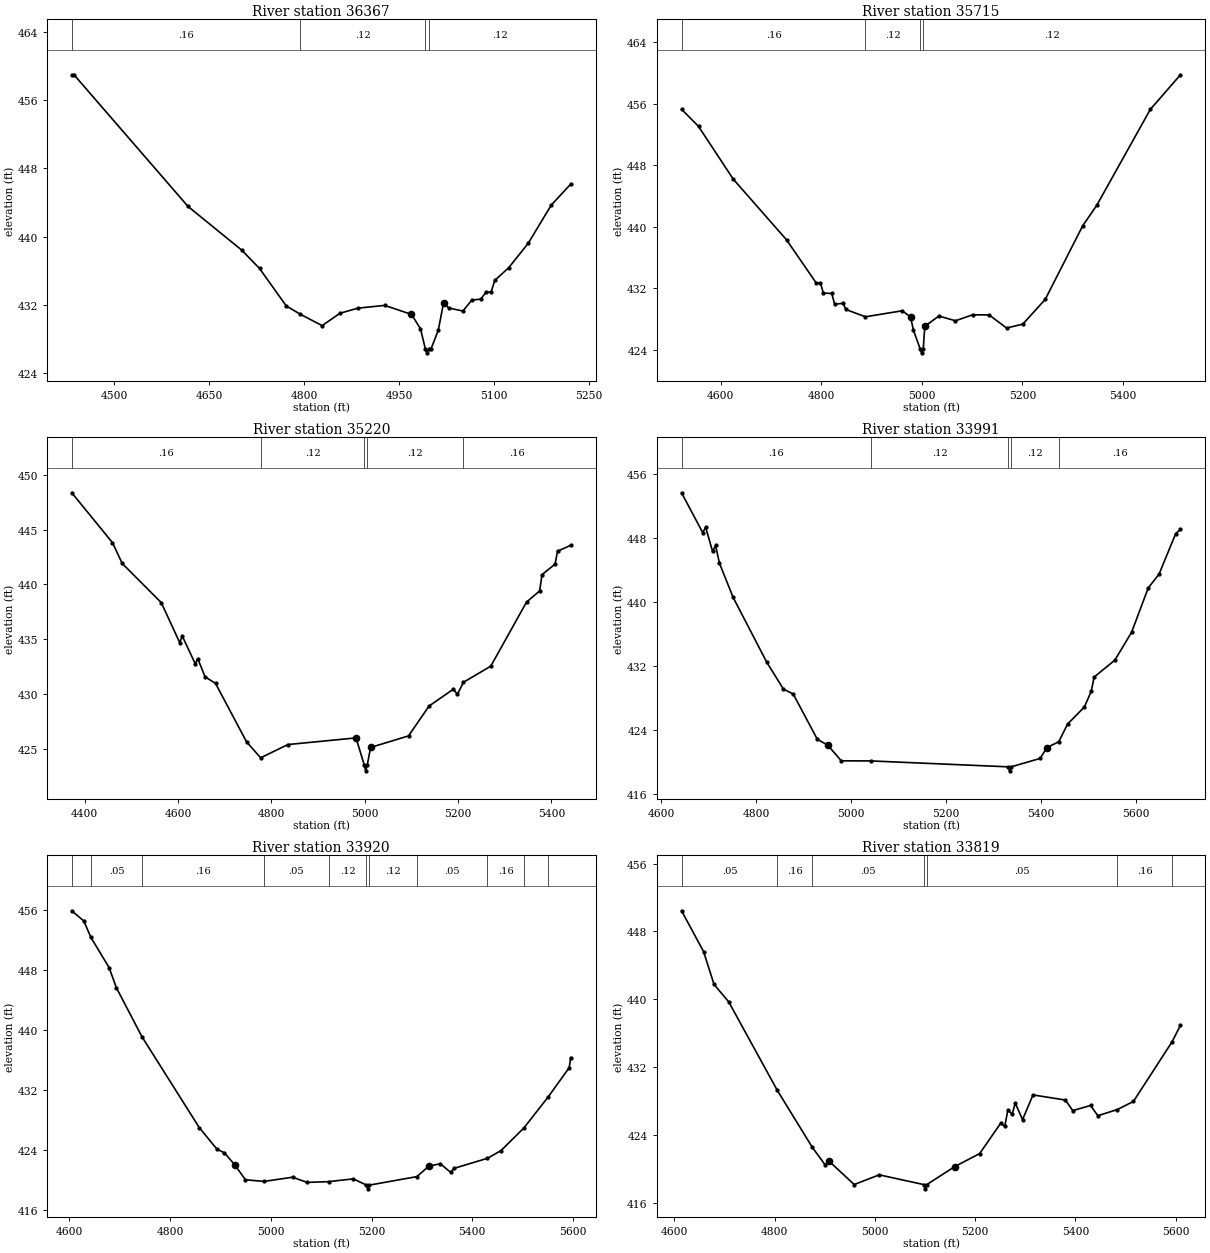
Type RM Length L Ch R = 1 ,36367   ,652,652,652
BEGIN DESCRIPTION:
DOOLEY CREEK 59.0
END DESCRIPTION:
XS GIS Cut Line= 3
      3508092.11     10505041.65      3507692.11     10504641.64
      3507592.11     10504441.64
#Sta/Elev= 30
  4432.5  458.97    4436  458.97  4616.4  443.53  4701.2  438.42  4729.5  436.26
  4771.9  431.86  4794.2  430.89  4828.5  429.56  4856.8  431.01  4885.1  431.61
  4927.5  431.93  4969.9  430.88  4984.1   429.2  4991.7  426.87  4994.4  426.37
  4997.7  426.87    5001  426.87  5012.2     429  5020.6  432.21  5028.9  431.63
  5051.3  431.27  5065.3  432.56  5079.3  432.66  5087.6  433.46    5096  433.51
  5101.6  434.86    5124  436.37  5154.7  439.23  5191.1   443.7  5221.8  446.15
#Mann= 4 ,-1 , 0
  4432.5     .16       0  4794.2     .12       0  4991.7     .07       0
  4997.7     .12       0
Bank Sta=4969.9,5020.6
XS Rating Curve= 0 ,0
Exp/Cntr=0.3,0.1

Type RM Length L Ch R = 1 ,35715   ,495,495,495
BEGIN DESCRIPTION:
DOOLEY CREEK 58.0
END DESCRIPTION:
XS GIS Cut Line= 3
      3508282.25     10504744.34      3508217.14      10504481.3
      3507571.29     10504160.98
#Sta/Elev= 30
  4522.4   455.3  4556.1  453.08    4625  446.23  4731.2  438.31  4790.6  432.66
  4798.6  432.73  4804.2   431.4  4821.1  431.34  4826.6  429.96  4843.5  430.05
  4849.1  429.26  4887.9  428.31  4961.1  429.09  4977.6  428.29  4983.5  426.55
  4996.9  424.12  4999.7  423.62  5002.9  424.12    5006  427.07    5034  428.41
  5066.9  427.79  5101.2  428.57  5133.9  428.55  5168.5  426.85  5200.8  427.35
  5245.5  430.58  5319.8  440.13  5347.8   442.8  5454.3  455.28  5514.3  459.79
#Mann= 4 ,-1 , 0
  4522.4     .16       0  4887.9     .12       0  4996.9     .07       0
  5002.9     .12       0
Bank Sta=4977.6,5006
XS Rating Curve= 0 ,0
Exp/Cntr=0.3,0.1

Type RM Length L Ch R = 1 ,35220   ,1229,1229,1229
BEGIN DESCRIPTION:
DOOLEY CREEK 56.0
END DESCRIPTION:
XS GIS Cut Line= 2
       3508564.2     10504745.24      3508258.62     10503720.85
#Sta/Elev= 30
  4372.5  448.37  4459.7  443.81  4480.6  441.91  4564.1  438.34  4603.9  434.67
  4609.1  435.29  4637.1  432.74  4642.3  433.23    4658  431.56  4680.6  430.95
  4746.9  425.62  4777.1  424.16  4835.4  425.37  4981.5  425.98  4999.4  423.47
  5002.1  422.97  5005.4  423.47  5012.8  425.11    5094  426.16    5138  428.89
  5190.2  430.43  5198.7  429.95  5211.6  431.06  5270.2  432.53  5346.9  438.39
  5374.8   439.4  5380.1  440.89    5408  441.86  5413.2  443.03  5441.5  443.57
#Mann= 5 ,-1 , 0
  4372.5     .16       0  4777.1     .12       0  4999.4     .07       0
  5005.4     .12       0  5211.6     .16       0
Bank Sta=4981.5,5012.8
XS Rating Curve= 0 ,0
Exp/Cntr=0.3,0.1

Type RM Length L Ch R = 1 ,33991   ,71,71,71
BEGIN DESCRIPTION:
DOOLEY CREEK 55.01
END DESCRIPTION:
XS GIS Cut Line= 2
      3509657.97      10504297.3      3508828.08     10503651.44
#Sta/Elev= 30
    4643  453.64  4687.5  448.67  4693.9  449.31  4708.3  446.32  4714.7  447.05
  4722.8  444.84  4751.8  440.55  4822.3  432.49  4857.6  429.11  4878.5  428.47
  4929.2  422.82  4950.8  422.11  4979.8  420.13  5041.8  420.12  5331.7  419.38
  5334.4  418.88  5337.7  419.38  5398.7  420.43  5413.2  421.79  5438.1  422.52
  5456.6  424.72  5491.9  426.85  5506.4   428.8  5512.7  430.61  5556.2  432.71
  5591.5  436.19  5626.7  441.75  5649.4  443.46  5684.6  448.54  5694.6  449.06
#Mann= 5 ,-1 , 0
    4643     .16       0  5041.8     .12       0  5331.7     .07       0
  5337.7     .12       0  5438.1     .16       0
Bank Sta=4950.8,5413.2
XS Rating Curve= 0 ,0
Exp/Cntr=0.3,0.1

Type RM Length L Ch R = 1 ,33920   ,101,101,101
BEGIN DESCRIPTION:
DOOLEY CREEK 55.0
END DESCRIPTION:
XS GIS Cut Line= 2
      3509717.37      10504250.3       3508926.4      10503653.6
#Sta/Elev= 30
  4604.7  455.93  4628.7  454.56  4642.6  452.38  4678.7  448.36  4693.3  445.66
    4744  439.13  4857.7  427.02  4893.1  424.12  4907.7  423.65  4928.5  422.03
  4949.5  420.05  4986.5  419.83    5043  420.39  5072.1   419.7  5114.6   419.8
  5163.7  420.17  5189.9  419.34  5192.6  418.84  5195.9  419.34    5290  420.47
  5313.6  421.86  5336.5  422.19  5357.3  421.02  5363.6  421.57  5430.1  422.91
  5457.2  423.95  5502.4  426.95  5550.3  431.06  5592.5     435  5595.5  436.35
#Mann= 11 ,-1 , 0
  4604.7     .16       0  4642.6     .05       0    4744     .16       0
  4986.5     .05       0  5114.6     .12       0  5189.9     .04       0
  5195.9     .12       0    5290     .05       0  5430.1     .16       0
  5502.4     .05       0  5550.3     .16       0
Bank Sta=4928.5,5313.6
XS Rating Curve= 0 ,0
Exp/Cntr=0.3,0.1

Type RM Length L Ch R = 1 ,33819   ,34,34,34
BEGIN DESCRIPTION:
DOOLEY CREEK 54.0
END DESCRIPTION:
XS GIS Cut Line= 2
      3509752.14     10504153.11      3508953.49     10503559.33
#Sta/Elev= 30
  4614.2  450.44  4658.2  445.62    4679  441.76  4708.3   439.7    4805  429.29
  4874.7  422.58  4900.8  420.47  4908.5  420.91  4958.6  418.17  5008.6  419.31
  5097.4  418.16  5100.1  417.66  5103.4  418.16  5158.8  420.27  5208.9  421.82
  5250.6  425.38    5259  425.04  5265.2  426.99  5273.6  426.44  5279.8  427.77
  5294.4  425.82  5315.2  428.73  5379.9  428.13  5394.5  426.88    5430  427.49
  5444.6  426.28  5483.5  427.01  5515.5  427.96  5592.7     435  5609.4  436.95
#Mann= 7 ,-1 , 0
  4614.2     .05       0    4805     .16       0  4874.7     .05       0
  5097.4     .04       0  5103.4     .05       0  5483.5     .16       0
  5592.7     .05       0
Bank Sta=4908.5,5158.8
XS Rating Curve= 0 ,0
Exp/Cntr=0.3,0.1

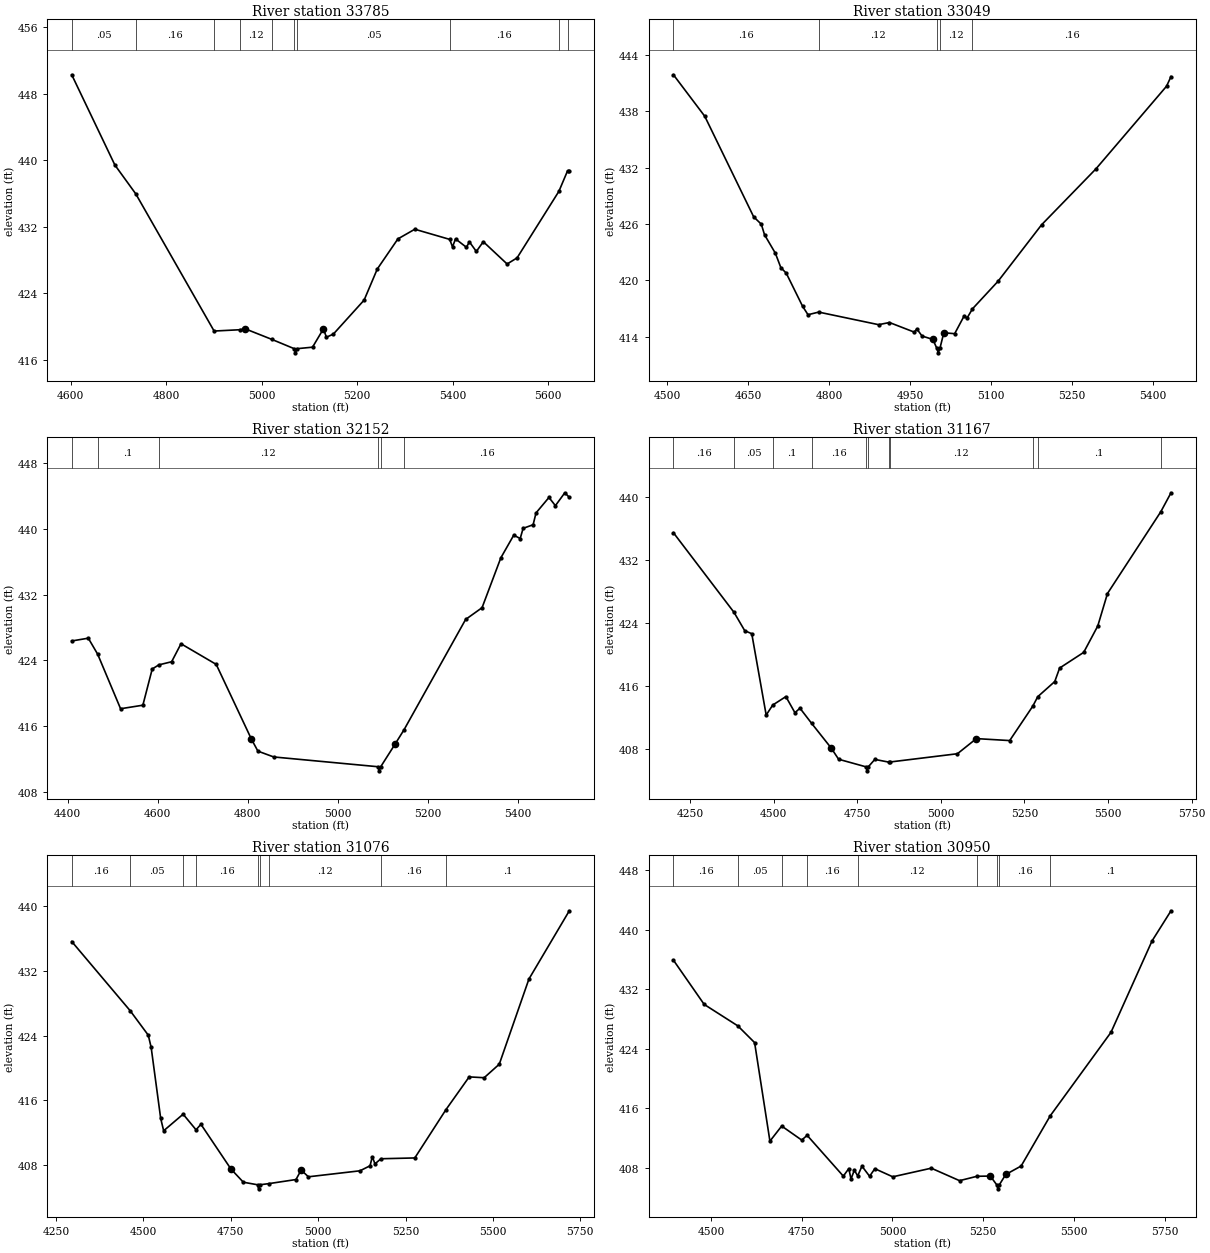
Type RM Length L Ch R = 1 ,33785   ,736,736,736
BEGIN DESCRIPTION:
DOOLEY CREEK 54.01
END DESCRIPTION:
XS GIS Cut Line= 2
      3509782.48     10504138.75      3508951.35     10503509.44
#Sta/Elev= 30
    4602  450.27  4692.4  439.42  4736.2  435.95  4900.3  419.46  4954.9  419.62
  4964.9  419.74  5020.7  418.47  5068.1  417.34  5070.8  416.84  5074.1  417.34
  5106.5  417.52  5129.3  419.72  5135.6  418.72  5150.1  419.09  5214.6  423.18
  5242.2  426.92  5285.4  430.54  5320.8   431.7  5393.9  430.48  5399.8  429.58
  5406.1  430.54  5428.9  429.53  5435.2  430.18  5449.7  429.03  5464.3   430.2
  5514.2  427.52  5535.1  428.26  5622.7  436.26  5640.9  438.73  5644.5  438.73
#Mann= 10 ,-1 , 0
    4602     .05       0  4736.2     .16       0  4900.3     .05       0
  4954.9     .12       0  5020.7     .05       0  5068.1     .07       0
  5074.1     .05       0  5393.9     .16       0  5622.7     .05       0
  5640.9     .16       0
Bank Sta=4964.9,5129.3
XS Rating Curve= 0 ,0
Exp/Cntr=0.3,0.1

Type RM Length L Ch R = 1 ,33049   ,897,897,897
BEGIN DESCRIPTION:
DOOLEY CREEK 52.0
END DESCRIPTION:
XS GIS Cut Line= 2
      3509950.04     10504079.31      3510047.19     10503163.35
#Sta/Elev= 30
  4511.7  441.91  4569.7  437.49  4660.2  426.78  4674.4  425.99  4680.3  424.87
  4700.4   422.9  4710.5  421.37  4720.5  420.78  4750.7  417.26  4760.8  416.35
  4780.6  416.63  4891.5  415.29  4911.6  415.52  4957.4   414.5  4962.4  414.83
  4971.9  414.08    4992  413.72  4999.1  412.79  5001.9  412.29  5005.1  412.79
  5012.2  414.43  5032.3  414.33  5050.1  416.25  5055.1  415.98  5065.3  416.98
  5112.7  419.92  5193.2  425.93  5293.7  431.88  5424.5  440.69  5432.8  441.72
#Mann= 5 ,-1 , 0
  4511.7     .16       0  4780.6     .12       0  4999.1     .07       0
  5005.1     .12       0  5065.3     .16       0
Bank Sta=4992,5012.2
XS Rating Curve= 0 ,0
Exp/Cntr=0.3,0.1

Type RM Length L Ch R = 1 ,32152   ,985,985,985
BEGIN DESCRIPTION:
DOOLEY CREEK 50.0
END DESCRIPTION:
XS GIS Cut Line= 2
      3511019.46     10503836.22      3510318.09     10502982.09
#Sta/Elev= 30
    4409  426.35  4445.8  426.69  4466.6  424.74  4517.5   418.1    4567  418.53
  4587.8  422.94  4602.5  423.44  4630.9  423.82  4651.7  426.01  4729.9   423.5
  4808.1   414.4  4822.5  412.94  4857.6  412.23  5089.3  411.04    5092  410.54
  5095.3  411.04  5127.4  413.81  5147.1  415.54  5283.9  428.97  5320.4   430.4
  5362.1  436.47  5390.8  439.23  5405.1  438.82  5411.6  440.06  5433.8   440.5
  5440.3  441.94    5469  443.82  5483.3  442.82  5504.2  444.39  5514.2  443.84
#Mann= 6 ,-1 , 0
    4409     .05       0  4466.6      .1       0  4602.5     .12       0
  5089.3     .07       0  5095.3     .12       0  5147.1     .16       0
Bank Sta=4808.1,5127.4
XS Rating Curve= 0 ,0
Exp/Cntr=0.3,0.1

Type RM Length L Ch R = 1 ,31167   ,91,91,91
BEGIN DESCRIPTION:
DOOLEY CREEK 49.01
END DESCRIPTION:
XS GIS Cut Line= 4
       3511802.5     10503276.38      3511182.68     10502861.43
      3511146.22       10502759.      3510645.77     10502371.11
#Sta/Elev= 30
  4200.5  435.46  4381.6  425.36  4413.7  423.03  4434.7  422.65  4477.8  412.33
  4497.5   413.6  4536.7  414.67  4563.8  412.62  4578.8   413.2  4613.4  411.29
  4671.9  408.16  4694.4  406.72  4776.9  405.75  4779.7  405.25  4782.9  405.75
  4802.7   406.7  4845.2  406.35  4847.8  406.37  5049.7  407.42  5106.3  409.34
  5205.9  409.09  5274.9  413.45  5289.9  414.66  5340.7  416.58  5355.2  418.29
  5427.2  420.28  5469.3  423.63  5498.3  427.75  5657.7  438.12  5688.3  440.53
#Mann= 11 ,-1 , 0
  4200.5     .16       0  4381.6     .05       0  4497.5      .1       0
  4613.4     .16       0  4776.9     .07       0  4782.9     .16       0
  4845.2      .1       0  4847.8     .12       0  5274.9     .16       0
  5289.9      .1       0  5657.7     .16       0
Bank Sta=4671.9,5106.3
XS Rating Curve= 0 ,0
Exp/Cntr=0.3,0.1

Type RM Length L Ch R = 1 ,31076   ,126,126,126
BEGIN DESCRIPTION:
DOOLEY CREEK 49.0
END DESCRIPTION:
XS GIS Cut Line= 4
      3511815.68     10503234.34      3511262.28     10502830.68
      3511246.66     10502785.11      3510708.92     10502352.83
#Sta/Elev= 30
  4295.3  435.63  4462.3  427.08  4514.2  424.05  4522.5  422.53  4549.7  413.76
  4558.2  412.23  4613.9  414.28  4650.8  412.35  4664.8  413.03  4750.5  407.51
  4786.1  405.87  4827.1  405.55  4829.8  405.05  4833.1  405.55  4859.9   405.7
  4936.7   406.2  4951.4  407.37  4972.2  406.54  5119.7  407.28  5148.5   407.9
  5154.9  409.02  5162.6  408.14  5179.7  408.77  5276.5  408.87  5365.7  414.85
    5432  418.89  5474.9  418.79  5518.1  420.46  5602.9  430.99  5718.4  439.43
#Mann= 9 ,-1 , 0
  4295.3     .16       0  4462.3     .05       0  4613.9      .1       0
  4650.8     .16       0  4827.1     .07       0  4833.1     .16       0
  4859.9     .12       0  5179.7     .16       0  5365.7      .1       0
Bank Sta=4750.5,4951.4
XS Rating Curve= 0 ,0
Exp/Cntr=0.3,0.1

Type RM Length L Ch R = 1 ,30950   ,46,46,46
BEGIN DESCRIPTION:
DOOLEY CREEK 47.0
END DESCRIPTION:
XS GIS Cut Line= 3
      3511870.32     10503161.39      3511414.63     10502864.54
      3510828.66     10502281.17
#Sta/Elev= 30
  4396.7  435.91  4481.4  429.96  4574.1  427.07  4620.3  424.82  4662.5  411.56
  4694.9  413.59  4750.1   411.7    4765  412.34  4864.7  406.85  4879.8  407.87
  4885.8  406.46    4895  407.65  4904.3  406.88    4916  408.19  4937.1  406.83
  4951.5  407.85  5000.9  406.76    5107  407.92  5184.8  406.24    5233  406.83
  5269.6  406.86  5287.9  405.64  5290.6  405.14  5293.9  405.64  5312.1  407.07
  5354.5  408.21  5434.7  414.97    5602   426.2  5715.1   438.5  5767.4  442.56
#Mann= 9 ,-1 , 0
  4396.7     .16       0  4574.1     .05       0  4694.9      .1       0
    4765     .16       0  4904.3     .12       0    5233     .16       0
  5287.9     .07       0  5293.9     .16       0  5434.7      .1       0
Bank Sta=5269.6,5312.1
XS Rating Curve= 0 ,0
Exp/Cntr=0.3,0.1

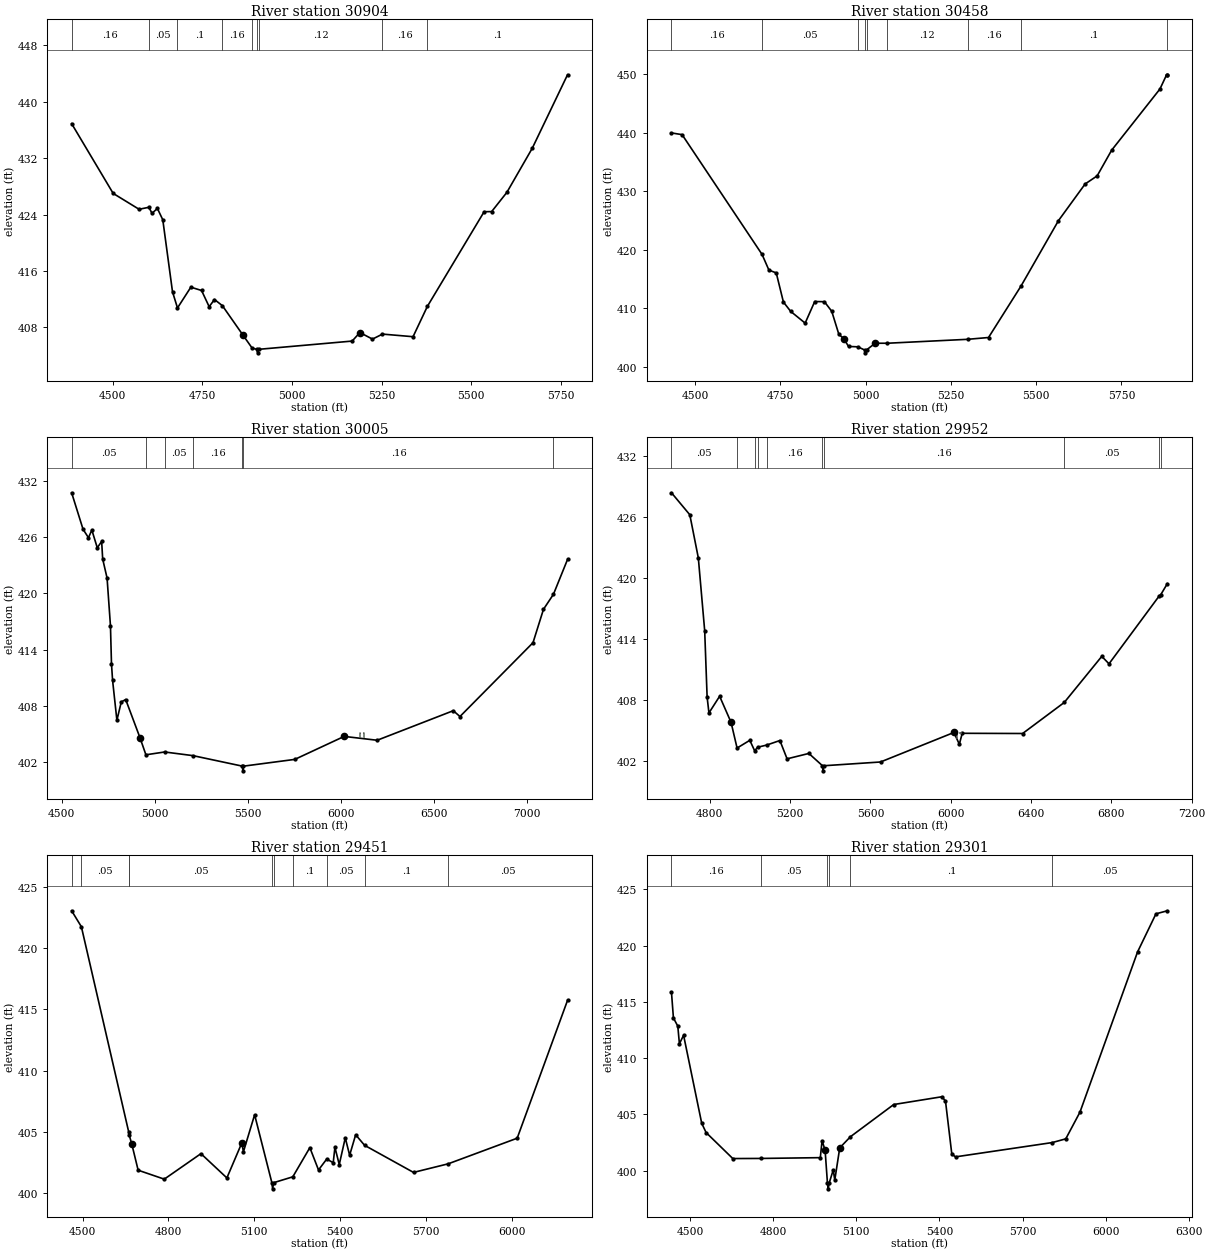
Type RM Length L Ch R = 1 ,30904   ,446,446,446
BEGIN DESCRIPTION:
DOOLEY CREEK 47.01
END DESCRIPTION:
XS GIS Cut Line= 3
      3511914.48     10503140.09      3511437.89     10502824.97
      3510879.34     10502235.25
#Sta/Elev= 30
  4385.4   436.9  4501.3     427  4573.5  424.75  4600.9  425.03  4609.6  424.18
  4624.7  424.86  4639.7  423.26  4666.8  413.04  4680.7  410.74    4718  413.69
  4747.9  413.22  4769.1  410.92  4783.9  411.94  4805.9  411.07  4862.4  406.96
  4888.9  405.05  4901.5  404.87  4904.3  404.37  4907.5  404.87  5168.1  406.04
  5189.6  407.25  5224.8  406.32  5252.7  407.03    5338  406.66  5377.9  410.96
  5536.3   424.4  5557.3  424.42  5599.8  427.15  5670.6  433.41    5769  443.84
#Mann= 9 ,-1 , 0
  4385.4     .16       0  4600.9     .05       0  4680.7      .1       0
  4805.9     .16       0  4888.9     .12       0  4901.5     .07       0
  4907.5     .12       0  5252.7     .16       0  5377.9      .1       0
Bank Sta=4862.4,5189.6
XS Rating Curve= 0 ,0
Exp/Cntr=0.3,0.1

Type RM Length L Ch R = 1 ,30458   ,453,453,453
BEGIN DESCRIPTION:
DOOLEY CREEK 47.02
END DESCRIPTION:
XS GIS Cut Line= 2
      3512110.97     10503006.64      3511113.57     10501949.35
#Sta/Elev= 30
  4431.1  439.98  4462.2  439.69  4696.6  419.22  4716.7  416.54  4738.2  416.06
  4759.2  411.08  4780.6  409.48  4822.9  407.48    4851  411.17  4879.3  411.14
  4900.8  409.51  4921.8  405.55    4936  404.84  4950.1  403.49    4977  403.43
  4996.9   402.9  4999.7   402.4  5002.9   402.9  5028.2  404.04  5063.6  404.04
  5298.8  404.71  5360.4  405.02  5455.6  413.81  5565.5     425  5643.6  431.26
  5678.8  432.64  5721.3  437.03  5862.9  447.49  5882.4  449.92  5884.6  449.92
#Mann= 9 ,-1 , 0
  4431.1     .16       0  4696.6     .05       0    4977     .07       0
  4996.9     .07       0  5002.9     .07       0  5063.6     .12       0
  5298.8     .16       0  5455.6      .1       0  5882.4     .16       0
Bank Sta=4936,5028.2
XS Rating Curve= 0 ,0
Exp/Cntr=0.3,0.1

Type RM Length L Ch R = 1 ,30005   ,53,53,53
BEGIN DESCRIPTION:
DOOLEY CREEK 45.01
END DESCRIPTION:
XS GIS Cut Line= 3
      3512130.56     10502644.23      3511922.22     10502153.76
      3513187.26     10500437.37
#Sta/Elev= 30
  4553.6  430.71  4614.9  426.82    4644  425.92  4662.2  426.74  4691.3  424.85
  4714.9  425.52  4720.4  423.65    4744  421.62  4762.2  416.53  4767.7  412.47
  4773.7   410.7  4796.8  406.46  4820.4  408.42  4844.1  408.67  4920.5  404.62
  4952.7  402.78  5053.5  403.08  5205.8  402.69  5471.2  401.57    5474  401.07
  5477.2  401.57  5752.9  402.29  6018.2  404.74  6195.6  404.33  6604.7  407.48
  6640.6  406.86  7033.2  414.73  7089.5  418.29  7143.1  419.89  7218.7   423.6
#Mann= 7 ,-1 , 0
  4553.6     .05       0  4952.7     .07       0  5053.5     .05       0
  5205.8     .16       0  5471.2     .07       0  5477.2     .16       0
  7143.1     .08       0
#XS Ineff= 1 ,-1
 6103.76 6124.61  405.14
Permanent Ineff=
       F
Bank Sta=4920.5,6018.2
XS Rating Curve= 0 ,0
Exp/Cntr=0.3,0.1

Type RM Length L Ch R = 1 ,29952   ,501,501,501
BEGIN DESCRIPTION:
DOOLEY CREEK 45.0
END DESCRIPTION:
XS GIS Cut Line= 4
      3512124.05     10502567.92      3511976.47     10502142.55
      3512909.63     10500879.53      3513159.86      10500506.6
#Sta/Elev= 30
  4608.9  428.41  4700.2  426.25  4742.6  422.01  4774.3  414.85  4786.4  408.33
  4795.5  406.77  4848.7  408.41  4905.6  405.85  4935.6  403.32    4999  404.08
  5023.2  403.05    5038   403.4  5082.5  403.61  5148.9  404.06  5184.6  402.26
  5293.1  402.79    5361  401.58  5363.8  401.08    5367  401.58    5650  401.95
  6015.4  404.85  6042.5   403.7  6057.1  404.77  6357.8  404.75  6565.1   407.8
    6752  412.33    6788   411.6  7037.3  418.25  7044.7  418.36  7078.6  419.48
#Mann= 10 ,-1 , 0
  4608.9     .05       0  4935.6      .1       0  5023.2     .07       0
    5038     .05       0  5082.5     .16       0    5361     .07       0
    5367     .16       0  6565.1     .05       0  7037.3     .16       0
  7044.7     .08       0
#XS Ineff= 1 ,-1
 6030.68 6057.95  404.81
Permanent Ineff=
       F
Bank Sta=4905.6,6015.4
XS Rating Curve= 0 ,0
Exp/Cntr=0.3,0.1

Type RM Length L Ch R = 1 ,29451   ,150,150,150
BEGIN DESCRIPTION:
DOOLEY CREEK 44.0
END DESCRIPTION:
XS GIS Cut Line= 5
      3512178.69     10502460.55       3512165.5     10502289.02
      3512363.41     10502039.02      3512420.71     10501910.54
      3513020.91     10500985.94
#Sta/Elev= 30
  4461.8  423.04  4495.8  421.74  4661.1  405.02  4663.4  404.72  4671.9  404.03
  4694.3  401.88  4785.7  401.15  4913.9  403.23  5004.6  401.25  5056.9  404.11
  5062.4  403.38  5101.6   406.4  5161.9  400.86  5164.6  400.36  5167.9  400.86
  5235.1  401.34  5294.7  403.72    5325   401.9  5353.7  402.79  5376.4  402.49
  5382.4  403.75  5397.5  402.34  5418.6  404.52  5433.8   403.1  5454.9  404.77
  5486.1  403.91  5657.2   401.7  5778.4   402.4  6019.7  404.49  6195.7  415.73
#Mann= 10 ,-1 , 0
  4461.8     .16       0  4495.8     .05       0  4661.1     .16       0
  4663.4     .05       0  5161.9     .04       0  5167.9     .05       0
  5235.1      .1       0  5353.7     .05       0  5486.1      .1       0
  5778.4     .05       0
Bank Sta=4671.9,5056.9
XS Rating Curve= 0 ,0
Exp/Cntr=0.3,0.1

Type RM Length L Ch R = 1 ,29301   ,881,881,881
BEGIN DESCRIPTION:
DOOLEY CREEK 44.01
END DESCRIPTION:
XS GIS Cut Line= 4
      3512245.34     10502455.71      3512484.94     10502039.02
      3512604.73     10501765.58       3513159.4     10500921.87
#Sta/Elev= 30
  4433.3  415.84  4440.3  413.57  4456.1  412.84  4461.9  411.28    4477  412.03
  4542.4  404.21  4558.2  403.39  4654.5  401.08  4755.3  401.09  4970.2  401.16
  4976.6  402.67  4987.5  401.82    4996  398.89  4998.8  398.39    5002  398.89
  5016.9  400.07  5022.4  399.16  5040.3  402.03  5078.9  403.02  5235.1  405.88
  5408.7  406.57  5421.8  406.19  5444.6  401.48    5458  401.23  5806.8   402.5
  5855.7  402.83  5906.9   405.2  6114.8  419.44  6181.1  422.82  6222.2  423.09
#Mann= 6 ,-1 , 0
  4433.3     .16       0  4755.3     .05       0    4996     .04       0
    5002     .05       0  5078.9      .1       0  5806.8     .05       0
Bank Sta=4987.5,5040.3
XS Rating Curve= 0 ,0
Exp/Cntr=0.3,0.1

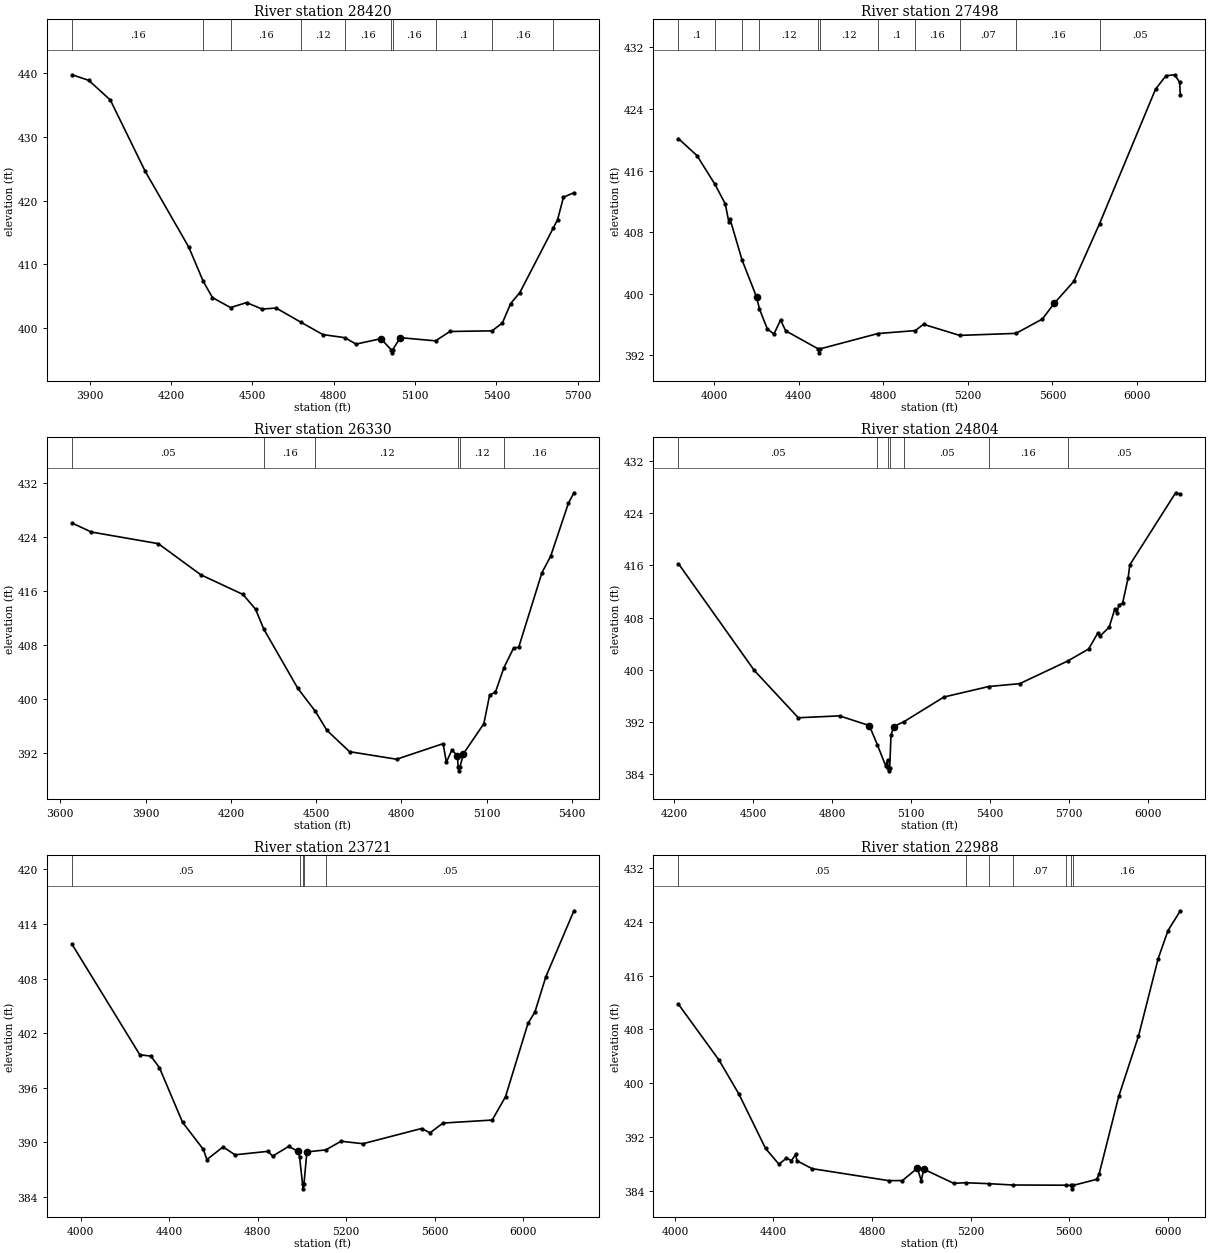
Type RM Length L Ch R = 1 ,28420   ,922,922,922
BEGIN DESCRIPTION:
DOOLEY CREEK 43.01
END DESCRIPTION:
XS GIS Cut Line= 2
      3513518.11     10502790.22      3513169.15     10500972.52
#Sta/Elev= 30
  3834.8  439.73  3896.3  438.86  3975.9  435.77  4104.3  424.61  4265.3  412.69
  4318.6  407.33  4352.7  404.78  4419.3  403.22  4478.3     404    4536  402.98
  4587.3  403.15  4677.9  400.94    4760  398.98  4840.5   398.5  4882.2  397.49
  4973.8  398.34  5011.5  396.62  5014.3  396.12  5017.5  396.62  5045.1   398.5
  5175.2     398  5228.4  399.47  5383.8  399.57  5421.8   400.8  5452.4  403.85
  5486.2  405.57  5608.9  415.64  5625.5  417.01  5647.2  420.53  5685.7  421.23
#Mann= 10 ,-1 , 0
  3834.8     .16       0  4318.6     .12       0  4419.3     .16       0
  4677.9     .12       0  4840.5     .16       0  5011.5     .07       0
  5017.5     .16       0  5175.2      .1       0  5383.8     .16       0
  5608.9     .05       0
Bank Sta=4973.8,5045.1
XS Rating Curve= 0 ,0
Exp/Cntr=0.3,0.1

Type RM Length L Ch R = 1 ,27498   ,1168,1168,1168
BEGIN DESCRIPTION:
DOOLEY CREEK 43.0
END DESCRIPTION:
XS GIS Cut Line= 3
      3514445.18     10502811.03       3514012.9     10501555.86
      3514288.76     10500546.09
#Sta/Elev= 30
    3831  420.14  3918.7  417.94  4003.9  414.19  4052.5  411.66  4069.5  409.26
  4074.8  409.71  4131.8  404.36  4200.5  399.55  4214.3  397.98  4251.6  395.38
  4282.8  394.74    4314  396.56    4338  395.16    4493  392.79  4495.8  392.29
    4499  392.79  4774.4   394.8  4950.8  395.18  4990.3     396  5161.1  394.56
  5427.8  394.82  5552.8  396.69  5608.7  398.73  5701.2  401.58  5823.1  409.08
  6087.9  426.57  6137.3  428.33  6178.8  428.45  6201.9  427.48  6205.3  425.78
#Mann= 11 ,-1 , 0
    3831      .1       0  4003.9     .16       0  4131.8     .05       0
  4214.3     .12       0    4493     .07       0    4499     .12       0
  4774.4      .1       0  4950.8     .16       0  5161.1     .07       0
  5427.8     .16       0  5823.1     .05       0
Bank Sta=4200.5,5608.7
XS Rating Curve= 0 ,0
Exp/Cntr=0.3,0.1

Type RM Length L Ch R = 1 ,26330   ,1526,1526,1526
BEGIN DESCRIPTION:
DOOLEY CREEK 42.0
END DESCRIPTION:
XS GIS Cut Line= 2
      3514621.73     10503518.31       3514992.1     10501791.68
#Sta/Elev= 30
  3641.2  426.07  3709.4  424.74  3944.6  423.02  4094.4   418.4  4242.7  415.49
  4286.9   413.3  4315.9  410.35  4435.5  401.58  4497.6  398.15  4537.8  395.36
  4617.5  392.19  4783.3  391.07  4946.9  393.38  4958.2  390.63  4977.6  392.42
  4997.4   391.6  4999.5  389.85  5002.3  389.35  5005.5  389.85  5018.5   391.9
  5090.1  396.33  5110.5  400.58    5131  401.02    5161  404.66    5195  407.56
  5212.8  407.66  5294.6  418.72  5325.3  421.16  5387.5  428.99  5407.1  430.56
#Mann= 6 ,-1 , 0
  3641.2     .05       0  4315.9     .16       0  4497.6     .12       0
  4999.5     .07       0  5005.5     .12       0    5161     .16       0
Bank Sta=4997.4,5018.5
XS Rating Curve= 0 ,0
Exp/Cntr=0.3,0.1

Type RM Length L Ch R = 1 ,24804   ,1083,1083,1083
BEGIN DESCRIPTION:
DOOLEY CREEK 41.0
END DESCRIPTION:
XS GIS Cut Line= 3
      3516195.19     10503446.48      3515929.57     10502352.73
      3515497.29     10501701.72
#Sta/Elev= 30
    4216  416.26  4504.2  399.89  4671.3  392.64  4828.1  392.93  4941.3  391.44
  4971.8  388.49  5003.1   385.3  5010.6  386.15  5012.7     385  5015.5   384.5
  5018.7     385  5023.6  389.98  5033.9  391.28  5073.8  392.06  5224.6  395.82
    5395  397.43  5512.8  397.87    5695  401.34  5774.4  403.18  5810.5   405.7
  5816.5  405.12  5852.6  406.52  5873.6  409.27  5882.7   408.7  5888.7  409.87
  5903.7  410.21  5924.8  414.11    5931  416.08  6105.2  427.14    6123  426.91
#Mann= 7 ,-1 , 0
    4216     .05       0  4971.8      .1       0  5012.7     .07       0
  5018.7      .1       0  5073.8     .05       0    5395     .16       0
    5695     .05       0
Bank Sta=4941.3,5033.9
XS Rating Curve= 0 ,0
Exp/Cntr=0.3,0.1

Type RM Length L Ch R = 1 ,23721   ,733,733,733
BEGIN DESCRIPTION:
DOOLEY CREEK 39.0
END DESCRIPTION:
XS GIS Cut Line= 2
      3517470.38     10503456.06      3516416.44     10501447.93
#Sta/Elev= 30
  3961.2  411.76  4267.5  399.62  4317.2  399.48  4355.7  398.22  4460.3  392.21
  4554.2  389.23  4570.6  388.11  4643.8   389.5  4697.2  388.63    4846  389.01
    4868  388.49  4939.8  389.55  4983.9     389  4989.2  388.39    5003  385.39
  5005.7  384.89    5009  385.39  5022.4  388.95  5107.6  389.17  5176.8  390.12
  5275.7  389.85  5540.4  391.52  5578.8  391.05  5637.6  392.12  5859.9  392.45
    5920  395.02  6021.6  403.08  6052.7  404.31  6102.4  408.21  6229.1  415.45
#Mann= 5 ,-1 , 0
  3961.2     .05       0  4989.2      .1       0    5003     .07       0
    5009      .1       0  5107.6     .05       0
Bank Sta=4983.9,5022.4
XS Rating Curve= 0 ,0
Exp/Cntr=0.3,0.1

Type RM Length L Ch R = 1 ,22988   ,525,525,525
BEGIN DESCRIPTION:
DOOLEY CREEK 37.0
END DESCRIPTION:
XS GIS Cut Line= 3
      3517509.44     10503434.28      3517696.06     10502301.52
      3517696.06     10501411.75
#Sta/Elev= 30
  4014.2  411.76    4179  403.43  4260.1  398.35  4367.7  390.29  4422.3  387.93
  4452.7  388.85  4472.9  388.47  4490.1  389.39  4495.1  388.46  4556.3  387.28
  4868.2  385.49  4923.3   385.5  4984.4  387.35    5000  385.47  5010.1   387.2
  5131.7  385.09  5179.8  385.18    5274  385.04  5372.1  384.84  5589.8  384.81
  5609.1  384.77  5611.9  384.27  5615.1  384.77  5712.1  385.68  5722.1  386.46
  5802.1  398.06  5882.1  407.01  5962.1  418.56  6002.1  422.74    6052  425.68
#Mann= 7 ,-1 , 0
  4014.2     .05       0  5179.8      .1       0    5274     .16       0
  5372.1     .07       0  5589.8     .16       0  5609.1     .03       0
  5615.1     .16       0
Bank Sta=4984.4,5010.1
XS Rating Curve= 0 ,0
Exp/Cntr=0.3,0.1

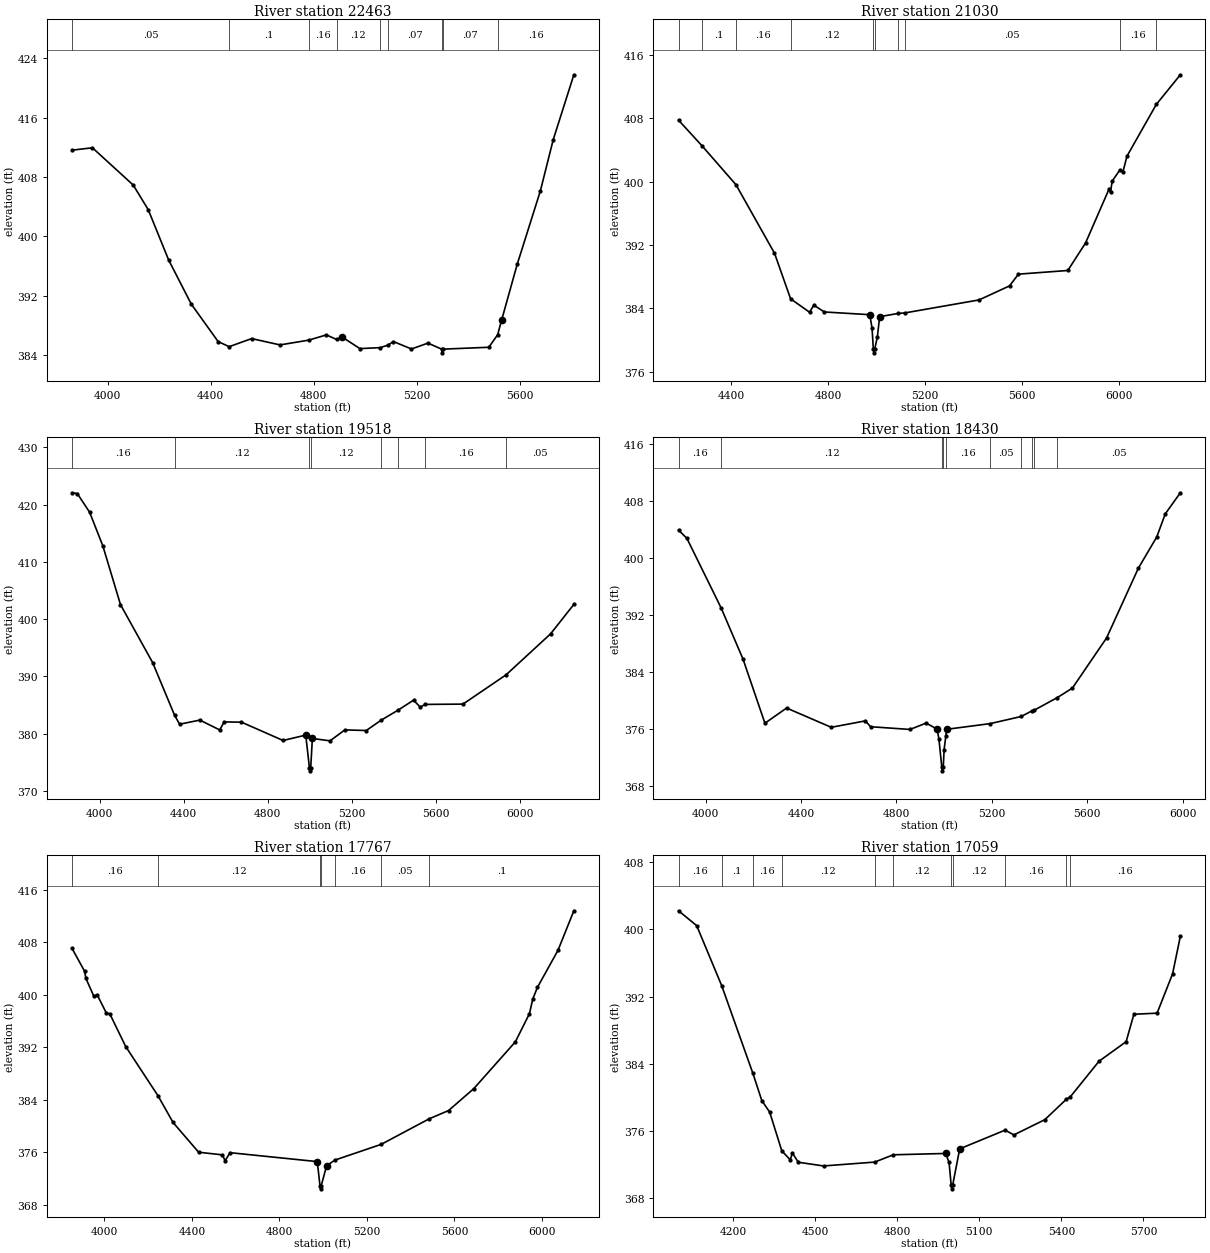
Type RM Length L Ch R = 1 ,22463   ,1433,1433,1433
BEGIN DESCRIPTION:
DOOLEY CREEK 35.0
END DESCRIPTION:
XS GIS Cut Line= 3
      3517813.36     10503360.21      3518056.42     10502964.36
      3517976.56     10501481.73
#Sta/Elev= 30
  3861.4   411.6  3940.5  411.92  4099.1  406.89  4157.1  403.59  4236.4  396.81
  4324.6  390.84  4428.8   385.8  4471.7  385.11    4559   386.2  4669.1  385.35
  4780.7  385.99  4849.4   386.7  4888.9  386.08  4909.5  386.43  4979.6  384.85
  5058.2  384.98    5089  385.32  5109.8   385.8  5179.9   384.8  5243.9  385.59
    5297  384.78  5299.8  384.28    5303  384.78  5480.3  385.03  5514.5  386.71
  5530.4  388.73  5590.5   396.2  5680.6  406.11  5730.7  413.03  5810.7  421.76
#Mann= 9 ,-1 , 0
  3861.4     .05       0  4471.7      .1       0  4780.7     .16       0
  4888.9     .12       0  5058.2     .16       0    5089     .07       0
    5297     .07       0    5303     .07       0  5514.5     .16       0
Bank Sta=4909.5,5530.4
XS Rating Curve= 0 ,0
Exp/Cntr=0.3,0.1

Type RM Length L Ch R = 1 ,21030   ,1512,1512,1512
BEGIN DESCRIPTION:
DOOLEY CREEK 33.0
END DESCRIPTION:
XS GIS Cut Line= 3
      3518717.19     10503192.24      3519185.93     10502140.18
      3519362.76     10501235.25
#Sta/Elev= 30
  4181.5  407.74  4279.9  404.46  4418.9   399.6  4578.1  390.97  4644.6  385.22
    4723  383.53  4740.5  384.42  4784.3  383.56  4971.7  383.22  4981.3  381.53
  4986.5  378.91  4989.2  378.41  4992.5  378.91  5003.2  380.42  5012.7  382.97
    5090  383.38  5116.6  383.44  5423.5  385.08  5549.4  386.85  5586.5  388.33
  5790.3  388.79  5863.8  392.27  5961.7  399.12  5966.8  398.68  5973.7  400.05
  6005.1  401.45  6018.4  401.26  6034.8   403.2    6156  409.72  6255.3  413.46
#Mann= 10 ,-1 , 0
  4181.5     .05       0  4279.9      .1       0  4418.9     .16       0
  4644.6     .12       0  4986.5     .07       0  4992.5     .12       0
    5090     .16       0  5116.6     .05       0  6005.1     .16       0
    6156     .05       0
Bank Sta=4971.7,5012.7
XS Rating Curve= 0 ,0
Exp/Cntr=0.3,0.1

Type RM Length L Ch R = 1 ,19518   ,1088,1088,1088
BEGIN DESCRIPTION:
DOOLEY CREEK 31.0
END DESCRIPTION:
XS GIS Cut Line= 2
      3519909.88     10503041.26      3520638.84     10500765.87
#Sta/Elev= 30
  3868.7  422.05  3893.5  421.92  3952.3  418.65  4015.3  412.77  4099.3  402.52
  4252.3   392.4  4356.7  383.21  4380.8  381.64  4477.2  382.36  4571.8  380.64
  4592.8  382.04  4675.3     382  4873.4   378.8  4981.4  379.74    4999     374
  5001.7   373.5    5005     374  5012.9  379.15  5096.9  378.74  5167.9  380.65
  5269.6  380.54  5340.6  382.35  5422.1  384.12  5494.6  385.84  5526.7  384.62
  5549.9   385.1    5730  385.15  5935.1  390.26  6146.9  397.41    6258  402.56
#Mann= 8 ,-1 , 0
  3868.7     .16       0  4356.7     .12       0    4999     .07       0
    5005     .12       0  5340.6     .16       0  5422.1     .12       0
  5549.9     .16       0  5935.1     .05       0
Bank Sta=4981.4,5012.9
XS Rating Curve= 0 ,0
Exp/Cntr=0.3,0.1

Type RM Length L Ch R = 1 ,18430   ,663,663,663
BEGIN DESCRIPTION:
DOOLEY CREEK 29.0
END DESCRIPTION:
XS GIS Cut Line= 2
      3520774.46     10503093.33      3521654.67     10501181.86
#Sta/Elev= 30
  3886.4   403.9  3921.7  402.72  4065.1  392.98  4156.9  385.81  4248.7  376.83
  4339.6  378.96  4526.8  376.26  4669.9  377.16  4691.9  376.34  4857.1  375.96
  4924.7  376.85  4970.6  376.01  4978.2  374.68  4990.6  370.66  4993.3  370.16
  4996.6  370.66  5000.2  373.14  5007.5  375.06    5011  375.98    5194  376.78
    5324  377.78  5369.8  378.59  5377.5  378.65  5474.3  380.41  5538.3  381.76
  5681.5  388.78  5814.9  398.56    5892  402.93  5927.7  406.17  5990.8  409.12
#Mann= 10 ,-1 , 0
  3886.4     .16       0  4065.1     .12       0  4990.6     .07       0
  4996.6     .12       0  5007.5     .16       0    5194     .05       0
    5324     .16       0  5369.8     .05       0  5377.5     .16       0
  5474.3     .05       0
Bank Sta=4970.6,5011
XS Rating Curve= 0 ,0
Exp/Cntr=0.3,0.1

Type RM Length L Ch R = 1 ,17767   ,708,708,708
BEGIN DESCRIPTION:
DOOLEY CREEK 28.0
END DESCRIPTION:
XS GIS Cut Line= 2
      3521133.84     10503411.02      3522366.66     10501475.97
#Sta/Elev= 30
  3851.9  407.05  3909.2  403.57  3915.1  402.49  3951.5  399.76  3966.7  399.98
    4009  397.18  4024.3  397.09  4097.1   392.1  4244.9  384.59  4313.6  380.53
  4430.6  375.99  4538.9  375.59  4551.6   374.7  4574.4  375.92  4973.1  374.56
  4985.4  370.91  4988.1  370.41  4991.4  370.91  5015.5  373.91  5053.3  374.79
  5265.3  377.19  5485.9   381.1  5573.3  382.34    5689  385.69  5878.7  392.81
  5943.2  397.11  5958.4  399.33  5979.6  401.11  6073.5  406.75  6146.3  412.79
#Mann= 7 ,-1 , 0
  3851.9     .16       0  4244.9     .12       0  4985.4     .07       0
  4991.4     .12       0  5053.3     .16       0  5265.3     .05       0
  5485.9      .1       0
Bank Sta=4973.1,5015.5
XS Rating Curve= 0 ,0
Exp/Cntr=0.3,0.1

Type RM Length L Ch R = 1 ,17059   ,846,846,846
BEGIN DESCRIPTION:
DOOLEY CREEK 26.0
END DESCRIPTION:
XS GIS Cut Line= 3
      3521942.11     10503591.63      3522342.11     10502691.64
      3522942.11     10502091.64
#Sta/Elev= 30
  4001.3  402.23  4067.6  400.46    4159   393.3    4273  382.84  4305.6  379.59
  4334.4  378.21  4378.5  373.61  4409.6  372.52  4417.1  373.35    4439  372.24
  4531.3   371.8  4718.1  372.26    4786  373.13  4977.3  373.29  4989.7  372.22
  4997.3  369.57  5000.1  369.07  5003.3  369.57  5028.6  373.84  5194.4  376.07
  5226.6   375.5  5339.7  377.32  5418.8  379.77  5433.2  380.06  5537.7  384.29
  5636.7  386.62    5665  389.89  5749.8  390.02  5806.4  394.71  5834.7  399.18
#Mann= 11 ,-1 , 0
  4001.3     .16       0    4159      .1       0    4273     .16       0
  4378.5     .12       0  4718.1     .16       0    4786     .12       0
  4997.3     .07       0  5003.3     .12       0  5194.4     .16       0
  5418.8     .05       0  5433.2     .16       0
Bank Sta=4977.3,5028.6
XS Rating Curve= 0 ,0
Exp/Cntr=0.3,0.1