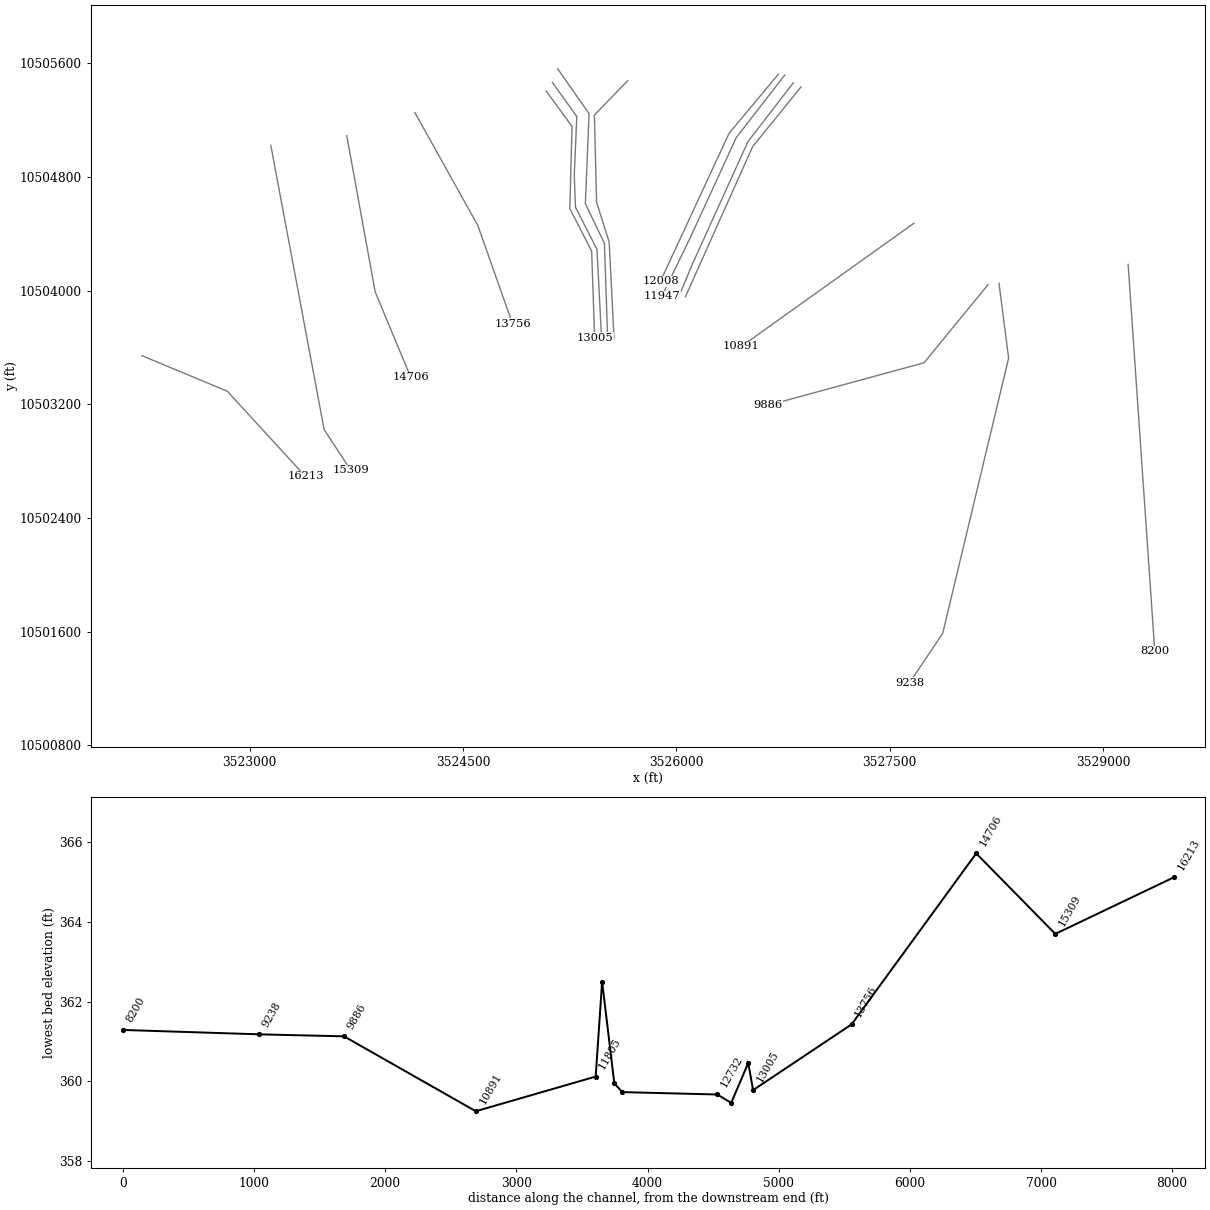
HEC-RAS study DOOLEY CREEK.prj: DOOLEY CREEK Base Level Engineering

--- DOOLEY CREEK.g01 (geometry) --- (continued)

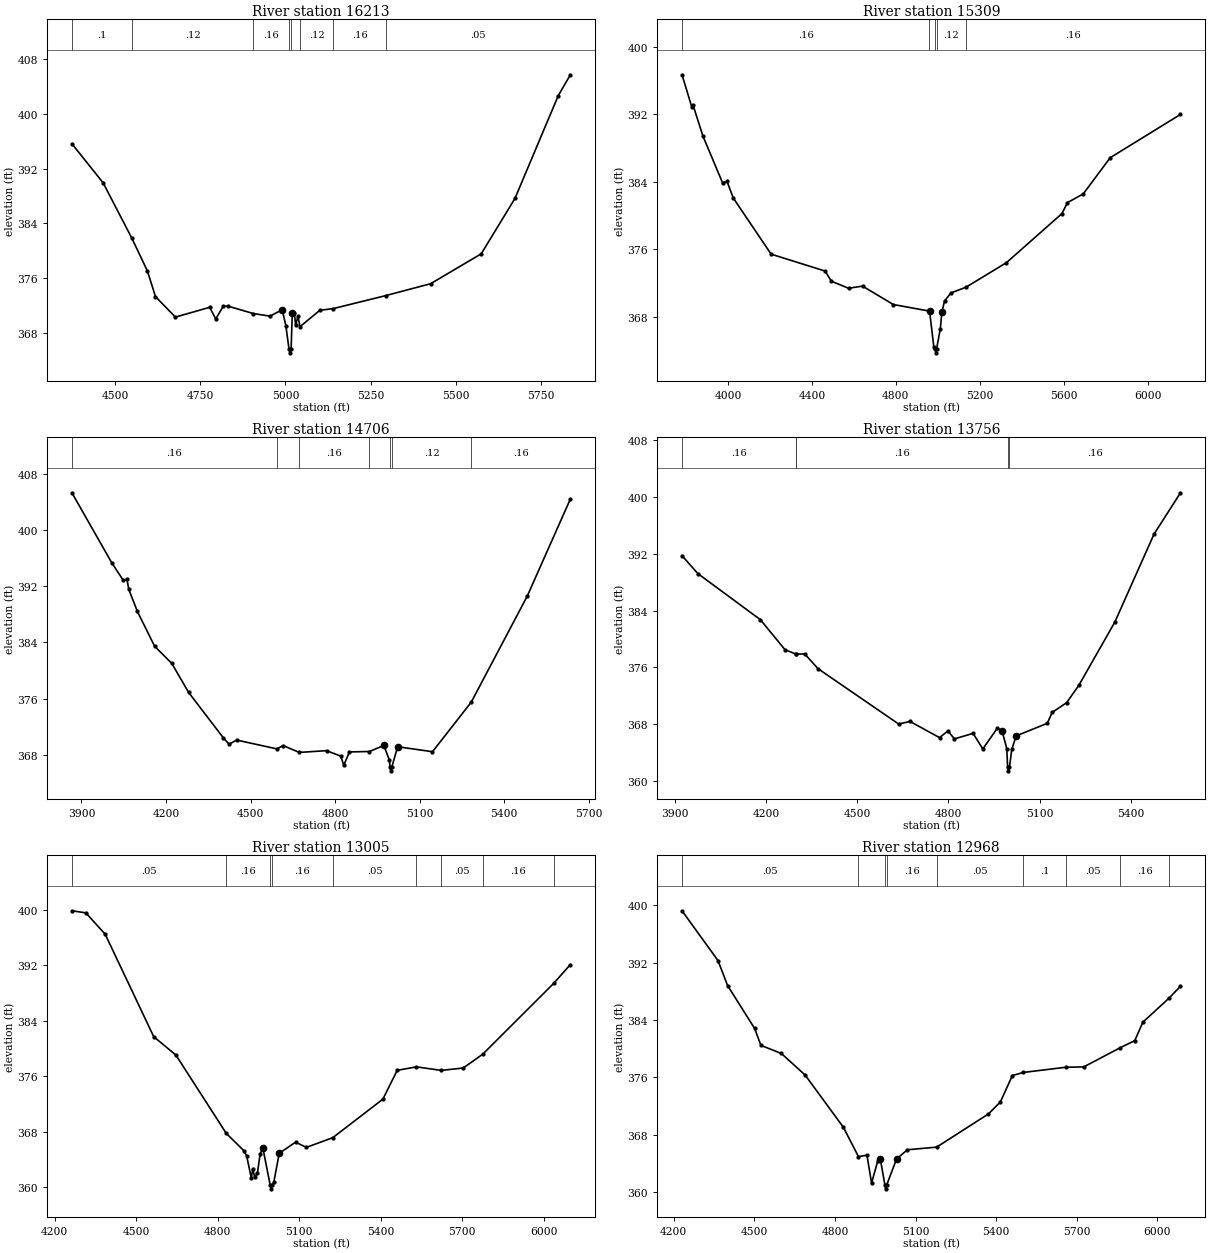
Type RM Length L Ch R = 1 ,16213   ,904,904,904
BEGIN DESCRIPTION:
DOOLEY CREEK 24.0
END DESCRIPTION:
XS GIS Cut Line= 3
      3522242.06     10503541.66      3522842.11     10503291.64
      3523392.11     10502691.64
#Sta/Elev= 30
  4372.9  395.61  4464.5  389.92  4548.4  381.89  4594.5  377.08  4618.3  373.33
  4676.8  370.33  4777.6  371.76  4795.4  370.06  4817.1   371.9  4830.7  371.94
  4905.8  370.85  4955.2  370.47  4990.4  371.42  5001.3  369.08  5010.7  365.62
  5013.5  365.12  5016.7  365.62  5020.2  370.91  5026.3  370.91    5030  369.12
  5036.8  370.47  5042.8  368.93    5101  371.32  5141.2  371.58  5294.1  373.46
  5426.5   375.2  5575.1  379.56  5674.1  387.63  5801.4  402.63  5836.9  405.67
#Mann= 8 ,-1 , 0
  4372.9      .1       0  4548.4     .12       0  4905.8     .16       0
  5010.7     .07       0  5016.7     .16       0  5042.8     .12       0
  5141.2     .16       0  5294.1     .05       0
Bank Sta=4990.4,5020.2
XS Rating Curve= 0 ,0
Exp/Cntr=0.3,0.1

Type RM Length L Ch R = 1 ,15309   ,603,603,603
BEGIN DESCRIPTION:
DOOLEY CREEK 22.0
END DESCRIPTION:
XS GIS Cut Line= 3
      3523148.34     10505021.64      3523523.34     10503021.63
      3523710.33     10502735.95
#Sta/Elev= 30
  3780.6  396.67  3827.3  392.83  3832.4  393.13  3879.8  389.43  3973.9  383.85
  3995.2  384.02  4024.8  382.06  4205.4   375.4  4462.3   373.4  4492.8  372.19
  4574.2  371.36  4641.2  371.61  4787.8  369.43  4959.6  368.65  4960.8  368.62
  4981.2  364.35  4988.3   364.2  4991.1   363.7  4994.3   364.2  5011.7  366.52
  5019.4  368.51    5032  369.85  5062.6   370.8  5134.1  371.48  5327.1  374.39
  5591.6  380.21  5617.9  381.51  5693.4  382.55  5821.9  386.84  6156.9  391.97
#Mann= 5 ,-1 , 0
  3780.6     .16       0  4959.6     .12       0  4988.3     .07       0
  4994.3     .12       0  5134.1     .16       0
Bank Sta=4960.8,5019.4
XS Rating Curve= 0 ,0
Exp/Cntr=0.3,0.1

Type RM Length L Ch R = 1 ,14706   ,950,950,950
BEGIN DESCRIPTION:
DOOLEY CREEK 21.0
END DESCRIPTION:
XS GIS Cut Line= 3
      3523682.39     10505090.22      3523882.38     10503990.25
      3524132.38     10503390.25
#Sta/Elev= 30
  3866.4  405.27  4008.5  395.26  4047.9  392.86  4061.8  392.94  4068.2  391.52
  4098.7  388.39  4159.7  383.45  4220.7     381  4280.3  376.88  4403.6  370.41
    4424  369.51  4450.6   370.1  4593.5  368.84  4615.7  369.31    4673  368.34
  4769.5  368.59  4820.4  367.81  4830.5   366.5  4850.9  368.41  4921.9  368.47
  4972.8  369.33  4992.5  367.25  4994.9  366.22  4997.7  365.72  5000.9  366.22
  5021.7  369.15  5145.4  368.44    5283   375.5  5481.2  390.55  5634.4  404.38
#Mann= 7 ,-1 , 0
  3866.4     .16       0  4593.5     .05       0    4673     .16       0
  4921.9     .12       0  4994.9     .07       0  5000.9     .12       0
    5283     .16       0
Bank Sta=4972.8,5021.7
XS Rating Curve= 0 ,0
Exp/Cntr=0.3,0.1

Type RM Length L Ch R = 1 ,13756   ,751,751,751
BEGIN DESCRIPTION:
DOOLEY CREEK 19.0
END DESCRIPTION:
XS GIS Cut Line= 3
      3524161.64     10505251.84      3524604.33     10504457.61
      3524847.24     10503767.91
#Sta/Elev= 30
  3923.3  391.73  3975.3  389.21  4181.1  382.72  4262.2  378.49    4297  377.89
  4299.8  377.89  4327.4  377.88  4370.8  375.82    4636  368.03  4673.7  368.38
  4770.7  366.11  4798.3  367.04    4820  365.93  4881.3  366.71  4913.1  364.51
  4961.1  367.44  4976.7  367.06    4992  364.56  4994.9  361.93  4997.7  361.43
  5000.9  361.93  5008.5  364.44    5023  366.35  5125.2  368.12  5141.5  369.66
  5188.8  371.02  5229.1  373.46  5347.6  382.37  5476.7  394.77  5563.8  400.59
#Mann= 5 ,-1 , 0
  3923.3     .16       0    4297     .05       0  4299.8     .16       0
  4994.9     .07       0  5000.9     .16       0
Bank Sta=4976.7,5023
XS Rating Curve= 0 ,0
Exp/Cntr=0.3,0.1

Type RM Length L Ch R = 1 ,13005   ,37,37,37
BEGIN DESCRIPTION:
DOOLEY CREEK 17.01
END DESCRIPTION:
XS GIS Cut Line= 5
      3525084.34     10505404.91      3525266.65     10505154.88
      3525251.03     10504576.75      3525404.67     10504277.27
      3525425.51      10503667.9
#Sta/Elev= 30
  4263.3  399.88  4314.8  399.58  4385.9  396.49  4564.4  381.72    4646  379.07
  4831.5  367.77  4896.1  365.28  4906.1  364.56  4923.6  361.31  4928.6   362.7
  4936.1  361.42  4946.1  362.12  4956.1  364.87  4966.1  365.64  4993.1  360.28
  4995.9  359.78  4999.1  360.28  5006.1  360.71  5026.1   364.9  5086.2  366.51
  5126.2  365.76  5223.3  367.16  5407.5  372.71  5460.3  376.87  5531.2  377.37
  5623.1  376.86  5703.4  377.21  5775.4  379.21    6036  389.41  6097.4  392.12
#Mann= 9 ,-1 , 0
  4263.3     .05       0  4831.5     .16       0  4993.1     .07       0
  4999.1     .16       0  5223.3     .05       0  5531.2      .1       0
  5623.1     .05       0  5775.4     .16       0    6036     .05       0
Bank Sta=4966.1,5026.1
XS Rating Curve= 0 ,0
Exp/Cntr=0.3,0.1

Type RM Length L Ch R = 1 ,12968   ,130,130,130
BEGIN DESCRIPTION:
DOOLEY CREEK 17.0
END DESCRIPTION:
XS GIS Cut Line= 6
      3525128.32     10505464.39      3525300.19     10505224.82
      3525282.37     10504812.39      3525290.96     10504586.52
        3525442.     10504289.64      3525472.39     10503701.71
#Sta/Elev= 30
  4230.7  399.26  4364.6  392.31  4400.2  388.83  4500.9  382.84  4524.4  380.48
  4600.4  379.35  4688.9  376.34  4831.3  369.05  4887.4  364.96  4919.1  365.15
  4936.2  361.26  4959.1  364.33  4969.1  364.56  4986.1  360.96  4988.9  360.46
  4992.1  360.96  5029.2  364.61  5069.2  365.91  5178.4  366.28  5371.3  370.91
  5415.8  372.59  5460.3  376.27  5501.1   376.7    5660  377.43  5725.8  377.47
  5861.8  380.15    5916  381.14  5946.1  383.71  6043.3  387.06  6086.2  388.73
#Mann= 9 ,-1 , 0
  4230.7     .05       0  4887.4     .16       0  4986.1     .07       0
  4992.1     .16       0  5178.4     .05       0  5501.1      .1       0
    5660     .05       0  5861.8     .16       0  6043.3     .05       0
Bank Sta=4969.1,5029.2
XS Rating Curve= 0 ,0
Exp/Cntr=0.3,0.1

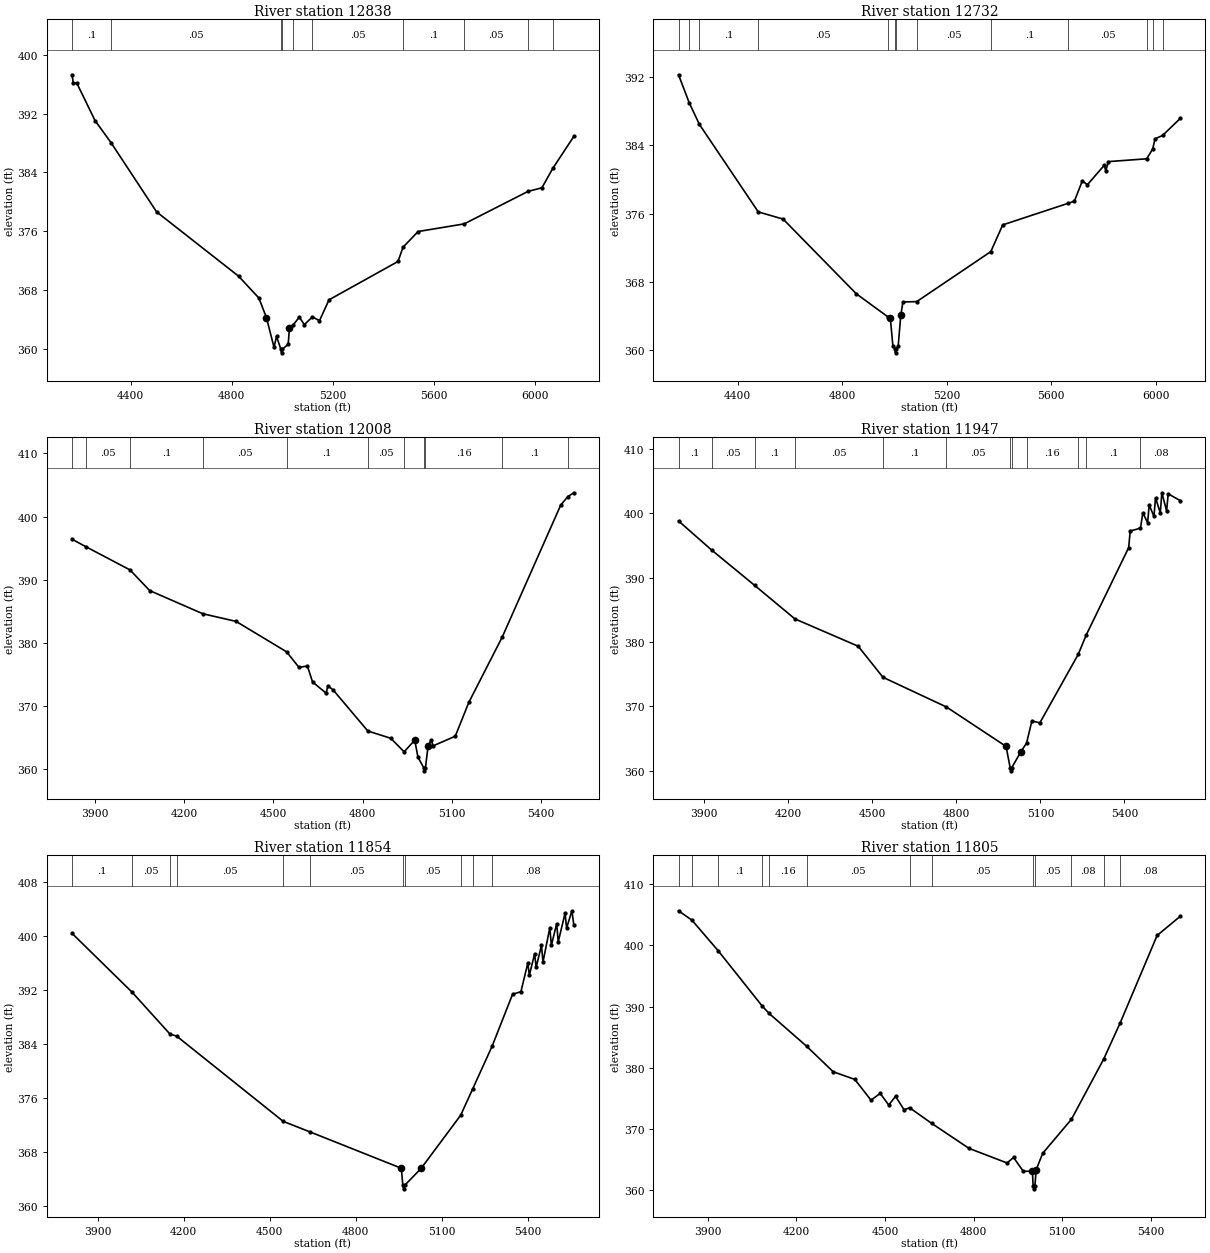
Type RM Length L Ch R = 1 ,12838   ,106,106,106
BEGIN DESCRIPTION:
DOOLEY CREEK 17.02
END DESCRIPTION:
XS GIS Cut Line= 5
      3525165.11      10505561.1      3525386.45      10505245.5
       3525360.4     10504611.39      3525494.52     10504331.44
      3525516.61     10503675.25
#Sta/Elev= 30
  4168.3  397.28  4172.8  396.22  4187.6  396.11  4259.1  391.06  4322.5  388.05
  4503.1  378.63  4827.9  369.88  4907.9  366.92    4938  364.25    4968  360.21
    4978   361.7    4995  359.96  4997.8  359.46    5001  359.96  5024.1  360.61
  5029.1  362.85  5044.5  363.27  5068.1  364.33  5088.1  363.29    5120  364.35
  5148.1  363.83  5185.8  366.67  5459.2  371.89  5478.9  373.83  5538.7  375.96
  5721.3     377  5973.3  381.41  6028.9  381.91  6071.8  384.54  6155.4   388.9
#Mann= 10 ,-1 , 0
  4168.3      .1       0  4322.5     .05       0    4995     .03       0
    5001     .05       0  5044.5     .16       0    5120     .05       0
  5478.9      .1       0  5721.3     .05       0  5973.3     .16       0
  6071.8     .05       0
Bank Sta=4938,5029.1
XS Rating Curve= 0 ,0
Exp/Cntr=0.3,0.1

Type RM Length L Ch R = 1 ,12732   ,724,724,724
BEGIN DESCRIPTION:
DOOLEY CREEK 17.03
END DESCRIPTION:
XS GIS Cut Line= 5
      3525658.18     10505476.87      3525423.77     10505234.65
       3525439.4     10504620.07      3525527.94     10504341.42
       3525561.8      10503666.9
#Sta/Elev= 30
  4174.4  392.27  4215.7  388.95  4254.3  386.45  4479.5  376.19  4574.5  375.35
  4854.6  366.59  4975.8  363.88  4984.6  363.75  4994.6  360.42  5001.6  360.17
  5004.4  359.67  5007.6  360.17  5014.6  360.42  5024.6   364.1  5032.9  365.63
  5085.8  365.68  5369.1  371.54  5414.5  374.67  5664.8   377.2  5688.7  377.45
  5718.8  379.81  5738.8  379.39  5802.4  381.64  5808.9  381.01  5818.9  382.09
  5965.4  382.42    5988  383.55  5997.3  384.76  6026.3  385.16    6094  387.16
#Mann= 13 ,-1 , 0
  4174.4      .1       0  4215.7     .05       0  4254.3      .1       0
  4479.5     .05       0  4975.8     .16       0  5001.6     .07       0
  5007.6     .16       0  5085.8     .05       0  5369.1      .1       0
  5664.8     .05       0  5965.4     .16       0    5988     .05       0
  6026.3     .16       0
Bank Sta=4984.6,5024.6
XS Rating Curve= 0 ,0
Exp/Cntr=0.3,0.1

Type RM Length L Ch R = 1 ,12008   ,61,61,61
BEGIN DESCRIPTION:
DOOLEY CREEK 15.01
END DESCRIPTION:
XS GIS Cut Line= 3
      3526718.03     10505522.83      3526370.82     10505106.18
      3525888.69      10504065.6
#Sta/Elev= 30
  3822.2  396.41  3869.8   395.2  4017.3  391.55  4083.4  388.28  4262.3  384.61
  4374.2   383.4  4544.4  378.58    4586  376.12  4614.4  376.33  4631.8   373.8
  4677.6  372.03  4683.1  373.17  4700.2  372.59  4817.8  366.04  4894.9  364.89
    4940  362.74  4975.7  364.59  4986.5  361.91  5005.8  360.23  5008.5  359.73
  5011.8  360.23  5020.5  363.61  5030.8  364.61  5037.9  363.69  5112.1  365.21
    5158  370.59  5270.7  380.96  5466.9  401.79    5491  403.17  5511.4  403.77
#Mann= 11 ,-1 , 0
  3822.2      .1       0  3869.8     .05       0  4017.3      .1       0
  4262.3     .05       0  4544.4      .1       0  4817.8     .05       0
    4940     .16       0  5005.8     .07       0  5011.8     .16       0
  5270.7      .1       0    5491     .08       0
Bank Sta=4975.7,5020.5
XS Rating Curve= 0 ,0
Exp/Cntr=0.3,0.1

Type RM Length L Ch R = 1 ,11947   ,93,93,93
BEGIN DESCRIPTION:
DOOLEY CREEK 15.0
END DESCRIPTION:
XS GIS Cut Line= 4
       3526762.3     10505515.88      3526421.17      10505075.8
      3526098.25     10504372.67      3525897.73     10503958.62
#Sta/Elev= 30
  3808.7  398.82  3926.6   394.3  4080.2   388.8  4224.1  383.58  4449.9  379.33
  4538.2   374.5  4764.8  369.88  4977.5  363.75    4992  360.45  4994.8  359.95
    4998  360.45  5030.3  362.93  5050.7  364.27  5069.5  367.72    5098  367.41
  5234.8  378.05  5263.8  381.11  5414.9  394.66  5420.5  397.25  5457.1   397.7
  5465.6  400.08  5482.6  398.54  5488.2   401.3  5505.2  399.52  5510.8  402.41
  5527.8  400.08  5533.4   403.2  5550.4  400.39    5556  403.03  5599.3  401.98
#Mann= 12 ,-1 , 0
  3808.7      .1       0  3926.6     .05       0  4080.2      .1       0
  4224.1     .05       0  4538.2      .1       0  4764.8     .05       0
    4992     .04       0    4998     .05       0  5050.7     .16       0
  5234.8     .05       0  5263.8      .1       0  5457.1     .08       0
Bank Sta=4977.5,5030.3
XS Rating Curve= 0 ,0
Exp/Cntr=0.3,0.1

Type RM Length L Ch R = 1 ,11854   ,49,49,49
BEGIN DESCRIPTION:
DOOLEY CREEK 14.0
END DESCRIPTION:
XS GIS Cut Line= 4
      3526823.14     10505462.67      3526503.69     10505047.73
       3526114.8     10504190.09      3526005.43     10503927.94
#Sta/Elev= 30
  3811.3  400.36  4021.3  391.61  4153.2  385.41  4175.4  385.15  4547.4   372.5
  4640.7  370.94  4959.2  365.55  4964.5     363  4967.3   362.5  4970.5     363
  5028.4  365.54  5166.1  373.41    5208  377.31  5275.8  383.65    5347  391.33
  5376.2  391.72  5400.1  395.95  5405.5  394.17  5423.9  397.32  5429.3  395.35
  5447.7  398.57  5453.1  396.12  5476.9   401.2  5482.3  398.58  5500.8   401.8
  5506.2   399.1    5530  403.35  5535.4  401.14  5553.8  403.71  5560.7  401.58
#Mann= 11 ,-1 , 0
  3811.3      .1       0  4021.3     .05       0  4153.2     .16       0
  4175.4     .05       0  4547.4      .1       0  4640.7     .05       0
  4964.5     .04       0  4970.5     .05       0  5166.1     .08       0
    5208     .05       0  5275.8     .08       0
Bank Sta=4959.2,5028.4
XS Rating Curve= 0 ,0
Exp/Cntr=0.3,0.1

Type RM Length L Ch R = 1 ,11805   ,914,914,914
BEGIN DESCRIPTION:
DOOLEY CREEK 14.01
END DESCRIPTION:
XS GIS Cut Line= 3
      3526876.72     10505432.44      3526536.45     10505012.31
      3526064.23     10503956.77
#Sta/Elev= 30
  3801.9  405.69  3847.2  404.15  3935.5  399.17  4085.3  390.05  4108.1  388.87
    4235  383.49  4324.9  379.31  4398.1  378.05  4452.8  374.65    4484  375.76
  4512.7  373.86  4535.9  375.28  4564.6  373.08  4583.5  373.41  4658.5  370.83
  4784.3  366.75  4912.9  364.36  4934.9  365.26  4967.7     363  4998.6     363
  5001.1  360.62  5003.8  360.12  5007.1  360.62  5011.5  363.26  5033.4  365.94
  5130.7  371.52  5240.1  381.42    5295  387.26  5420.4  401.64  5498.9   404.8
#Mann= 13 ,-1 , 0
  3801.9      .1       0  3847.2     .16       0  3935.5      .1       0
  4085.3     .05       0  4108.1     .16       0    4235     .05       0
  4583.5     .16       0  4658.5     .05       0  5001.1     .04       0
  5007.1     .05       0  5130.7     .08       0  5240.1     .16       0
    5295     .08       0
Bank Sta=4998.6,5011.5
XS Rating Curve= 0 ,0
Exp/Cntr=0.3,0.1

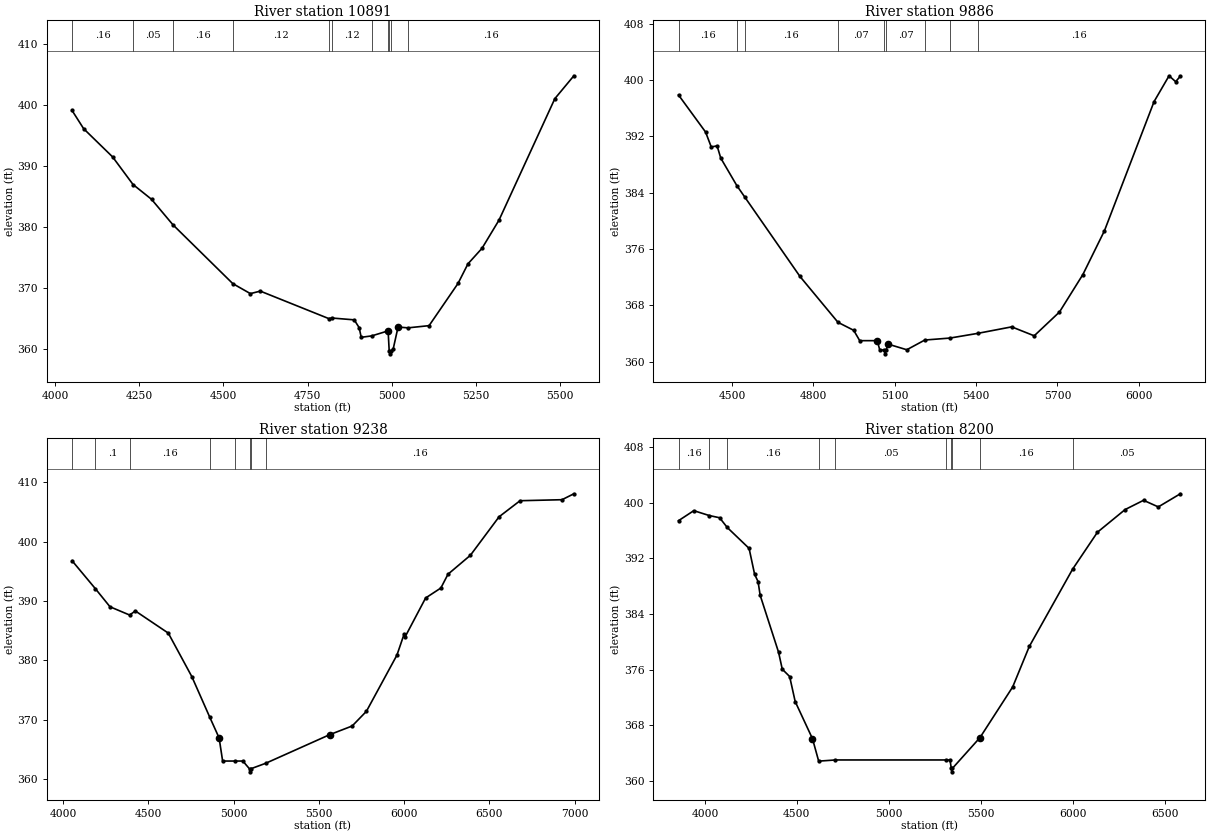
Type RM Length L Ch R = 1 ,10891   ,1005,1005,1005
BEGIN DESCRIPTION:
DOOLEY CREEK 12.0
END DESCRIPTION:
XS GIS Cut Line= 2
      3527670.15     10504473.09      3526457.11     10503606.64
#Sta/Elev= 30
  4050.3  399.13  4084.8  396.14  4170.8  391.52  4231.4     387  4286.3  384.58
  4349.6  380.42  4527.7  370.76    4580  369.12  4609.5  369.53  4812.8  365.03
  4822.2  365.12  4888.5  364.82  4903.2  363.54  4909.3  361.96  4940.4  362.19
  4988.4     363  4989.2     363  4992.4  359.75  4995.1  359.25  4998.4  359.75
    5004  359.97  5018.7  363.64  5048.4  363.51  5110.9  363.87  5196.9  370.79
  5226.4     374  5268.2  376.55  5318.6  381.16  5484.5  401.07    5541  404.82
#Mann= 11 ,-1 , 0
  4050.3     .16       0  4231.4     .05       0  4349.6     .16       0
  4527.7     .12       0  4812.8     .16       0  4822.2     .12       0
  4940.4     .07       0  4988.4     .12       0  4992.4     .07       0
  4998.4     .12       0  5048.4     .16       0
Bank Sta=4989.2,5018.7
XS Rating Curve= 0 ,0
Exp/Cntr=0.3,0.1

Type RM Length L Ch R = 1 ,9886    ,648,648,648
BEGIN DESCRIPTION:
DOOLEY CREEK 10.0
END DESCRIPTION:
XS GIS Cut Line= 3
      3528192.13     10504041.68      3527742.11     10503491.64
      3526642.06     10503191.63
#Sta/Elev= 30
  4302.2  397.87    4402  392.61  4422.8   390.5  4444.4  390.65    4458  388.91
  4517.4     385  4546.4  383.39  4750.2  372.11  4890.4   365.6  4948.3  364.47
  4970.5     363  5035.3     363    5044  361.74  5061.7  361.63  5064.5  361.13
  5067.7  361.63  5075.1  362.51  5144.2  361.71  5210.6  363.09  5303.6  363.37
    5405  364.03  5531.1  364.96  5614.1  363.69  5707.4  367.07  5793.7  372.39
  5873.2   378.6  6056.3  396.94  6111.6   400.6  6135.8  399.76  6153.1  400.54
#Mann= 9 ,-1 , 0
  4302.2     .16       0  4517.4     .05       0  4546.4     .16       0
  4890.4     .07       0  5061.7     .07       0  5067.7     .07       0
  5210.6     .12       0  5303.6     .07       0    5405     .16       0
Bank Sta=5035.3,5075.1
XS Rating Curve= 0 ,0
Exp/Cntr=0.3,0.1

Type RM Length L Ch R = 1 ,9238    ,1038,1038,1038
BEGIN DESCRIPTION:
DOOLEY CREEK 9.0
END DESCRIPTION:
XS GIS Cut Line= 4
      3528269.15     10504050.64      3528336.86     10503524.65
      3527873.31     10501587.15      3527638.92     10501238.17
#Sta/Elev= 30
  4053.2  396.77  4190.1  392.05  4275.6  389.01  4390.5  387.62  4424.5   388.3
  4617.5  384.57  4755.3  377.25  4861.1  370.37  4915.7  366.89  4936.2     363
    5009     363  5054.8     363  5093.9  361.68  5096.6  361.18  5099.9  361.68
  5188.6  362.62  5563.4  367.44  5695.9  368.91  5779.4  371.38  5958.5  380.86
  6000.6  384.41  6005.7   383.9  6126.7  390.49    6216  392.17    6258   394.5
  6389.3  397.69  6557.5  404.18  6680.6  406.89  6926.6  407.06  6996.1  408.06
#Mann= 8 ,-1 , 0
  4053.2     .16       0  4190.1      .1       0  4390.5     .16       0
  4861.1     .12       0    5009     .05       0  5093.9     .07       0
  5099.9     .05       0  5188.6     .16       0
Bank Sta=4915.7,5563.4
XS Rating Curve= 0 ,0
Exp/Cntr=0.3,0.1

Type RM Length L Ch R = 1 ,8200    ,1318,1318,1318
BEGIN DESCRIPTION:
DOOLEY CREEK 7.0
END DESCRIPTION:
XS GIS Cut Line= 2
      3529177.13      10504184.4      3529364.63     10501462.15
#Sta/Elev= 30
  3856.6  397.44  3939.6  398.88  4023.4  398.18  4079.9  397.86  4121.5  396.46
  4240.3  393.45  4270.3  389.72  4289.1  388.67  4300.4  386.71  4400.6   378.5
  4420.7  376.06  4460.8  375.01  4490.9  371.41    4585  366.06  4618.7  362.83
    4710     363  5311.1     363  5332.8     363  5339.9  361.79  5342.6  361.29
  5345.9  361.79  5495.9  366.22  5673.7  373.51  5763.9  379.33  5999.1  390.44
  6134.7  395.78  6285.1  399.04  6385.3  400.37  6465.5  399.42  6585.3  401.31
#Mann= 10 ,-1 , 0
  3856.6     .16       0  4023.4     .05       0  4121.5     .16       0
  4618.7     .12       0    4710     .05       0  5311.1     .12       0
  5339.9    .033       0  5345.9     .12       0  5495.9     .16       0
  5999.1     .05       0
Bank Sta=4585,5495.9
XS Rating Curve= 0 ,0
Exp/Cntr=0.3,0.1