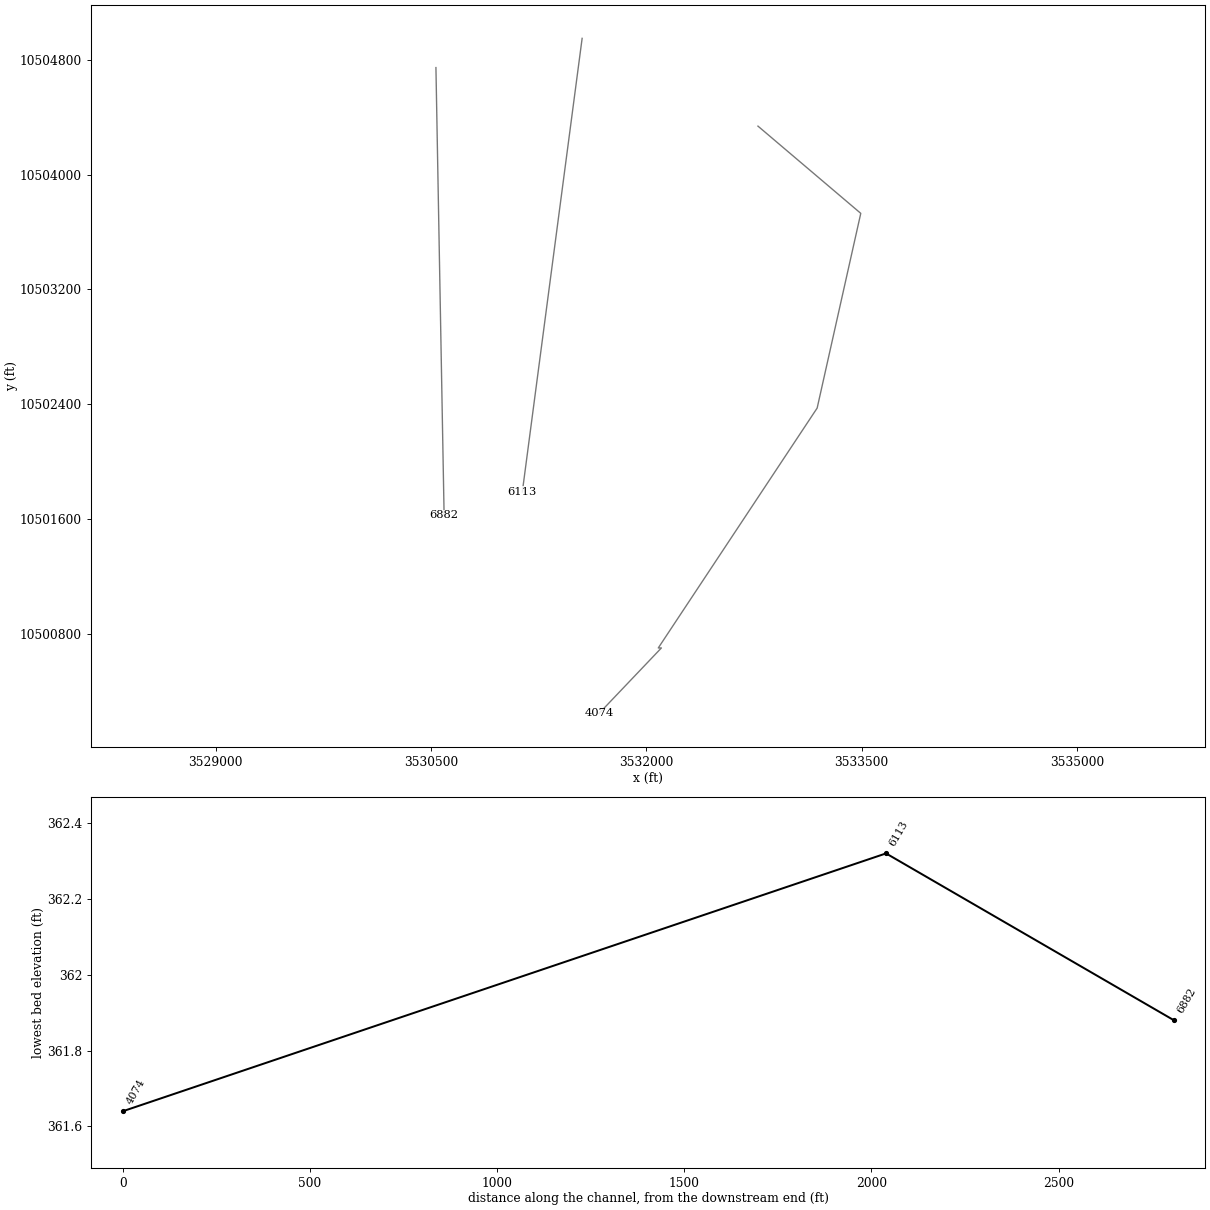
HEC-RAS study DOOLEY CREEK.prj: DOOLEY CREEK Base Level Engineering

--- DOOLEY CREEK.g01 (geometry) --- (continued)

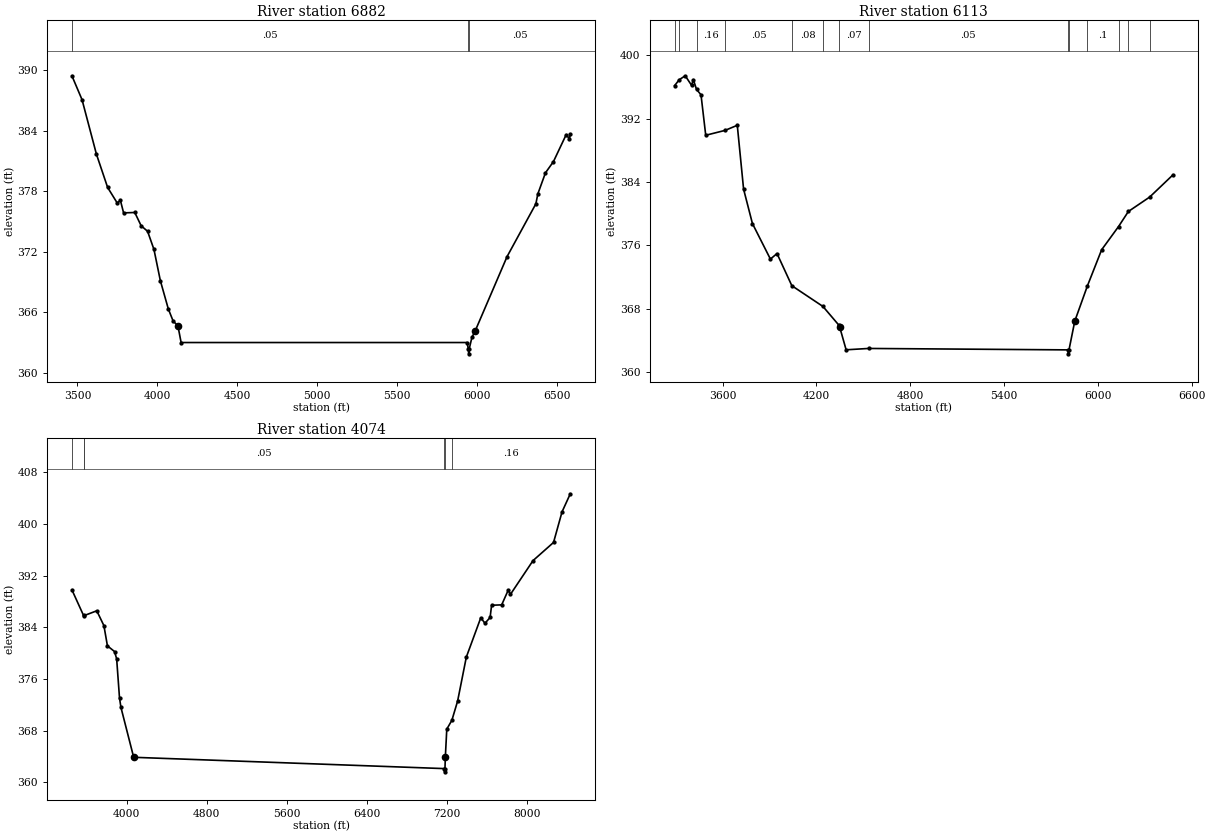
Type RM Length L Ch R = 1 ,6882    ,769,769,769
BEGIN DESCRIPTION:
DOOLEY CREEK 5.0
END DESCRIPTION:
XS GIS Cut Line= 2
       3530533.9     10504745.17      3530590.86     10501626.29
#Sta/Elev= 30
  3465.2  389.42  3528.7  387.05  3618.8  381.65  3688.8  378.36  3748.8  376.82
  3768.8  377.08  3788.8  375.84  3858.8  375.88  3898.8  374.56  3938.8  374.02
  3978.8  372.22  4018.8  369.13  4068.8  366.32  4098.8  365.13  4128.8  364.65
  4148.8     363  5939.1     363  5946.1  362.38  5948.9  361.88  5952.1  362.38
  5969.1  363.52  5989.1  364.14  6189.2  371.52  6369.2  376.74  6381.5  377.72
  6429.2  379.81  6479.2  380.92  6559.2   383.6  6579.2  383.17  6584.6  383.65
#Mann= 3 ,-1 , 0
  3465.2     .05       0  5946.1    .033       0  5952.1     .05       0
Bank Sta=4128.8,5989.1
XS Rating Curve= 0 ,0
Exp/Cntr=0.3,0.1

Type RM Length L Ch R = 1 ,6113    ,2039,2039,2039
BEGIN DESCRIPTION:
DOOLEY CREEK 3.0
END DESCRIPTION:
XS GIS Cut Line= 2
      3531552.28     10504948.88      3531135.61     10501789.14
#Sta/Elev= 30
  3293.7  396.18    3323  396.92  3361.5  397.42  3401.9  396.22  3413.4  396.94
  3433.7   395.7  3462.4  395.02  3492.6  389.91  3616.8  390.53  3694.4  391.17
  3734.7  383.11  3791.2  378.77  3906.2  374.28  3948.4  374.98  4043.3  370.92
  4242.3   368.3  4341.8  365.99    4350  365.65  4390.4  362.83  4533.9     363
  5809.6  362.82  5812.3  362.32  5815.6  362.82  5852.6  366.45  5933.6  370.91
  6024.4  375.46  6132.5  378.39  6195.3  380.29  6331.5  382.11  6480.8  384.92
#Mann= 14 ,-1 , 0
  3293.7     .16       0    3323     .05       0  3433.7     .16       0
  3616.8     .05       0  4043.3     .08       0  4242.3     .05       0
  4341.8     .07       0  4533.9     .05       0  5809.6    .033       0
  5815.6     .05       0  5933.6      .1       0  6132.5     .05       0
  6195.3      .1       0  6331.5     .05       0
Bank Sta=4350,5852.6
XS Rating Curve= 0 ,0
Exp/Cntr=0.3,0.1

Type RM Length L Ch R = 1 ,4074    ,0,0,0
BEGIN DESCRIPTION:
DOOLEY CREEK 1.0
END DESCRIPTION:
XS GIS Cut Line= 6
      3532777.09     10504337.37      3533493.25     10503729.71
      3533189.43     10502373.38      3532082.66     10500702.37
      3532104.36     10500702.37      3531670.34     10500246.65
#Sta/Elev= 30
  3451.7  389.81  3568.2  385.84    3569  385.79  3700.5  386.56  3771.9  384.26
  3807.1  381.13    3878  380.26  3899.3  379.13  3927.9  373.06  3942.2  371.61
  4069.6  363.89  7176.9  362.14  7179.7  361.64  7182.9  362.14  7186.3  363.86
    7201  368.25  7251.8  369.61  7309.3  372.59  7396.5   379.4  7540.9  385.48
    7583  384.63  7634.2  385.53  7649.2  387.42  7750.1  387.48  7816.1  389.78
  7837.1  389.09  8063.6  394.33  8268.7  397.14  8353.6  401.87  8436.2  404.67
#Mann= 6 ,-1 , 0
  3451.7     .05       0  3568.2     .16       0    3569     .05       0
  7176.9    .033       0  7182.9     .05       0  7251.8     .16       0
Bank Sta=4069.6,7186.3
XS Rating Curve= 0 ,0
Exp/Cntr=0.3,0.1

Chan Stop Cuts=-1
Use User Specified Reach Order=0
Composite Channel Slope=5