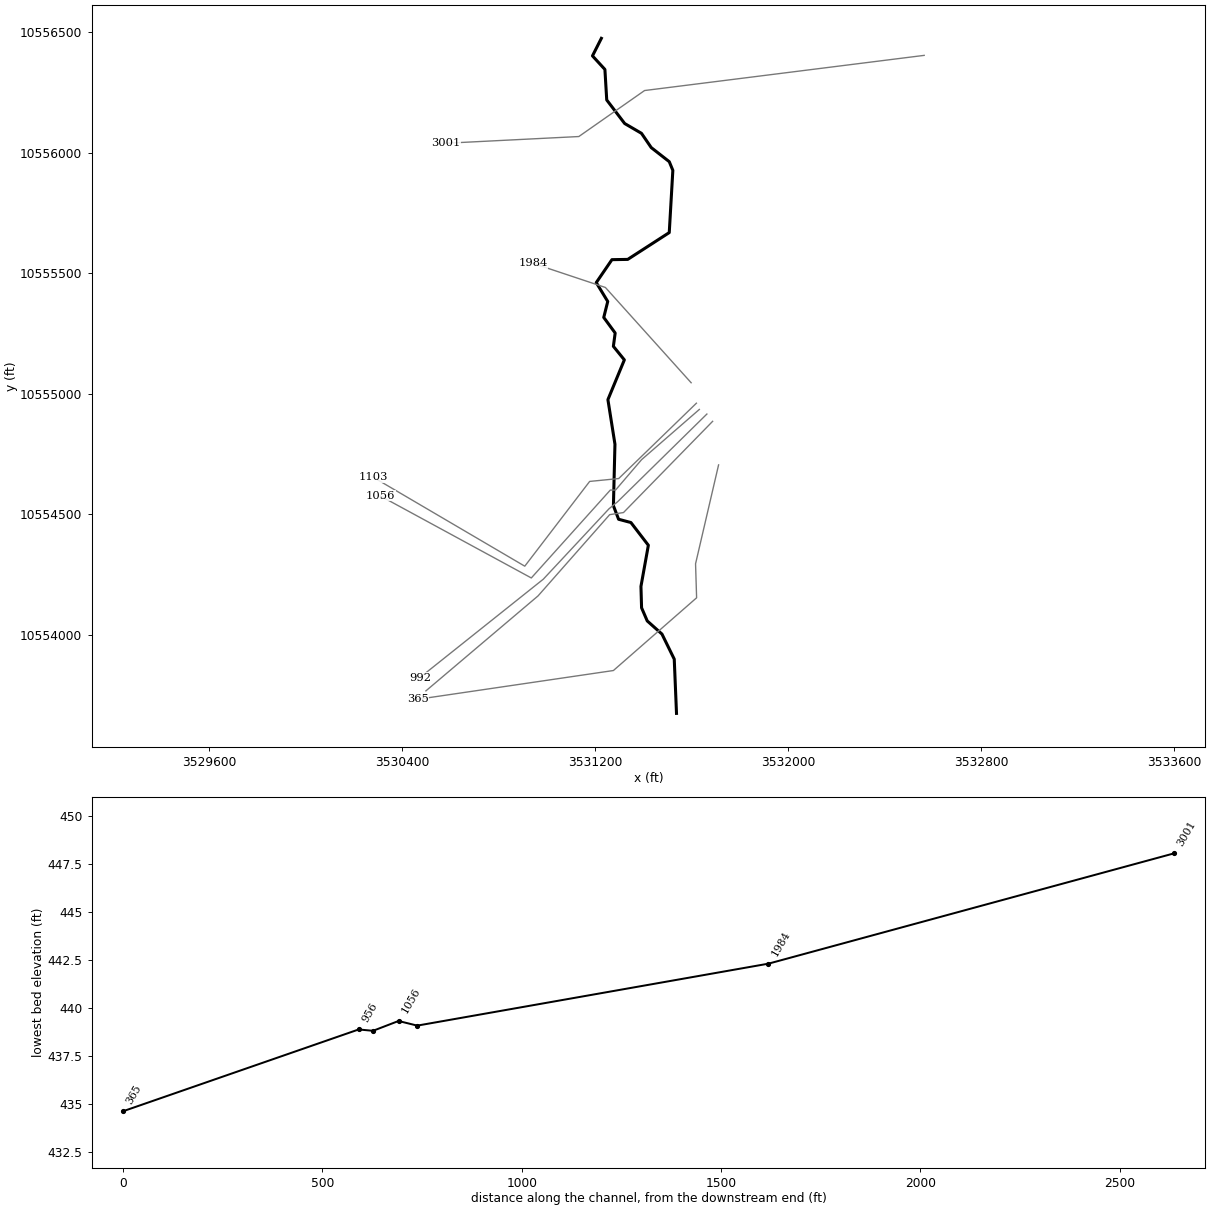
--- E FK CHAMBERS CREEK.prj (project) ---

Proj Title=E FK CHAMBERS CREEK Base Level Engineering
Current Plan=p01
Default Exp/Contr=0.3,0.1
English Units
Geom File=g01
Flow File=f01
Plan File=p01
Y Axis Title=Elevation
X Axis Title(PF)=Main Channel Distance
X Axis Title(XS)=Station
BEGIN DESCRIPTION:
E FK CHAMBERS CREEK
END DESCRIPTION:
DSS Export Rating Curves= 0
DSS Export Rating Curve Sorted= 0
DSS Export Volume Flow Curves= 0
DXF OffsetX= 0
DXF OffsetY= 0
DXF ScaleX= 1
DXF ScaleY= 10

--- E FK CHAMBERS CREEK.p01 (plan) ---

Plan Title=Multiple Run
Short Identifier=Multiple
Geom File=g01
Flow File=f01
Subcritical Flow
K Sum by GR= 0
Std Step Tol= 0.01
Critical Tol= 0.01
Num of Std Step Trials= 20
Max Error Tol= 0.3
Flow Tol Ratio= 0.001
Split Flow NTrial= 30
Split Flow Tol= 0.02
Split Flow Ratio= 0.02
Log Output Level= 0
Friction Slope Method= 1
Unsteady Friction Slope Method= 2
Unsteady Bridges Friction Slope Method= 1
Parabolic Critical Depth
Global Vel Dist=  1 , 1 , 1
Global Log Level= 0
CheckData=True
Encroach Param= -1, 0, 0, 0
BEGIN DESCRIPTION:
Multiple Run
END DESCRIPTION:

--- E FK CHAMBERS CREEK.f01 (steady flow) ---

Flow Title=Multiple
Program Version=4.10
Number of Profiles= 7
Profile Names=10-year,25-year,50-year,1pct_min,100-year,1pct_plu,500-year
River Rch & RM=E FK CHAMBERS CR,Reach-1         ,3001
     594     792     950     834    1127    1525    1581
River Rch & RM=E FK CHAMBERS CR,Reach-1         ,992
    1449    2043    2544    2310    3124    4226    4701
Boundary for River Rch & Prof#=E FK CHAMBERS CR,Reach-1         , 1
Up Type= 0
Dn Type= 1
Dn Known WS=438.92
Boundary for River Rch & Prof#=E FK CHAMBERS CR,Reach-1         , 2
Up Type= 0
Dn Type= 1
Dn Known WS=440.02
Boundary for River Rch & Prof#=E FK CHAMBERS CR,Reach-1         , 3
Up Type= 0
Dn Type= 1
Dn Known WS=440.76
Boundary for River Rch & Prof#=E FK CHAMBERS CR,Reach-1         , 4
Up Type= 0
Dn Type= 1
Dn Known WS=440.45
Boundary for River Rch & Prof#=E FK CHAMBERS CR,Reach-1         , 5
Up Type= 0
Dn Type= 1
Dn Known WS=441.52
Boundary for River Rch & Prof#=E FK CHAMBERS CR,Reach-1         , 6
Up Type= 0
Dn Type= 1
Dn Known WS=442.71
Boundary for River Rch & Prof#=E FK CHAMBERS CR,Reach-1         , 7
Up Type= 0
Dn Type= 1
Dn Known WS=443.2
DSS Import GetInterval= 0
DSS Import GetPeak= 0
DSS Import FillOption= 0

--- E FK CHAMBERS CREEK.g01 (geometry) ---

Geom Title=Existing Conditions
Program Version=4.10

River Reach=E FK CHAMBERS CR,Reach-1
Reach XY= 30
       3531225.4     10556474.94      3531188.54     10556402.16
       3531240.1     10556345.92       3531247.7     10556219.27
      3531322.11     10556121.62      3531391.77     10556080.99
      3531432.26      10556021.8      3531507.03     10555963.36
      3531521.88     10555927.36      3531506.99     10555669.25
      3531334.76     10555558.05      3531269.26     10555556.94
      3531204.23     10555461.79      3531251.86     10555383.52
      3531235.32     10555317.31      3531282.69      10555252.7
      3531275.24     10555197.49      3531320.76     10555141.29
      3531252.57     10554976.36      3531281.78     10554791.51
      3531275.41     10554536.27      3531296.88     10554480.21
      3531347.93     10554466.67      3531420.32      10554372.4
      3531389.59     10554201.57       3531392.2     10554113.03
      3531415.68     10554058.54      3531476.74     10554004.06
       3531527.7     10553900.14      3531537.07      10553675.1

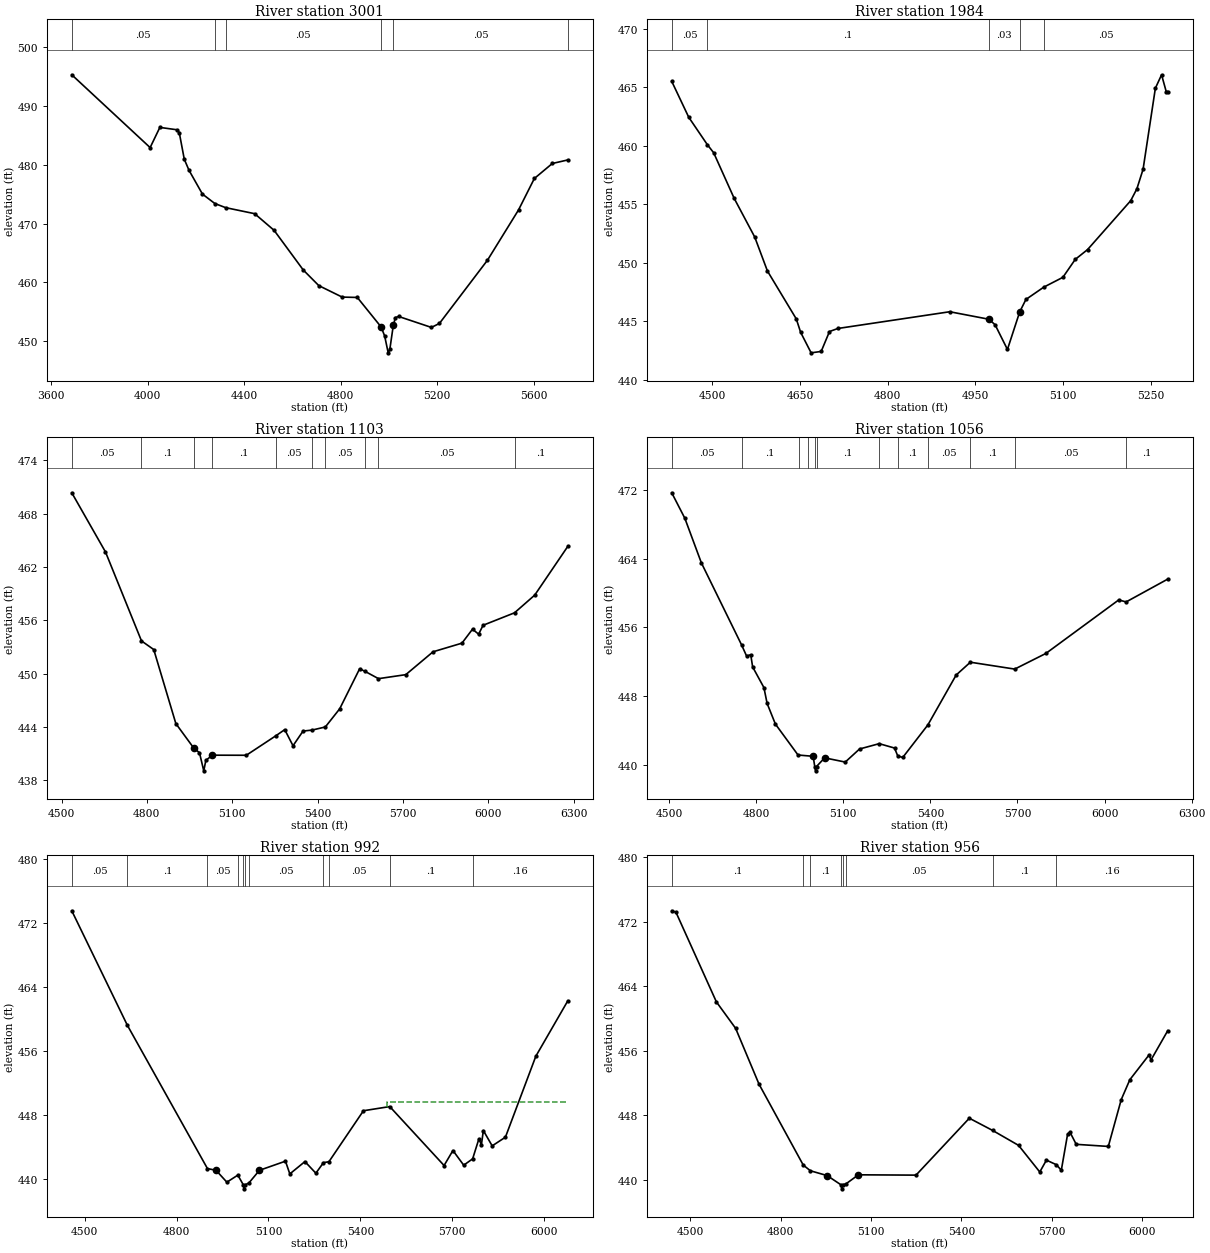
Type RM Length L Ch R = 1 ,3001    ,1017,1017,1017
BEGIN DESCRIPTION:
CHAMBERS CREEK 6.0
END DESCRIPTION:
XS GIS Cut Line= 4
      3532564.34     10556404.27      3531404.62     10556258.44
      3531131.92     10556067.64      3530578.19     10556039.69
#Sta/Elev= 30
  3685.7  495.27  4010.5   482.9  4050.8  486.33  4121.3  485.93  4131.4  485.42
  4152.1  480.92  4171.7  479.04  4227.4     475  4278.7   473.4  4323.3   472.7
  4443.9  471.67  4524.5  468.84  4645.4   462.1  4709.8  459.45  4806.7   457.5
  4869.4  457.44    4968  452.43  4982.8  450.89  4997.4  448.03  5004.1   448.6
  5018.5  452.68  5027.3  454.03  5040.7  454.21  5176.4  452.35  5209.7  453.02
    5409  463.77  5537.6   472.3  5603.3  477.65  5677.8   480.2  5741.8   480.8
#Mann= 6 ,-1 , 0
  3685.7     .05       0  4278.7      .1       0  4323.3     .05       0
    4968     .03       0  5018.5     .05       0  5741.8     .05       0
Bank Sta=4968,5018.5
XS Rating Curve= 0 ,0
Exp/Cntr=0.3,0.1

Type RM Length L Ch R = 1 ,1984    ,881,881,881
BEGIN DESCRIPTION:
CHAMBERS CREEK 4.0
END DESCRIPTION:
XS GIS Cut Line= 3
      3531597.79     10555046.44      3531242.11     10555441.64
      3530942.13     10555541.64
#Sta/Elev= 30
  4430.8  465.49  4459.9  462.42  4491.7  460.08  4502.5  459.39  4537.6  455.49
  4572.7  452.19  4594.4  449.29  4643.7   445.2  4651.2  444.05  4669.1   442.3
  4686.3  442.42  4700.5  444.12  4714.7  444.38  4906.1  445.81    4973  445.17
  4983.6   444.7  5004.7  442.59  5025.7   445.8  5036.3  446.86  5066.8  447.91
  5099.5  448.75  5120.6  450.28  5141.7  451.12  5215.5   455.3    5226  456.31
  5236.6  457.98  5257.6   464.9  5268.2  466.05  5276.1  464.62  5278.7  464.62
#Mann= 5 ,-1 , 0
  4430.8     .05       0  4491.7      .1       0    4973     .03       0
  5025.7      .1       0  5066.8     .05       0
Bank Sta=4973,5025.7
XS Rating Curve= 0 ,0
Exp/Cntr=0.3,0.1

Type RM Length L Ch R = 1 ,1103    ,47,47,47
BEGIN DESCRIPTION:
CHAMBERS CREEK 3.0
END DESCRIPTION:
XS GIS Cut Line= 5
      3531619.59     10554961.61      3531297.29     10554649.08
      3531176.85     10554637.14      3530907.75     10554285.58
      3530277.32     10554655.59
#Sta/Elev= 30
    4536  470.33  4654.5  463.68  4781.1  453.68  4824.2  452.71  4901.9  444.39
  4965.5  441.61  4984.9  441.12    5000  439.08  5007.4  440.26  5030.3  440.84
  5149.6  440.83  5253.4  443.02  5284.7  443.71  5313.8   441.9  5349.1  443.55
  5380.7  443.66  5427.4  444.01  5477.9  446.05    5548  450.55  5566.9  450.26
  5614.3  449.44  5710.3  449.89  5806.1  452.46  5907.7  453.43  5944.8     455
  5966.3  454.44    5982  455.44  6092.5  456.84  6163.6  458.83  6279.7   464.3
#Mann= 10 ,-1 , 0
    4536     .05       0  4781.1      .1       0  4965.5     .03       0
  5030.3      .1       0  5253.4     .05       0  5380.7      .1       0
  5427.4     .05       0  5566.9      .1       0  5614.3     .05       0
  6092.5      .1       0
Bank Sta=4965.5,5030.3
XS Rating Curve= 0 ,0
Exp/Cntr=0.3,0.1

Type RM Length L Ch R = 1 ,1056    ,64,64,64
BEGIN DESCRIPTION:
CHAMBERS CREEK 3.01
END DESCRIPTION:
XS GIS Cut Line= 6
      3531631.79     10554935.73      3531392.23     10554727.42
      3531284.27     10554601.34      3531262.57     10554601.34
      3530934.88     10554236.75       3530308.5     10554577.03
#Sta/Elev= 30
  4509.3  471.65  4554.4  468.69  4611.4   463.5  4749.6  453.98  4767.1  452.67
  4781.4  452.82    4788   451.4  4826.8     449  4837.8  447.16  4866.3  444.76
  4944.3  441.16  4996.3  441.01  5001.9  439.82  5004.7  439.32  5007.9  439.82
  5035.9  440.83  5106.9  440.34  5156.2  441.86  5223.9  442.48  5276.6  441.97
  5287.9  441.04    5305  440.88  5391.5  444.66  5488.9  450.46  5537.8  451.95
  5690.6  451.15  5797.9  452.97  6048.7  459.19  6074.3  458.96  6217.5  461.61
#Mann= 12 ,-1 , 0
  4509.3     .05       0  4749.6      .1       0  4946.6     .05       0
    4980      .1       0  5001.9     .07       0  5007.9      .1       0
  5223.9     .05       0  5287.9      .1       0  5391.5     .05       0
  5537.8      .1       0  5690.6     .05       0  6074.3      .1       0
Bank Sta=4996.3,5035.9
XS Rating Curve= 0 ,0
Exp/Cntr=0.3,0.1

Type RM Length L Ch R = 1 ,992     ,36,36,36
BEGIN DESCRIPTION:
CHAMBERS CREEK 1.0
END DESCRIPTION:
XS GIS Cut Line= 5
       3531663.1     10554916.65      3531293.27     10554553.33
      3531256.82     10554523.39      3530984.68     10554231.72
      3530472.99      10553823.8
#Sta/Elev= 30
    4458  473.49  4639.4  459.21  4900.8  441.34  4928.9  441.12  4964.2  439.64
    5000  440.52  5017.9  439.31  5020.6  438.81  5023.9  439.31  5036.1  439.54
  5070.5  441.12  5155.5  442.26  5169.7  440.67    5219  442.21  5254.7  440.76
  5279.6  442.08  5297.3  442.19    5410  448.55  5495.9  449.07  5673.2  441.72
  5702.1  443.59  5737.3  441.76  5766.4  442.55  5786.9  445.05    5795   444.3
  5801.4  446.08  5830.2  444.17  5873.4  445.25  5972.7  455.35  6076.9  462.25
#Mann= 11 ,-1 , 0
    4458     .05       0  4639.4      .1       0  4900.8     .05       0
    5000      .1       0  5017.9    .035       0  5023.9      .1       0
  5036.1     .05       0  5279.6      .1       0  5297.3     .05       0
  5495.9      .1       0  5766.4     .16       0
#XS Ineff= 2 , 0
                         5485.82          449.63
Permanent Ineff=
       F       F
Bank Sta=4928.9,5070.5
XS Rating Curve= 0 ,0
Exp/Cntr=0.3,0.1

Type RM Length L Ch R = 1 ,956     ,591,591,591
BEGIN DESCRIPTION:
CHAMBERS CREEK 1.011
END DESCRIPTION:
XS GIS Cut Line= 5
      3531686.97     10554886.49      3531317.18     10554508.02
      3531259.89     10554499.34      3530963.02     10554162.54
      3530497.73     10553768.43
#Sta/Elev= 30
  4438.9  473.37  4452.8   473.2  4587.1  462.07  4650.9  458.79  4728.6  451.86
  4875.3  441.83  4899.1  441.12  4954.9  440.52  5000.5  439.38  5003.3  438.88
  5006.5  439.38  5016.8  439.49  5058.3  440.62  5249.5  440.58  5426.4  447.64
  5503.9  446.12  5589.9  444.27  5660.2  440.97  5682.2  442.44  5715.4  441.87
  5731.6  441.18  5752.5  445.66  5760.2  445.92  5781.1   444.4  5887.6  444.14
  5930.5  449.95  5959.1  452.42  6022.8  455.49  6029.3  454.87  6084.7  458.49
#Mann= 8 ,-1 , 0
  4438.9      .1       0  4875.3     .05       0  4899.1      .1       0
  5000.5     .07       0  5006.5      .1       0  5016.8     .05       0
  5503.9      .1       0  5715.4     .16       0
#XS Ineff= 2 , 0
                         5427.59          447.48
Permanent Ineff=
       F       F
Bank Sta=4954.9,5058.3
XS Rating Curve= 0 ,0
Exp/Cntr=0.3,0.1

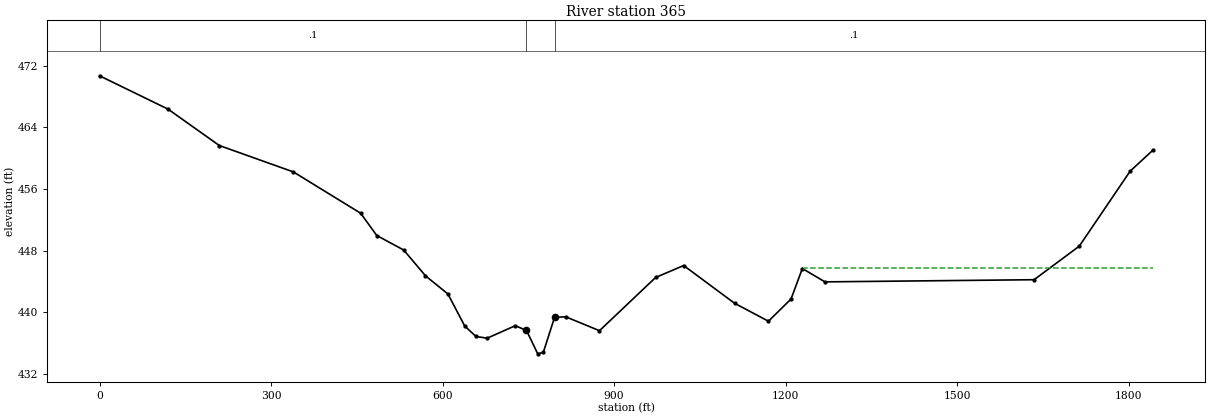
Type RM Length L Ch R = 1 ,365     ,0,0,0
XS GIS Cut Line= 5
     3531711.588     10554705.69     3531616.102    10554295.533
     3531620.442    10554154.474      3531275.39    10553852.825
     3530463.758    10553733.467
#Sta/Elev= 30
       0  470.68  119.72  466.36  209.51  461.64   339.2  458.21  456.67  452.86
  484.91  449.97  531.98  448.09  570.04  444.75   609.3  442.39  638.75  438.23
  658.39  436.88  678.02  436.66   727.1  438.28  746.73  437.66  766.37  434.63
  776.18  434.83  795.82  439.36  815.45  439.43  874.35  437.63  972.52  444.53
  1021.6  446.08 1110.55  441.19 1169.86  438.86 1209.39  441.74 1229.16  445.69
 1268.69  443.96  1634.4  444.24 1713.47  448.59 1802.42  458.31 1841.96  461.02
#Mann= 3 , 0 , 0
       0      .1       0  746.73     .05       0  795.82      .1       0
#XS Ineff= 2 , 0
                         1232.65          445.71
Permanent Ineff=
       F       F
Bank Sta=746.73,795.82
XS Rating Curve= 0 ,0
Exp/Cntr=0.3,0.1

Chan Stop Cuts=-1
Use User Specified Reach Order=0
Composite Channel Slope=5