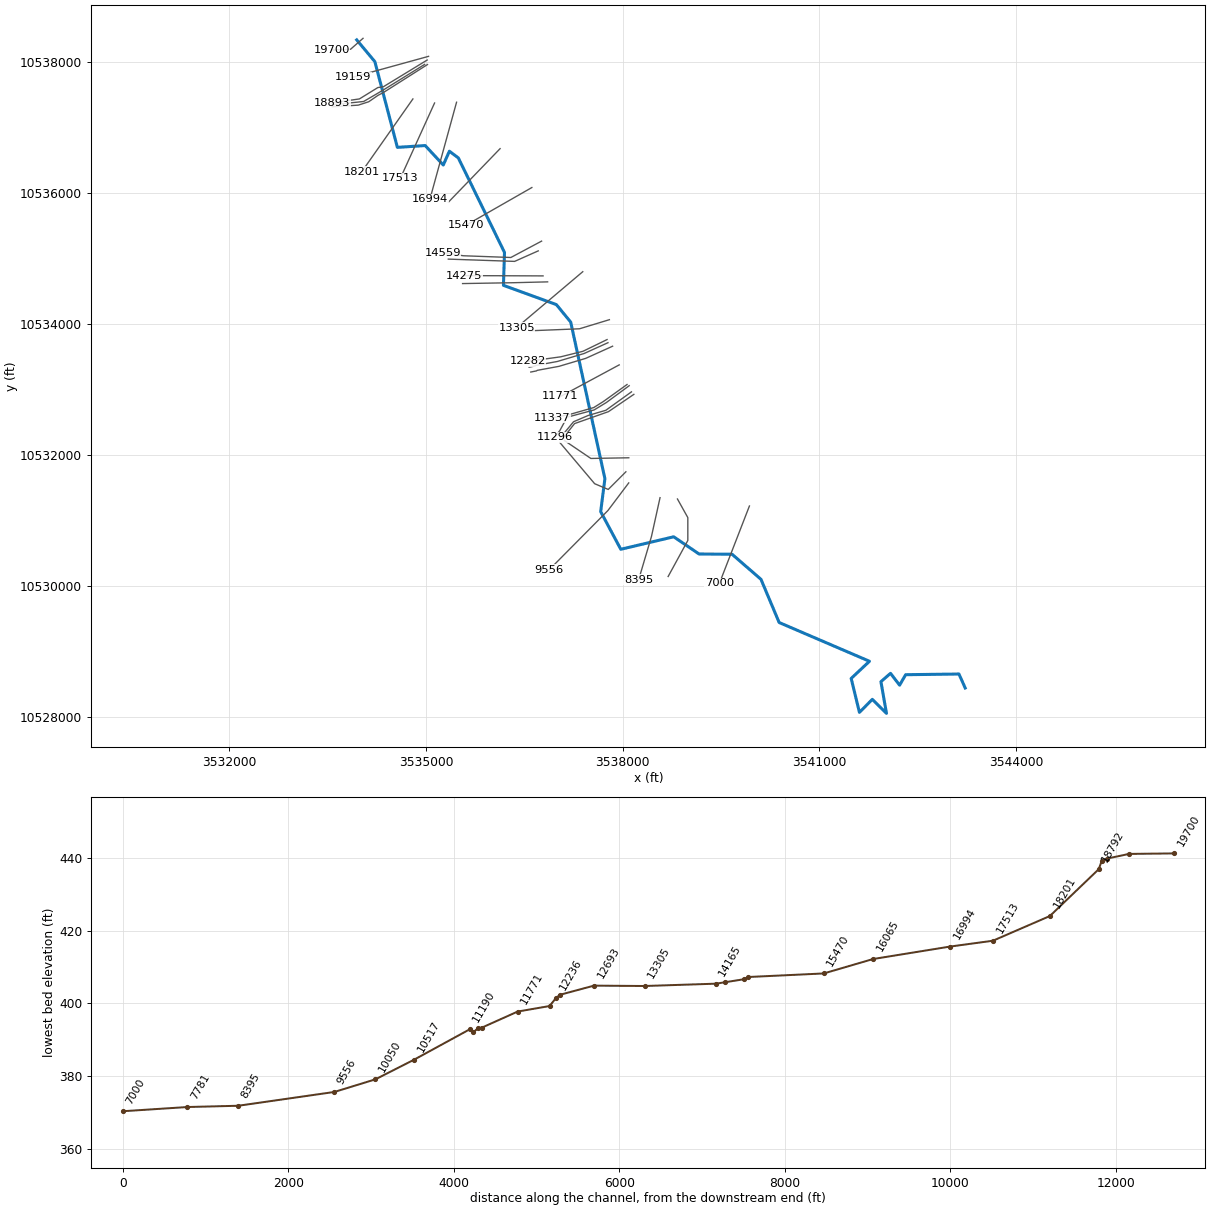
--- EZELL BRANCH.prj (project) ---

Proj Title=EZELL BRANCH Base Level Engineering
Current Plan=p01
Default Exp/Contr=0.3,0.1
English Units
Geom File=g01
Flow File=f01
Plan File=p01
BEGIN DESCRIPTION:
EZELL BRANCH
END DESCRIPTION:

--- EZELL BRANCH.p01 (plan) ---

Plan Title=Multiple Run
Short Identifier=Multiple
Geom File=g01
Flow File=f01
Subcritical Flow
K Sum by GR= 0
Std Step Tol= 0.01
Critical Tol= 0.01
Num of Std Step Trials= 20
Max Error Tol= 0.3
Flow Tol Ratio= 0.001
Split Flow NTrial= 30
Split Flow Tol= 0.02
Split Flow Ratio= 0.02
Log Output Level= 0
Friction Slope Method= 1
Unsteady Friction Slope Method= 2
Unsteady Bridges Friction Slope Method= 1
Parabolic Critical Depth
Global Vel Dist=  1 , 1 , 1
Global Log Level= 0
CheckData=True
Encroach Param= -1, 0, 0, 0
BEGIN DESCRIPTION:
Multiple Run
END DESCRIPTION:

--- EZELL BRANCH.f01 (steady flow) ---

Flow Title=Multiple
Number of Profiles=7
Profile Names=10-year,25-year,50-year,1pct_min,100-year,1pct_plu,500-year
River Rch & RM= EZELL BRANCH,Reach-1,19700
     737     992    1198    1056    1429    1932    2024
River Rch & RM= EZELL BRANCH,Reach-1,14275
     914    1246    1518    1350    1825    2468    2629
River Rch & RM= EZELL BRANCH,Reach-1,11190
     966    1324    1618    1443    1951    2638    2829
River Rch & RM= EZELL BRANCH,Reach-1,9556
    1657    2338    2913    2644    3575    4835    5374
River Rch & RM= EZELL BRANCH,Reach-1,7000
    1829    2575    3202    2898    3919    5300    5857
Boundary for River Rch & Prof#=EZELL BRANCH,Reach-1,1
Up Type=0
Dn Type=3
Dn Slope=0.005
Boundary for River Rch & Prof#=EZELL BRANCH,Reach-1,2
Up Type=0
Dn Type=3
Dn Slope=0.005
Boundary for River Rch & Prof#=EZELL BRANCH,Reach-1,3
Up Type=0
Dn Type=3
Dn Slope=0.005
Boundary for River Rch & Prof#=EZELL BRANCH,Reach-1,4
Up Type=0
Dn Type=3
Dn Slope=0.005
Boundary for River Rch & Prof#=EZELL BRANCH,Reach-1,5
Up Type=0
Dn Type=3
Dn Slope=0.005
Boundary for River Rch & Prof#=EZELL BRANCH,Reach-1,6
Up Type=0
Dn Type=3
Dn Slope=0.005
Boundary for River Rch & Prof#=EZELL BRANCH,Reach-1,7
Up Type=0
Dn Type=3
Dn Slope=0.005

--- EZELL BRANCH.g01 (geometry) ---

Geom Title=Existing Conditions

River Reach=EZELL BRANCH,Reach-1
Reach XY= 30
      3533942.11     10538331.86      3534218.59     10538000.25
      3534562.11     10536691.64      3534986.29     10536719.29
      3535262.12     10536422.33      3535355.29     10536632.85
      3535491.53     10536530.97      3536195.92     10535088.46
      3536179.92     10534585.75      3536987.24     10534291.62
      3537205.69     10534024.57      3537727.56     10531634.89
      3537663.01     10531132.06      3537969.63     10530557.06
      3538777.05     10530747.73      3539163.61     10530485.00
      3539667.04     10530481.49      3540107.98     10530098.69
      3540385.17     10529439.34      3541762.92     10528847.89
      3541483.83     10528585.65      3541609.88     10528067.69
      3541806.28     10528266.26      3542022.21     10528052.50
      3541937.57     10528536.44      3542083.84     10528663.61
      3542222.30     10528483.05      3542314.74     10528642.77
      3543127.68     10528653.19      3543222.77     10528440.37

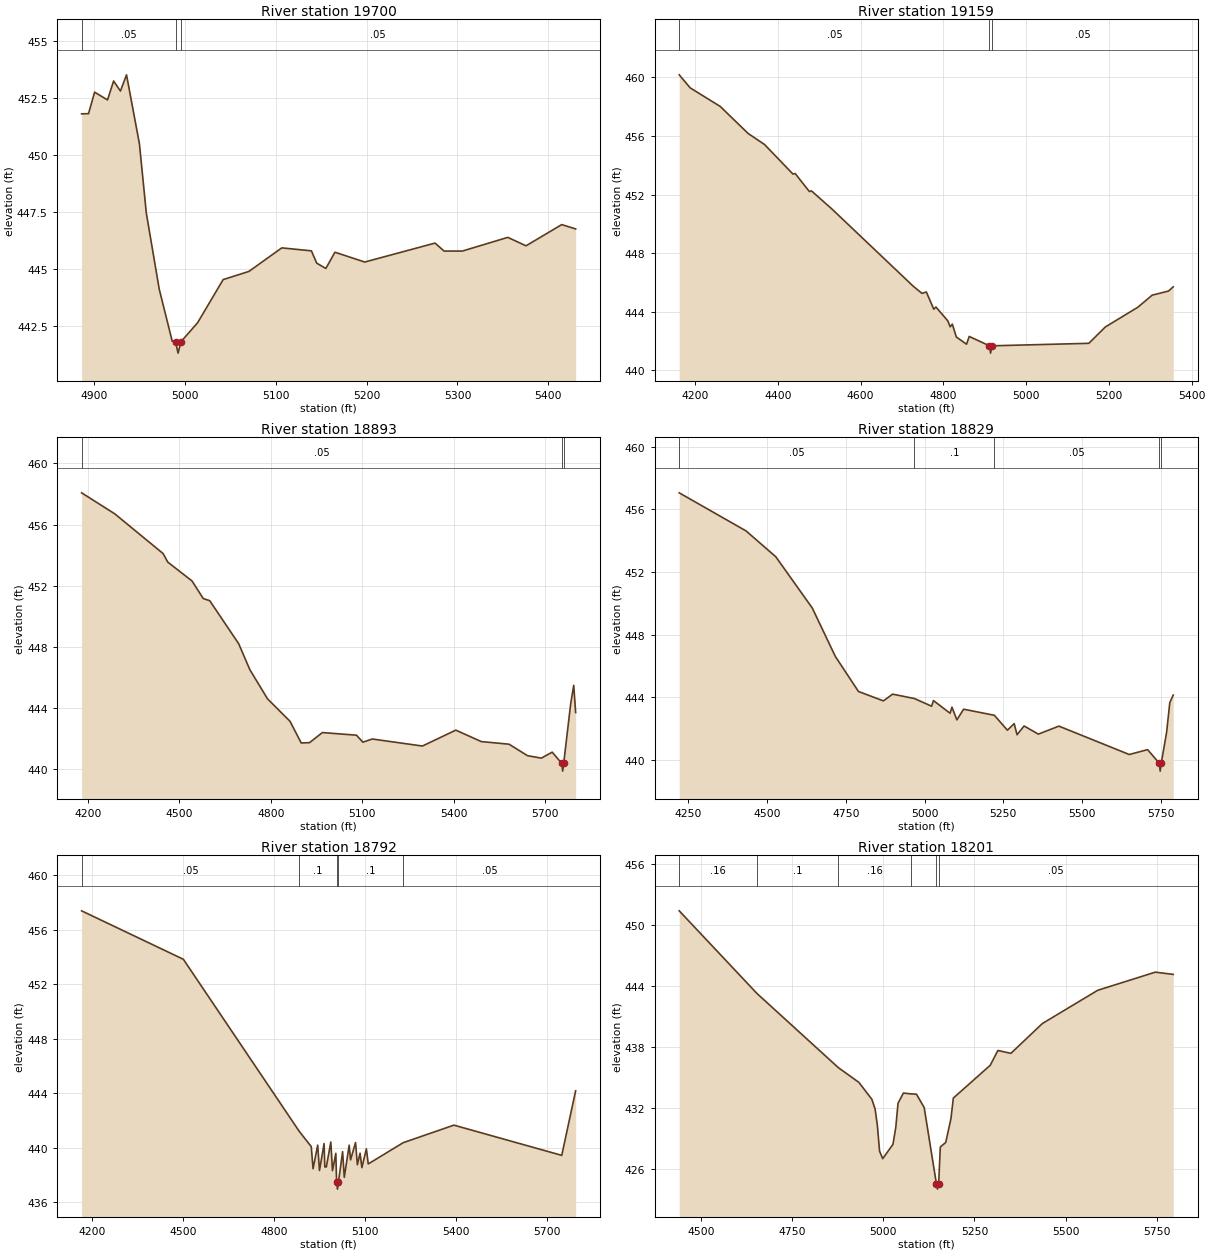
Type RM Length L Ch R = 1,19700,541,541,541
BEGIN DESCRIPTION:
EZELL BRANCH 33.01
END DESCRIPTION:
XS GIS Cut Line= 3
      3534038.07     10538355.85      3533847.95     10538189.17
      3533557.58     10538176.15
#Sta/Elev= 30
  4886.5  451.79  4894.1  451.80  4900.8  452.74  4915.0  452.40  4921.7  453.23
  4929.2  452.79  4935.9  453.50  4950.1  450.48  4957.7  447.44  4971.9  444.11
  4986.2  441.83  4989.8  441.81  4992.6  441.31  4995.8  441.81  5014.1  442.64
  5042.2  444.53  5070.6  444.89  5106.7  445.92  5139.3  445.79  5145.2  445.25
  5155.2  445.02  5165.2  445.73  5198.0  445.30  5275.3  446.13  5285.3  445.78
  5305.3  445.78  5355.4  446.38  5375.4  446.01  5414.7  446.94  5430.0  446.75
#Mann=3,-1,0
  4886.5    0.05       0  4989.8    0.03       0  4995.8    0.05       0
Bank Sta=4989.8,4995.8
Exp/Cntr=0.3,0.1

Type RM Length L Ch R = 1,19159,266,266,266
BEGIN DESCRIPTION:
EZELL BRANCH 33.0
END DESCRIPTION:
XS GIS Cut Line= 2
      3535037.65     10538081.04      3533886.88     10537763.40
#Sta/Elev= 30
  4161.7  460.18  4188.2  459.29  4260.8  458.02  4328.4  456.17  4367.9  455.42
  4436.6  453.40  4441.8  453.44  4476.2  452.21  4481.4  452.25  4530.5  451.02
  4727.6  445.73  4748.4  445.25  4758.8  445.35  4776.9  444.17  4782.1  444.32
  4810.6  443.38  4816.5  442.97  4821.7  443.15  4831.4  442.27  4856.0  441.78
  4862.5  442.31  4911.4  441.67  4914.1  441.17  4917.4  441.67  5151.6  441.84
  5191.1  442.95  5270.2  444.31  5304.6  445.13  5344.1  445.41  5355.5  445.70
#Mann=3,-1,0
  4161.7    0.05       0  4911.4   0.033       0  4917.4    0.05       0
Bank Sta=4911.4,4917.4
Exp/Cntr=0.3,0.1

Type RM Length L Ch R = 1,18893,64,64,64
BEGIN DESCRIPTION:
EZELL BRANCH 32.01
END DESCRIPTION:
XS GIS Cut Line= 5
      3535016.98     10538024.83      3534348.58     10537616.85
      3534264.52     10537604.69      3533983.27     10537431.08
      3533565.98     10537370.48
#Sta/Elev= 30
  4179.1  458.08  4287.6  456.71  4446.4  454.11  4461.8  453.55  4541.2  452.32
  4578.0  451.17  4599.3  451.03  4694.2  448.22  4730.9  446.52  4789.0  444.61
  4862.5  443.15  4899.3  441.73  4926.5  441.75  4968.7  442.41  5080.4  442.24
  5101.7  441.78  5132.2  441.99  5296.8  441.53  5406.3  442.57  5490.0  441.82
  5580.9  441.65  5641.5  440.90  5686.9  440.74  5722.4  441.13  5754.1  440.39
  5756.8  439.89  5760.1  440.39  5783.0  444.28  5793.1  445.50  5799.3  443.72
#Mann=3,-1,0
  4179.1    0.05       0  5754.1   0.033       0  5760.1    0.05       0
Bank Sta=5754.1,5760.1
Exp/Cntr=0.3,0.1

Type RM Length L Ch R = 1,18829,37,37,37
BEGIN DESCRIPTION:
EZELL BRANCH 32.0
END DESCRIPTION:
XS GIS Cut Line= 4
      3534977.98     10537958.06      3534339.10     10537562.23
      3534047.80     10537392.02      3533571.20     10537341.67
#Sta/Elev= 30
  4221.2  457.05  4433.4  454.62  4527.9  452.97  4643.7  449.70  4716.9  446.61
  4790.2  444.38  4869.3  443.78  4898.6  444.21  4967.8  443.93  5022.4  443.44
  5028.2  443.80  5081.1  442.99  5086.9  443.38  5102.6  442.57  5124.1  443.25
  5221.7  442.86  5263.0  441.91  5284.5  442.33  5293.6  441.62  5315.9  442.18
  5361.2  441.66  5426.5  442.17  5649.8  440.36  5708.0  440.67  5745.3  439.80
  5748.0  439.30  5751.3  439.80  5768.4  441.78  5778.4  443.66  5789.4  444.15
#Mann=5,-1,0
  4221.2    0.05       0  4967.8     0.1       0  5221.7    0.05       0
  5745.3    0.07       0  5751.3    0.05       0
Bank Sta=5745.3,5751.3
Exp/Cntr=0.3,0.1

Type RM Length L Ch R = 1,18792,591,591,591
BEGIN DESCRIPTION:
EZELL BRANCH 32.02
END DESCRIPTION:
XS GIS Cut Line= 6
      3535021.47     10537955.91      3534343.08     10537524.92
      3534268.86     10537487.16      3534125.64     10537388.20
      3533965.48     10537336.12      3533566.43     10537311.42
#Sta/Elev= 30
  4165.9  457.40  4501.5  453.84  4883.8  441.20  4923.3  440.08  4929.2  438.46
  4944.5  440.19  4950.4  438.33  4965.6  440.31  4968.0  438.59  4973.0  438.59
  4987.7  440.42  4993.3  438.32  5004.3  439.59  5006.9  437.46  5009.7  436.96
  5012.9  437.46  5026.6  439.71  5032.2  437.83  5048.3  440.19  5052.9  439.11
  5069.3  440.38  5075.4  438.75  5084.2  439.60  5090.2  438.54  5105.1  439.92
  5111.2  438.81  5226.4  440.37  5393.7  441.66  5749.4  439.44  5795.2  444.18
#Mann=5,-1,0
  4165.9    0.05       0  4883.8     0.1       0  5006.9    0.07       0
  5012.9     0.1       0  5226.4    0.05       0
Bank Sta=5006.9,5012.9
Exp/Cntr=0.3,0.1

Type RM Length L Ch R = 1,18201,688,688,688
BEGIN DESCRIPTION:
EZELL BRANCH 31.0
END DESCRIPTION:
XS GIS Cut Line= 2
      3534798.95     10537430.85      3534021.20     10536323.25
#Sta/Elev= 30
  4441.1  451.37  4654.0  443.26  4876.9  435.98  4933.3  434.53  4969.0  432.86
  4977.7  431.92  4983.8  430.36  4990.0  427.77  4998.6  427.04  5026.7  428.45
  5034.4  430.11  5040.5  432.48  5055.3  433.48  5076.0  433.40  5091.0  433.37
  5112.2  432.06  5145.8  424.55  5148.6  424.05  5151.8  424.55  5156.4  428.19
  5171.2  428.63  5185.5  430.97  5192.1  432.99  5293.2  436.21  5314.1  437.66
  5349.8  437.38  5436.1  440.31  5587.7  443.57  5745.4  445.35  5794.5  445.13
#Mann=6,-1,0
  4441.1    0.16       0  4654.0     0.1       0  4876.9    0.16       0
  5076.0    0.05       0  5145.8    0.07       0  5151.8    0.05       0
Bank Sta=5145.8,5151.8
Exp/Cntr=0.3,0.1

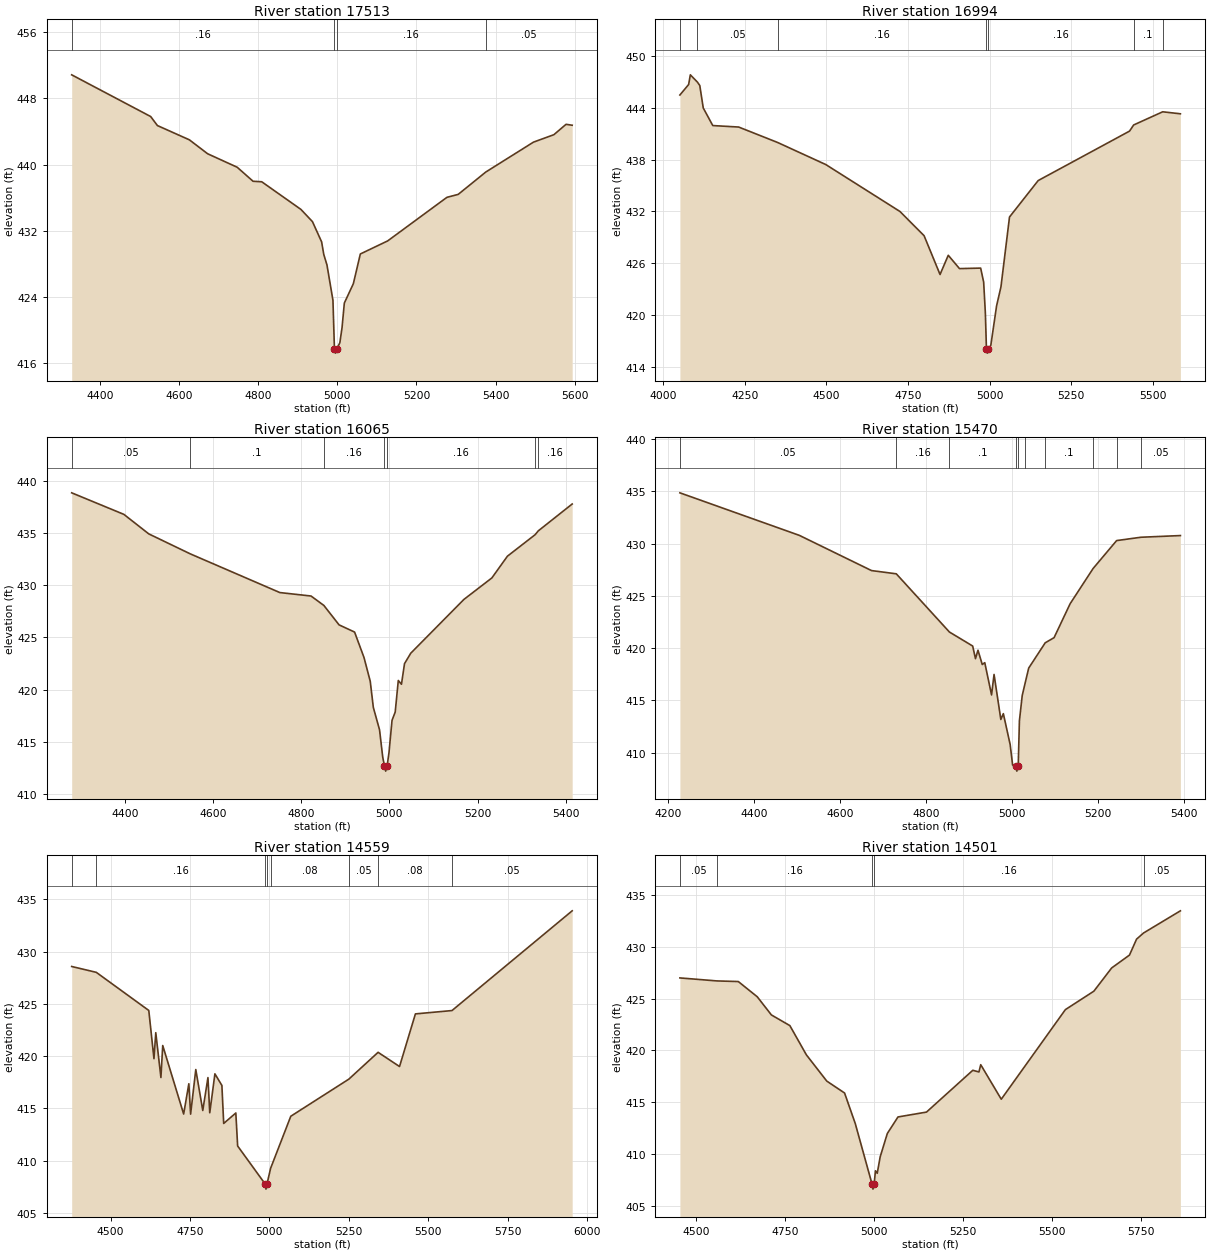
Type RM Length L Ch R = 1,17513,519,519,519
BEGIN DESCRIPTION:
EZELL BRANCH 30.0
END DESCRIPTION:
XS GIS Cut Line= 2
      3535129.29     10537368.85      3534606.73     10536217.49
#Sta/Elev= 30
  4329.2  450.82  4528.7  445.79  4545.8  444.70  4626.5  442.98  4672.6  441.30
  4747.4  439.67  4787.4  437.98  4809.3  437.92  4908.2  434.59  4937.5  433.11
  4960.6  430.67  4966.1  429.14  4974.1  427.89  4989.2  423.63  4993.0  417.75
  4995.8  417.25  4999.0  417.75  5006.7  418.51  5012.2  420.33  5018.0  423.29
  5040.8  425.63  5058.4  429.21  5127.6  430.79  5277.1  436.04  5305.7  436.40
  5375.5  439.10  5495.8  442.70  5547.4  443.60  5578.1  444.85  5593.6  444.74
#Mann=4,-1,0
  4329.2    0.16       0  4993.0    0.07       0  4999.0    0.16       0
  5375.5    0.05       0
Bank Sta=4993,4999
Exp/Cntr=0.3,0.1

Type RM Length L Ch R = 1,16994,929,929,929
BEGIN DESCRIPTION:
EZELL BRANCH 28.0
END DESCRIPTION:
XS GIS Cut Line= 2
      3535464.73     10537380.50      3535058.49     10535901.38
#Sta/Elev= 30
  4051.0  445.45  4077.8  446.66  4083.0  447.78  4104.7  446.94  4112.0  446.54
  4122.6  443.95  4151.8  441.92  4231.1  441.75  4350.3  439.97  4498.0  437.42
  4725.4  432.00  4799.4  429.20  4848.3  424.72  4873.5  426.94  4907.9  425.40
  4972.8  425.46  4982.0  423.83  4987.2  420.26  4990.5  416.14  4993.3  415.64
  4996.5  416.14  5003.9  416.54  5021.6  421.10  5035.0  423.30  5061.2  431.36
  5149.1  435.57  5429.1  441.28  5441.7  441.99  5530.7  443.51  5584.9  443.28
#Mann=7,-1,0
  4051.0     0.1       0  4104.7    0.05       0  4350.3    0.16       0
  4990.5    0.07       0  4996.5    0.16       0  5441.7     0.1       0
  5530.7    0.05       0
Bank Sta=4990.5,4996.5
Exp/Cntr=0.3,0.1

Type RM Length L Ch R = 1,16065,595,595,595
BEGIN DESCRIPTION:
EZELL BRANCH 26.0
END DESCRIPTION:
XS GIS Cut Line= 2
      3536128.81     10536672.20      3535340.75     10535855.53
#Sta/Elev= 30
  4279.8  438.83  4398.1  436.77  4454.7  434.90  4548.8  432.99  4751.8  429.29
  4822.5  428.96  4851.6  428.06  4886.1  426.20  4921.3  425.51  4942.7  423.07
  4956.8  420.80  4963.8  418.30  4977.9  416.16  4985.1  413.55  4989.1  412.71
  4991.8  412.21  4995.1  412.71  4999.3  413.98  5006.2  417.07  5013.4  417.86
  5020.4  420.88  5027.6  420.52  5034.5  422.49  5048.7  423.49  5169.1  428.63
  5232.6  430.69  5267.9  432.77  5330.8  434.83  5337.8  435.19  5414.7  437.76
#Mann=7,-1,0
  4279.8    0.05       0  4548.8     0.1       0  4851.6    0.16       0
  4989.1    0.07       0  4995.1    0.16       0  5330.8     0.1       0
  5337.8    0.16       0
Bank Sta=4989.1,4995.1
Exp/Cntr=0.3,0.1

Type RM Length L Ch R = 1,15470,911,911,911
BEGIN DESCRIPTION:
EZELL BRANCH 25.0
END DESCRIPTION:
XS GIS Cut Line= 2
      3536613.20     10536078.45      3535602.80     10535500.33
#Sta/Elev= 30
  4226.8  434.87  4504.6  430.80  4672.5  427.43  4730.1  427.12  4853.7  421.55
  4907.8  420.21  4914.3  419.00  4920.1  419.81  4930.1  418.44  4935.9  418.62
  4951.7  415.53  4957.5  417.49  4973.3  413.18  4979.1  413.74  4994.9  410.80
  5000.7  408.82  5007.7  408.74  5010.5  408.24  5013.7  408.74  5016.5  413.06
  5023.0  415.47  5030.4  416.77  5038.1  418.10  5076.5  420.52  5097.1  421.01
  5134.5  424.26  5187.9  427.63  5242.6  430.30  5299.3  430.62  5390.9  430.78
#Mann=10,-1,0
  4226.8    0.05       0  4730.1    0.16       0  4853.7     0.1       0
  5007.7    0.07       0  5013.7     0.1       0  5030.4    0.16       0
  5076.5     0.1       0  5187.9    0.05       0  5242.6     0.1       0
  5299.3    0.05       0
Bank Sta=5007.7,5013.7
Exp/Cntr=0.3,0.1

Type RM Length L Ch R = 1,14559,58,58,58
BEGIN DESCRIPTION:
EZELL BRANCH 24.0
END DESCRIPTION:
XS GIS Cut Line= 4
      3536761.64     10535260.74      3536292.86     10535010.73
      3535567.58     10535037.30      3535252.24     10535085.82
#Sta/Elev= 30
  4377.5  428.58  4454.9  428.02  4620.3  424.37  4636.6  419.75  4642.3  422.24
  4658.5  417.95  4664.2  421.01  4730.1  414.45  4746.4  417.35  4752.0  414.44
  4768.3  418.71  4790.3  414.79  4806.6  417.94  4812.3  414.57  4828.5  418.30
  4850.5  417.19  4856.2  413.55  4894.4  414.55  4900.1  411.39  4986.6  407.76
  4989.3  407.26  4992.6  407.76  5004.0  409.26  5067.5  414.24  5250.2  417.79
  5342.4  420.36  5409.9  419.00  5459.9  424.04  5575.1  424.36  5953.6  433.91
#Mann=8,-1,0
  4377.5    0.05       0  4454.9    0.16       0  4986.6    0.07       0
  4992.6    0.16       0  5004.0    0.08       0  5250.2    0.05       0
  5342.4    0.08       0  5575.1    0.05       0
Bank Sta=4986.6,4992.6
Exp/Cntr=0.3,0.1

Type RM Length L Ch R = 1,14501,226,226,226
BEGIN DESCRIPTION:
EZELL BRANCH 23.0
END DESCRIPTION:
XS GIS Cut Line= 3
      3536710.64     10535111.86      3536350.37     10534951.26
      3535339.11     10534985.98
#Sta/Elev= 30
  4454.8  427.00  4558.4  426.71  4618.9  426.65  4672.2  425.18  4711.9  423.43
  4763.8  422.40  4810.2  419.58  4867.5  417.05  4917.5  415.90  4947.6  412.95
  4994.6  407.13  4997.3  406.63  5000.6  407.13  5004.3  408.40  5009.3  408.16
  5017.6  409.75  5037.6  411.99  5067.6  413.59  5147.7  414.06  5277.8  418.09
  5295.1  417.93  5300.1  418.63  5357.8  415.30  5537.9  423.94  5618.0  425.72
  5668.0  427.96  5718.0  429.20  5738.0  430.74  5757.5  431.33  5861.1  433.47
#Mann=5,-1,0
  4454.8    0.05       0  4558.4    0.16       0  4994.6    0.07       0
  5000.6    0.16       0  5757.5    0.05       0
Bank Sta=4994.6,5000.6
Exp/Cntr=0.3,0.1

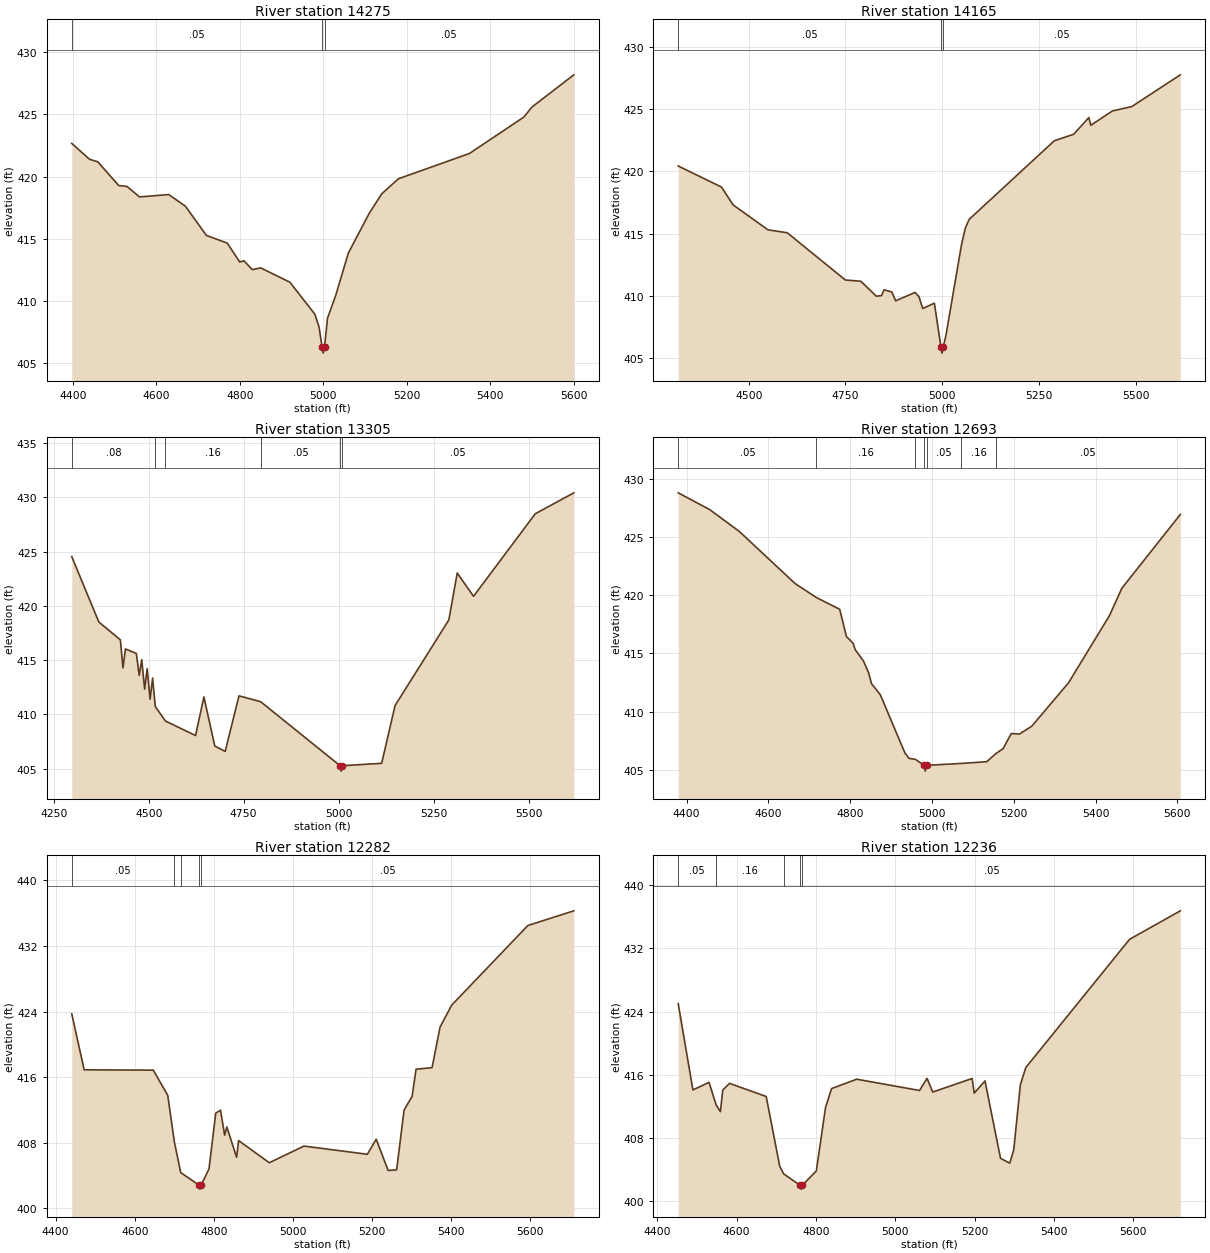
Type RM Length L Ch R = 1,14275,110,110,110
BEGIN DESCRIPTION:
EZELL BRANCH 22.0
END DESCRIPTION:
XS GIS Cut Line= 2
      3536784.40     10534729.91      3535582.11     10534734.25
#Sta/Elev= 30
  4397.8  422.66  4440.1  421.39  4460.1  421.18  4510.1  419.28  4530.1  419.20
  4560.1  418.36  4630.1  418.55  4670.1  417.61  4720.1  415.27  4770.1  414.65
  4800.1  413.13  4810.1  413.23  4830.1  412.52  4850.1  412.66  4920.1  411.51
  4980.1  408.93  4990.1  407.89  4997.1  406.31  4999.9  405.81  5003.1  406.31
  5010.1  408.60  5030.1  410.47  5060.1  413.85  5110.1  417.04  5140.1  418.61
  5180.1  419.82  5350.1  421.85  5480.1  424.77  5500.1  425.59  5600.1  428.17
#Mann=3,-1,0
  4397.8    0.05       0  4997.1    0.03       0  5003.1    0.05       0
Bank Sta=4997.1,5003.1
Exp/Cntr=0.3,0.1

Type RM Length L Ch R = 1,14165,860,860,860
BEGIN DESCRIPTION:
EZELL BRANCH 21.0
END DESCRIPTION:
XS GIS Cut Line= 3
      3536853.84     10534638.76      3536328.67     10534625.74
      3535556.61     10534612.73
#Sta/Elev= 30
  4317.9  420.44  4429.7  418.75  4459.7  417.32  4549.7  415.32  4599.7  415.08
  4749.8  411.29  4789.8  411.19  4829.8  409.99  4843.2  410.04  4849.8  410.50
  4869.8  410.33  4879.8  409.62  4929.8  410.29  4939.8  409.96  4949.8  409.00
  4979.8  409.43  4996.8  405.92  4999.6  405.42  5002.8  405.92  5009.8  406.85
  5049.8  414.10  5059.8  415.46  5069.8  416.16  5289.9  422.47  5339.9  422.99
  5379.1  424.33  5384.1  423.71  5439.9  424.86  5489.9  425.21  5615.4  427.76
#Mann=3,-1,0
  4317.9    0.05       0  4996.8    0.03       0  5002.8    0.05       0
Bank Sta=4996.8,5002.8
Exp/Cntr=0.3,0.1

Type RM Length L Ch R = 1,13305,612,612,612
BEGIN DESCRIPTION:
EZELL BRANCH 20.0
END DESCRIPTION:
XS GIS Cut Line= 2
      3537389.78     10534793.88      3536380.78     10533940.01
#Sta/Elev= 30
  4297.4  424.55  4368.5  418.53  4425.3  416.88  4432.2  414.29  4438.7  416.04
  4467.3  415.63  4475.0  413.61  4481.6  415.05  4489.3  412.34  4495.9  414.22
  4503.6  411.41  4510.2  413.36  4517.3  410.73  4543.9  409.40  4623.3  408.06
  4645.3  411.62  4673.9  407.09  4701.3  406.60  4737.6  411.72  4794.6  411.18
  5003.8  405.28  5006.5  404.78  5009.8  405.28  5113.3  405.50  5148.5  410.82
  5290.2  418.72  5312.2  423.04  5355.1  420.89  5517.6  428.50  5619.2  430.43
#Mann=6,-1,0
  4297.4    0.08       0  4517.3     0.1       0  4543.9    0.16       0
  4794.6    0.05       0  5003.8    0.03       0  5009.8    0.05       0
Bank Sta=5003.8,5009.8
Exp/Cntr=0.3,0.1

Type RM Length L Ch R = 1,12693,411,411,411
BEGIN DESCRIPTION:
EZELL BRANCH 19.0
END DESCRIPTION:
XS GIS Cut Line= 3
      3537795.68     10534061.51      3537339.95     10533922.62
      3536589.09     10533892.24
#Sta/Elev= 30
  4379.4  428.80  4456.3  427.36  4528.8  425.48  4665.3  421.00  4717.3  419.80
  4774.3  418.79  4790.8  416.45  4807.1  415.87  4812.3  415.32  4832.7  414.33
  4845.2  413.31  4852.1  412.40  4873.7  411.44  4933.7  406.45  4943.7  405.98
  4959.6  405.89  4980.8  405.38  4983.5  404.88  4986.8  405.38  5071.9  405.54
  5133.9  405.69  5156.4  406.39  5173.9  406.81  5193.9  408.11  5214.0  408.07
  5244.0  408.74  5334.1  412.48  5434.1  418.25  5464.2  420.59  5607.3  426.94
#Mann=7,-1,0
  4379.4    0.05       0  4717.3    0.16       0  4959.6    0.05       0
  4980.8    0.03       0  4986.8    0.05       0  5071.9    0.16       0
  5156.4    0.05       0
Bank Sta=4980.8,4986.8
Exp/Cntr=0.3,0.1

Type RM Length L Ch R = 1,12282,46,46,46
BEGIN DESCRIPTION:
EZELL BRANCH 18.11
END DESCRIPTION:
XS GIS Cut Line= 4
      3537760.36     10533757.95      3537392.94     10533579.17
      3537052.23     10533494.54      3536546.84     10533425.13
#Sta/Elev= 30
  4440.8  423.73  4472.2  416.91  4647.0  416.87  4683.5  413.80  4700.4  408.09
  4716.3  404.38  4762.3  402.86  4765.1  402.36  4768.3  402.86  4787.9  404.83
  4804.9  411.62  4817.0  411.99  4827.4  408.94  4833.0  409.94  4857.7  406.24
  4862.8  408.28  4940.4  405.58  5028.2  407.61  5188.4  406.61  5210.7  408.45
  5241.0  404.63  5262.4  404.71  5281.3  412.01  5301.5  413.66  5311.6  416.99
  5352.0  417.17  5372.2  422.11  5401.5  424.79  5594.3  434.51  5710.6  436.30
#Mann=5,-1,0
  4440.8    0.05       0  4700.4    0.16       0  4716.3    0.05       0
  4762.3    0.03       0  4768.3    0.05       0
Bank Sta=4762.3,4768.3
Exp/Cntr=0.3,0.1

Type RM Length L Ch R = 1,12236,80,80,80
BEGIN DESCRIPTION:
EZELL BRANCH 18.0
END DESCRIPTION:
XS GIS Cut Line= 6
      3537774.44     10533710.23      3537409.40     10533545.01
      3537001.41     10533423.49      3536671.55     10533362.72
      3536658.53     10533354.04      3536571.70     10533336.68
#Sta/Elev= 30
  4452.9  425.00  4489.9  414.08  4530.6  415.04  4548.2  412.22  4559.2  411.33
  4565.2  414.06  4582.3  414.91  4674.7  413.25  4708.8  404.42  4718.5  403.46
  4759.8  402.02  4762.6  401.52  4765.8  402.02  4801.1  403.82  4824.3  411.86
  4839.6  414.25  4902.9  415.44  5061.4  414.01  5080.3  415.55  5094.5  413.81
  5194.0  415.53  5199.2  413.68  5226.4  415.22  5265.6  405.42  5288.8  404.81
  5298.9  406.49  5315.6  414.74  5329.4  416.92  5590.9  433.15  5718.9  436.76
#Mann=5,-1,0
  4452.9    0.05       0  4548.2    0.16       0  4718.5    0.05       0
  4759.8    0.03       0  4765.8    0.05       0
Bank Sta=4759.8,4765.8
Exp/Cntr=0.3,0.1

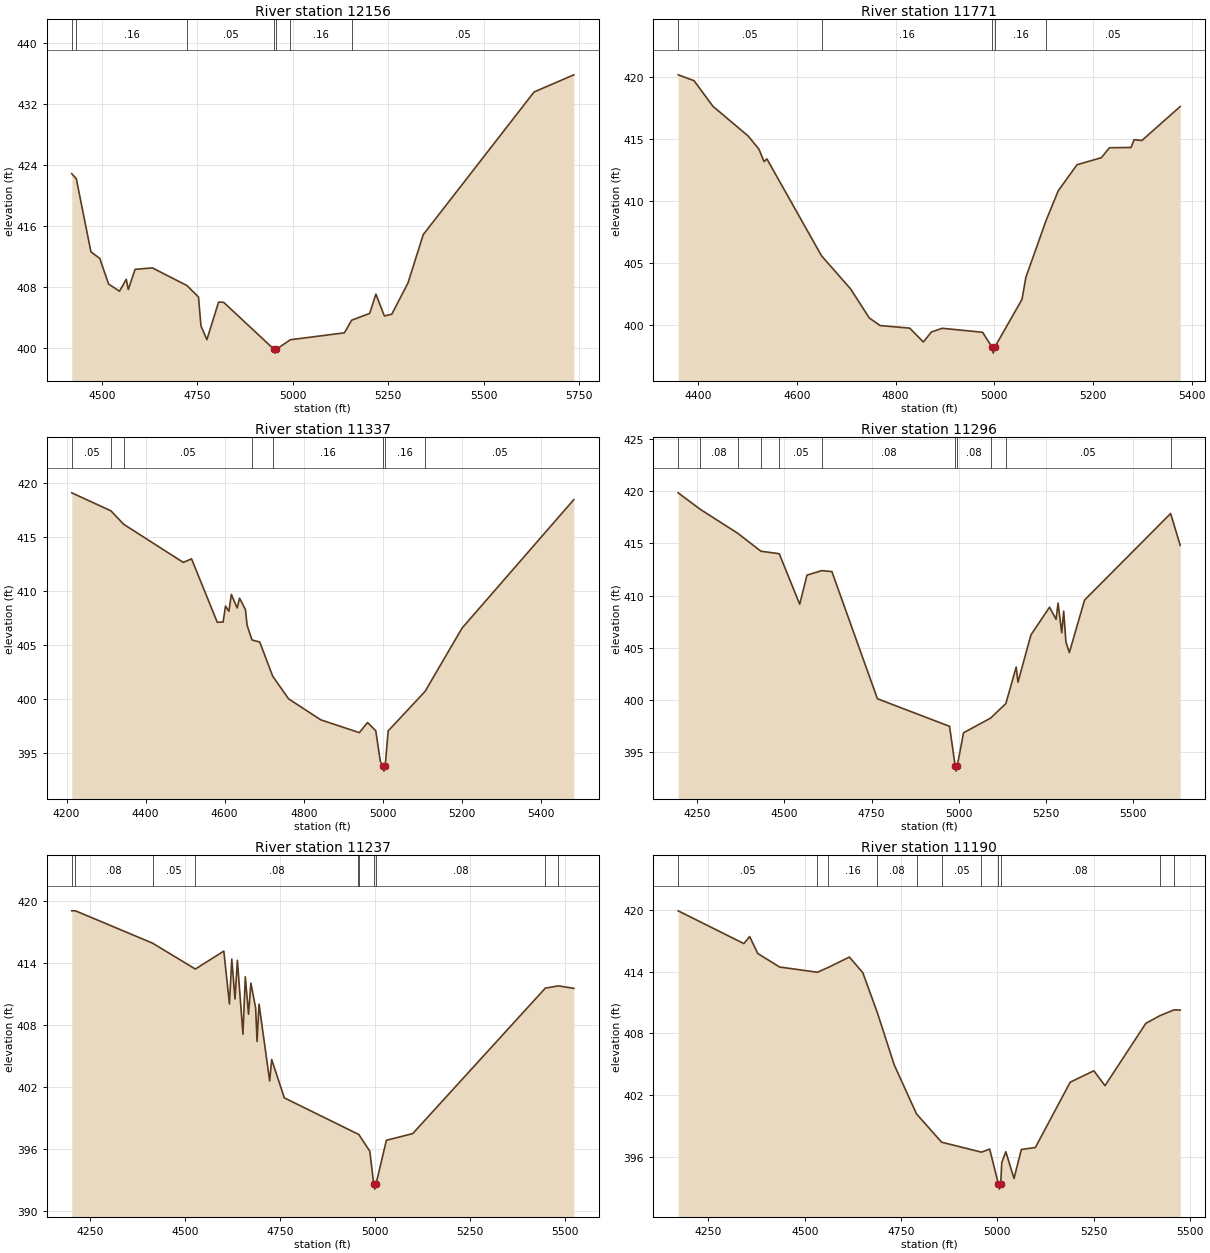
Type RM Length L Ch R = 1,12156,385,385,385
BEGIN DESCRIPTION:
EZELL BRANCH 18.1
END DESCRIPTION:
XS GIS Cut Line= 6
      3537844.68     10533656.62      3537433.74     10533470.64
      3537025.76     10533349.11      3536695.89     10533288.35
      3536682.87     10533279.67      3536596.61     10533262.41
#Sta/Elev= 30
  4420.7  422.86  4432.7  422.19  4471.0  412.58  4494.1  411.72  4517.2  408.35
  4545.8  407.41  4563.5  408.97  4568.9  407.63  4586.6  410.28  4632.1  410.47
  4722.6  408.15  4752.8  406.65  4759.3  402.85  4774.8  401.03  4805.5  405.97
  4818.7  405.95  4950.8  399.76  4953.5  399.26  4956.8  399.76  4993.5  401.02
  5135.3  401.93  5154.3  403.59  5201.6  404.49  5217.8  407.03  5240.0  404.15
  5259.5  404.38  5301.9  408.49  5341.9  414.85  5632.3  433.61  5736.5  435.87
#Mann=7,-1,0
  4420.7    0.05       0  4432.7    0.16       0  4722.6    0.05       0
  4950.8    0.07       0  4956.8    0.05       0  4993.5    0.16       0
  5154.3    0.05       0
Bank Sta=4950.8,4956.8
Exp/Cntr=0.3,0.1

Type RM Length L Ch R = 1,11771,434,434,434
BEGIN DESCRIPTION:
EZELL BRANCH 17.01
END DESCRIPTION:
XS GIS Cut Line= 2
      3537945.67     10533371.76      3537049.82     10532889.10
#Sta/Elev= 30
  4359.3  420.15  4391.5  419.68  4429.6  417.62  4501.0  415.23  4522.9  414.17
  4533.4  413.16  4539.1  413.38  4649.8  405.58  4708.6  402.92  4746.7  400.57
  4768.6  399.96  4828.7  399.75  4856.2  398.64  4872.5  399.44  4894.4  399.74
  4976.3  399.42  4995.2  398.24  4997.9  397.74  5001.2  398.24  5056.2  402.07
  5063.9  403.83  5105.0  408.42  5129.6  410.81  5167.7  412.91  5217.2  413.48
  5233.4  414.28  5277.2  414.30  5283.4  414.93  5299.1  414.86  5376.9  417.60
#Mann=5,-1,0
  4359.3    0.05       0  4649.8    0.16       0  4995.2    0.07       0
  5001.2    0.16       0  5105.0    0.05       0
Bank Sta=4995.2,5001.2
Exp/Cntr=0.3,0.1

Type RM Length L Ch R = 1,11337,41,41,41
BEGIN DESCRIPTION:
EZELL BRANCH 17.0
END DESCRIPTION:
XS GIS Cut Line= 6
      3538065.10     10533071.94      3537702.73     10532811.55
      3537557.33     10532720.41      3537210.10     10532620.58
      3537114.62     10532601.05      3536925.42     10532562.35
#Sta/Elev= 30
  4213.3  419.10  4312.4  417.43  4344.4  416.19  4495.3  412.65  4516.2  412.98
  4581.3  407.10  4596.0  407.12  4602.1  408.60  4610.7  408.12  4616.9  409.68
  4631.6  408.43  4637.7  409.33  4652.5  408.28  4656.8  406.81  4669.1  405.46
  4688.7  405.27  4721.5  402.10  4761.7  400.00  4843.3  398.05  4940.6  396.87
  4961.4  397.81  4982.2  397.04  4993.7  394.21  5000.0  393.80  5002.8  393.30
  5006.0  393.80  5013.5  397.03  5106.8  400.69  5200.6  406.57  5483.0  418.47
#Mann=8,-1,0
  4213.3    0.05       0  4312.4    0.08       0  4344.4    0.05       0
  4669.1    0.08       0  4721.5    0.16       0  5000.0    0.07       0
  5006.0    0.16       0  5106.8    0.05       0
Bank Sta=5000,5006
Exp/Cntr=0.3,0.1

Type RM Length L Ch R = 1,11296,59,59,59
BEGIN DESCRIPTION:
EZELL BRANCH 16.0
END DESCRIPTION:
XS GIS Cut Line= 6
      3538097.92     10533053.75      3537748.95     10532796.79
      3537563.19     10532683.95      3537150.43     10532572.40
      3537039.75     10532368.41      3536957.62     10532266.02
#Sta/Elev= 30
  4194.7  419.85  4257.3  418.29  4365.6  415.98  4432.2  414.26  4484.9  414.02
  4543.7  409.18  4564.6  411.97  4607.0  412.40  4636.1  412.31  4766.9  400.13
  4974.1  397.49  4990.2  393.70  4993.0  393.20  4996.2  393.70  5014.2  396.87
  5092.0  398.28  5135.8  399.67  5165.5  403.17  5170.6  401.72  5207.9  406.25
  5261.3  408.90  5280.0  407.73  5285.7  409.29  5296.2  406.45  5301.9  408.52
  5308.3  405.57  5318.1  404.55  5361.8  409.58  5609.0  417.87  5636.6  414.82
#Mann=11,-1,0
  4194.7    0.05       0  4257.3    0.08       0  4365.6    0.05       0
  4432.2    0.08       0  4484.9    0.05       0  4607.0    0.08       0
  4990.2    0.07       0  4996.2    0.08       0  5092.0    0.16       0
  5135.8    0.05       0  5609.0    0.08       0
Bank Sta=4990.2,4996.2
Exp/Cntr=0.3,0.1

Type RM Length L Ch R = 1,11237,47,47,47
BEGIN DESCRIPTION:
EZELL BRANCH 15.0
END DESCRIPTION:
XS GIS Cut Line= 5
      3538132.60     10532959.97      3537742.01     10532678.74
      3537471.17     10532598.88      3537248.95     10532503.39
      3537047.55     10532260.33
#Sta/Elev= 30
  4201.3  419.05  4211.1  419.05  4413.8  415.92  4526.6  413.41  4601.5  415.15
  4616.2  410.03  4622.4  414.38  4630.9  410.51  4637.1  414.26  4651.8  407.10
  4658.0  412.66  4666.5  409.03  4672.7  412.05  4685.2  409.64  4688.9  406.40
  4694.1  410.02  4722.2  402.56  4727.4  404.65  4760.7  400.93  4954.6  397.42
  4956.0  397.42  4985.7  395.76  4996.0  392.59  4998.8  392.09  5002.0  392.59
  5029.3  396.82  5098.6  397.47  5447.5  411.56  5482.1  411.78  5522.5  411.54
#Mann=10,-1,0
  4201.3    0.05       0  4211.1    0.08       0  4413.8    0.05       0
  4526.6    0.08       0  4954.6    0.05       0  4956.0    0.08       0
  4996.0    0.07       0  5002.0    0.08       0  5447.5    0.05       0
  5482.1    0.08       0
Bank Sta=4996,5002
Exp/Cntr=0.3,0.1

Type RM Length L Ch R = 1,11190,673,673,673
BEGIN DESCRIPTION:
EZELL BRANCH 14.0
END DESCRIPTION:
XS GIS Cut Line= 4
      3538169.12     10532921.82      3537781.94     10532657.91
      3537264.57     10532475.61      3537087.50     10532251.67
#Sta/Elev= 30
  4171.7  419.92  4342.1  416.73  4357.1  417.42  4378.0  415.77  4434.9  414.45
  4532.9  413.94  4561.0  414.41  4615.9  415.42  4650.7  413.90  4688.7  409.98
  4732.3  404.92  4790.1  400.15  4855.2  397.40  4958.6  396.43  4979.9  396.73
  5002.5  393.33  5005.3  392.83  5008.5  393.33  5011.2  395.42  5021.8  396.47
  5043.0  393.87  5062.1  396.69  5098.4  396.88  5188.8  403.24  5250.2  404.35
  5279.1  402.90  5385.1  408.97  5421.3  409.71  5458.1  410.28  5474.3  410.26
#Mann=11,-1,0
  4171.7    0.05       0  4532.9    0.08       0  4561.0    0.16       0
  4688.7    0.08       0  4790.1     0.1       0  4855.2    0.05       0
  4958.6    0.08       0  5002.5    0.07       0  5008.5    0.08       0
  5421.3    0.05       0  5458.1    0.08       0
Bank Sta=5002.5,5008.5
Exp/Cntr=0.3,0.1

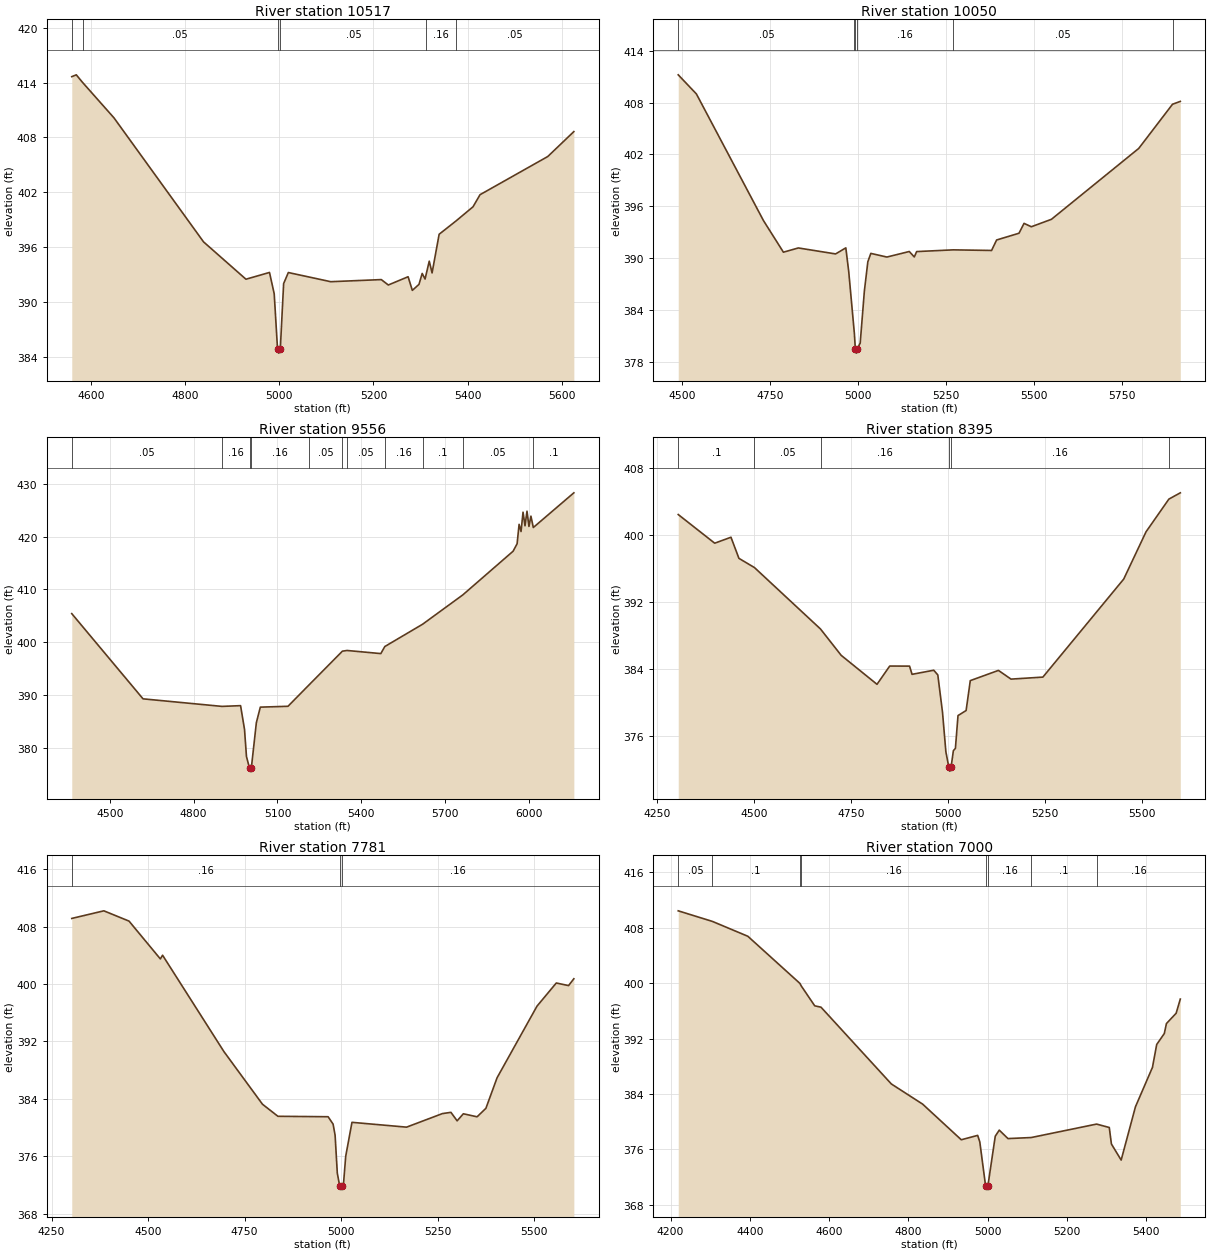
Type RM Length L Ch R = 1,10517,467,467,467
BEGIN DESCRIPTION:
EZELL BRANCH 13.01
END DESCRIPTION:
XS GIS Cut Line= 3
      3538091.73     10531953.77      3537513.56     10531943.35
      3537110.01     10532216.73
#Sta/Elev= 30
  4559.7  414.64  4569.3  414.84  4582.8  414.00  4649.3  410.14  4839.4  396.60
  4929.4  392.52  4979.4  393.26  4989.4  390.93  4996.4  384.95  4999.1  384.45
  5002.4  384.95  5009.4  392.04  5019.4  393.25  5109.4  392.25  5216.7  392.48
  5231.6  391.89  5273.6  392.79  5282.6  391.30  5296.7  391.96  5303.5  393.15
  5309.6  392.54  5312.6  393.20  5318.5  394.49  5324.5  393.21  5339.5  397.43
  5375.0  398.87  5411.4  400.43  5426.3  401.75  5570.1  405.92  5625.4  408.64
#Mann=6,-1,0
  4559.7     0.1       0  4582.8    0.05       0  4996.4    0.03       0
  5002.4    0.05       0  5312.6    0.16       0  5375.0    0.05       0
Bank Sta=4996.4,5002.4
Exp/Cntr=0.3,0.1

Type RM Length L Ch R = 1,10050,494,494,494
BEGIN DESCRIPTION:
EZELL BRANCH 13.0
END DESCRIPTION:
XS GIS Cut Line= 4
      3538047.42     10531739.46      3537778.32     10531470.36
      3537571.19     10531557.83      3537040.50     10532186.48
#Sta/Elev= 30
  4487.9  411.20  4539.6  408.99  4730.5  394.35  4787.1  390.71  4829.5  391.20
  4935.5  390.51  4964.6  391.21  4972.9  388.45  4989.0  381.28  4991.6  379.55
  4994.4  379.05  4997.6  379.55  5005.5  380.22  5017.4  386.24  5027.2  389.60
  5035.7  390.57  5081.5  390.15  5145.1  390.79  5159.4  390.16  5166.0  390.78
  5270.3  390.98  5379.2  390.91  5393.5  392.12  5457.2  392.90  5471.5  394.04
  5492.3  393.65  5549.5  394.51  5797.8  402.70  5893.8  407.80  5916.0  408.13
#Mann=6,-1,0
  4487.9    0.05       0  4989.0    0.16       0  4991.6    0.07       0
  4997.6    0.16       0  5270.3    0.05       0  5893.8    0.08       0
Bank Sta=4991.6,4997.6
Exp/Cntr=0.3,0.1

Type RM Length L Ch R = 1,9556,1161,1161,1161
BEGIN DESCRIPTION:
EZELL BRANCH 12.0
END DESCRIPTION:
XS GIS Cut Line= 3
      3538090.80     10531570.16      3537773.98     10531149.18
      3536880.00     10530246.52
#Sta/Elev= 30
  4363.7  405.42  4618.8  389.28  4901.4  387.85  4968.0  387.99  4982.1  383.49
  4989.1  378.35  5000.3  376.09  5003.0  375.59  5006.3  376.09  5024.5  384.77
  5038.7  387.71  5137.7  387.87  5214.2  391.98  5332.5  398.31  5349.3  398.44
  5470.0  397.85  5484.4  399.19  5619.8  403.42  5763.6  408.97  5943.7  417.25
  5957.9  418.66  5965.0  422.33  5972.0  420.97  5979.1  424.63  5986.2  422.06
  5993.3  424.82  6000.3  421.94  6007.4  423.88  6015.9  421.73  6161.0  428.30
#Mann=11,-1,0
  4363.7    0.05       0  4901.4    0.16       0  5000.3    0.07       0
  5006.3    0.16       0  5214.2    0.05       0  5332.5    0.16       0
  5349.3    0.05       0  5484.4    0.16       0  5619.8     0.1       0
  5763.6    0.05       0  6015.9     0.1       0
Bank Sta=5000.3,5006.3
Exp/Cntr=0.3,0.1

Type RM Length L Ch R = 1,8395,614,614,614
BEGIN DESCRIPTION:
EZELL BRANCH 10.0
END DESCRIPTION:
XS GIS Cut Line= 3
      3538568.26     10531344.54      3538438.04     10530754.21
      3538242.09     10530091.60
#Sta/Elev= 30
  4303.6  402.41  4397.7  398.99  4439.7  399.70  4460.2  397.18  4500.3  396.08
  4670.7  388.75  4724.0  385.61  4816.5  382.15  4849.3  384.33  4900.5  384.32
  4906.9  383.34  4962.9  383.83  4973.4  383.27  4985.5  378.81  4994.2  374.10
  5001.7  372.29  5004.4  371.79  5007.7  372.29  5013.5  374.22  5018.8  374.51
  5025.5  378.42  5046.4  379.02  5057.2  382.59  5129.8  383.81  5162.3  382.77
  5244.5  383.01  5453.1  394.71  5510.7  400.35  5569.6  404.25  5599.1  405.00
#Mann=6,-1,0
  4303.6     0.1       0  4500.3    0.05       0  4670.7    0.16       0
  5001.7    0.07       0  5007.7    0.16       0  5569.6    0.05       0
Bank Sta=5001.7,5007.7
Exp/Cntr=0.3,0.1

Type RM Length L Ch R = 1,7781,781,781,781
BEGIN DESCRIPTION:
EZELL BRANCH 8.0
END DESCRIPTION:
XS GIS Cut Line= 4
      3538834.08     10531324.65      3538992.11     10531040.81
      3538992.11     10530691.64      3538692.12     10530141.67
#Sta/Elev= 30
  4302.4  409.13  4385.5  410.19  4450.7  408.76  4531.9  403.49  4537.6  404.01
  4696.4  390.60  4796.4  383.26  4836.4  381.58  4966.4  381.52  4979.3  380.49
  4984.5  378.94  4990.2  373.67  4996.2  371.94  4999.0  371.44  5002.2  371.94
  5006.3  372.20  5012.0  376.02  5028.2  380.74  5169.6  380.07  5262.6  381.96
  5284.5  382.13  5300.6  380.95  5316.7  381.93  5352.3  381.51  5375.1  382.69
  5404.1  386.95  5507.5  396.92  5557.4  400.14  5589.2  399.78  5602.9  400.73
#Mann=3,-1,0
  4302.4    0.16       0  4996.2    0.07       0  5002.2    0.16       0
Bank Sta=4996.2,5002.2
Exp/Cntr=0.3,0.1

Type RM Length L Ch R = 1,7000,632,632,632
BEGIN DESCRIPTION:
EZELL BRANCH 7.0
END DESCRIPTION:
XS GIS Cut Line= 2
      3539931.71     10531217.71      3539473.64     10530036.09
#Sta/Elev= 30
  4219.3  410.42  4305.7  408.89  4395.0  406.75  4526.3  399.96  4529.8  399.59
  4563.8  396.72  4579.7  396.52  4757.2  385.45  4836.2  382.54  4933.7  377.40
  4975.1  378.03  4980.5  377.09  4995.0  370.78  4997.8  370.28  5001.0  370.78
  5019.5  377.91  5029.6  378.79  5051.6  377.57  5110.2  377.72  5275.2  379.66
  5307.3  379.17  5312.7  376.79  5337.3  374.47  5373.4  382.16  5416.3  387.84
  5427.0  391.14  5446.2  392.72  5451.6  394.16  5476.1  395.65  5486.6  397.69
#Mann=8,-1,0
  4219.3    0.05       0  4305.7     0.1       0  4526.3    0.05       0
  4529.8    0.16       0  4995.0    0.07       0  5001.0    0.16       0
  5110.2     0.1       0  5275.2    0.16       0
Bank Sta=4995,5001
Exp/Cntr=0.3,0.1