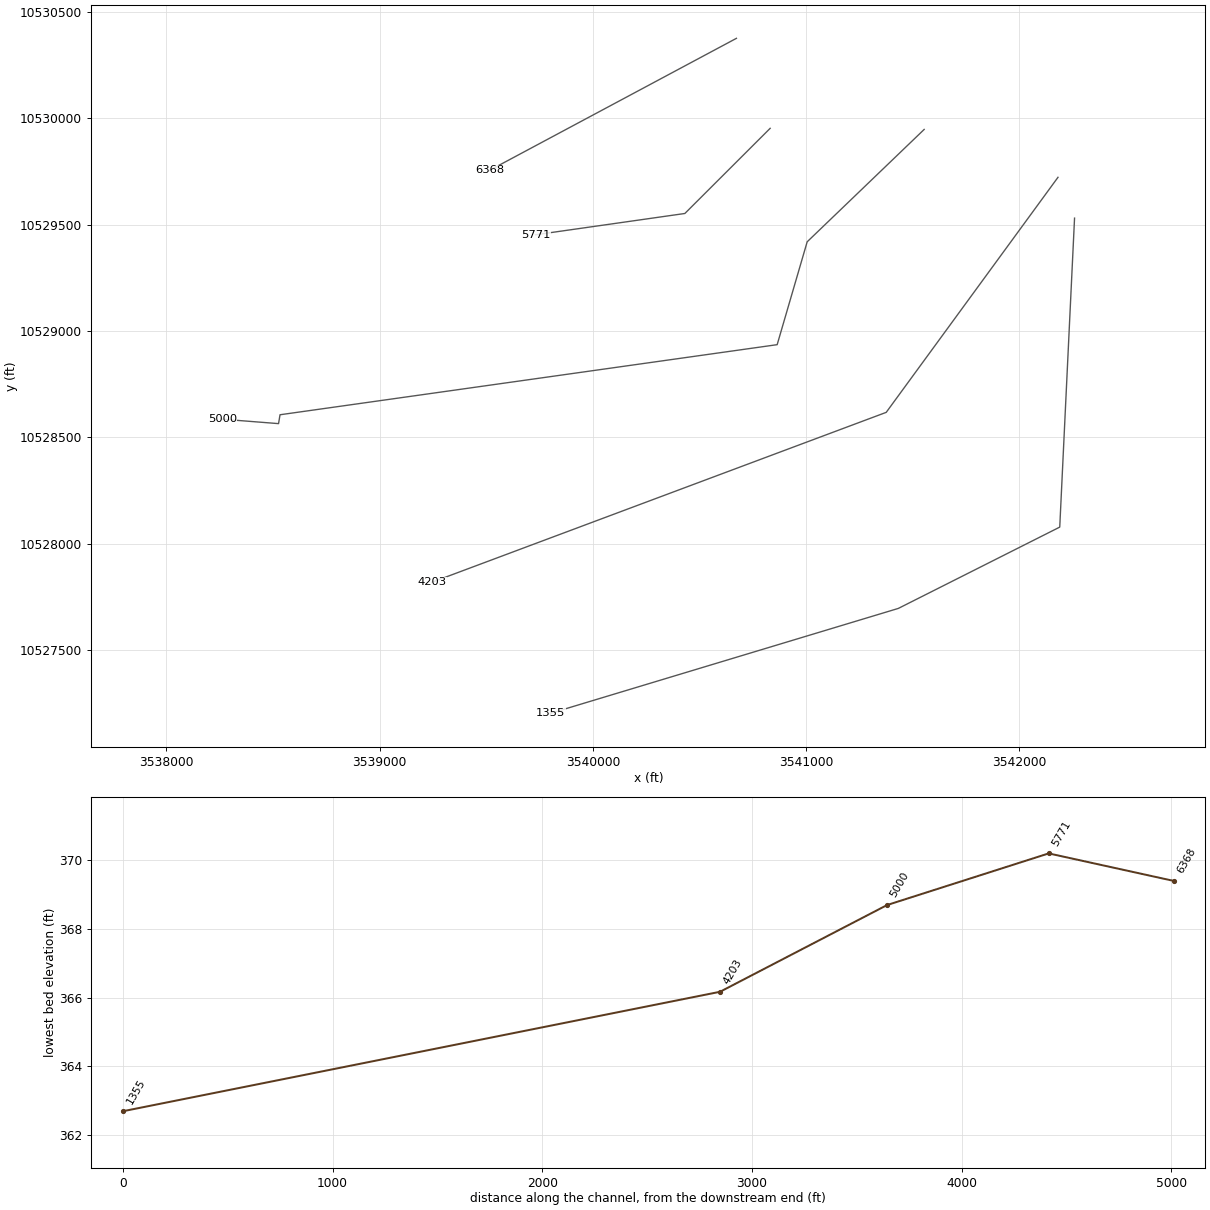
HEC-RAS study EZELL BRANCH.prj: EZELL BRANCH Base Level Engineering

--- EZELL BRANCH.g01 (geometry) --- (continued)

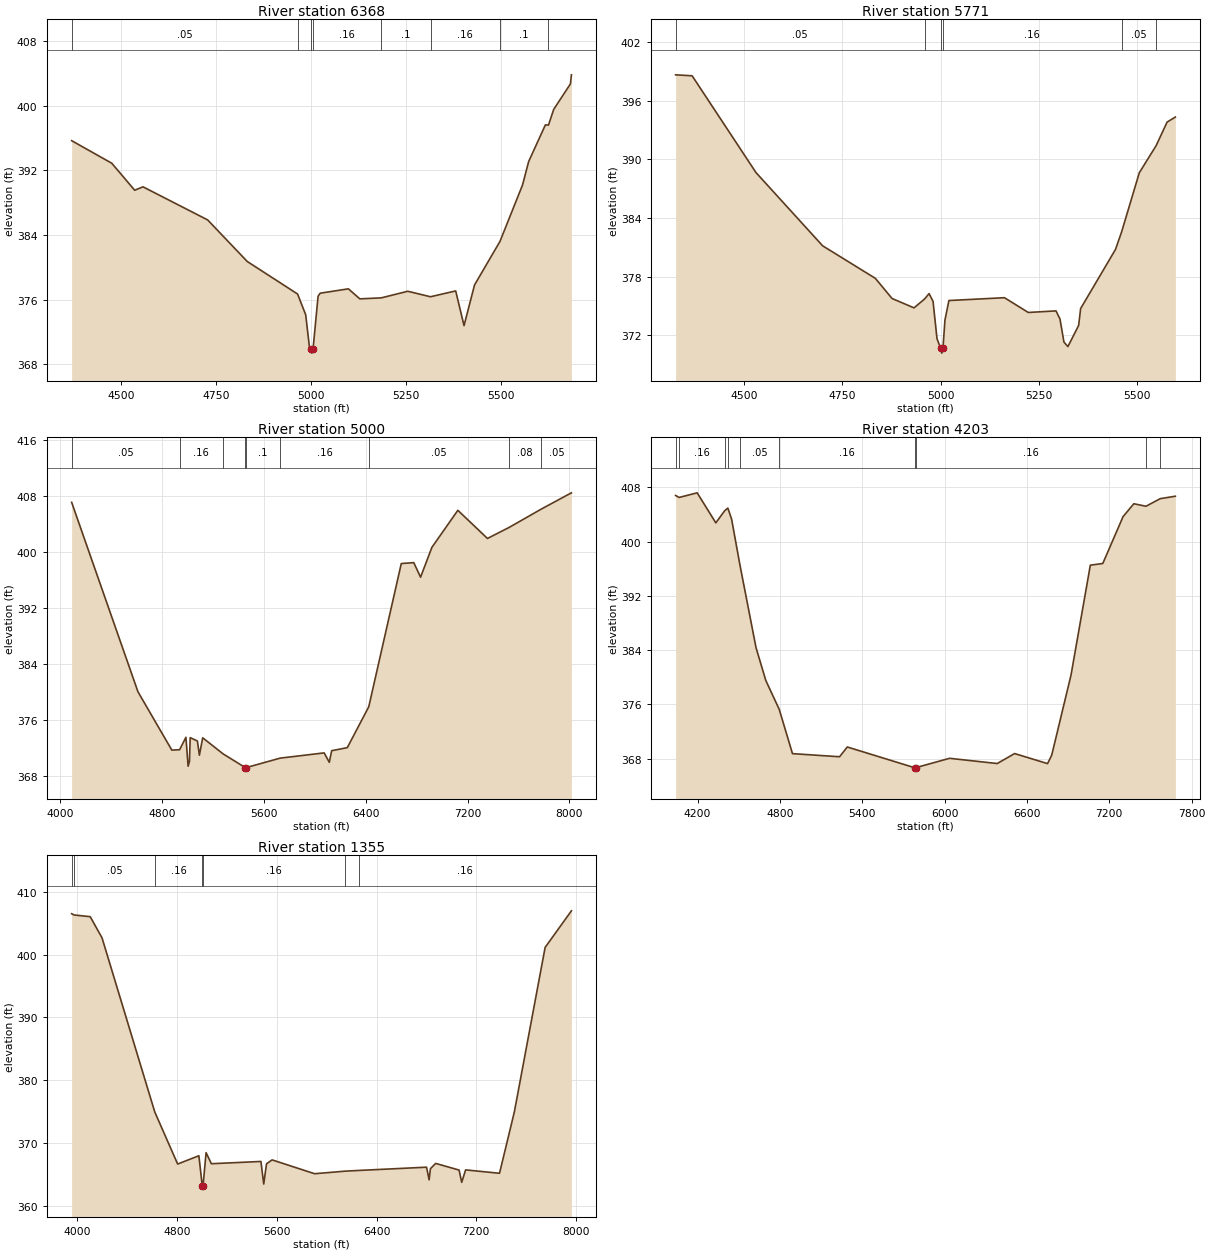
Type RM Length L Ch R = 1,6368,597,597,597
BEGIN DESCRIPTION:
EZELL BRANCH 5.0
END DESCRIPTION:
XS GIS Cut Line= 2
      3540673.00     10530374.85      3539515.64     10529754.99
#Sta/Elev= 30
  4371.0  395.66  4476.4  392.87  4536.6  389.53  4558.5  389.95  4728.3  385.86
  4832.3  380.72  4964.5  376.70  4985.8  374.14  4995.9  370.05  4999.1  369.89
  5001.9  369.39  5005.1  369.89  5018.4  376.43  5024.0  376.80  5098.0  377.34
  5128.0  376.10  5184.2  376.22  5254.0  377.04  5313.7  376.36  5379.9  377.08
  5401.8  372.79  5429.4  377.82  5496.2  383.20  5555.4  390.17  5571.6  393.08
  5615.5  397.61  5623.6  397.58  5637.4  399.53  5681.3  402.68  5683.9  403.80
#Mann=8,-1,0
  4371.0    0.05       0  4964.5    0.16       0  4999.1    0.07       0
  5005.1    0.16       0  5184.2     0.1       0  5313.7    0.16       0
  5496.2     0.1       0  5623.6    0.05       0
Bank Sta=4999.1,5005.1
Exp/Cntr=0.3,0.1

Type RM Length L Ch R = 1,5771,771,771,771
BEGIN DESCRIPTION:
EZELL BRANCH 3.0
END DESCRIPTION:
XS GIS Cut Line= 3
      3540831.24     10529952.12      3540431.23     10529552.11
      3539731.24     10529452.11
#Sta/Elev= 30
  4325.1  398.66  4367.3  398.56  4529.9  388.66  4699.6  381.17  4833.9  377.84
  4876.4  375.78  4932.4  374.82  4959.3  375.73  4970.7  376.28  4980.8  375.49
  4990.9  371.67  5000.1  370.69  5002.9  370.19  5006.1  370.69  5011.1  373.56
  5021.2  375.57  5162.7  375.86  5223.3  374.35  5294.0  374.51  5304.1  373.68
  5314.2  371.32  5324.3  370.86  5351.6  373.02  5356.7  374.75  5445.5  380.80
  5460.8  382.56  5506.1  388.64  5549.2  391.43  5576.8  393.82  5597.9  394.34
#Mann=6,-1,0
  4325.1    0.05       0  4959.3    0.16       0  5000.1    0.07       0
  5006.1    0.16       0  5460.8    0.05       0  5549.2    0.16       0
Bank Sta=5000.1,5006.1
Exp/Cntr=0.3,0.1

Type RM Length L Ch R = 1,5000,797,797,797
BEGIN DESCRIPTION:
EZELL BRANCH 2.0
END DESCRIPTION:
XS GIS Cut Line= 6
      3541553.52     10529946.95      3541004.88     10529419.15
      3540864.08     10528935.90      3538532.66     10528606.65
      3538525.72     10528564.98      3538261.88     10528585.81
#Sta/Elev= 30
  4089.7  407.15  4610.7  380.04  4876.6  371.70  4937.5  371.75  4987.5  373.53
  5004.6  369.39  5015.1  370.07  5021.0  373.48  5077.6  373.00  5093.2  370.97
  5119.2  373.46  5279.3  371.16  5454.3  369.19  5457.1  368.69  5460.3  369.19
  5727.8  370.55  6073.4  371.30  6113.8  369.95  6132.3  371.61  6255.2  372.05
  6423.8  377.90  6679.3  398.39  6777.3  398.52  6830.8  396.44  6919.5  400.70
  7123.7  406.01  7356.2  401.98  7524.5  403.54  7778.7  406.18  8015.8  408.51
#Mann=9,-1,0
  4089.7    0.05       0  4937.5    0.16       0  5279.3     0.1       0
  5454.3    0.07       0  5460.3     0.1       0  5727.8    0.16       0
  6423.8    0.05       0  7524.5    0.08       0  7778.7    0.05       0
Bank Sta=5454.3,5460.3
Exp/Cntr=0.3,0.1

Type RM Length L Ch R = 1,4203,2848,2848,2848
BEGIN DESCRIPTION:
EZELL BRANCH 1.0
END DESCRIPTION:
XS GIS Cut Line= 3
      3542181.09     10529722.09      3541375.54     10528617.93
      3539245.37     10527819.98
#Sta/Elev= 30
  4039.7  406.82  4066.0  406.53  4197.1  407.21  4333.0  402.78  4397.1  404.56
  4420.6  404.96  4448.1  403.32  4509.3  396.50  4625.8  384.39  4696.9  379.55
  4795.3  375.26  4891.5  368.75  5234.5  368.29  5290.9  369.73  5782.0  366.67
  5784.7  366.17  5788.0  366.67  6036.1  368.06  6383.3  367.29  6510.0  368.76
  6750.1  367.28  6780.4  368.52  6921.1  380.34  7061.8  396.54  7152.6  396.79
  7300.3  403.70  7378.7  405.60  7467.2  405.23  7571.3  406.35  7681.2  406.71
#Mann=10,-1,0
  4039.7    0.05       0  4066.0    0.16       0  4397.1    0.05       0
  4420.6    0.16       0  4509.3    0.05       0  4795.3    0.16       0
  5782.0    0.07       0  5788.0    0.16       0  7467.2     0.1       0
  7571.3    0.05       0
Bank Sta=5782,5788
Exp/Cntr=0.3,0.1

Type RM Length L Ch R = 1,1355,0,0,0
BEGIN DESCRIPTION:
EZELL BRANCH 1.01
END DESCRIPTION:
XS GIS Cut Line= 4
      3542258.72     10529530.30      3542189.28     10528078.91
      3541432.33     10527696.96      3539800.39     10527203.91
#Sta/Elev= 30
  3956.6  406.50  3976.2  406.30  4105.4  406.03  4200.1  402.66  4622.8  374.97
  4806.2  366.69  4976.4  368.01  5003.5  363.20  5006.2  362.70  5009.5  363.20
  5034.1  368.50  5076.5  366.74  5473.7  367.10  5496.1  363.51  5518.5  366.73
  5563.3  367.35  5904.0  365.15  6150.2  365.56  6258.7  365.67  6801.0  366.19
  6821.8  364.18  6832.3  365.95  6874.1  366.79  7062.1  365.73  7083.0  363.78
  7114.3  365.76  7386.0  365.22  7504.7  374.96  7751.6  401.14  7962.3  406.96
#Mann=7,-1,0
  3956.6    0.16       0  3976.2    0.05       0  4622.8    0.16       0
  5003.5    0.07       0  5009.5    0.16       0  6150.2    0.12       0
  6258.7    0.16       0
Bank Sta=5003.5,5009.5
Exp/Cntr=0.3,0.1

Chan Stop Cuts=-1