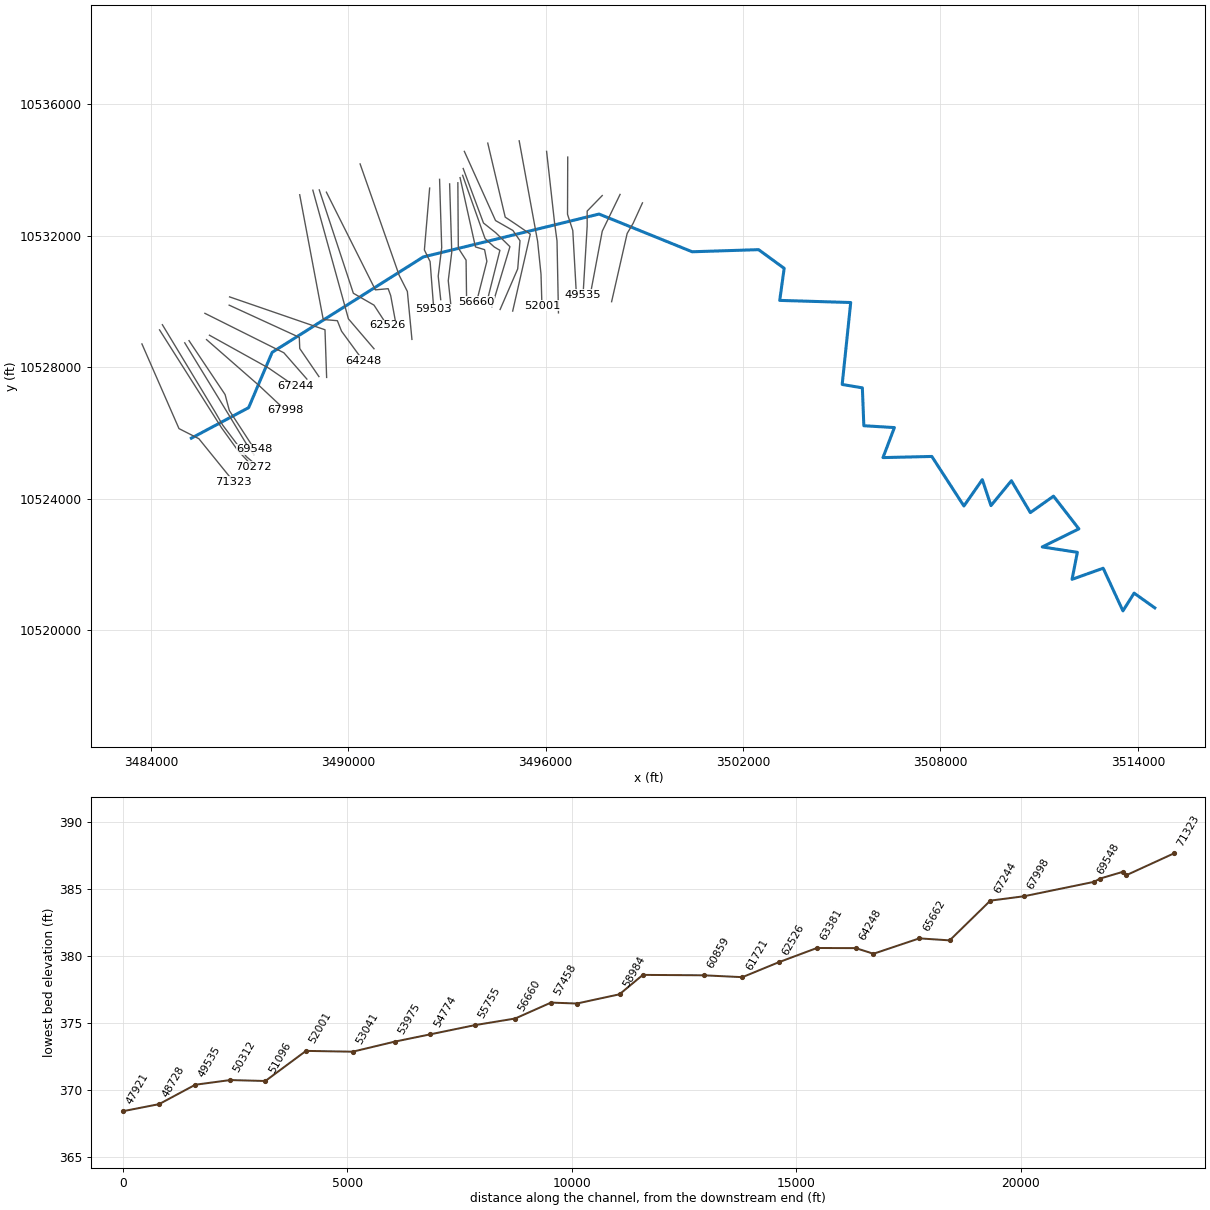
--- FAULKENBERRY CREEK.prj (project) ---

Proj Title=FAULKENBERRY CREEK Base Level Engineering
Current Plan=p01
Default Exp/Contr=0.3,0.1
English Units
Geom File=g01
Flow File=f01
Plan File=p01
Y Axis Title=Elevation
X Axis Title(PF)=Main Channel Distance
X Axis Title(XS)=Station
BEGIN DESCRIPTION:
FAULKENBERRY CREEK
END DESCRIPTION:
DSS Export Rating Curves= 0
DSS Export Rating Curve Sorted= 0
DSS Export Volume Flow Curves= 0
DXF OffsetX= 0
DXF OffsetY= 0
DXF ScaleX= 1
DXF ScaleY= 10

--- FAULKENBERRY CREEK.p01 (plan) ---

Plan Title=Multiple Run
Short Identifier=Multiple
Geom File=g01
Flow File=f01
Subcritical Flow
K Sum by GR= 0
Std Step Tol= 0.01
Critical Tol= 0.01
Num of Std Step Trials= 20
Max Error Tol= 0.3
Flow Tol Ratio= 0.001
Split Flow NTrial= 30
Split Flow Tol= 0.02
Split Flow Ratio= 0.02
Log Output Level= 0
Friction Slope Method= 1
Unsteady Friction Slope Method= 2
Unsteady Bridges Friction Slope Method= 1
Parabolic Critical Depth
Global Vel Dist=  1 , 1 , 1
Global Log Level= 0
CheckData=True
Encroach Param= -1, 0, 0, 0
BEGIN DESCRIPTION:
Multiple Run
END DESCRIPTION:

--- FAULKENBERRY CREEK.f01 (steady flow) ---

Flow Title=Multiple
Program Version=4.10
Number of Profiles= 7
Profile Names=10-year,25-year,50-year,1pct_min,100-year,1pct_plu,500-year
River Rch & RM=FAULKENBERRY CRE,Reach-1         ,71323
   10309   15258   19633   18288   24732   33447   39147
River Rch & RM=FAULKENBERRY CRE,Reach-1         ,64248
   10628   15717   20212   18813   25443   34409   40212
River Rch & RM=FAULKENBERRY CRE,Reach-1         ,51096
   10742   15873   20402   18979   25667   34712   40519
River Rch & RM=FAULKENBERRY CRE,Reach-1         ,46971
   10558   15537   19913   18469   24977   33778   39191
River Rch & RM=FAULKENBERRY CRE,Reach-1         ,33437
   10528   15466   19798   18339   24802   33541   38816
River Rch & RM=FAULKENBERRY CRE,Reach-1         ,24233
   12753   18751   24021   22258   30101   40708   47123
River Rch & RM=FAULKENBERRY CRE,Reach-1         ,7152
   12936   19027   24381   22596   30559   41327   47862
Boundary for River Rch & Prof#=FAULKENBERRY CRE,Reach-1         , 1
Up Type= 0
Dn Type= 3
Dn Slope=0.001
Boundary for River Rch & Prof#=FAULKENBERRY CRE,Reach-1         , 2
Up Type= 0
Dn Type= 3
Dn Slope=0.001
Boundary for River Rch & Prof#=FAULKENBERRY CRE,Reach-1         , 3
Up Type= 0
Dn Type= 3
Dn Slope=0.001
Boundary for River Rch & Prof#=FAULKENBERRY CRE,Reach-1         , 4
Up Type= 0
Dn Type= 3
Dn Slope=0.001
Boundary for River Rch & Prof#=FAULKENBERRY CRE,Reach-1         , 5
Up Type= 0
Dn Type= 3
Dn Slope=0.001
Boundary for River Rch & Prof#=FAULKENBERRY CRE,Reach-1         , 6
Up Type= 0
Dn Type= 3
Dn Slope=0.001
Boundary for River Rch & Prof#=FAULKENBERRY CRE,Reach-1         , 7
Up Type= 0
Dn Type= 3
Dn Slope=0.001
DSS Import GetInterval= 0
DSS Import GetPeak= 0
DSS Import FillOption= 0

--- FAULKENBERRY CREEK.g01 (geometry) ---

Geom Title=Existing Conditions
Program Version=4.10

River Reach=FAULKENBERRY CRE,Reach-1
Reach XY= 30
      3485230.15     10525844.06      3486970.95     10526772.16
      3487685.62     10528454.24       3492279.5     10531356.49
      3497621.92     10532661.05      3500452.72     10531514.05
      3502470.85     10531578.22      3503248.71     10531010.73
      3503113.57     10530035.18        3505271.     10529970.54
      3505012.29     10527477.99      3505625.14      10527374.7
      3505670.01     10526222.47      3506598.83     10526166.91
      3506252.47     10525253.72      3507736.85     10525288.44
      3508711.67     10523781.49      3509271.57     10524583.58
      3509534.59     10523792.78      3510155.25     10524550.59
      3510731.64     10523580.97      3511435.63      10524080.8
      3512205.86     10523086.01      3511093.01     10522536.53
      3512159.85     10522372.47      3511998.94     10521551.03
      3512945.12      10521888.7      3513544.95     10520590.96
      3513885.23     10521130.89      3514513.13      10520683.4

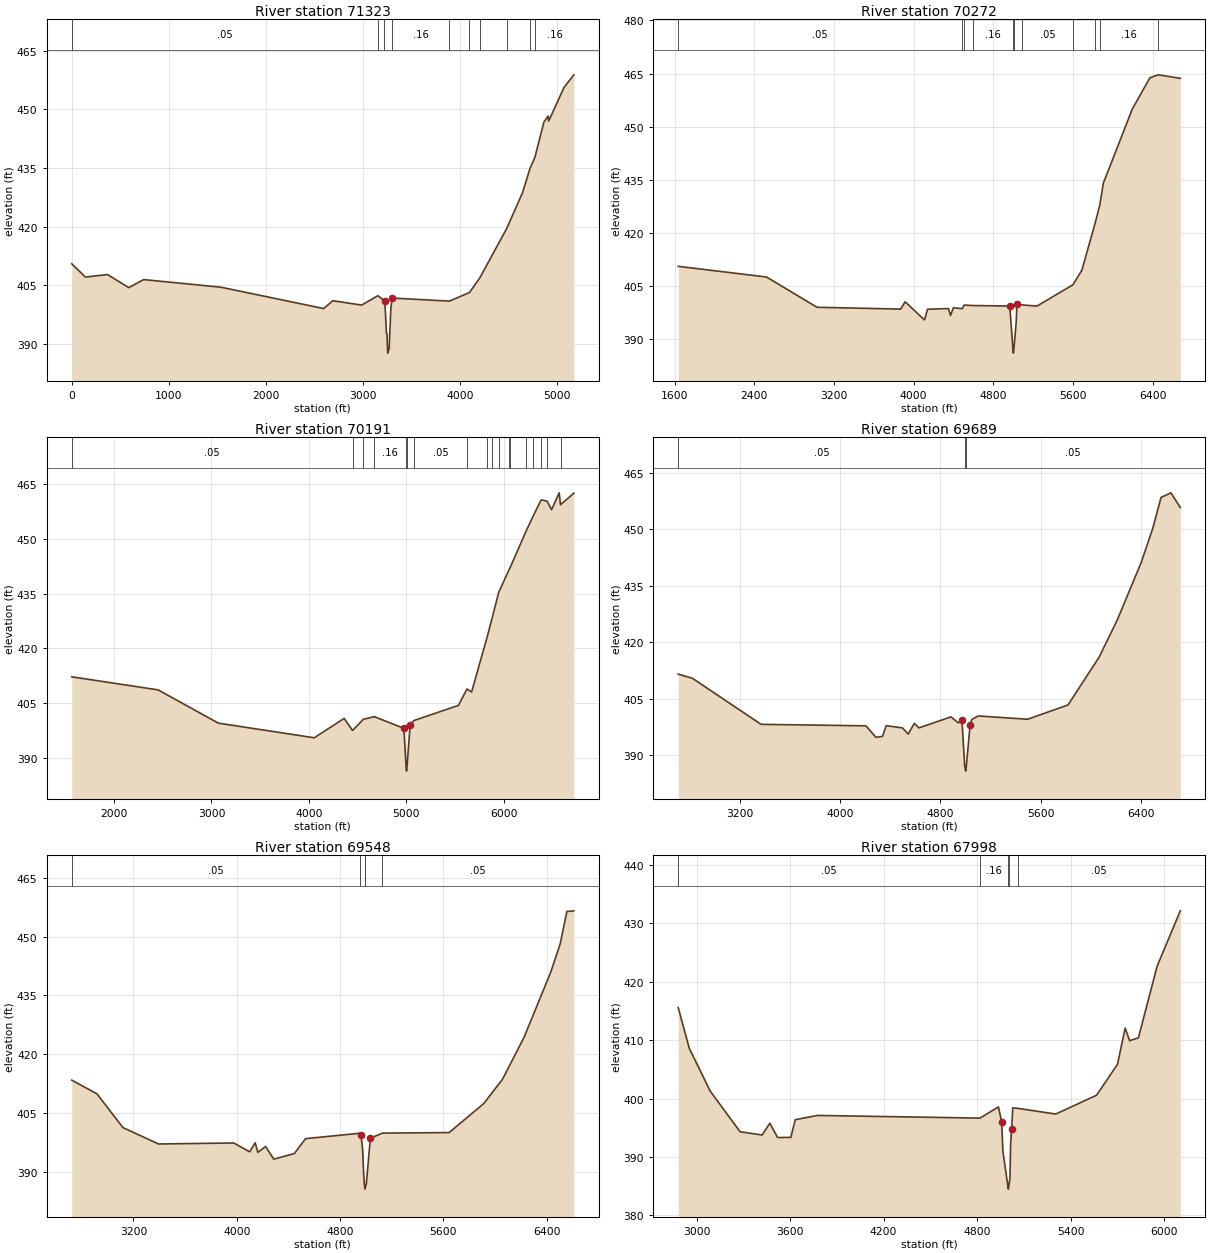
Type RM Length L Ch R = 1 ,71323   ,1060,1060,1060
XS GIS Cut Line= 4
      3483728.12     10528710.78      3484854.42     10526135.26
      3485458.59     10525827.97      3486521.09     10524515.47
#Sta/Elev= 30
       0  410.51   140.9  407.11   368.3  407.76   588.4  404.41     741  406.47
    1538  404.52  2597.6  399.07  2691.2  401.07    2989  399.95  3155.8  402.35
  3222.5  401.08  3228.1  400.97  3244.8  392.68  3250.4  392.61  3257.2  387.68
  3272.6  388.81  3289.2  398.68  3302.1  401.75  3894.6  400.97  4100.8  403.17
  4206.4  406.87  4484.5  419.51  4647.6  428.68  4725.9  434.95  4775.5  437.71
  4868.2  446.73  4911.3  448.27  4917.8  446.97  5074.4  455.52  5176.8  458.79
#Mann= 10 ,-1 , 0
       0     .05       0  3155.8     .16       0  3222.5     .05       0
  3302.1     .16       0  3894.6     .07       0  4100.8     .16       0
  4206.4     .05       0  4484.5     .16       0  4725.9     .12       0
  4775.5     .16       0
Bank Sta=3228.1,3302.1
XS Rating Curve= 0 ,0
Exp/Cntr=0.3,0.1

Type RM Length L Ch R = 1 ,70272   ,81,81,81
BEGIN DESCRIPTION:
FAULKENBERRY CREEK 20.01
END DESCRIPTION:
XS GIS Cut Line= 4
      3484263.34     10529137.85      3486146.82     10526162.07
      3486645.95     10525467.63      3487101.69     10524979.33
#Sta/Elev= 30
  1634.5  410.56  2521.9  407.54  3028.8     399  3869.7  398.48  3914.1  400.56
  4109.5  395.42    4139  398.45  4349.4  398.63  4370.6  396.67  4399.3  398.87
    4488  398.61  4507.4  399.62  4599.3  399.49  4965.7  399.35  4999.1  386.55
  5001.9  386.05  5005.1  386.55  5029.2  394.38  5038.4  399.82  5088.4  399.66
  5239.6  399.34  5600.4  405.35  5690.2  409.47  5821.9  422.57  5870.8  427.92
  5906.2  434.06  6197.2  454.99    6374   463.8    6457  464.64  6679.4  463.65
#Mann= 11 ,-1 , 0
  1634.5     .05       0    4488     .16       0  4507.4     .05       0
  4599.3     .16       0  4999.1     .07       0  5005.1     .16       0
  5088.4     .05       0  5600.4     .16       0  5821.9     .12       0
  5870.8     .16       0    6457     .05       0
Bank Sta=4965.7,5038.4
XS Rating Curve= 0 ,0
Exp/Cntr=0.3,0.1

Type RM Length L Ch R = 1 ,70191   ,502,502,502
BEGIN DESCRIPTION:
FAULKENBERRY CREEK 20.0
END DESCRIPTION:
XS GIS Cut Line= 5
       3484349.4     10529295.55      3485950.97     10526642.76
        3486181.     10526243.45      3486901.49     10525284.25
      3487200.98     10525028.16
#Sta/Elev= 30
  1566.2  412.17  2452.2  408.59  3071.4  399.46  4055.4  395.45    4362  400.77
    4448  397.46  4559.9  400.54  4671.8  401.23  4974.9  398.05  4999.2   386.8
    5002   386.3  5005.2   386.8  5039.6  399.07  5079.8  400.19    5535  404.34
  5622.4  408.84  5670.4  408.02  5828.6     423  5879.1  428.13  5947.7   435.3
    6053  441.48  6066.9  442.22  6226.8  451.97  6305.1  456.44  6383.7  460.71
  6445.1  460.37  6490.9  458.03  6568.8  462.65  6582.6  459.39  6719.5  462.55
#Mann= 18 ,-1 , 0
  1566.2     .05       0    4448     .16       0  4559.9     .05       0
  4671.8     .16       0  4999.2     .07       0  5005.2     .16       0
  5079.8     .05       0  5622.4     .16       0  5828.6     .12       0
  5879.1     .05       0  5947.7     .12       0    6053     .08       0
  6066.9     .16       0  6226.8     .08       0  6305.1     .16       0
  6383.7     .08       0  6445.1     .05       0  6582.6     .08       0
Bank Sta=4974.9,5039.6
XS Rating Curve= 0 ,0
Exp/Cntr=0.3,0.1

Type RM Length L Ch R = 1 ,69689   ,141,141,141
BEGIN DESCRIPTION:
FAULKENBERRY CREEK 18.0
END DESCRIPTION:
XS GIS Cut Line= 4
      3485029.22      10528744.5      3486342.13      10526596.1
      3486993.17     10525521.88      3487134.23     10525348.28
#Sta/Elev= 30
    2712  411.53  2824.8  410.43  3371.6  398.21  4206.7  397.81  4286.1  394.77
  4338.3  395.02  4367.8  397.86    4497  397.27  4543.3  395.62  4591.8  398.48
  4628.6  397.27  4883.5  400.19  4942.1   398.6  4971.1   399.4  4992.4  387.34
  4997.6   386.3  5000.4   385.8  5003.6   386.3  5035.8  398.01  5050.5  399.55
  5102.7  400.43  5494.2  399.56    5816  403.36  6064.2  416.09  6207.8   425.9
  6397.8  441.11    6489  450.04  6556.3  458.39  6634.6  459.61  6709.6  455.73
#Mann= 3 ,-1 , 0
    2712     .05       0  4997.6    .035       0  5003.6     .05       0
Bank Sta=4971.1,5035.8
XS Rating Curve= 0 ,0
Exp/Cntr=0.3,0.1

Type RM Length L Ch R = 1 ,69548   ,1550,1550,1550
BEGIN DESCRIPTION:
FAULKENBERRY CREEK 18.01
END DESCRIPTION:
XS GIS Cut Line= 4
      3485159.39     10528809.67      3486255.33     10527171.19
      3486385.54     10526682.91      3487155.95     10525500.16
#Sta/Elev= 30
  2722.6  413.38  2917.5  409.89  3118.7  401.27    3394  397.08  3977.5  397.33
  4100.6  395.08  4142.7  397.39  4163.9  394.94  4223.7  396.44  4286.8   393.2
  4445.9  394.63    4533  398.44  4954.3  399.82  4962.4  399.25  4975.2  395.71
  4983.1  389.33  4990.5  386.05  4993.2  385.55  4996.5  386.05  5003.8  386.93
  5034.9  398.54  5128.3  399.85    5645  399.99  5913.7  407.42  6058.6  413.63
  6224.6  424.27  6432.7  441.02  6505.2  448.21  6556.5  456.43  6610.7  456.61
#Mann= 5 ,-1 , 0
  2722.6     .05       0  4954.3     .16       0  4990.5     .07       0
  4996.5     .16       0  5128.3     .05       0
Bank Sta=4962.4,5034.9
XS Rating Curve= 0 ,0
Exp/Cntr=0.3,0.1

Type RM Length L Ch R = 1 ,67998   ,754,754,754
BEGIN DESCRIPTION:
FAULKENBERRY CREEK 16.0
END DESCRIPTION:
XS GIS Cut Line= 3
       3485692.1     10528841.65      3487292.11     10527441.64
      3488092.09     10526691.66
#Sta/Elev= 30
  2881.9  415.57  2952.6  408.61  3087.4  401.26  3279.1   394.3  3420.5  393.75
  3469.9  395.77  3519.7  393.32  3604.7  393.34  3633.1  396.37  3774.6   397.1
  4818.6  396.64  4937.2  398.56  4958.1  395.98  4965.7     391  4997.8  384.98
  5000.6  384.48  5003.8  384.98  5011.4  386.48    5015  391.97  5021.9  394.86
  5029.2  398.39  5059.6  398.32  5305.2  397.34    5567  400.56  5701.3  405.85
  5750.6  412.07    5779   409.9  5835.6  410.39  5955.8  422.66  6104.5  432.14
#Mann= 5 ,-1 , 0
  2881.9     .05       0  4818.6     .16       0  4997.8     .07       0
  5003.8     .16       0  5059.6     .05       0
Bank Sta=4958.1,5021.9
XS Rating Curve= 0 ,0
Exp/Cntr=0.3,0.1

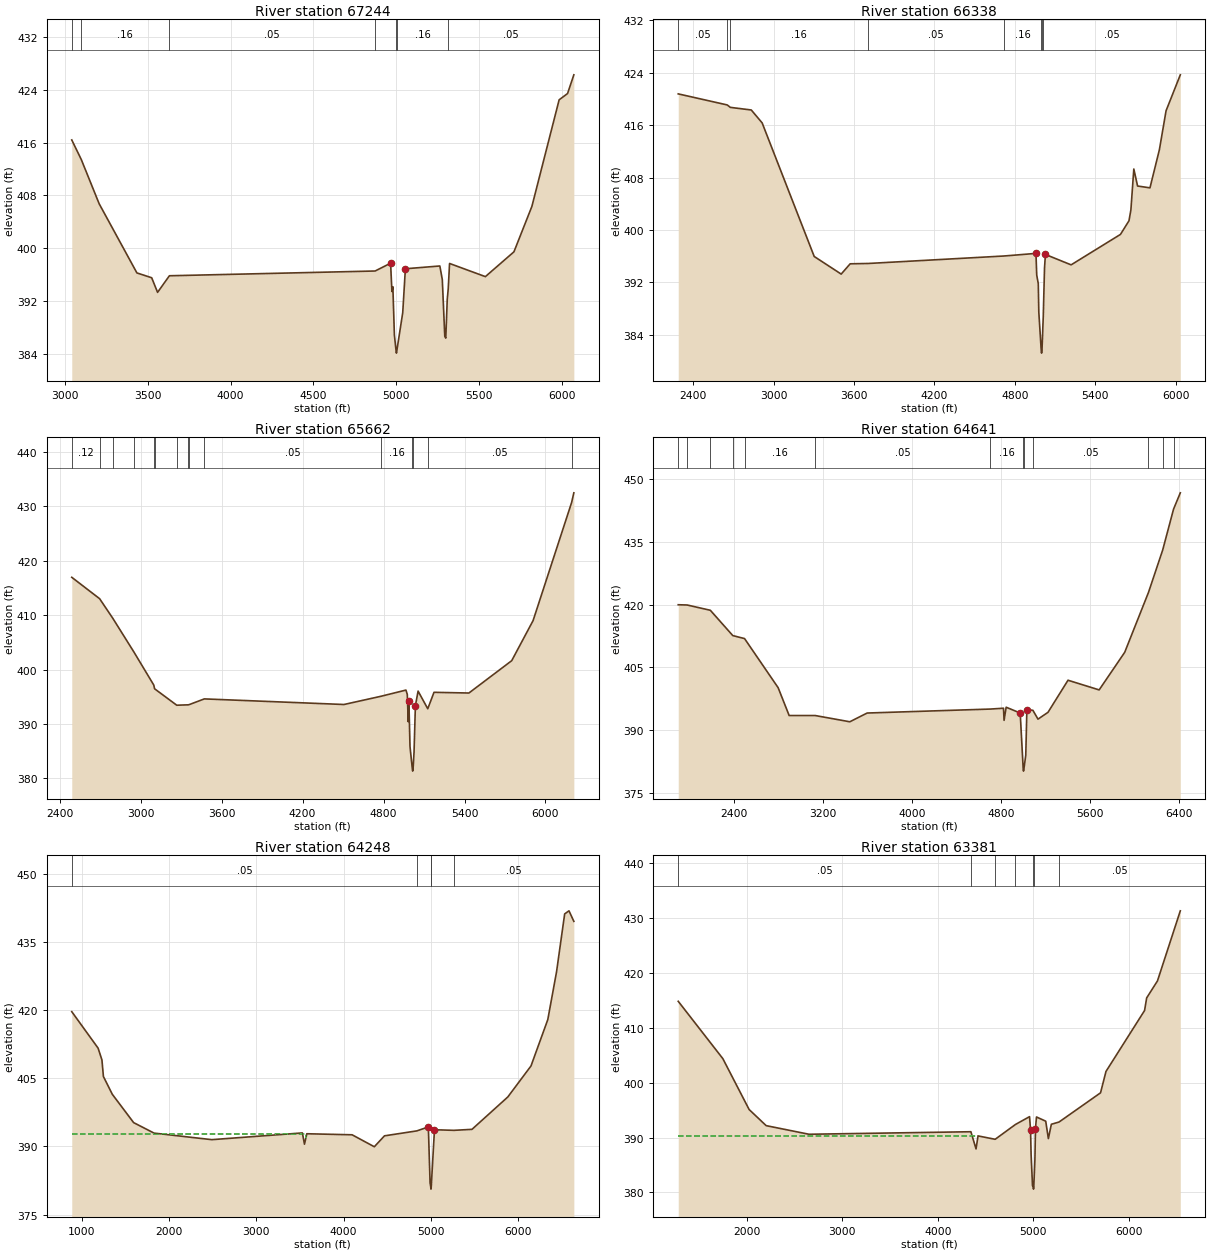
Type RM Length L Ch R = 1 ,67244   ,906,906,906
BEGIN DESCRIPTION:
FAULKENBERRY CREEK 15.0
END DESCRIPTION:
XS GIS Cut Line= 3
      3485780.57     10528975.83      3487580.59     10527975.82
      3488379.96     10527426.25
#Sta/Elev= 30
  3042.3  416.39  3099.7  413.43  3207.6  406.74  3435.3  396.28  3524.5  395.55
    3560  393.34  3631.3  395.85  4872.5  396.57  4965.9  397.75  4973.9  393.47
  4979.6  394.19  4988.8  386.87  4998.4  384.65  5001.1  384.15  5004.4  384.65
  5039.1  390.27  5055.1  396.91    5263  397.33  5277.9  395.27  5292.8   386.7
  5298.8  386.42  5307.7  392.27  5313.7  393.91  5321.7  397.71  5537.7  395.72
  5710.1  399.47  5818.4  406.34  5982.8  422.46  6033.6  423.41  6071.5  426.24
#Mann= 7 ,-1 , 0
  3042.3     .05       0  3099.7     .16       0  3631.3     .05       0
  4872.5     .16       0  4998.4     .07       0  5004.4     .16       0
  5313.7     .05       0
Bank Sta=4965.9,5055.1
XS Rating Curve= 0 ,0
Exp/Cntr=0.3,0.1

Type RM Length L Ch R = 1 ,66338   ,676,676,676
BEGIN DESCRIPTION:
FAULKENBERRY CREEK 13.0
END DESCRIPTION:
XS GIS Cut Line= 3
      3485642.11     10529641.64      3488042.11     10528441.64
      3488742.11     10527641.64
#Sta/Elev= 30
    2288  420.77  2653.5  419.08  2676.8  418.71    2833  418.31  2914.1  416.34
  3302.6  395.94  3503.9  393.25  3570.9  394.82  3705.5  394.87  4717.2  396.01
  4957.3  396.41  4962.9   393.1  4974.6  391.78  4978.4  387.48  4996.3  381.68
    4999  381.18  5002.3  381.68  5011.7  386.76  5021.1  394.18  5027.8  396.25
  5219.5  394.66  5587.7  399.31  5651.3  401.39  5665.6  403.06  5687.4   409.3
  5715.4   406.7  5807.9  406.42  5878.2  412.24    5928  418.19  6034.3  423.68
#Mann= 8 ,-1 , 0
    2288     .05       0  2653.5     .12       0  2676.8     .16       0
  3705.5     .05       0  4717.2     .16       0  4996.3     .07       0
  5002.3     .16       0  5011.7     .05       0
Bank Sta=4957.3,5027.8
XS Rating Curve= 0 ,0
Exp/Cntr=0.3,0.1

Type RM Length L Ch R = 1 ,65662   ,1021,1021,1021
BEGIN DESCRIPTION:
FAULKENBERRY CREEK 12.0
END DESCRIPTION:
XS GIS Cut Line= 4
      3486379.14     10529890.54      3488511.04     10528911.39
      3488524.93     10528571.12      3489107.69     10527717.79
#Sta/Elev= 30
  2490.2  416.94  2696.5  413.01  2794.2  409.41  2950.2  403.23  3097.9  397.14
  3103.9  396.46  3267.9  393.44    3354  393.51  3361.5  393.56  3472.4   394.6
    4507  393.57    4781  395.08  4966.1  396.22  4976.1  395.42    4983  390.41
    4988   394.2  4996.1  385.87  5013.1  381.83  5015.9  381.33  5019.1  381.83
  5026.1  384.81  5036.1  393.35  5056.1  396.03  5127.8  392.79    5174  395.81
  5432.7  395.68  5749.7  401.62  5908.2  408.99  6193.6  430.68  6210.1  432.46
#Mann= 15 ,-1 , 0
  2490.2     .12       0  2696.5     .16       0  2794.2     .12       0
  2950.2     .16       0  3097.9     .12       0  3103.9     .16       0
  3267.9     .12       0    3354     .16       0  3361.5     .12       0
  3472.4     .05       0    4781     .16       0  5013.1     .07       0
  5019.1     .16       0  5127.8     .05       0  6193.6     .16       0
Bank Sta=4988,5036.1
XS Rating Curve= 0 ,0
Exp/Cntr=0.3,0.1

Type RM Length L Ch R = 1 ,64641   ,393,393,393
BEGIN DESCRIPTION:
FAULKENBERRY CREEK 10.0
END DESCRIPTION:
XS GIS Cut Line= 3
      3486392.11     10530141.64      3489292.11     10529141.64
       3489342.1     10527691.67
#Sta/Elev= 30
  1894.8  419.96  1974.9   419.9  2183.6  418.64  2385.7  412.59  2491.7  411.87
  2793.9  400.13  2893.1  393.47  3128.1  393.47  3438.9  391.98  3594.9  394.07
  4704.3  395.02  4821.9  395.22  4827.2  392.32    4846  395.46  4972.4  394.07
  4999.4  380.68  5002.1  380.18  5005.4  380.68  5022.4  383.97  5032.4  394.85
  5086.7  394.72  5132.5  392.61  5222.5  394.24  5402.6  401.91  5682.8   399.6
  5912.9  408.59  6126.7   422.9  6254.4  433.03  6352.4  442.82  6413.2  446.72
#Mann= 13 ,-1 , 0
  1894.8     .16       0  1974.9     .12       0  2183.6     .16       0
  2385.7     .12       0  2491.7     .16       0  3128.1     .05       0
  4704.3     .16       0  4999.4     .07       0  5005.4     .16       0
  5086.7     .05       0  6126.7     .16       0  6254.4     .12       0
  6352.4     .16       0
Bank Sta=4972.4,5032.4
XS Rating Curve= 0 ,0
Exp/Cntr=0.3,0.1

Type RM Length L Ch R = 1 ,64248   ,867,867,867
BEGIN DESCRIPTION:
FAULKENBERRY CREEK 9.0
END DESCRIPTION:
XS GIS Cut Line= 5
      3488523.43     10533248.07      3489238.83     10529453.73
      3489668.16     10529417.52      3489794.38     10529099.57
      3490454.11     10528196.77
#Sta/Elev= 30
   885.5  419.63  1187.2  411.61  1231.1  409.02  1248.2  405.36    1350  401.46
  1594.2  395.23  1828.3  392.92  2489.7  391.48  3527.7  392.96  3551.6  390.49
  3578.6  392.78  4097.5  392.55  4351.9  389.92  4468.3  392.32  4839.2  393.41
  4970.8  394.27  4990.8  381.97  4997.9   381.1  5000.6   380.6  5003.9   381.1
    5041  393.66  5264.8  393.53  5470.9  393.75  5881.3  400.87  6146.9  407.69
  6339.3  417.88  6439.6  428.39  6532.7  441.13  6582.2  441.81  6637.8   439.5
#Mann= 5 ,-1 , 0
   885.5     .05       0  4839.2     .16       0  4997.9     .07       0
  5003.9     .16       0  5264.8     .05       0
#XS Ineff= 2 , 0
         3568.21  392.74
Permanent Ineff=
       F       F
Bank Sta=4970.8,5041
XS Rating Curve= 0 ,0
Exp/Cntr=0.3,0.1

Type RM Length L Ch R = 1 ,63381   ,855,855,855
BEGIN DESCRIPTION:
FAULKENBERRY CREEK 11.0
END DESCRIPTION:
XS GIS Cut Line= 3
      3488922.72     10533387.02       3490004.1     10529473.89
      3490781.89     10528564.16
#Sta/Elev= 30
  1282.7  414.84  1749.8  404.39  2024.9  395.12  2203.3  392.18  2651.6  390.61
  4346.9  391.07  4400.7  387.94  4421.5  390.31  4600.8  389.69  4813.1  392.39
    4961  393.82  4971.3  391.36  4977.4  386.81  4992.1  381.18  4999.5  381.11
  5002.2  380.61  5005.5  381.11    5017  385.96  5023.2  391.63  5033.6  393.76
  5130.3  392.99  5158.1  389.82  5189.2  392.43  5269.8  392.84  5704.2  398.16
  5761.3  402.06  6165.2  413.16  6187.2  415.46  6300.3  418.56  6539.4  431.33
#Mann= 7 ,-1 , 0
  1282.7     .05       0  4346.9     .16       0  4600.8     .05       0
  4813.1     .16       0  4999.5     .07       0  5005.5     .16       0
  5269.8     .05       0
#XS Ineff= 2 , 0
         4421.44  390.32
Permanent Ineff=
       F       F
Bank Sta=4971.3,5023.2
XS Rating Curve= 0 ,0
Exp/Cntr=0.3,0.1

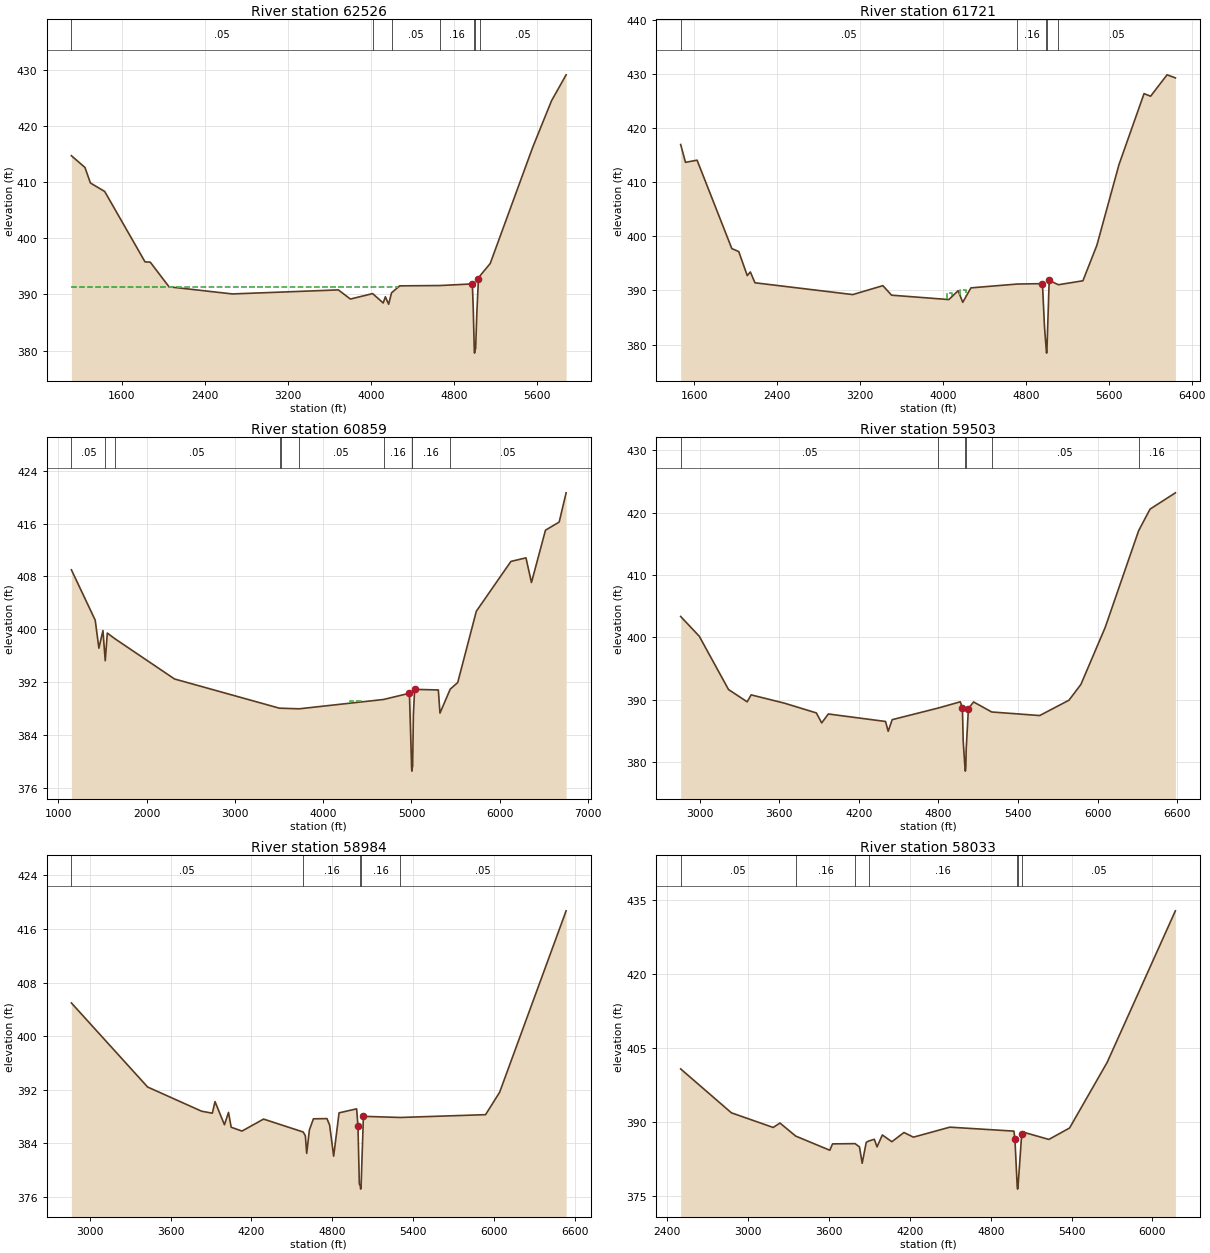
Type RM Length L Ch R = 1 ,62526   ,805,805,805
BEGIN DESCRIPTION:
FAULKENBERRY CREEK 10.1
END DESCRIPTION:
XS GIS Cut Line= 4
      3489118.04     10533395.67        3490154.     10530252.06
      3490781.88     10529890.56      3491182.45     10529275.63
#Sta/Elev= 30
  1113.8  414.73  1244.4  412.64    1297  409.87  1434.7  408.36  1823.5  395.81
  1874.2  395.75  2055.1  391.36  2665.8  390.09  3687.1  390.81  3802.9  389.18
  4017.3  390.15  4119.1  388.48  4139.9  389.59  4171.5  388.25  4199.2  390.29
  4277.9  391.53  4667.5  391.59  4978.4  391.88  4986.9  387.52    4997  380.04
  4999.7  379.54    5003  380.04    5010  380.35  5021.5   386.7  5037.3  392.83
  5054.3  393.37  5150.6  395.52  5559.8  416.22  5740.9  424.51  5882.1  429.15
#Mann= 7 ,-1 , 0
  1113.8     .05       0  4017.3     .16       0  4199.2     .05       0
  4667.5     .16       0    4997     .07       0    5003     .16       0
  5054.3     .05       0
#XS Ineff= 2 , 0
         4255.68   391.4
Permanent Ineff=
       F       F
Bank Sta=4978.4,5037.3
XS Rating Curve= 0 ,0
Exp/Cntr=0.3,0.1

Type RM Length L Ch R = 1 ,61721   ,862,862,862
BEGIN DESCRIPTION:
FAULKENBERRY CREEK 9.1
END DESCRIPTION:
XS GIS Cut Line= 5
      3489335.07     10533326.19      3490823.54     10530355.84
      3491212.43     10530390.56      3491288.82     10530182.23
      3491441.52     10529356.28
#Sta/Elev= 30
  1468.4  416.95  1515.1  413.66  1626.8  414.06    1962  397.74  2029.1  397.18
    2111  392.75  2140.8  393.42  2185.5  391.42  3129.6  389.24  3420.1  390.89
  3503.9  389.13  4056.9  388.32  4146.3  389.96    4191  387.81  4269.8  390.48
  4718.3  391.19  4960.1  391.26  4980.1  383.19  4997.2  378.93    5000  378.43
  5003.2  378.93    5025  391.85    5114  391.06  5350.5  391.79  5485.1  398.33
  5698.7  413.24  5940.7  426.35  6003.8  425.87  6162.6  429.82  6243.1  429.26
#Mann= 5 ,-1 , 0
  1468.4     .05       0  4718.3     .16       0  4997.2     .07       0
  5003.2     .16       0    5114     .05       0
#XS Ineff= 2 ,-1
  4037.5 4085.23   389.6 4163.64    4225  390.05
Permanent Ineff=
       F       F
Bank Sta=4960.1,5025
XS Rating Curve= 0 ,0
Exp/Cntr=0.3,0.1

Type RM Length L Ch R = 1 ,60859   ,1356,1356,1356
BEGIN DESCRIPTION:
FAULKENBERRY CREEK 8.0
END DESCRIPTION:
XS GIS Cut Line= 4
      3490359.38     10534185.55      3491545.07     10530802.78
      3491795.77     10530307.23      3491934.65     10528848.93
#Sta/Elev= 30
  1147.4     409  1417.2  401.39  1458.8  397.16  1504.9  399.82  1530.8  395.26
  1554.2  399.44  1638.6   398.6  2315.7   392.5  3505.5  388.08  3522.1  388.08
  3727.1  387.99  4683.4   389.4  4977.1  390.34    5002  379.07  5004.8  378.57
    5008  379.07  5013.4  379.28  5021.7  387.06  5035.8  390.93  5304.7  390.84
    5323  387.34    5439  390.96    5524  391.96  5734.9  402.74  6126.7  410.27
  6297.4  410.81  6359.5  407.08  6518.4  414.99  6673.4  416.22  6752.2  420.64
#Mann= 10 ,-1 , 0
  1147.4     .05       0  1530.8     .16       0  1638.6     .05       0
  3505.5     .12       0  3522.1     .16       0  3727.1     .05       0
  4683.4     .16       0    5002     .07       0    5008     .16       0
    5439     .05       0
#XS Ineff= 1 ,-1
 4303.41 4432.95  389.15
Permanent Ineff=
       F
Bank Sta=4977.1,5035.8
XS Rating Curve= 0 ,0
Exp/Cntr=0.3,0.1

Type RM Length L Ch R = 1 ,59503   ,519,519,519
BEGIN DESCRIPTION:
FAULKENBERRY CREEK 7.1
END DESCRIPTION:
XS GIS Cut Line= 4
      3492472.92     10533451.48       3492313.2     10531569.58
      3492486.81     10531215.42      3492597.92     10529770.98
#Sta/Elev= 30
  2855.3  403.36  2995.6   400.2  3216.4  391.66  3356.9   389.7    3387  390.81
  3638.2  389.48  3878.8  387.92    3919  386.32  3969.1  387.75  4400.7  386.55
  4420.7  384.98  4450.9  386.84  4799.4  388.71  4964.4   389.7  4980.6  388.76
  4986.7  383.35  5000.1   379.1  5002.8   378.6  5006.1   379.1    5009  382.07
  5025.6  388.59  5064.6  389.68  5201.5  388.07  5563.4   387.5  5784.1  389.95
  5874.3  392.48  6057.4   401.6    6310   417.1  6395.9  420.55  6587.1  423.16
#Mann= 6 ,-1 , 0
  2855.3     .05       0  4799.4     .16       0  5000.1     .07       0
  5006.1     .16       0  5201.5     .05       0    6310     .16       0
Bank Sta=4980.6,5025.6
XS Rating Curve= 0 ,0
Exp/Cntr=0.3,0.1

Type RM Length L Ch R = 1 ,58984   ,951,951,951
BEGIN DESCRIPTION:
FAULKENBERRY CREEK 6.6
END DESCRIPTION:
XS GIS Cut Line= 4
      3492774.93      10533716.9      3492839.41     10531641.87
      3492733.27      10530772.5      3492809.65     10530057.23
#Sta/Elev= 30
  2864.1  404.95  3429.6   392.4  3829.8  388.79  3909.9  388.49  3929.9  390.22
  3999.9  386.76  4029.9  388.61  4049.9  386.39    4130  385.82  4290.1  387.61
  4584.3  385.68  4600.2  385.12  4610.2  382.49  4630.2     386  4660.2  387.65
  4760.3  387.68  4780.3  386.73  4810.3  382.07  4850.3  388.54  4980.7  389.14
  4990.7   386.6  5000.8   377.9  5007.9  377.65  5010.6  377.15  5013.9  377.65
    5031  388.02  5304.5  387.85  5937.5  388.27  6041.8  391.61  6535.3  418.71
#Mann= 5 ,-1 , 0
  2864.1     .05       0  4584.3     .16       0  5007.9     .07       0
  5013.9     .16       0  5304.5     .05       0
Bank Sta=4990.7,5031
XS Rating Curve= 0 ,0
Exp/Cntr=0.3,0.1

Type RM Length L Ch R = 1 ,58033   ,575,575,575
BEGIN DESCRIPTION:
FAULKENBERRY CREEK 6.5
END DESCRIPTION:
XS GIS Cut Line= 4
      3493080.49     10533578.02      3493144.97     10531502.98
      3493038.82     10530633.62      3493115.21     10529918.35
#Sta/Elev= 30
  2498.9  400.77  2875.5  391.89  3185.6  388.93  3235.6  389.83  3352.4  387.19
  3605.8  384.32  3625.8  385.61  3793.4  385.66  3825.9  384.99  3845.9  381.69
  3875.9  385.92  3892.8  386.17    3936  386.54    3956     385  3995.4  387.41
    4066  386.05  4156.1  387.91  4226.1  386.97  4496.2  388.99    4972  388.19
  4979.3  386.61  4996.4  376.96  4999.2  376.46  5002.4  376.96  5029.6  387.63
    5035  388.03  5231.1  386.51  5384.8  388.82  5663.9   402.1  6170.1  432.74
#Mann= 7 ,-1 , 0
  2498.9     .05       0  3352.4     .16       0  3793.4     .12       0
  3892.8     .16       0  4996.4     .07       0  5002.4     .16       0
    5035     .05       0
Bank Sta=4979.3,5029.6
XS Rating Curve= 0 ,0
Exp/Cntr=0.3,0.1

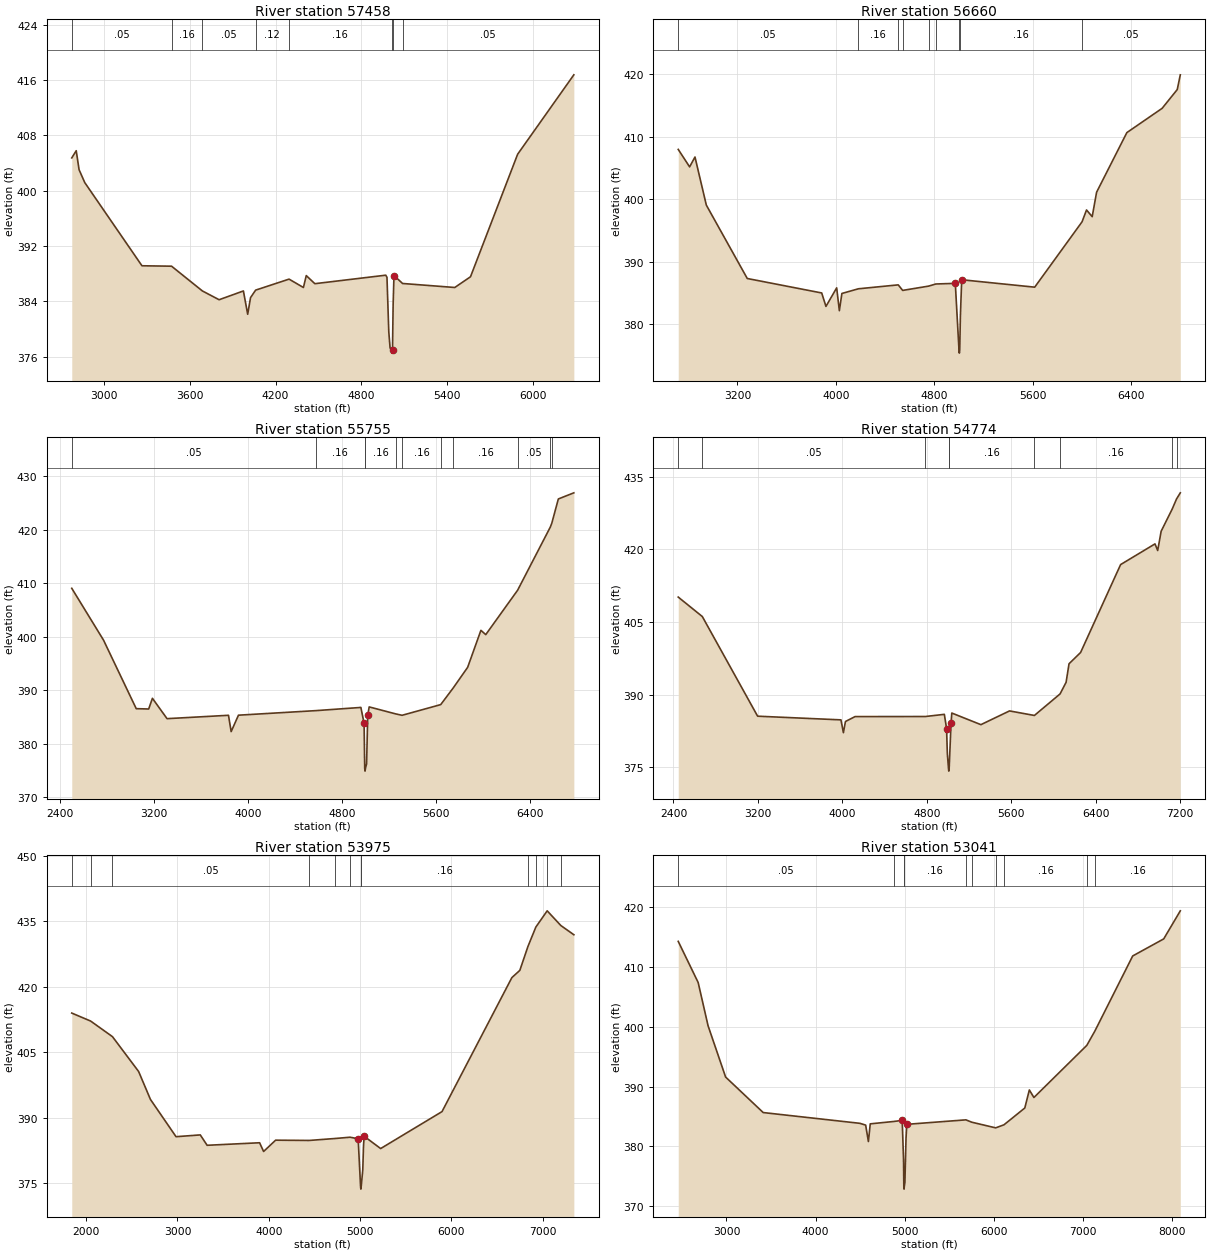
Type RM Length L Ch R = 1 ,57458   ,798,798,798
BEGIN DESCRIPTION:
FAULKENBERRY CREEK 6.4
END DESCRIPTION:
XS GIS Cut Line= 4
      3493330.49     10533612.81      3493344.38     10531626.67
      3493580.49     10531258.62      3493594.38     10530168.37
#Sta/Elev= 30
  2773.5  404.76  2804.7   405.8  2824.7  403.05  2864.7  401.18  3264.7  389.16
  3471.9   389.1  3687.7  385.52  3804.7  384.25  3974.7  385.52  4004.7  382.15
  4024.7  384.56  4060.3  385.64  4294.3  387.23  4394.7  386.02  4414.7  387.74
  4474.7  386.57    4971   387.8  4979.5  387.49  4992.2  379.61  5001.4  377.26
  5012.2  377.03  5014.9  376.53  5018.2  377.03  5022.6  383.54  5028.5  387.75
  5088.7   386.6    5454  386.02    5564  387.57    5894  405.29  6287.3  416.77
#Mann= 8 ,-1 , 0
  2773.5     .05       0  3471.9     .16       0  3687.7     .05       0
  4060.3     .12       0  4294.3     .16       0  5012.2     .07       0
  5018.2     .16       0  5088.7     .05       0
Bank Sta=5018.2,5028.5
XS Rating Curve= 0 ,0
Exp/Cntr=0.3,0.1

Type RM Length L Ch R = 1 ,56660   ,905,905,905
BEGIN DESCRIPTION:
FAULKENBERRY CREEK 7.0
END DESCRIPTION:
XS GIS Cut Line= 5
      3493397.55     10533768.96      3493865.21     10531661.39
      3494142.99     10531578.06      3494212.43     10531223.89
      3493900.18     10529995.71
#Sta/Elev= 30
  2719.4  407.99  2811.8  405.19  2855.4  406.77  2947.6  399.06    3280   387.3
  3884.4  384.98  3918.9  382.83    4006   385.8  4027.8  382.14  4048.3   384.9
  4182.2  385.65  4505.9  386.28  4541.8  385.39  4752.5  386.08  4811.4  386.42
  4969.3  386.52  4999.3  375.84  5002.1  375.34  5005.3  375.84  5010.7  381.35
  5021.2   387.1    5614  385.91  5998.7  396.39  6034.8  398.28  6080.9  397.21
  6116.7  401.13  6362.3  410.68  6648.8  414.57  6771.6  417.58  6796.4  419.94
#Mann= 9 ,-1 , 0
  2719.4     .05       0  4182.2     .16       0  4505.9     .12       0
  4541.8     .16       0  4752.5     .05       0  4811.4     .16       0
  4999.3     .07       0  5005.3     .16       0  5998.7     .05       0
Bank Sta=4969.3,5021.2
XS Rating Curve= 0 ,0
Exp/Cntr=0.3,0.1

Type RM Length L Ch R = 1 ,55755   ,981,981,981
BEGIN DESCRIPTION:
FAULKENBERRY CREEK 6.3
END DESCRIPTION:
XS GIS Cut Line= 5
      3493475.69     10533838.35      3494156.75     10531915.64
      3494434.66     10531661.39      3494608.27     10531557.23
      3494205.94     10529954.86
#Sta/Elev= 30
  2503.1  409.06  2773.5  399.35  3051.5  386.53  3157.4  386.47  3189.2  388.47
  3313.6  384.66  3836.3  385.29    3859  382.24  3921.2  385.31    4578  386.16
  4962.5  386.76  4989.7  383.79  4995.2  375.34  4997.9  374.84  5001.2  375.34
  5011.1   376.2  5020.8  385.29  5033.2  386.86  5257.3  385.56  5313.1  385.29
  5641.6  387.29  5748.7  390.43  5870.6  394.26  5983.5  401.19  6024.8  400.39
  6295.8   408.7  6574.2  420.53  6586.9  421.27  6642.2  425.78  6774.1  426.93
#Mann= 11 ,-1 , 0
  2503.1     .05       0    4578     .16       0  4995.2     .07       0
  5001.2     .16       0  5257.3     .05       0  5313.1     .16       0
  5641.6     .05       0  5748.7     .16       0  6295.8     .05       0
  6574.2     .16       0  6586.9     .05       0
Bank Sta=4989.7,5020.8
XS Rating Curve= 0 ,0
Exp/Cntr=0.3,0.1

Type RM Length L Ch R = 1 ,54774   ,799,799,799
BEGIN DESCRIPTION:
FAULKENBERRY CREEK 6.2
END DESCRIPTION:
XS GIS Cut Line= 5
      3493493.03     10534046.73      3494109.36     10532388.72
      3494483.27     10532091.95      3494913.82     10531668.34
      3494365.22     10529841.99
#Sta/Elev= 30
  2444.9  410.15    2673  406.13  3197.1  385.52  3986.6  384.76  4009.8  382.11
  4029.3  384.42  4120.6  385.44  4784.3  385.45  4966.3   385.9  4987.5  382.96
  4994.6  377.82  5005.8  374.66  5008.5  374.16  5011.8  374.66  5029.9  384.07
    5037  386.17  5312.6  383.77    5584  386.61  5819.6  385.67  6062.6  390.12
  6119.9  392.53  6147.7  396.36  6257.3  398.69  6636.4  416.87  6962.3  421.15
  6987.7  419.78  7020.7  423.77    7126  428.39  7166.1  430.43  7202.1  431.71
#Mann= 9 ,-1 , 0
  2444.9     .16       0    2673     .05       0  4784.3     .16       0
  5005.8     .07       0  5011.8     .16       0  5819.6     .05       0
  6062.6     .16       0    7126     .12       0  7166.1     .05       0
Bank Sta=4987.5,5029.9
XS Rating Curve= 0 ,0
Exp/Cntr=0.3,0.1

Type RM Length L Ch R = 1 ,53975   ,934,934,934
BEGIN DESCRIPTION:
FAULKENBERRY CREEK 5.3
END DESCRIPTION:
XS GIS Cut Line= 6
      3493527.76     10534567.54      3494475.67     10532463.35
       3495004.1     10532161.39      3495219.38     10531848.89
      3495149.93     10530994.73      3494615.22     10529758.64
#Sta/Elev= 30
  1842.1  413.97  2048.7  412.14  2287.6  408.57  2574.4  400.58  2704.1  394.17
  2984.3  385.63  3249.8  386.04  3324.7  383.66  3899.6  384.24  3943.4  382.24
    4075  384.83    4443  384.77  4722.4  385.21  4890.4  385.51  4979.1  385.15
  5005.9  374.11  5008.7  373.61  5011.9  374.11  5029.9  378.05  5037.5  383.39
  5044.8  385.73  5225.6  382.91  5897.8  391.38    6663   422.1  6750.2  423.76
  6838.7  429.22  6925.5  433.68  7049.8  437.41  7199.5  434.04  7341.8  431.93
#Mann= 12 ,-1 , 0
  1842.1     .05       0  2048.7     .16       0  2287.6     .05       0
    4443     .16       0  4722.4     .12       0  4890.4     .16       0
  5005.9     .07       0  5011.9     .16       0  6838.7     .12       0
  6925.5     .16       0  7049.8     .12       0  7199.5     .16       0
Bank Sta=4979.1,5044.8
XS Rating Curve= 0 ,0
Exp/Cntr=0.3,0.1

Type RM Length L Ch R = 1 ,53041   ,1040,1040,1040
BEGIN DESCRIPTION:
FAULKENBERRY CREEK 5.2
END DESCRIPTION:
XS GIS Cut Line= 5
      3494239.57     10534819.25      3494769.73     10532567.64
      3495108.27     10532341.95      3495531.88     10532050.28
      3494997.14     10529709.96
#Sta/Elev= 30
  2458.9  414.31  2682.5  407.43  2793.8  400.19  2990.7  391.61  3412.5  385.67
  4497.3  383.87  4562.5  383.57  4593.3  380.82  4613.9  383.78  4878.2  384.18
  4972.7  384.36  4987.7  377.74  4990.7  373.36  4993.5  372.86  4996.7  373.36
  5002.8  373.97  5015.3  381.29  5023.8   383.7  5687.8  384.45  5752.6  384.06
  6021.5  383.11  6114.6  383.62  6348.4  386.43  6399.7  389.45  6450.9  388.19
  7044.5  396.91  7134.8   399.3  7559.6  411.87  7907.5  414.72  8093.9  419.42
#Mann= 10 ,-1 , 0
  2458.9     .05       0  4878.2     .16       0  4990.7     .07       0
  4996.7     .16       0  5687.8     .05       0  5752.6     .16       0
  6021.5     .05       0  6114.6     .16       0  7044.5     .12       0
  7134.8     .16       0
Bank Sta=4972.7,5023.8
XS Rating Curve= 0 ,0
Exp/Cntr=0.3,0.1

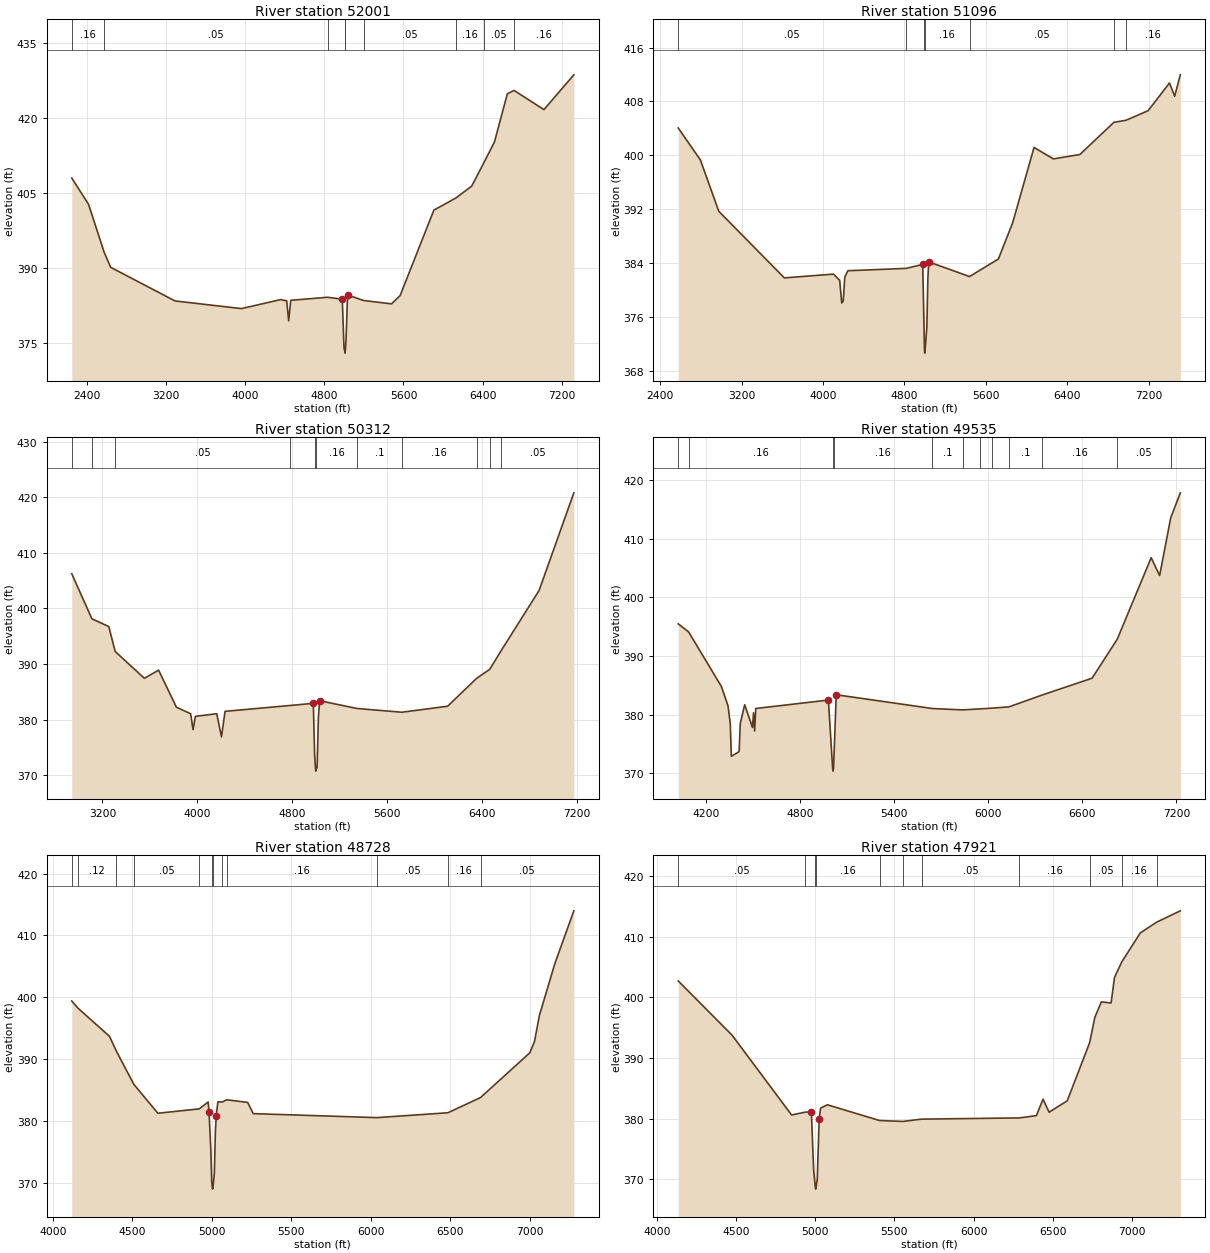
Type RM Length L Ch R = 1 ,52001   ,905,905,905
BEGIN DESCRIPTION:
FAULKENBERRY CREEK 4.3
END DESCRIPTION:
XS GIS Cut Line= 4
      3495194.44     10534888.67       3495754.1       10531835.
      3495858.27     10530828.06      3495886.04     10529869.71
#Sta/Elev= 30
  2247.1  407.96  2416.9  402.69  2574.9  393.08  2640.6  390.09  3291.2  383.36
  3962.2  381.83  4358.7  383.63  4419.7  383.39  4440.1  379.39  4460.4  383.49
  4833.1   384.1    4982  383.71  4999.2  373.91  5006.4  373.42  5009.1  372.92
  5012.4  373.42  5019.5  375.46  5035.1  384.55  5197.7  383.45  5479.3  382.78
  5566.1  384.42  5907.9  401.54  6130.9  403.97    6290  406.34  6411.9  410.97
  6520.4  415.19  6650.5  424.82  6717.7  425.49  7020.6  421.65  7322.7  428.61
#Mann= 9 ,-1 , 0
  2247.1     .16       0  2574.9     .05       0  4833.1     .16       0
  5006.4     .07       0  5012.4     .16       0  5197.7     .05       0
  6130.9     .16       0  6411.9     .05       0  6717.7     .16       0
Bank Sta=4982,5035.1
XS Rating Curve= 0 ,0
Exp/Cntr=0.3,0.1

Type RM Length L Ch R = 1 ,51096   ,784,784,784
BEGIN DESCRIPTION:
FAULKENBERRY CREEK 4.2
END DESCRIPTION:
XS GIS Cut Line= 4
      3496027.77      10534567.5      3496267.99     10532411.39
      3496344.38     10531841.95       3496388.3     10529655.38
#Sta/Elev= 30
    2578  404.07  2795.2  399.34  2976.3  391.71  3620.3  381.83  4102.8  382.39
  4163.6  381.47  4183.7  378.11  4198.2  378.36  4213.9  381.95  4244.1  382.89
    4815  383.24  4979.3  383.82  4996.4  371.17  4999.2  370.67  5002.4  371.17
  5019.6   374.5  5029.7  381.72  5038.2   384.2    5439  382.03  5722.4  384.63
  5862.4     390  6072.5  401.18  6262.5  399.48  6522.5  400.13    6857  404.91
  6974.2   405.2  7192.7  406.63  7402.7  410.74  7453.6  408.77    7509  411.95
#Mann= 7 ,-1 , 0
    2578     .05       0    4815     .16       0  4996.4     .07       0
  5002.4     .16       0    5439     .05       0    6857      .1       0
  6974.2     .16       0
Bank Sta=4979.3,5038.2
XS Rating Curve= 0 ,0
Exp/Cntr=0.3,0.1

Type RM Length L Ch R = 1 ,50312   ,777,777,777
BEGIN DESCRIPTION:
FAULKENBERRY CREEK 3.3
END DESCRIPTION:
XS GIS Cut Line= 4
      3496670.12     10534393.89      3496663.82     10532654.45
      3496823.54     10532161.39      3496934.66     10530189.15
#Sta/Elev= 30
  2941.7  406.23  3111.6  398.13  3253.9  396.73  3307.8  392.25  3553.9  387.43
  3673.9   388.9    3824  382.23    3944  381.06    3964   378.2    3984  380.59
    4164  381.06    4204   376.9    4234  381.49  4781.3  382.54  4978.4  382.93
    4989  373.86  4996.4  371.24  4999.2  370.74  5002.4  371.24    5010  371.32
    5021   380.4    5031   383.4  5347.1     382  5724.8  381.33  6110.6  382.41
  6356.6  387.45  6465.5  389.04  6563.5  392.45  6881.8  403.22  7174.8  420.78
#Mann= 11 ,-1 , 0
  2941.7     .05       0  3111.6      .1       0  3307.8     .05       0
  4781.3     .16       0  4996.4     .07       0  5002.4     .16       0
  5347.1      .1       0  5724.8     .16       0  6356.6     .12       0
  6465.5     .16       0  6563.5     .05       0
Bank Sta=4978.4,5031
XS Rating Curve= 0 ,0
Exp/Cntr=0.3,0.1

Type RM Length L Ch R = 1 ,49535   ,807,807,807
BEGIN DESCRIPTION:
FAULKENBERRY CREEK 3.2
END DESCRIPTION:
XS GIS Cut Line= 4
      3497719.36     10533223.87      3497261.04     10532751.67
      3497261.04     10532293.34      3497136.04     10530209.97
#Sta/Elev= 30
  4021.1  395.48  4087.1  394.11  4296.5  384.81    4339  381.48  4353.1   378.5
  4360.1  372.92  4409.7  373.72  4416.7  378.47    4445   381.7  4494.6  377.84
  4501.6  380.32  4508.7  377.24  4515.7  381.06  4979.2  382.49  5006.2  370.89
  5008.9  370.39  5012.2  370.89  5029.2   383.4  5642.9  381.05  5835.1  380.82
  5946.6  380.99  6022.1  381.12  6130.6  381.33  6342.9  383.35  6661.9  386.22
  6822.3  392.86  7038.7  406.74  7092.7   403.7  7163.5  413.54  7224.6  417.79
#Mann= 12 ,-1 , 0
  4021.1     .12       0  4087.1     .16       0  5006.2     .07       0
  5012.2     .16       0  5642.9      .1       0  5835.1     .05       0
  5946.6      .1       0  6022.1     .05       0  6130.6      .1       0
  6342.9     .16       0  6822.3     .05       0  7163.5     .16       0
Bank Sta=4979.2,5029.2
XS Rating Curve= 0 ,0
Exp/Cntr=0.3,0.1

Type RM Length L Ch R = 1 ,48728   ,807,807,807
BEGIN DESCRIPTION:
FAULKENBERRY CREEK 6.1
END DESCRIPTION:
XS GIS Cut Line= 3
      3498261.05     10533258.62      3497719.38     10532140.56
      3497365.22     10530258.66
#Sta/Elev= 30
  4119.1  399.39  4157.9  398.23  4356.1  393.68  4398.7  391.32  4509.9  385.88
  4660.7  381.22    4921  381.93  4976.8  383.04  4982.5  381.37  4993.6  375.25
  4999.4  370.06    5002  369.44  5004.7  368.94    5008  369.44  5015.8  371.51
    5022  378.08  5027.6  380.81    5038  383.07  5065.6  383.04  5094.3   383.4
  5225.2  382.97  5260.3  381.16  6037.6  380.51  6484.8   381.3  6689.5  383.76
  6999.8  391.01  7029.2  392.86  7059.7  397.03  7157.2  405.46  7276.4  413.98
#Mann= 12 ,-1 , 0
  4119.1     .16       0  4157.9     .12       0  4398.7     .16       0
  4509.9     .05       0    4921     .16       0    5002     .07       0
    5008     .16       0  5065.6     .08       0  5094.3     .16       0
  6037.6     .05       0  6484.8     .16       0  6689.5     .05       0
Bank Sta=4982.5,5027.6
XS Rating Curve= 0 ,0
Exp/Cntr=0.3,0.1

Type RM Length L Ch R = 1 ,47921   ,950,950,950
BEGIN DESCRIPTION:
FAULKENBERRY CREEK 5.1
END DESCRIPTION:
XS GIS Cut Line= 4
      3498941.58     10533001.63      3498656.88     10532376.67
      3498476.32     10532071.12      3498003.86     10529995.58
#Sta/Elev= 30
    4135   402.7  4475.6  393.75  4850.8  380.62  4936.7  381.09  4975.7  381.14
  4990.2  371.51  4999.9  368.91  5002.7  368.41  5005.9  368.91  5012.8  369.98
  5025.1  380.03  5034.2  381.76  5077.1   382.3  5405.9  379.71  5554.5  379.56
  5671.5  379.94  6289.5  380.14  6396.6  380.52  6438.7  383.23  6476.6  381.08
  6591.4  382.96  6732.6  392.52  6765.8  396.72  6806.8  399.25  6868.3  399.07
  6889.6  403.26  6935.7  405.84  7052.9  410.62  7156.5  412.39  7305.3  414.25
#Mann= 11 ,-1 , 0
    4135     .05       0  4936.7     .16       0  4999.9     .07       0
  5005.9     .16       0  5405.9     .05       0  5554.5      .1       0
  5671.5     .05       0  6289.5     .16       0  6732.6     .05       0
  6935.7     .16       0  7156.5     .12       0
Bank Sta=4975.7,5025.1
XS Rating Curve= 0 ,0
Exp/Cntr=0.3,0.1