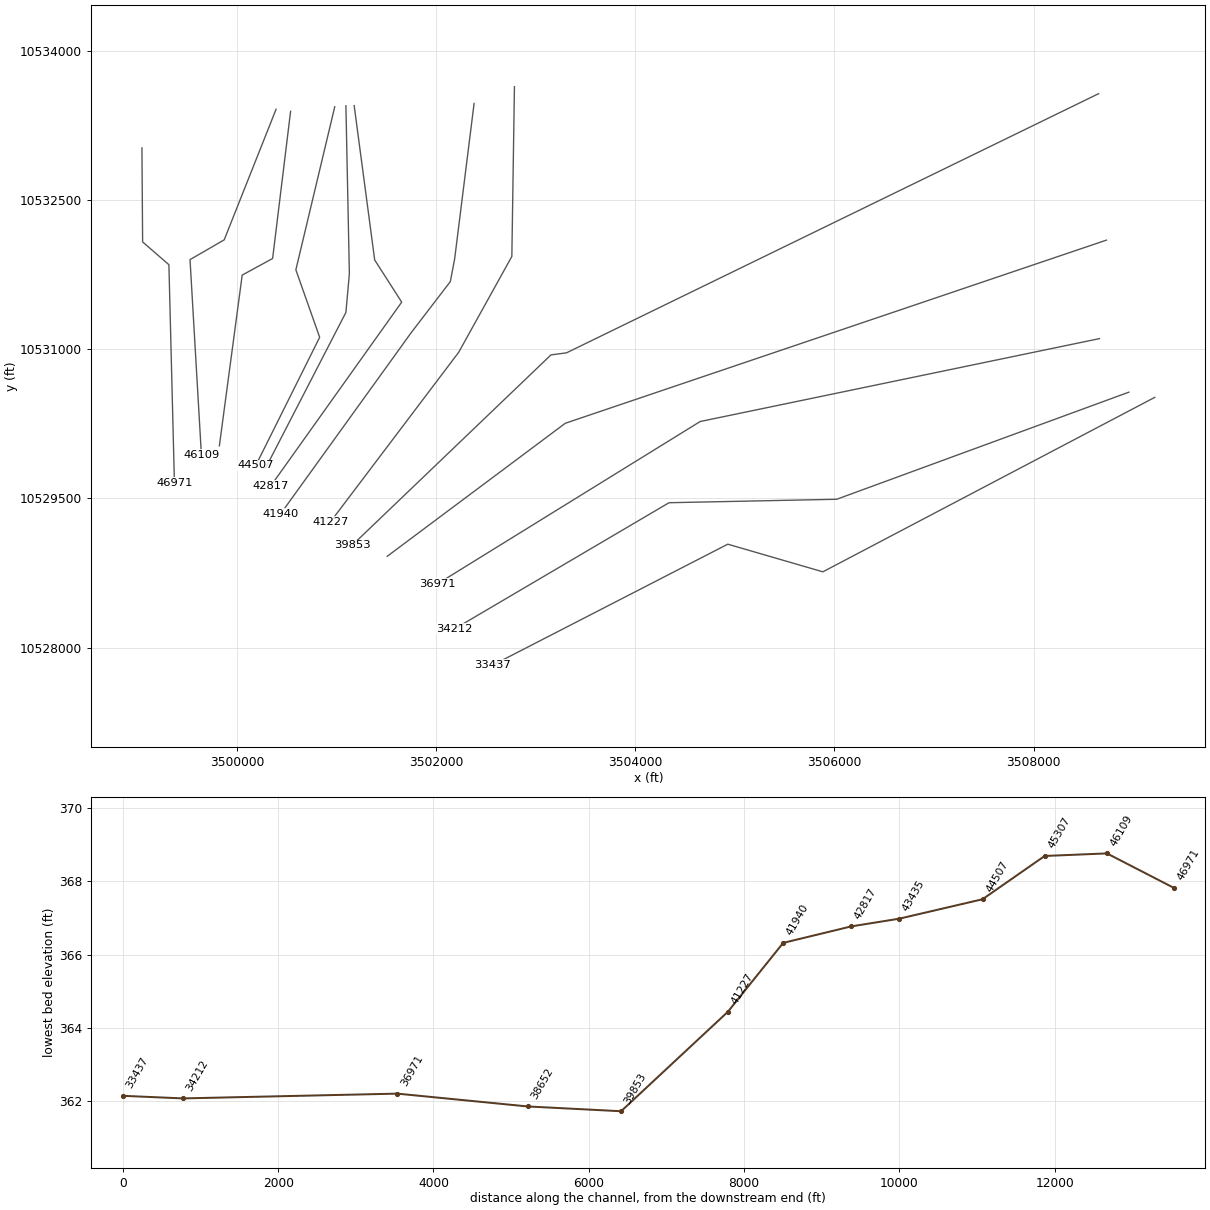
HEC-RAS study FAULKENBERRY CREEK.prj: FAULKENBERRY CREEK Base Level Engineering

--- FAULKENBERRY CREEK.g01 (geometry) --- (continued)

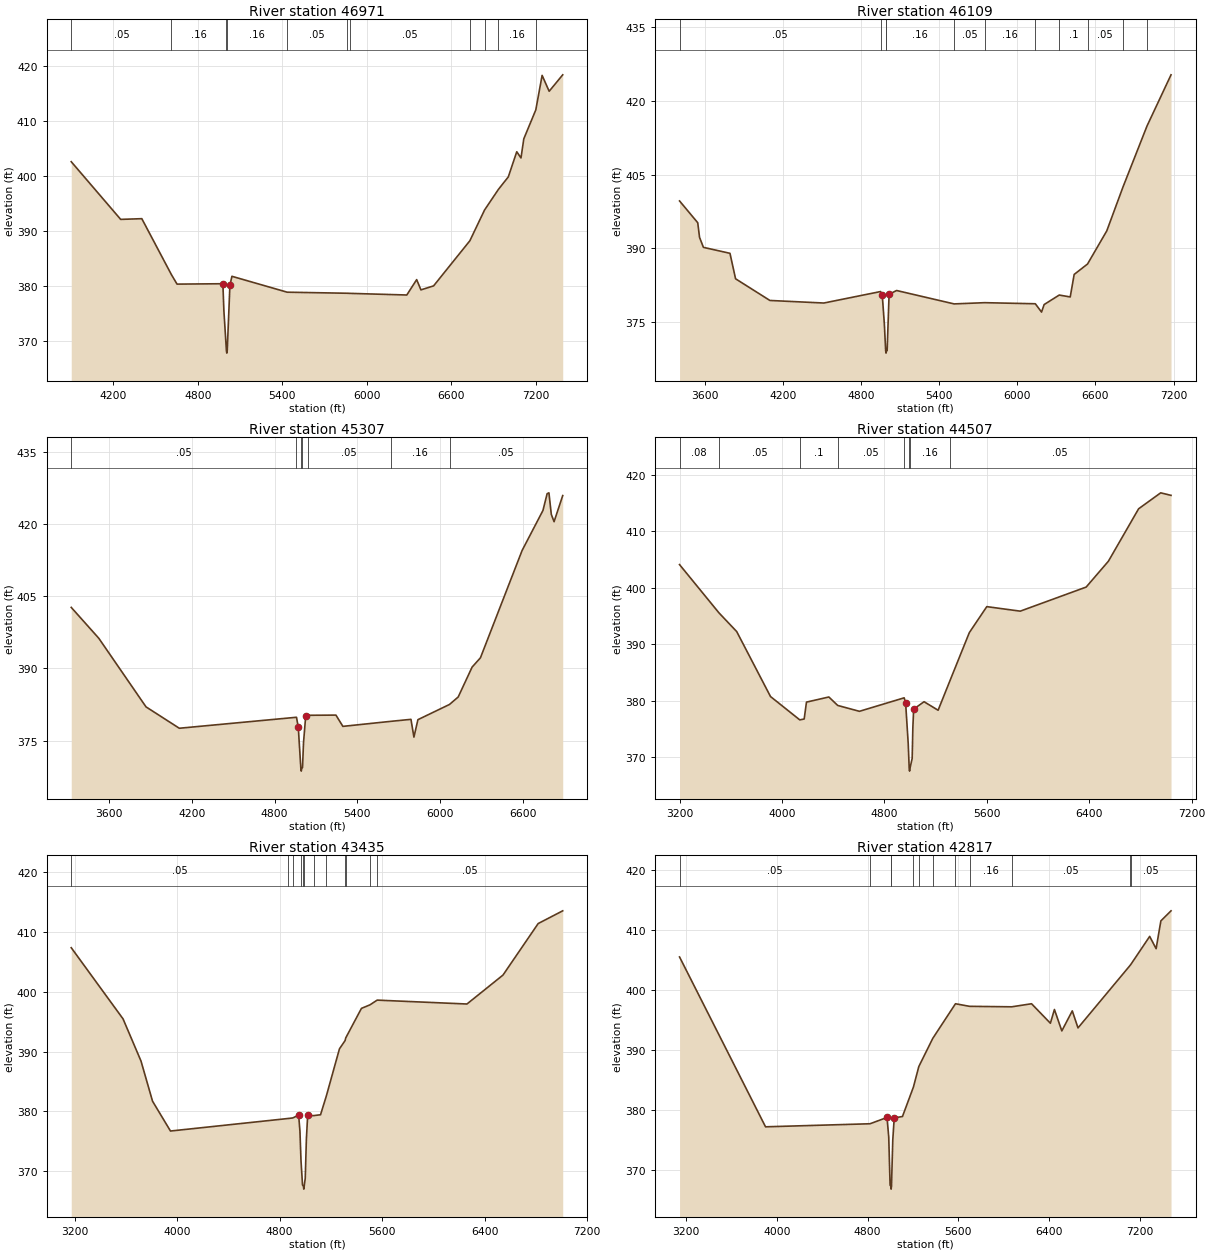
Type RM Length L Ch R = 1 ,46971   ,862,862,862
BEGIN DESCRIPTION:
FAULKENBERRY CREEK 4.1
END DESCRIPTION:
XS GIS Cut Line= 4
      3499045.77     10533022.55      3499052.71     10532078.06
       3499316.6     10531848.89      3499372.13     10529655.52
#Sta/Elev= 30
  3902.5  402.63  4253.4  392.14  4403.4  392.27    4614  382.07  4653.4  380.37
  4978.7  380.44  4985.9  375.51  5003.7  368.32  5006.5  367.82  5009.7  368.32
  5028.6  380.16  5042.9  381.79  5435.3   378.9  5859.5  378.71  5877.5  378.69
  6284.1  378.39  6354.1  381.19  6384.2  379.32  6474.2  380.05  6731.7  388.26
  6835.7  393.84  6933.7  397.58  7004.4  399.87  7064.4  404.44  7094.4  403.31
  7114.4  406.79  7199.6  412.06  7244.4  418.33  7294.4  415.44  7390.6  418.43
#Mann= 11 ,-1 , 0
  3902.5     .05       0    4614     .16       0  5003.7     .07       0
  5009.7     .16       0  5435.3     .05       0  5859.5     .16       0
  5877.5     .05       0  6731.7     .16       0  6835.7     .05       0
  6933.7     .16       0  7199.6     .05       0
Bank Sta=4978.7,5028.6
XS Rating Curve= 0 ,0
Exp/Cntr=0.3,0.1

Type RM Length L Ch R = 1 ,46109   ,802,802,802
BEGIN DESCRIPTION:
FAULKENBERRY CREEK 3.1
END DESCRIPTION:
XS GIS Cut Line= 4
      3500392.99     10533411.41      3499872.16     10532098.89
      3499528.79     10531900.17      3499642.99     10529939.19
#Sta/Elev= 30
  3407.9  399.65  3547.5  395.23  3561.5  392.25  3591.2  390.23    3795  389.02
    3838  383.85  4101.6  379.45  4515.8  378.93  4951.5  381.26  4964.3   380.5
  4980.1   374.7  4990.3  369.26  4993.1  368.76  4996.3  369.26  5001.6  369.28
  5016.5   380.7  5074.2  381.47  5515.6  378.75  5749.7     379  6139.2  378.78
  6186.9  377.09  6206.9  378.62  6322.9  380.55  6407.2  380.16  6437.3  384.73
    6540  386.85  6687.7  393.57  6811.9  402.46  6996.9  414.88    7181  425.25
#Mann= 11 ,-1 , 0
  3407.9     .05       0  4951.5     .16       0  4990.3     .07       0
  4996.3     .16       0  5515.6     .05       0  5749.7     .16       0
  6139.2     .05       0  6322.9      .1       0    6540     .05       0
  6811.9     .16       0  6996.9     .05       0
Bank Sta=4964.3,5016.5
XS Rating Curve= 0 ,0
Exp/Cntr=0.3,0.1

Type RM Length L Ch R = 1 ,45307   ,800,800,800
BEGIN DESCRIPTION:
FAULKENBERRY CREEK 6.0
END DESCRIPTION:
XS GIS Cut Line= 4
      3500538.82     10533390.53      3500358.27     10531911.39
      3500052.71     10531744.73      3499823.54     10530029.44
#Sta/Elev= 30
  3322.9  402.68  3523.3  396.26  3865.8  382.03  4107.6  377.59  4958.5  379.87
  4971.5  377.79  4990.3  369.19    4993  368.69  4996.3  369.19  5002.3  369.46
  5009.4  374.55  5025.1  380.04  5039.5  380.28  5244.9  380.32  5295.3  377.98
  5642.1  379.02  5789.7  379.44  5811.2  375.75  5840.1  379.37  6069.5  382.53
  6132.7  384.08  6233.6  390.28  6294.1  392.21  6596.8   414.5  6748.1   422.8
  6778.4  426.28  6791.4  426.46  6808.7  421.99  6828.8  420.47  6891.6  425.89
#Mann= 7 ,-1 , 0
  3322.9     .05       0  4958.5     .16       0  4990.3     .07       0
  4996.3     .16       0  5039.5     .05       0  5642.1     .16       0
  6069.5     .05       0
Bank Sta=4971.5,5025.1
XS Rating Curve= 0 ,0
Exp/Cntr=0.3,0.1

Type RM Length L Ch R = 1 ,44507   ,1072,1072,1072
BEGIN DESCRIPTION:
FAULKENBERRY CREEK 4.0
END DESCRIPTION:
XS GIS Cut Line= 4
      3500982.26     10533435.85      3500591.64     10531797.41
      3500830.74     10531119.48      3500190.95     10529835.02
#Sta/Elev= 30
  3200.2  404.11  3507.6  395.57  3646.6  392.24  3910.5  380.73  4139.3  376.59
  4173.5  376.75  4191.4  379.74  4366.2  380.65  4435.4  379.15    4605  378.11
  4954.3   380.5  4965.7  379.61    4986  372.37  4993.7  368.01  4996.5  367.51
  4999.7  368.01  5016.9  369.76  5022.2  375.27  5028.5   378.5  5109.7  379.81
  5219.4   378.3  5308.5  383.34  5463.3  392.06  5599.6  396.66  5860.9  395.86
  6375.8  400.13  6549.3  404.71  6785.2     414  6957.8  416.83  7038.4  416.38
#Mann= 8 ,-1 , 0
  3200.2     .08       0  3507.6     .05       0  4139.3      .1       0
  4435.4     .05       0  4954.3     .16       0  4993.7     .07       0
  4999.7     .16       0  5308.5     .05       0
Bank Sta=4965.7,5028.5
XS Rating Curve= 0 ,0
Exp/Cntr=0.3,0.1

Type RM Length L Ch R = 1 ,43435   ,618,618,618
BEGIN DESCRIPTION:
FAULKENBERRY CREEK 5.0
END DESCRIPTION:
XS GIS Cut Line= 4
      3501094.38     10533446.07       3501129.1     10531758.62
      3501094.38     10531369.73      3500288.81     10529807.21
#Sta/Elev= 30
  3173.5  407.37    3578  395.46    3718  388.41  3808.1  381.69  3948.1   376.7
  4867.9   378.8  4902.8  378.89  4948.6  379.36  4958.7  376.63  4966.8  371.78
  4978.8  367.66  4985.8  367.48  4988.5  366.98  4991.8  367.48    5000  368.78
  5008.9  375.35  5018.9  379.31  5065.6  379.28  5119.3  379.42  5164.5  382.55
    5267  390.45  5311.2  391.84  5315.9  392.27  5438.7  397.22  5504.9  397.81
  5561.6   398.6  6262.2  397.95  6543.4  402.79  6818.1  411.41  7009.7  413.54
#Mann= 12 ,-1 , 0
  3173.5     .05       0  4867.9     .12       0  4902.8     .16       0
  4966.8     .12       0  4985.8     .07       0  4991.8     .12       0
  5065.6     .16       0  5164.5     .12       0  5311.2     .16       0
  5315.9     .12       0  5504.9     .16       0  5561.6     .05       0
Bank Sta=4948.6,5018.9
XS Rating Curve= 0 ,0
Exp/Cntr=0.3,0.1

Type RM Length L Ch R = 1 ,42817   ,877,877,877
BEGIN DESCRIPTION:
FAULKENBERRY CREEK 3.0
END DESCRIPTION:
XS GIS Cut Line= 4
      3501177.28     10533447.85      3501383.44      10531896.2
      3501654.71     10531473.02      3500341.78     10529628.41
#Sta/Elev= 30
  3143.2  405.52  3901.1  377.17  4822.1  377.68    4972  378.73  4987.1  375.46
  4999.1  367.42  5005.3  367.27  5008.1  366.77  5011.3  367.27  5022.7  374.97
  5035.4  378.66  5108.1  378.89  5204.7  383.81  5252.2  387.23  5375.2  391.93
  5575.3  397.71  5699.8  397.28  6071.5   397.2  6245.9  397.71  6411.9  394.46
  6447.5  396.75  6512.7  393.18  6604.9  396.52  6655.3  393.68  7112.3  404.06
  7122.3  404.31  7287.2  408.95  7343.9   406.9  7385.7  411.54  7475.3  413.22
#Mann= 12 ,-1 , 0
  3143.2     .05       0  4822.1     .16       0  5005.3     .07       0
  5011.3     .16       0  5204.7     .05       0  5252.2     .12       0
  5375.2     .05       0  5575.3     .12       0  5699.8     .16       0
  6071.5     .05       0  7112.3     .16       0  7122.3     .05       0
Bank Sta=4972,5035.4
XS Rating Curve= 0 ,0
Exp/Cntr=0.3,0.1

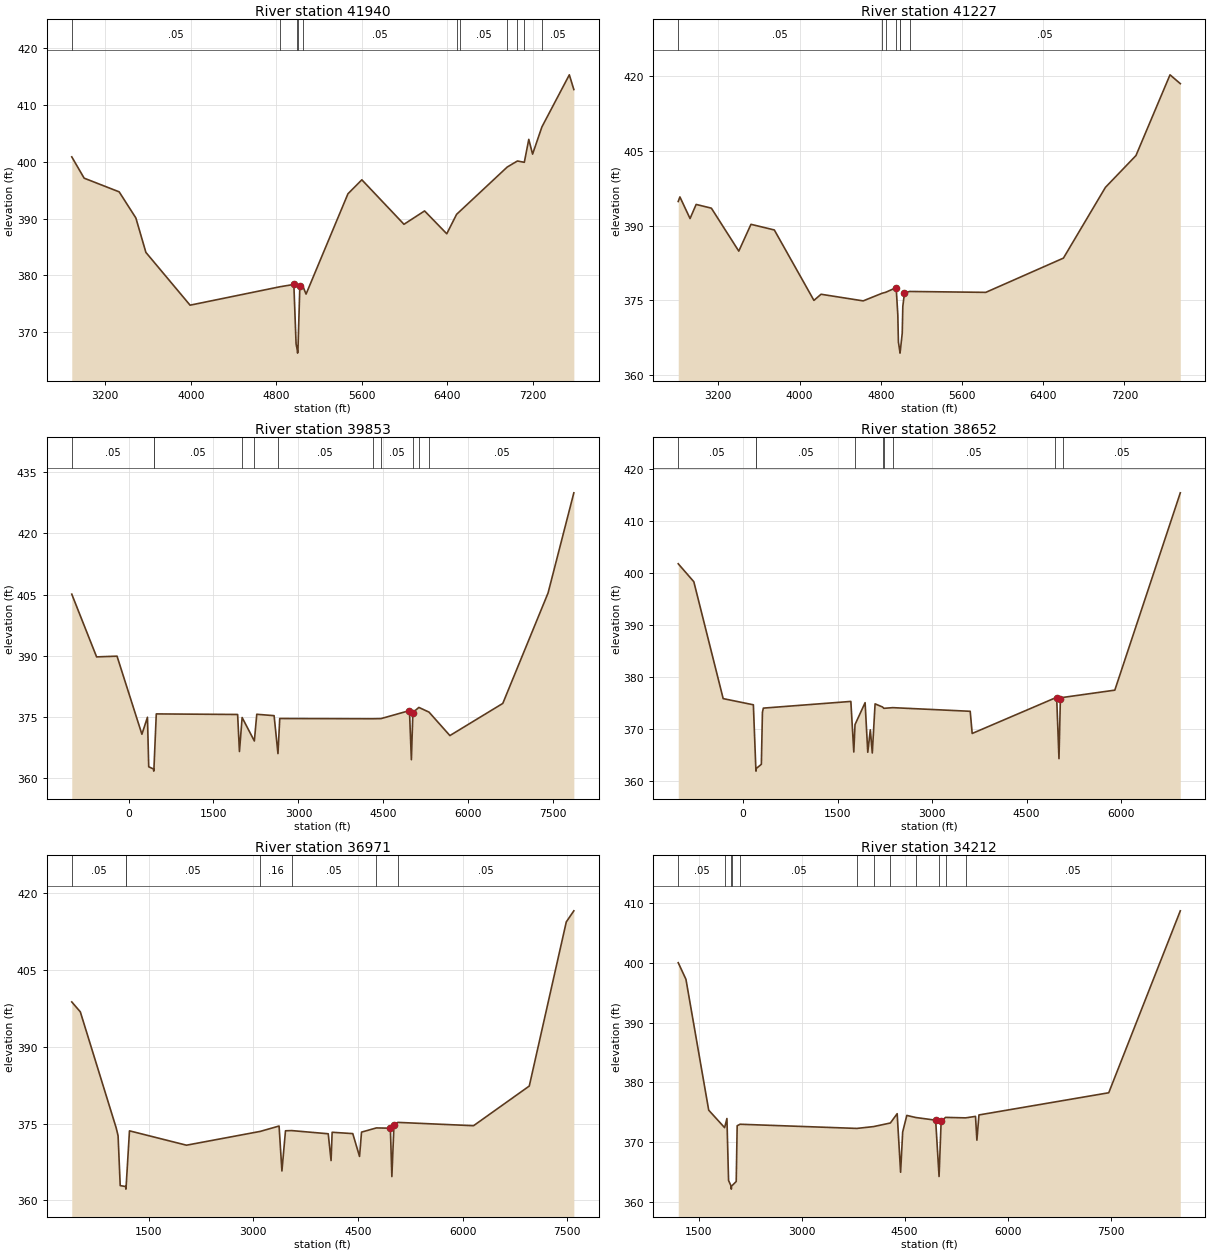
Type RM Length L Ch R = 1 ,41940   ,713,713,713
BEGIN DESCRIPTION:
FAULKENBERRY CREEK 2.0
END DESCRIPTION:
XS GIS Cut Line= 5
       3502381.7     10533469.54      3502186.39     10531907.05
      3502142.99     10531679.19      3501752.36     10531169.21
      3500439.56     10529346.47
#Sta/Elev= 30
  2887.8  400.87  3003.5  397.12  3331.1  394.71  3487.3  390.11  3581.1  384.05
  3994.2  374.76  4836.7  378.01  4964.7  378.41  4985.5  367.95    4997  366.82
  4999.8  366.32    5003  366.82  5020.8  378.16  5046.2  378.24  5078.9  376.71
  5470.6  394.37  5600.6  396.83  5994.6     389  6187.3  391.35  6394.7  387.33
  6486.5  390.75    6519  391.32  6959.6  399.07  7055.2  400.14  7119.9  399.91
  7161.7  403.95  7197.3  401.35  7284.4  406.14  7540.9  415.31  7583.1  412.72
#Mann= 11 ,-1 , 0
  2887.8     .05       0  4836.7     .16       0    4997     .07       0
    5003     .16       0  5046.2     .05       0  6486.5     .16       0
    6519     .05       0  6959.6     .16       0  7055.2     .05       0
  7119.9     .16       0  7284.4     .05       0
Bank Sta=4964.7,5020.8
XS Rating Curve= 0 ,0
Exp/Cntr=0.3,0.1

Type RM Length L Ch R = 1 ,41227   ,1374,1374,1374
BEGIN DESCRIPTION:
FAULKENBERRY CREEK 1.0
END DESCRIPTION:
XS GIS Cut Line= 4
      3502786.89     10533638.07      3502760.85     10531932.32
        3502227.     10530968.78      3500937.95     10529263.08
#Sta/Elev= 30
  2805.2  394.86  2821.6  395.78  2921.6  391.44  2981.7  394.27  3131.7  393.52
  3401.7   384.9  3521.7  390.28  3751.7  389.15  4141.8  375.02  4211.8  376.25
    4627  374.92  4814.7  376.46    4848  376.64  4949.6  377.55  4952.1  377.51
  4968.2  372.11  4973.9  366.66  4986.9  364.94  4989.7  364.44  4992.9  364.94
  5011.7  368.44  5017.4  373.83  5033.4  376.46  5083.3  376.81  5834.7  376.63
  6599.3   383.5    7013  397.69  7313.8  404.07  7649.3  420.27  7750.7   418.5
#Mann= 7 ,-1 , 0
  2805.2     .05       0  4814.7     .16       0    4848     .05       0
  4949.6     .16       0  4986.9     .07       0  4992.9     .16       0
  5083.3     .05       0
Bank Sta=4952.1,5033.4
XS Rating Curve= 0 ,0
Exp/Cntr=0.3,0.1

Type RM Length L Ch R = 1 ,39853   ,1201,1201,1201
BEGIN DESCRIPTION:
FAULKENBERRY CREEK 1.01
END DESCRIPTION:
XS GIS Cut Line= 4
       3508653.5      10533567.7      3503309.86     10530963.31
      3503153.61     10530942.48      3501158.83     10529031.03
#Sta/Elev= 30
 -1002.1  405.09  -563.6  389.72    -203   389.9   236.3  370.77   334.4  374.93
   356.6   362.8   442.6  362.23   445.4  361.73   448.6  362.23   490.1  375.75
  1926.3  375.61  1958.6  366.53  2005.8  374.87  2221.7  369.12  2264.4  375.66
  2570.4  375.32  2638.8  366.02    2670  374.62    4309  374.56  4458.8   374.6
  4960.3  376.56  4994.3  364.52  5020.6  375.97  5020.9  376.09  5126.4  377.34
  5305.6  376.19  5674.5  370.44  6608.3  378.32  7407.4  405.37  7862.8  429.92
#Mann= 11 ,-1 , 0
 -1002.1     .05       0   442.6    .035       0   448.6     .05       0
  2005.8     .12       0  2221.7     .16       0  2638.8     .05       0
    4309     .12       0  4458.8     .05       0  5020.6     .12       0
  5126.4     .16       0  5305.6     .05       0
Bank Sta=4960.3,5020.9
XS Rating Curve= 0 ,0
Exp/Cntr=0.3,0.1

Type RM Length L Ch R = 1 ,38652   ,1681,1681,1681
BEGIN DESCRIPTION:
FAULKENBERRY CREEK 1.02
END DESCRIPTION:
XS GIS Cut Line= 3
      3508731.78     10532095.79      3503297.71      10530255.5
      3501509.49     10528918.68
#Sta/Elev= 30
 -1030.2  401.78  -782.9  398.33  -316.8  375.82   162.5  374.63   201.7  362.36
   204.5  361.86   207.7  362.36   289.2  363.17   306.4  373.19   320.9  373.99
  1709.9  375.28  1756.7  365.54    1776  370.82  1936.2  375.04  1978.5  365.49
  2018.9  369.81  2050.3  365.35  2094.6  374.81  2213.8   374.2  2233.2  373.95
  2376.9  374.08  3604.4  373.38    3636  369.11  4943.4   375.9  4977.4  375.92
  5013.7  364.26  5035.8  375.74  5077.7  376.05  5900.1  377.45  6939.7  415.44
#Mann= 9 ,-1 , 0
 -1030.2     .05       0   201.7     .07       0   207.7     .05       0
    1776     .16       0  2213.8     .12       0  2233.2     .16       0
  2376.9     .05       0  4943.4     .16       0  5077.7     .05       0
Bank Sta=4977.4,5035.8
XS Rating Curve= 0 ,0
Exp/Cntr=0.3,0.1

Type RM Length L Ch R = 1 ,36971   ,2759,2759,2759
BEGIN DESCRIPTION:
FAULKENBERRY CREEK 1.03
END DESCRIPTION:
XS GIS Cut Line= 3
      3508662.27     10531106.19      3504651.87     10530272.86
      3502012.99     10528640.92
#Sta/Elev= 30
   396.3  398.73     519  396.79  1033.9  374.12  1060.4  372.61    1091   362.9
  1169.7  362.71  1172.5  362.21  1175.7  362.71  1223.8  373.58  2040.9  370.78
  3098.2  373.47  3368.6  374.52  3409.5  365.75  3460.6  373.59  3549.2  373.63
  4073.4  373.01  4114.2  367.78  4129.6   373.3  4425.2  373.04  4522.3  368.59
  4550.9  373.33  4764.1  374.15  4964.4   374.1  4985.9  364.66  5016.4  374.81
  5072.8  375.23    6157  374.58  6956.1  382.32  7486.8  414.34  7595.1   416.5
#Mann= 7 ,-1 , 0
   396.3     .05       0  1169.7     .07       0  1175.7     .05       0
  3098.2     .16       0  3549.2     .05       0  4764.1     .16       0
  5072.8     .05       0
Bank Sta=4964.4,5016.4
XS Rating Curve= 0 ,0
Exp/Cntr=0.3,0.1

Type RM Length L Ch R = 1 ,34212   ,775,775,775
BEGIN DESCRIPTION:
FAULKENBERRY CREEK 1.04
END DESCRIPTION:
XS GIS Cut Line= 4
       3508957.4     10530567.99       3506023.4     10529491.61
      3504339.37     10529456.89      3502186.88      10528189.7
#Sta/Elev= 30
  1204.4  400.05  1316.6  397.27    1648  375.32  1879.5  372.39  1913.1  373.92
  1936.9  363.54    1974  362.58  1976.7  362.08    1980  362.58  2048.3  363.36
  2062.2  372.71    2105  372.96  3803.5  372.26  4049.3  372.57  4292.1  373.17
  4390.9  374.73  4440.9  364.91  4470.9  371.65    4531  374.44  4661.3  374.09
    4951  373.64  5000.6   364.2  5031.1  373.49    5096  374.11  5386.2  374.03
  5531.2  374.28  5551.2  370.29  5581.2  374.52  7470.1  378.24  8511.8  408.75
#Mann= 12 ,-1 , 0
  1204.4     .05       0  1879.5     .07       0    1974     .07       0
    1980     .07       0    2105     .05       0  3803.5     .16       0
  4049.3     .05       0  4292.1     .12       0  4661.3     .16       0
  5000.6     .12       0    5096     .16       0  5386.2     .05       0
Bank Sta=4951,5031.1
XS Rating Curve= 0 ,0
Exp/Cntr=0.3,0.1

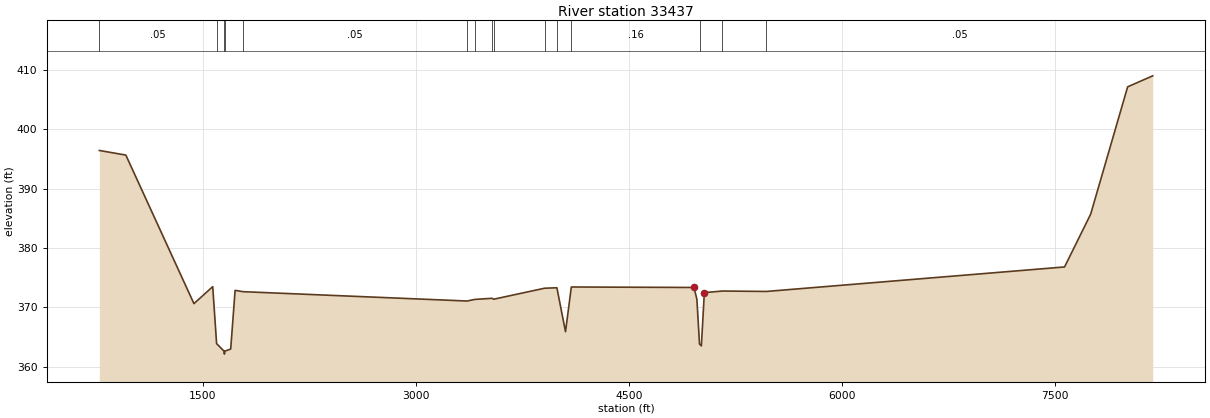
Type RM Length L Ch R = 1 ,33437   ,1599,1599,1599
BEGIN DESCRIPTION:
FAULKENBERRY CREEK 1.05
END DESCRIPTION:
XS GIS Cut Line= 4
      3509217.83     10530515.91      3505884.51     10528762.45
      3504929.65     10529040.22      3502570.18     10527825.79
#Sta/Elev= 30
   772.4   396.4   959.1  395.62  1438.3  370.64  1570.5   373.5  1597.8  363.92
    1650  362.65  1652.8  362.15    1656  362.65  1697.1  363.01    1728  372.87
  1784.9  372.65  3361.4  371.08    3415  371.35  3537.2  371.54  3547.4  371.38
  3906.2  373.23    3993  373.31  4053.6  365.92  4094.6  373.44  4957.9  373.36
  4978.4  371.37  4996.7  363.85  5009.9  363.54  5030.8  372.49  5157.8  372.76
  5467.9  372.69  7566.2  376.81  7749.9  385.68  8010.3   407.1  8186.9  408.95
#Mann= 15 ,-1 , 0
   772.4     .05       0  1597.8     .07       0    1650     .07       0
    1656     .07       0  1784.9     .05       0  3361.4     .12       0
    3415     .05       0  3537.2     .12       0  3547.4     .16       0
  3906.2     .05       0    3993     .12       0  4094.6     .16       0
  4996.7     .12       0  5157.8     .16       0  5467.9     .05       0
Bank Sta=4957.9,5030.8
XS Rating Curve= 0 ,0
Exp/Cntr=0.3,0.1