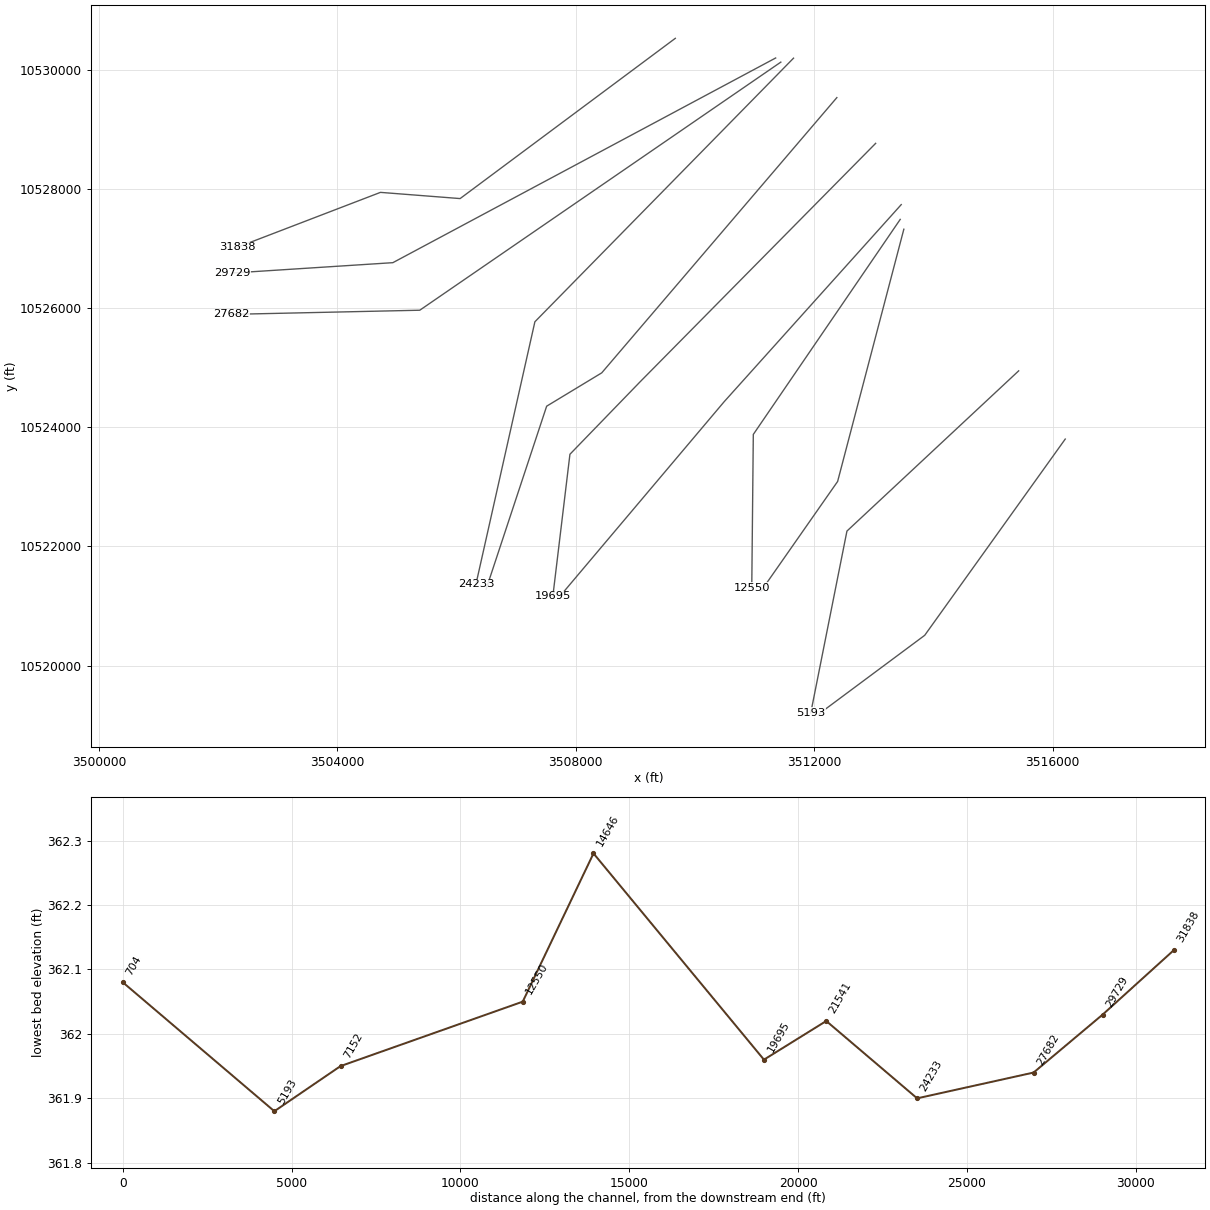
HEC-RAS study FAULKENBERRY CREEK.prj: FAULKENBERRY CREEK Base Level Engineering

--- FAULKENBERRY CREEK.g01 (geometry) --- (continued)

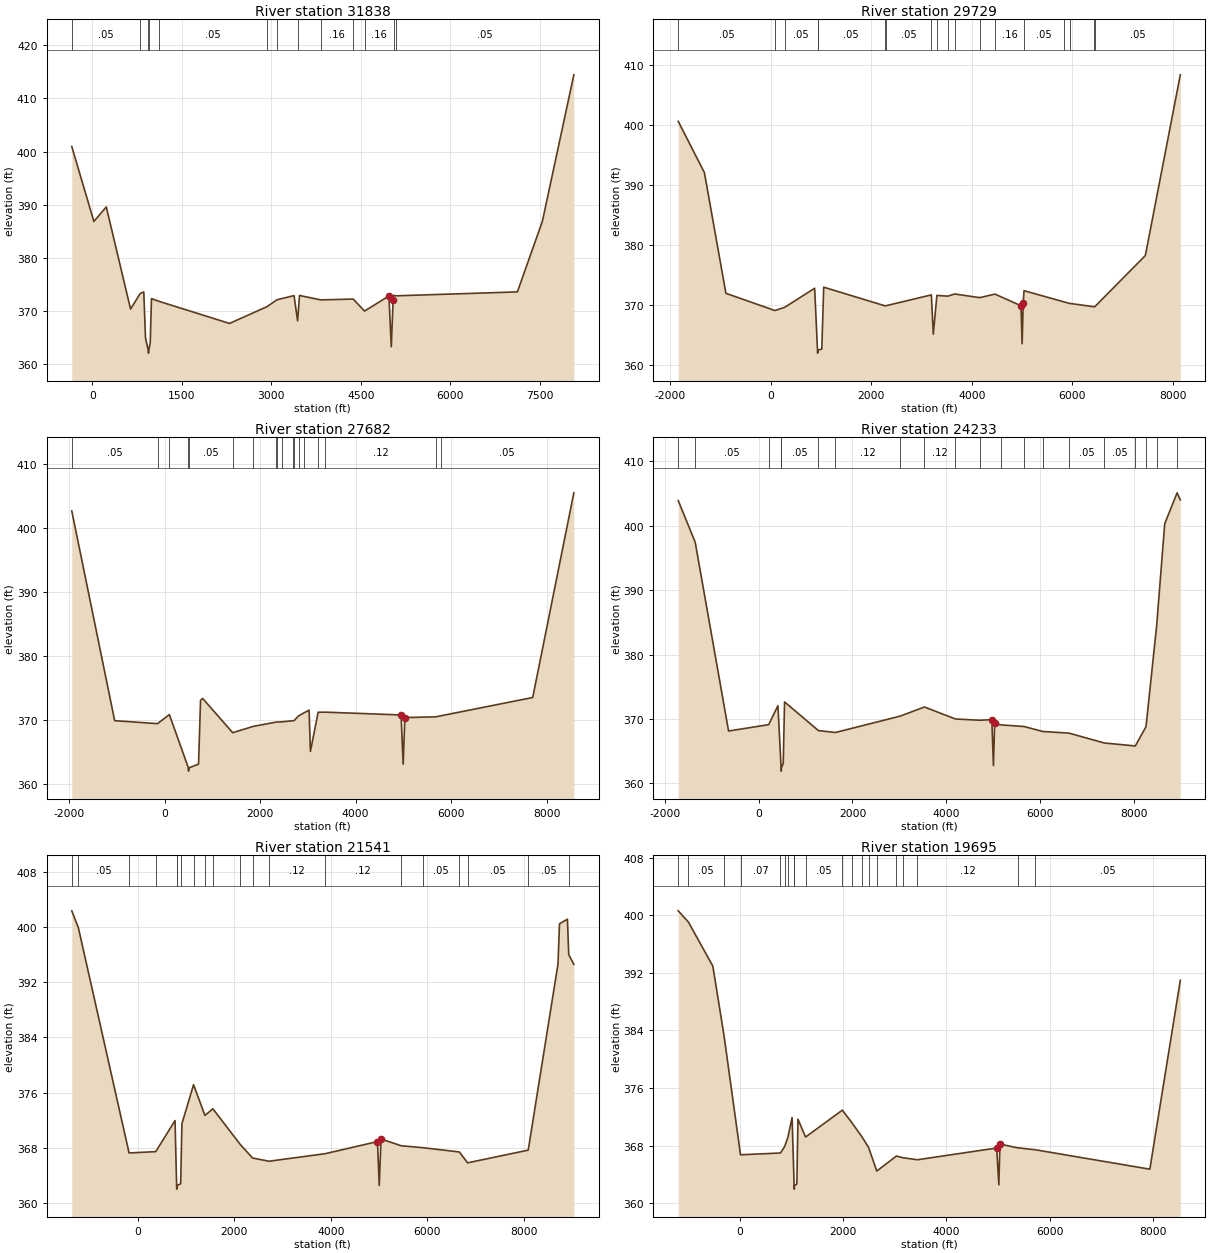
Type RM Length L Ch R = 1 ,31838   ,2109,2109,2109
BEGIN DESCRIPTION:
FAULKENBERRY CREEK 1.06
END DESCRIPTION:
XS GIS Cut Line= 4
      3509669.21     10530533.26      3506058.12     10527842.31
      3504721.32     10527946.47      3502326.67     10527026.79
#Sta/Elev= 30
  -342.8  400.97    27.7  386.88   235.4  389.61     642  370.41   804.8  373.35
   863.3  373.63   892.2  364.98   939.3  362.63     942  362.13   945.3  362.63
   971.5  364.06   992.3  372.38  1117.5  371.87  2299.7  367.71  2926.3  370.86
  3094.9  372.16  3379.9  372.94  3439.7  368.21  3471.6  372.97  3825.7  372.14
    4372  372.29  4560.5  370.03  4969.1  372.87  5009.2  363.32  5039.3   372.1
  5052.8  372.99  5088.7   372.9  7121.2  373.64  7539.2  386.89  8066.7  414.44
#Mann= 13 ,-1 , 0
  -342.8     .05       0   804.8     .07       0   939.3     .07       0
   945.3     .07       0  1117.5     .05       0  2926.3     .16       0
  3094.9     .05       0  3439.7      .1       0  3825.7     .16       0
    4372     .12       0  4560.5     .16       0  5052.8     .12       0
  5088.7     .05       0
Bank Sta=4969.1,5039.3
XS Rating Curve= 0 ,0
Exp/Cntr=0.3,0.1

Type RM Length L Ch R = 1 ,29729   ,2047,2047,2047
BEGIN DESCRIPTION:
FAULKENBERRY CREEK 1.07
END DESCRIPTION:
XS GIS Cut Line= 3
      3511353.31     10530203.44      3504929.65     10526765.92
      3502238.64     10526592.31
#Sta/Elev= 30
 -1837.6  400.59 -1317.4  392.07  -889.9  371.98    84.1  369.12   276.6  369.64
   874.5  372.82   931.5  362.53   934.2  362.03   937.5  362.53  1016.5   362.7
  1054.7     373    2265  369.92  2285.5   369.9  3194.9  371.72  3233.6  365.19
  3304.7  371.63  3524.3  371.51  3658.1  371.87  4157.5  371.26    4460  371.85
  4977.4  369.91  4999.3  363.59  5021.2  370.31  5037.3  372.42  5838.2  370.54
  5944.6   370.3    6438  369.74    6444  369.75  7449.7  378.27  8144.6  408.33
#Mann= 18 ,-1 , 0
 -1837.6     .05       0    84.1     .07       0   276.6     .05       0
   931.5     .07       0   937.5     .05       0    2265      .1       0
  2285.5     .05       0  3194.9     .12       0  3304.7     .16       0
  3524.3     .12       0  3658.1     .16       0  4157.5     .12       0
    4460     .16       0  5037.3     .05       0  5838.2      .1       0
  5944.6     .05       0    6438     .07       0    6444     .05       0
Bank Sta=4977.4,5021.2
XS Rating Curve= 0 ,0
Exp/Cntr=0.3,0.1

Type RM Length L Ch R = 1 ,27682   ,3449,3449,3449
BEGIN DESCRIPTION:
FAULKENBERRY CREEK 1.08
END DESCRIPTION:
XS GIS Cut Line= 3
      3511440.04     10530133.95      3505381.04     10525967.31
       3502221.3     10525897.86
#Sta/Elev= 30
 -1942.6  402.62 -1044.1  369.83  -146.5  369.36   101.3  370.78   500.1  362.44
   502.8  361.94   506.1  362.44   712.1  363.03     754     373   797.7  373.31
  1427.2  367.95  1860.7  368.94  2341.7  369.61  2345.8  369.61  2458.5  369.65
  2692.1  369.82  2713.3  369.84    2809  370.59  2918.8  371.04  3027.1  371.48
  3055.1  365.03  3216.6  371.14  3370.1  371.16  4953.8  370.72  4996.9  363.03
  5033.3  370.31  5680.3  370.43  5779.1  370.58  7710.3  373.45  8571.3  405.45
#Mann= 18 ,-1 , 0
 -1942.6     .05       0  -146.5     .07       0   101.3     .05       0
   500.1     .07       0   506.1     .05       0  1427.2     .12       0
  1860.7      .1       0  2341.7     .05       0  2345.8      .1       0
  2458.5     .05       0  2692.1      .1       0  2713.3     .12       0
    2809      .1       0  2918.8     .12       0  3216.6      .1       0
  3370.1     .12       0  5680.3     .16       0  5779.1     .05       0
Bank Sta=4953.8,5033.3
XS Rating Curve= 0 ,0
Exp/Cntr=0.3,0.1

Type RM Length L Ch R = 1 ,24233   ,2692,2692,2692
BEGIN DESCRIPTION:
UNT0001 IN SAND CR 1.0
END DESCRIPTION:
XS GIS Cut Line= 3
      3511653.11     10530200.36       3507312.8     10525773.24
      3506323.57     10521365.08
#Sta/Elev= 30
 -1718.6  403.93 -1356.3  397.45  -643.9  368.13   213.1  369.12   409.6  372.07
   477.4   362.4   480.1   361.9   483.4   362.4   522.8  363.11   551.1  372.65
  1273.5   368.2  1635.9   367.9  3022.4  370.45  3537.2  371.86    4199     370
  4719.4   369.8  4974.8   369.9  5010.1  362.77  5036.3  369.34    5175  369.08
  5665.9  368.83  6059.8  368.06  6617.3  367.81  7378.7  366.27  8038.4  365.81
  8266.7  368.81  8494.6  384.53  8666.3  400.33  8930.6  405.13    8999  404.04
#Mann= 20 ,-1 , 0
 -1718.6     .05       0 -1356.3     .05       0   213.1     .05       0
   477.4     .07       0   483.4     .05       0  1273.5     .16       0
  1635.9     .12       0  3022.4     .05       0  3537.2     .12       0
    4199     .05       0  4719.4     .12       0    5175     .05       0
  5665.9      .1       0  6059.8      .1       0  6617.3     .05       0
  7378.7     .05       0  8038.4     .12       0  8266.7     .05       0
  8494.6     .08       0  8930.6     .05       0
Bank Sta=4974.8,5036.3
XS Rating Curve= 0 ,0
Exp/Cntr=0.3,0.1

Type RM Length L Ch R = 1 ,21541   ,1846,1846,1846
BEGIN DESCRIPTION:
UNT0001 IN SAND CR 2.0
END DESCRIPTION:
XS GIS Cut Line= 4
      3512380.07     10529537.99      3508434.76      10524915.6
      3507510.28     10524355.71      3506494.65     10521282.77
#Sta/Elev= 30
 -1361.6  402.34 -1224.5  399.88  -175.1  367.26   376.5  367.45   776.6  371.95
   809.2  362.52   811.9  362.02   815.2  362.52   892.8   362.8   918.7   371.5
  1159.8  377.15  1395.3   372.7  1560.3  373.66  2123.1  368.52  2381.8  366.53
  2722.4  366.06  3888.6  367.16  4967.3  368.91  5004.1  362.56  5040.9  369.29
  5453.6  368.31  5912.3  368.02  6663.5   367.4  6833.2  365.83  8088.3  367.67
  8704.3  394.61    8736  400.47  8899.9  401.12  8926.9  395.99  9032.8  394.59
#Mann= 20 ,-1 , 0
 -1361.6     .05       0 -1224.5     .05       0  -175.1     .07       0
   376.5      .1       0   809.2     .07       0   815.2     .16       0
   892.8     .12       0  1159.8     .05       0  1395.3     .16       0
  1560.3      .1       0  2123.1     .12       0  2381.8     .07       0
  2722.4     .12       0  3888.6     .12       0  5453.6      .1       0
  5912.3     .05       0  6663.5      .1       0  6833.2     .05       0
  8088.3     .05       0  8926.9     .05       0
Bank Sta=4967.3,5040.9
XS Rating Curve= 0 ,0
Exp/Cntr=0.3,0.1

Type RM Length L Ch R = 1 ,19695   ,5049,5049,5049
BEGIN DESCRIPTION:
UNT0001 IN SAND CR 3.0
END DESCRIPTION:
XS GIS Cut Line= 4
      3513031.11     10528769.76      3509072.78     10524759.35
      3507900.91     10523548.42      3507614.52     10521166.17
#Sta/Elev= 30
 -1191.5  400.62  -993.4  399.05  -521.7  392.94  -304.5  383.26    14.1  366.73
   787.3  366.98   867.8  367.87   930.8  369.15  1012.6  371.91  1052.1  362.46
  1054.8  361.96  1058.1  362.46  1104.6  362.66  1125.8  371.68  1273.8   369.2
  1985.5  372.93  2163.8  371.25  2365.4  369.22  2491.7  367.78  2652.3  364.47
    3033  366.56    3158  366.32  3438.9  366.04  4972.6  367.67    5015  362.56
  5036.4  368.22  5377.3   367.7  5720.2  367.43  7938.2  364.73  8527.9  390.97
#Mann= 20 ,-1 , 0
 -1191.5      .1       0  -993.4     .05       0  -304.5      .1       0
    14.1     .07       0   787.3     .16       0   867.8      .1       0
   930.8     .16       0  1052.1     .07       0  1058.1     .07       0
  1273.8     .05       0  1985.5     .12       0  2163.8     .05       0
  2365.4     .07       0  2491.7     .12       0  2652.3     .12       0
    3033     .07       0    3158     .07       0  3438.9     .12       0
  5377.3      .1       0  5720.2     .05       0
Bank Sta=4972.6,5036.4
XS Rating Curve= 0 ,0
Exp/Cntr=0.3,0.1

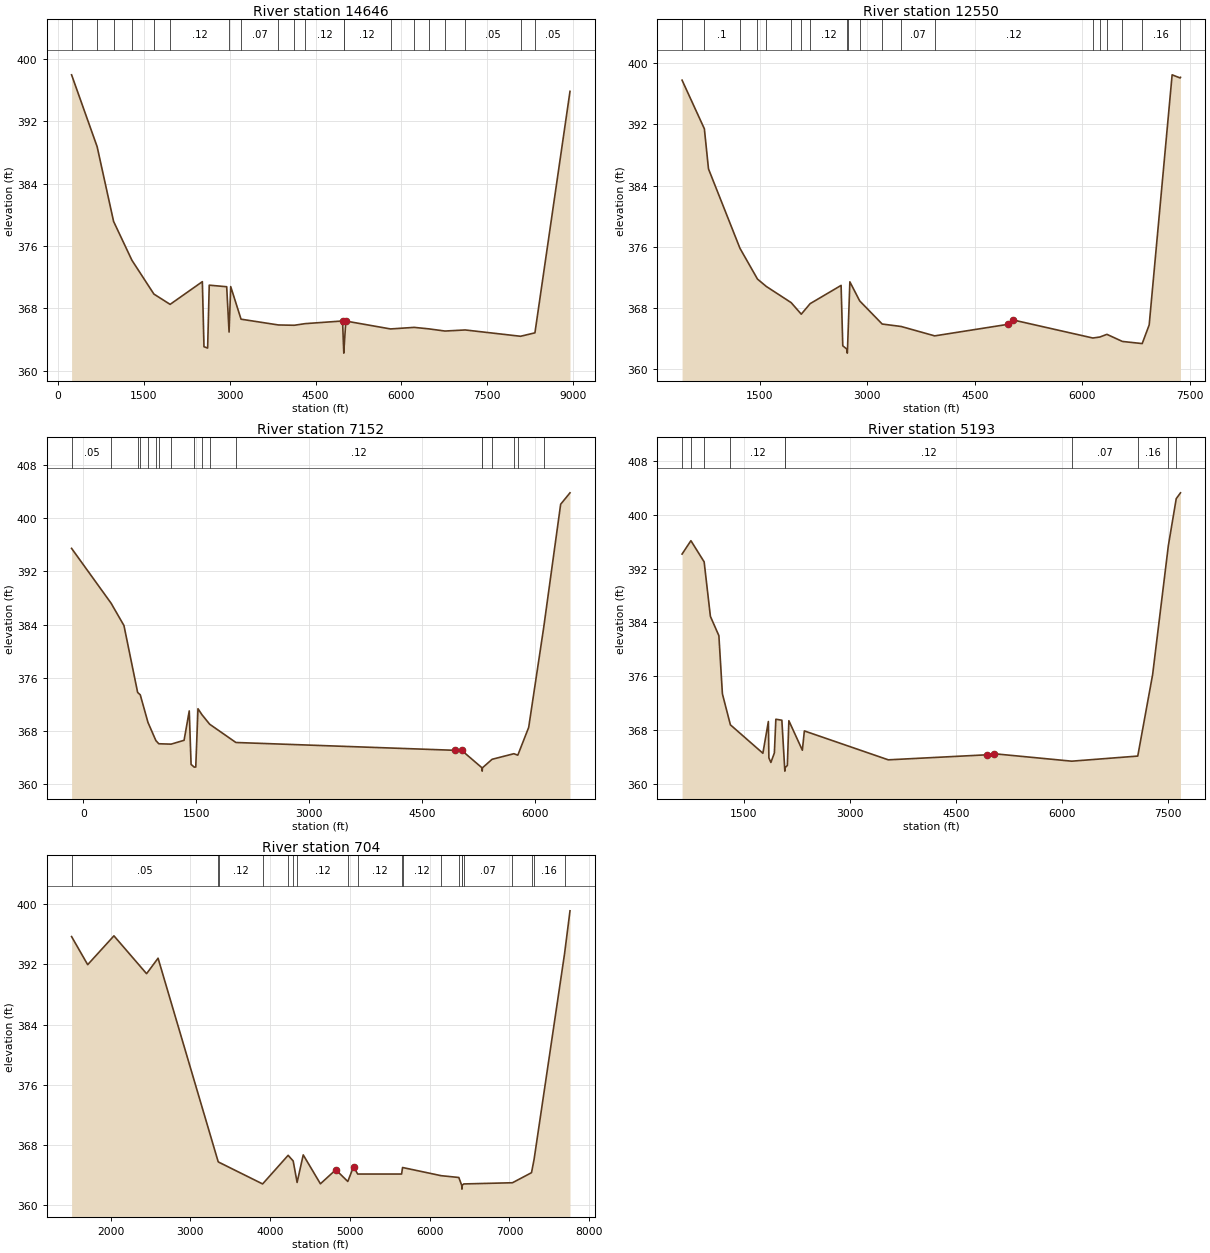
Type RM Length L Ch R = 1 ,14646   ,2096,2096,2096
BEGIN DESCRIPTION:
UNT0001 IN SAND CR 4.0
END DESCRIPTION:
XS GIS Cut Line= 3
      3513460.79     10527741.11      3510487.71     10524429.49
      3507740.31     10521172.11
#Sta/Elev= 30
   235.4  397.95     682  388.74   969.7  379.16  1289.5  374.19  1674.2  369.85
  1957.7  368.53  2521.1  371.44  2549.5   363.1  2613.3  362.93  2641.4  370.99
  2946.4  370.79  2988.1  364.98  3016.7  370.81  3197.2  366.63  3850.2  365.89
  4127.3  365.85  4318.6  366.06  4971.6   366.4  4990.7  362.78  4993.4  362.28
  4996.7  362.78  5028.8  366.39    5810  365.38  6223.6  365.58  6479.4  365.39
  6762.2  365.11  7114.4  365.25  8082.6  364.44  8334.1  364.88  8947.1  395.83
#Mann= 20 ,-1 , 0
   235.4     .05       0     682     .05       0   969.7     .16       0
  1289.5     .05       0  1674.2     .16       0  1957.7     .12       0
  2988.1     .05       0  3197.2     .07       0  3850.2     .12       0
  4127.3     .07       0  4318.6     .12       0  4990.7     .07       0
  4996.7     .12       0    5810     .12       0  6223.6      .1       0
  6479.4     .05       0  6762.2     .12       0  7114.4     .05       0
  8082.6     .12       0  8334.1     .05       0
Bank Sta=4971.6,5028.8
XS Rating Curve= 0 ,0
Exp/Cntr=0.3,0.1

Type RM Length L Ch R = 1 ,12550   ,5398,5398,5398
BEGIN DESCRIPTION:
UNT0001 IN SAND CR 5.0
END DESCRIPTION:
XS GIS Cut Line= 3
      3513443.44     10527492.72      3510978.16     10523881.61
      3510952.14     10521305.02
#Sta/Elev= 30
   418.6   397.8   729.4  391.43   786.9  386.18  1225.7  375.78  1469.9  371.75
    1592  370.79    1940  368.66  2080.4  367.15  2203.9  368.53  2635.7  370.92
  2659.2  363.01  2719.1  362.55  2721.9  362.05  2725.1  362.55    2758  371.39
    2895  368.89  3208.6  365.86  3472.8  365.54  3940.6  364.31    4961  365.82
    5031   366.4  6145.4  364.03  6243.6  364.16  6341.7  364.51  6557.9  363.58
  6833.8   363.3  6931.1  365.74  7251.1   398.5    7363  398.09  7367.7  398.17
#Mann= 20 ,-1 , 0
   418.6     .05       0   729.4      .1       0  1225.7     .05       0
  1469.9      .1       0    1592      .1       0    1940     .12       0
  2080.4     .05       0  2203.9     .12       0  2719.1     .07       0
  2725.1     .12       0    2895     .05       0  3208.6     .12       0
  3472.8     .07       0  3940.6     .12       0  6145.4      .1       0
  6243.6     .07       0  6341.7      .1       0  6557.9     .07       0
  6833.8     .16       0    7363      .1       0
Bank Sta=4961,5031
XS Rating Curve= 0 ,0
Exp/Cntr=0.3,0.1

Type RM Length L Ch R = 1 ,7152    ,1959,1959,1959
BEGIN DESCRIPTION:
UNT0001 IN SAND CR 6.0
END DESCRIPTION:
XS GIS Cut Line= 3
       3513504.2     10527327.77      3512393.09     10523091.68
       3511108.4     10521251.44
#Sta/Elev= 30
    -155  395.47     370  387.22   540.9  383.86   722.9  373.79   757.7  373.43
   860.2  369.28   965.1  366.55    1004  366.07  1167.7  366.01    1340  366.59
  1408.7  371.01  1433.1  362.96  1475.2  362.55  1495.1  362.57  1524.7  371.34
  1577.6  370.44  1680.1  369.01  2028.4  366.26    4944  365.08  5029.4  365.07
  5299.1  362.45  5301.9  361.95  5305.1  362.45  5433.3  363.73  5722.7  364.57
  5775.1  364.35  5919.6  368.53  6119.4  383.58  6344.5  402.11  6468.7  403.83
#Mann= 18 ,-1 , 0
    -155     .05       0     370     .16       0   722.9     .05       0
   757.7      .1       0   860.2     .12       0   965.1     .05       0
    1004     .12       0  1167.7     .07       0  1475.2     .05       0
  1577.6     .07       0  1680.1     .05       0  2028.4     .12       0
  5299.1     .07       0  5305.1     .12       0  5433.3     .07       0
  5722.7     .12       0  5775.1     .16       0  6119.4     .05       0
Bank Sta=4944,5029.4
XS Rating Curve= 0 ,0
Exp/Cntr=0.3,0.1

Type RM Length L Ch R = 1 ,5193    ,4489,4489,4489
BEGIN DESCRIPTION:
UNT0001 IN SAND CR 7.0
END DESCRIPTION:
XS GIS Cut Line= 3
      3515431.26     10524949.29      3512549.34     10522258.34
       3511942.1     10519204.76
#Sta/Elev= 30
   625.8  394.17   750.8  396.16   938.2  393.01  1026.8   384.9  1146.9  382.03
  1196.8  373.37  1309.8  368.77  1769.8  364.54  1847.5  369.26  1854.8  363.85
  1883.2  363.17  1932.5  364.59  1953.5   369.6  2038.5  369.45    2078  362.38
  2080.8  361.88    2084  362.38  2116.2  362.73  2137.7  369.38  2328.7  364.99
    2357  367.86  3545.6  363.56  4943.4  364.31  5040.5  364.47  6142.4  363.36
  7077.1  364.12  7287.6  376.24    7510  395.41  7621.8  402.41  7682.1  403.28
#Mann= 10 ,-1 , 0
   625.8     .05       0   750.8      .1       0   938.2     .05       0
  1309.8     .12       0    2078     .07       0    2084     .12       0
  6142.4     .07       0  7077.1     .16       0    7510     .05       0
  7621.8     .16       0
Bank Sta=4943.4,5040.5
XS Rating Curve= 0 ,0
Exp/Cntr=0.3,0.1

Type RM Length L Ch R = 1 ,704     ,0,0,0
BEGIN DESCRIPTION:
UNT0001 IN SAND CR 8.0
END DESCRIPTION:
XS GIS Cut Line= 3
      3516212.54     10523803.48      3513854.32     10520507.76
      3512092.19     10519197.01
#Sta/Elev= 30
  1510.5  395.71  1712.3  391.97  2041.5  395.81  2450.6  390.77  2594.8  392.83
  3348.1  365.74  3355.5  365.67  3905.5  362.77  4225.3  366.58  4288.6  365.83
    4338  362.97  4414.7  366.64  4630.1  362.79    4823  364.66  4973.2   363.1
  5045.3  365.06  5097.4  364.09    5648  364.09  5659.8  364.96  6143.9  363.87
  6365.3  363.63  6401.9  362.58  6404.6  362.08  6407.9  362.58  6426.8  362.77
    7038  362.93  7276.7  364.27  7308.9  366.04  7690.6   393.4  7759.2  399.14
#Mann= 20 ,-1 , 0
  1510.5     .05       0  3348.1      .1       0  3355.5     .12       0
  3905.5     .07       0  4225.3     .12       0  4288.6     .07       0
    4338     .12       0  4973.2     .07       0  5097.4     .12       0
    5648     .07       0  5659.8     .12       0  6143.9     .07       0
  6365.3     .12       0  6401.9     .07       0  6407.9     .12       0
  6426.8     .07       0    7038     .05       0  7276.7     .07       0
  7308.9     .16       0  7690.6     .05       0
Bank Sta=4823,5045.3
XS Rating Curve= 0 ,0
Exp/Cntr=0.3,0.1

Chan Stop Cuts=-1
Use User Specified Reach Order=0
Composite Channel Slope=5