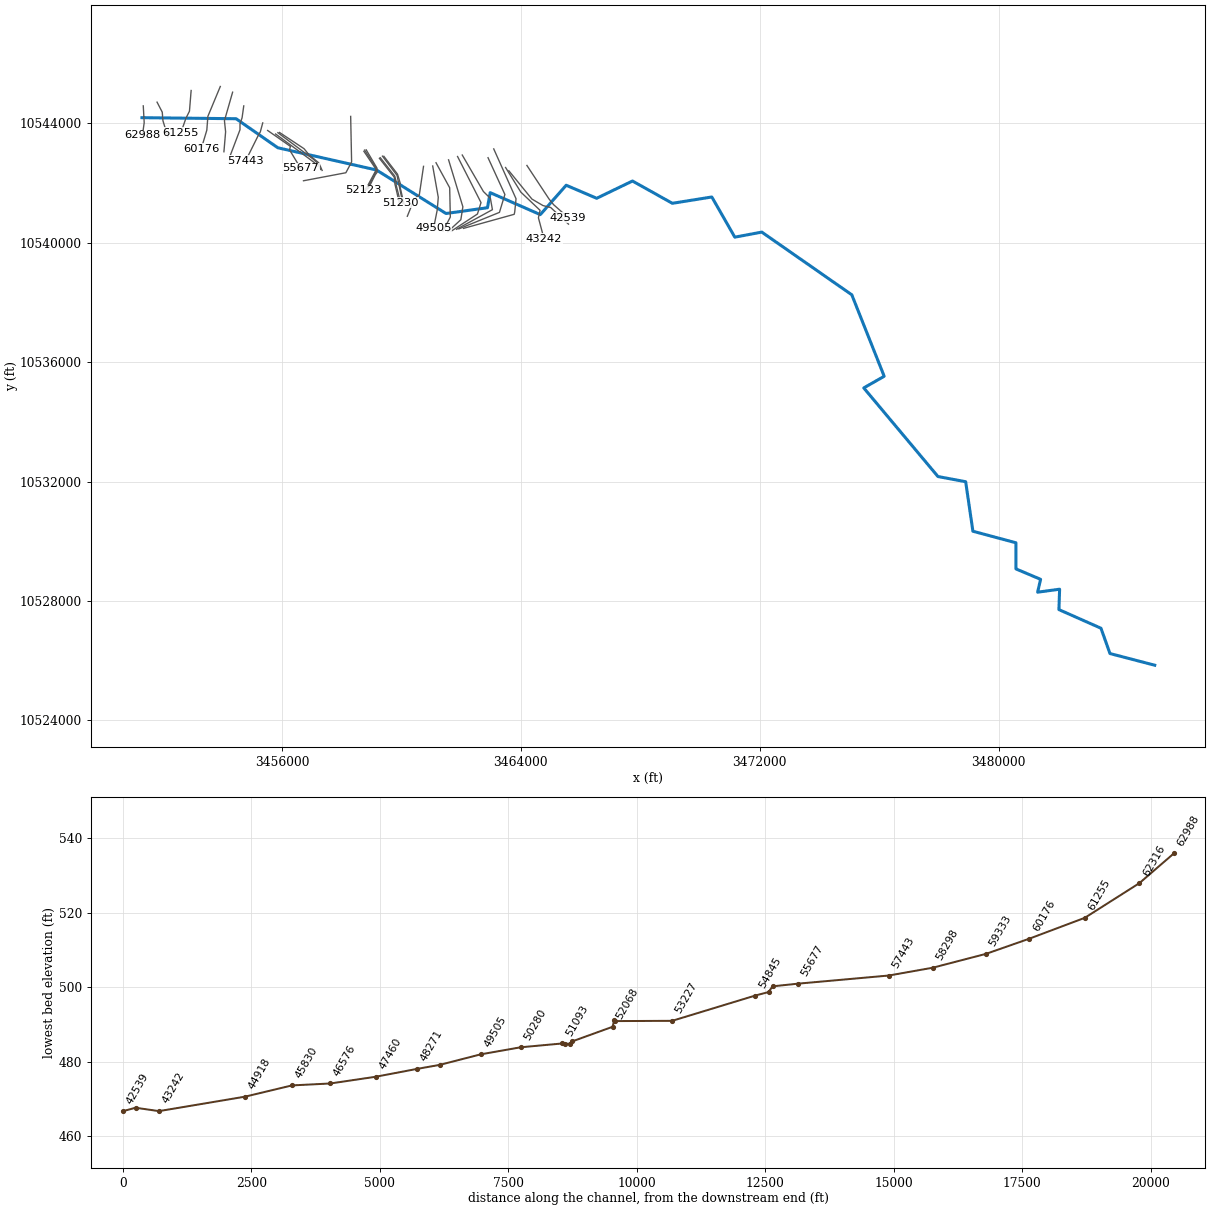
--- FROST CREEK.prj (project) ---

Proj Title=FROST CREEK Base Level Engineering
Current Plan=p01
Default Exp/Contr=0.3,0.1
English Units
Geom File=g01
Flow File=f01
Plan File=p01
Y Axis Title=Elevation
X Axis Title(PF)=Main Channel Distance
X Axis Title(XS)=Station
BEGIN DESCRIPTION:
FROST CREEK
END DESCRIPTION:
DSS Export Rating Curves= 0
DSS Export Rating Curve Sorted= 0
DSS Export Volume Flow Curves= 0
DXF OffsetX= 0
DXF OffsetY= 0
DXF ScaleX= 1
DXF ScaleY= 10

--- FROST CREEK.p01 (plan) ---

Plan Title=Multiple Run
Short Identifier=Multiple
Geom File=g01
Flow File=f01
Subcritical Flow
K Sum by GR= 0
Std Step Tol= 0.01
Critical Tol= 0.01
Num of Std Step Trials= 20
Max Error Tol= 0.3
Flow Tol Ratio= 0.001
Split Flow NTrial= 30
Split Flow Tol= 0.02
Split Flow Ratio= 0.02
Log Output Level= 0
Friction Slope Method= 1
Unsteady Friction Slope Method= 2
Unsteady Bridges Friction Slope Method= 1
Parabolic Critical Depth
Global Vel Dist=  1 , 1 , 1
Global Log Level= 0
CheckData=True
Encroach Param= -1, 0, 0, 0
BEGIN DESCRIPTION:
Multiple Run
END DESCRIPTION:

--- FROST CREEK.f01 (steady flow) ---

Flow Title=Multiple
Program Version=4.10
Number of Profiles= 7
Profile Names=10-year,25-year,50-year,1pct_min,100-year,1pct_plu,500-year
River Rch & RM=FROST CREEK,Reach-1         ,62988
    1009    1390    1705    1526    2064    2792    3016
River Rch & RM=FROST CREEK,Reach-1         ,52123
    1957    2773    3465    3151    4261    5763    6431
River Rch & RM=FROST CREEK,Reach-1         ,43242
    3091    4476    5675    5230    7073    9565   10964
River Rch & RM=FROST CREEK,Reach-1         ,42539
    3195    4625    5862    5398    7301    9873   11304
River Rch & RM=FROST CREEK,Reach-1         ,40663
    3617    5252    6672    6155    8325   11258   12936
River Rch & RM=FROST CREEK,Reach-1         ,36879
    3994    5812    7393    6827    9233   12486   14375
River Rch & RM=FROST CREEK,Reach-1         ,30673
    4180    6093    7760    7173    9701   13120   15134
River Rch & RM=FROST CREEK,Reach-1         ,29264
    4478    6547    8355    7739   10466   14154   16390
River Rch & RM=FROST CREEK,Reach-1         ,28692
    4696    6866    8762    8113   10972   14838   17174
River Rch & RM=FROST CREEK,Reach-1         ,22060
    5235    7676    9815    9103   12311   16649   19330
River Rch & RM=FROST CREEK,Reach-1         ,20812
    5245    7668    9784    9053   12243   16557   19134
River Rch & RM=FROST CREEK,Reach-1         ,16359
    5586    8179   10445    9672   13080   17690   20474
Boundary for River Rch & Prof#=FROST CREEK,Reach-1         , 1
Up Type= 0
Dn Type= 1
Dn Known WS=403.2
Boundary for River Rch & Prof#=FROST CREEK,Reach-1         , 2
Up Type= 0
Dn Type= 1
Dn Known WS=403.9
Boundary for River Rch & Prof#=FROST CREEK,Reach-1         , 3
Up Type= 0
Dn Type= 1
Dn Known WS=404.44
Boundary for River Rch & Prof#=FROST CREEK,Reach-1         , 4
Up Type= 0
Dn Type= 1
Dn Known WS=404.27
Boundary for River Rch & Prof#=FROST CREEK,Reach-1         , 5
Up Type= 0
Dn Type= 1
Dn Known WS=405.03
Boundary for River Rch & Prof#=FROST CREEK,Reach-1         , 6
Up Type= 0
Dn Type= 1
Dn Known WS=405.83
Boundary for River Rch & Prof#=FROST CREEK,Reach-1         , 7
Up Type= 0
Dn Type= 1
Dn Known WS=406.3
DSS Import GetInterval= 0
DSS Import GetPeak= 0
DSS Import FillOption= 0

--- FROST CREEK.g01 (geometry) ---

Geom Title=Existing Conditions
Program Version=4.10

River Reach=FROST CREEK     ,Reach-1
Reach XY= 30
      3451308.63     10544193.68      3454461.58     10544159.04
      3455859.23     10543185.91       3459163.3     10542441.17
      3461492.22      10540982.6      3462880.66     10541176.63
      3462972.13     10541681.55       3464650.7     10540945.38
      3465517.73     10541929.61      3466539.11     10541492.67
      3467737.49      10542071.5      3469073.34     10541324.51
      3470394.91      10541536.2      3471165.33     10540189.75
      3472068.69     10540359.49      3475083.02     10538257.92
      3476168.05     10535527.53      3475483.48     10535137.47
      3477969.31     10532167.13      3478896.84     10531994.49
      3479138.89     10530334.38       3480580.1     10529947.95
      3480582.11     10529071.64      3481406.41      10528722.8
      3481306.91     10528291.39      3482042.95     10528391.96
      3482020.33     10527708.34      3483428.48     10527083.43
      3483729.06     10526236.05      3485230.15     10525844.06

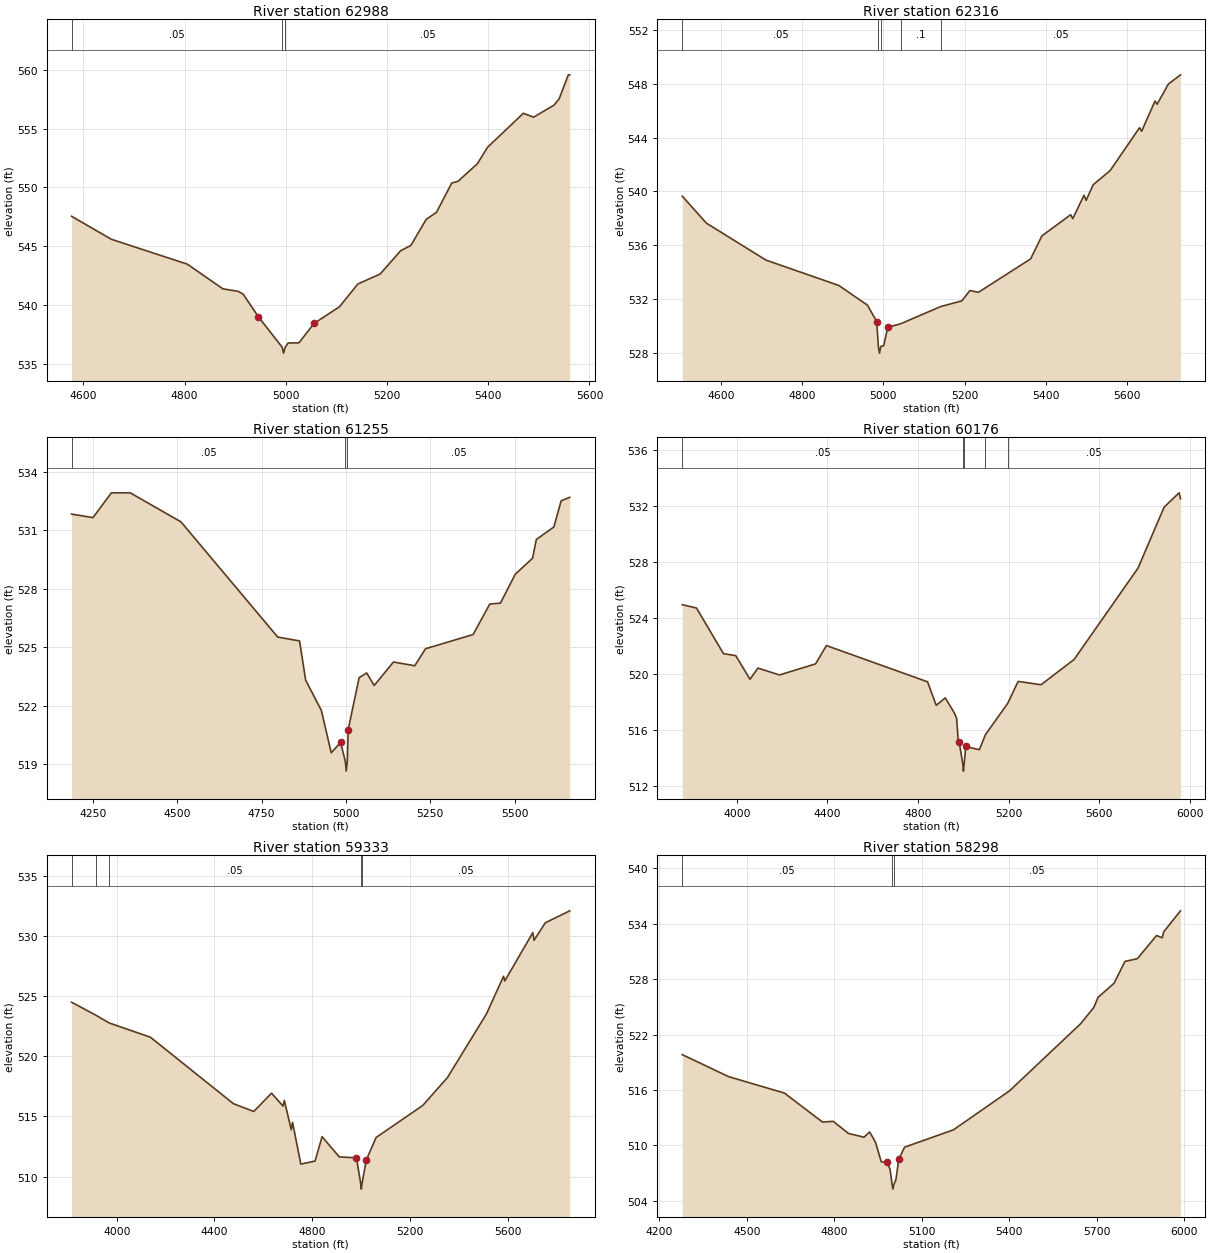
Type RM Length L Ch R = 1 ,62988   ,672,672,672
BEGIN DESCRIPTION:
FROST CREEK 77.1
END DESCRIPTION:
XS GIS Cut Line= 3
      3451353.28      10544590.1      3451384.54      10544024.1
       3451325.5     10543610.86
#Sta/Elev= 30
  4576.8  547.56  4655.4  545.61  4805.6   543.5  4875.7  541.41  4905.8   541.2
  4915.8  540.96  4945.8  539.05  4992.9  536.46  4995.6  535.96  4998.9  536.46
  5004.9  536.82  5025.9  536.83    5056  538.48  5106.1  539.89  5142.4  541.82
  5186.6  542.67    5227  544.64  5247.2  545.09  5277.5   547.3  5297.7  547.89
    5328  550.38  5340.4  550.53  5378.5  552.01  5398.7  553.41  5469.4  556.29
  5489.6  555.96    5530  556.98  5540.1  557.51  5558.2  559.55  5561.1  559.55
#Mann= 3 ,-1 , 0
  4576.8     .05       0  4992.9     .03       0  4998.9     .05       0
Bank Sta=4945.8,5056
XS Rating Curve= 0 ,0
Exp/Cntr=0.3,0.1

Type RM Length L Ch R = 1 ,62316   ,1061,1061,1061
BEGIN DESCRIPTION:
FROST CREEK 77.0
END DESCRIPTION:
XS GIS Cut Line= 4
      3451815.12     10544714.29      3451988.73      10544380.1
      3452013.37     10544087.39      3452175.18     10543556.02
#Sta/Elev= 30
  4505.5  539.65  4564.8  537.64  4711.3  534.89  4890.6     533  4960.8  531.54
  4983.9  530.31  4987.9  528.46  4990.7  527.96  4993.9  528.46    5001  528.51
    5011  529.88  5043.1  530.15  5141.2  531.43  5193.1  531.85  5213.2  532.62
  5234.1  532.49  5362.5  534.98  5390.2  536.69  5461.1  538.27  5466.3  537.98
  5493.9  539.72  5499.1  539.34  5516.4   540.5  5558.2  541.56  5630.5  544.75
  5635.7  544.49  5668.6  546.74  5673.8   546.5  5701.4     548  5731.3  548.69
#Mann= 5 ,-1 , 0
  4505.5     .05       0  4987.9    .035       0  4993.9     .05       0
  5043.1      .1       0  5141.2     .05       0
Bank Sta=4983.9,5011
XS Rating Curve= 0 ,0
Exp/Cntr=0.3,0.1

Type RM Length L Ch R = 1 ,61255   ,1079,1079,1079
BEGIN DESCRIPTION:
FROST CREEK 75.0
END DESCRIPTION:
XS GIS Cut Line= 4
      3452956.61     10545104.88      3452900.19     10544410.48
      3452779.31     10544169.27      3452613.39     10543687.43
#Sta/Elev= 30
  4187.2  531.82  4250.6  531.64  4305.2  532.91    4361  532.91  4511.5  531.42
    4798  525.52  4862.7  525.32  4880.8  523.31  4927.3  521.76  4956.5  519.59
  4984.5  520.12  4998.2  519.15    5001  518.65  5004.2  519.15  5006.8  520.78
  5039.2  523.44  5061.6  523.68  5083.9  523.04  5140.9  524.24  5204.1  524.05
  5235.8  524.92    5377  525.65  5426.2  527.21  5457.9  527.26  5501.9  528.74
  5553.1  529.56  5564.3  530.52  5616.2  531.16  5637.7   532.5  5663.3  532.68
#Mann= 3 ,-1 , 0
  4187.2     .05       0  4998.2    .035       0  5004.2     .05       0
Bank Sta=4984.5,5006.8
XS Rating Curve= 0 ,0
Exp/Cntr=0.3,0.1

Type RM Length L Ch R = 1 ,60176   ,843,843,843
BEGIN DESCRIPTION:
FROST CREEK 73.0
END DESCRIPTION:
XS GIS Cut Line= 4
      3453933.18     10545239.47      3453517.65     10544239.81
      3453481.78      10543776.8      3453295.14     10543151.76
#Sta/Elev= 30
  3759.9  524.93  3822.5  524.69  3941.7  521.43  3995.8  521.29  4058.8   519.6
  4093.5   520.4  4188.9  519.91  4348.3   520.7    4396  522.01  4842.5  519.42
  4880.8  517.74  4920.9  518.27    4961  517.19    4971  516.81  4977.5   515.3
  4982.5   515.1  4998.1  513.54  5000.9  513.04  5004.1  513.54  5011.2   514.8
  5071.3  514.57    5098  515.64  5196.7  517.89  5242.4  519.45  5343.6  519.21
  5489.7  521.02  5771.5  527.54    5887   531.9  5953.2  532.92  5959.2   532.5
#Mann= 5 ,-1 , 0
  3759.9     .05       0  4998.1    .035       0  5004.1     .05       0
    5098      .1       0  5196.7     .05       0
Bank Sta=4982.5,5011.2
XS Rating Curve= 0 ,0
Exp/Cntr=0.3,0.1

Type RM Length L Ch R = 1 ,59333   ,1035,1035,1035
BEGIN DESCRIPTION:
FROST CREEK 72.0
END DESCRIPTION:
XS GIS Cut Line= 4
       3454345.5     10545048.48      3454072.06     10544093.64
      3454111.12     10543720.37       3454054.7     10543051.98
#Sta/Elev= 30
  3815.1  524.49  3915.2   523.4  3969.5  522.76  4137.8  521.58  4477.5  516.06
  4560.8  515.41  4633.6  516.93  4680.7  515.86  4685.9  516.33  4714.5  513.89
  4719.7  514.51  4753.4  511.04  4811.8  511.29  4840.5  513.32  4910.9  511.64
  4981.3  511.56  4998.4  509.46  5001.1  508.96  5004.4  509.46  5021.5  511.38
  5061.7  513.25  5252.6  515.91  5354.1  518.24  5513.5  523.52  5583.4  526.64
  5588.4  526.25  5703.1  530.27  5708.1  529.63  5754.4  531.09  5854.4  532.08
#Mann= 5 ,-1 , 0
  3815.1     .05       0  3915.2      .1       0  3969.5     .05       0
  4998.4     .03       0  5004.4     .05       0
Bank Sta=4981.3,5021.5
XS Rating Curve= 0 ,0
Exp/Cntr=0.3,0.1

Type RM Length L Ch R = 1 ,58298   ,855,855,855
BEGIN DESCRIPTION:
FROST CREEK 71.0
END DESCRIPTION:
XS GIS Cut Line= 5
      3454718.77     10544588.46      3454662.34     10544189.12
       3454592.9     10543985.13       3454592.9     10543789.82
      3454276.58     10542953.54
#Sta/Elev= 30
  4278.4  519.82  4437.5  517.43  4628.7  515.65  4759.1  512.51  4795.8  512.59
  4847.9  511.28  4901.4  510.87  4920.7  511.44  4940.7  510.33  4960.7  508.19
  4980.7  508.15  4990.7  507.38  4997.7  505.74  5000.4  505.24  5003.7  505.74
  5010.7  506.24  5020.7  508.51  5040.7  509.79  5208.2  511.67  5400.6   515.9
  5643.5  523.15  5689.3  524.93  5703.9  526.03  5758.9  527.56  5796.2  529.93
  5838.7  530.22  5904.4  532.73  5923.9  532.49  5929.2  533.14  5986.6  535.41
#Mann= 3 ,-1 , 0
  4278.4     .05       0  4997.7     .03       0  5003.7     .05       0
Bank Sta=4980.7,5020.7
XS Rating Curve= 0 ,0
Exp/Cntr=0.3,0.1

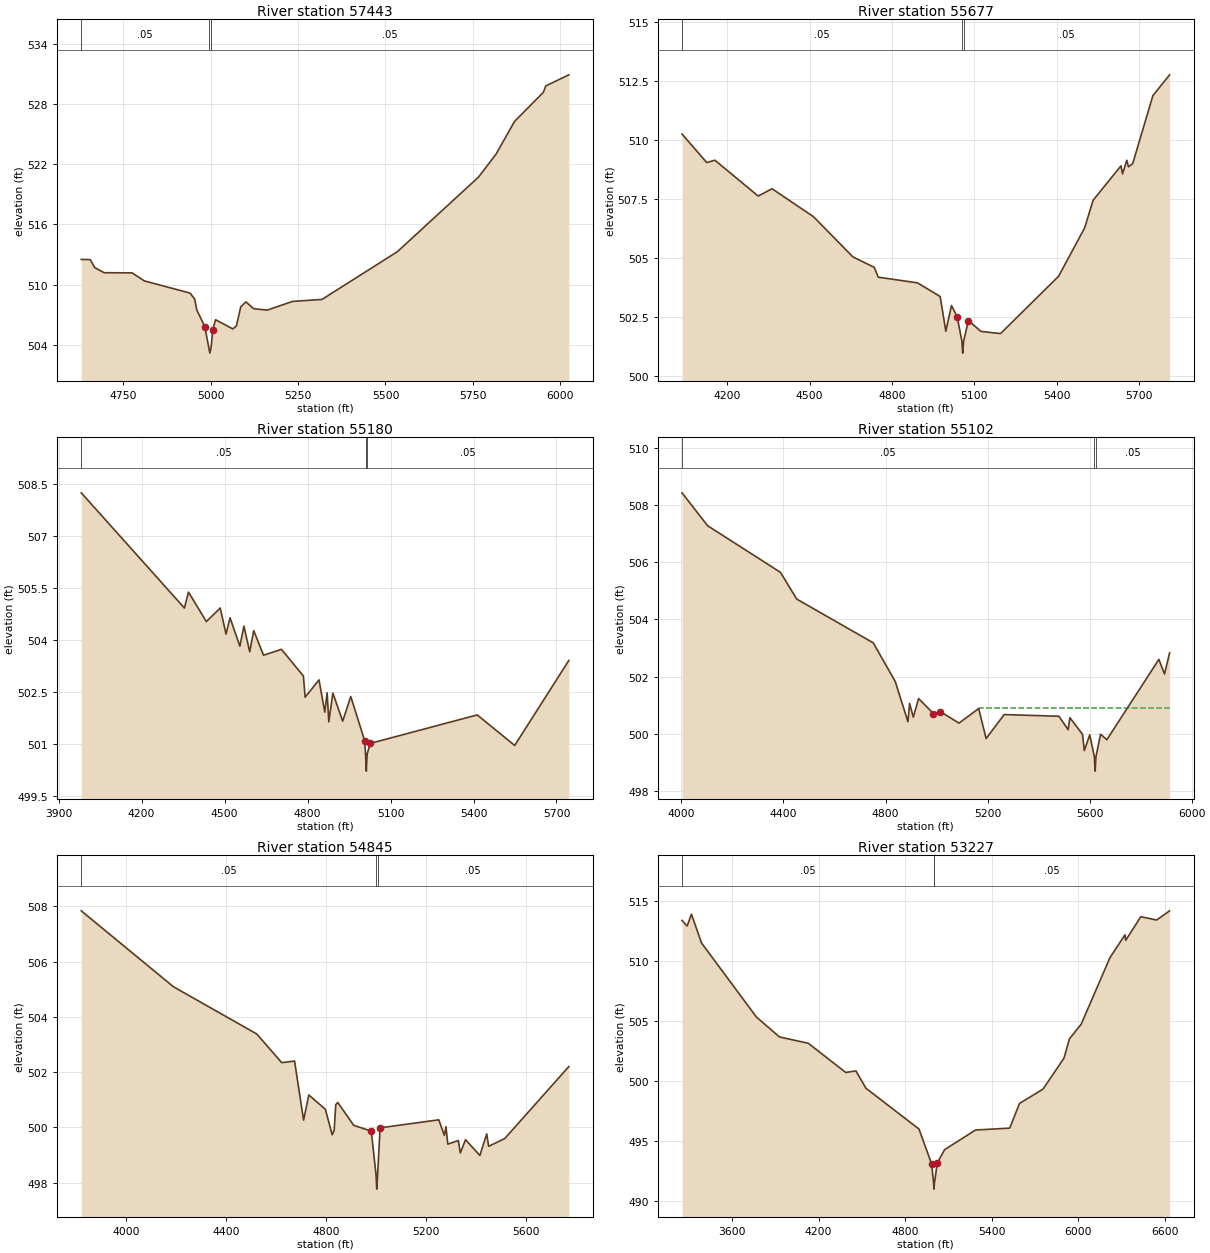
Type RM Length L Ch R = 1 ,57443   ,1766,1766,1766
BEGIN DESCRIPTION:
FROST CREEK 69.0
END DESCRIPTION:
XS GIS Cut Line= 4
      3455354.28     10544018.89      3455274.32     10543720.37
      3455183.17     10543555.44      3454783.88     10542752.52
#Sta/Elev= 30
  4630.2  512.51  4655.6  512.49  4668.8  511.68  4695.6  511.18  4775.7  511.16
  4810.5  510.36  4941.4  509.14  4954.5  508.54  4960.6  507.44  4983.5  505.79
  4995.1  503.64  4997.8  503.14  5001.1  503.64  5006.3  505.48  5014.1  506.48
  5063.5  505.56  5073.7  505.86  5086.3  507.78  5101.2  508.26  5122.9  507.58
  5161.8  507.44  5234.6  508.31  5318.6  508.51    5534  513.28  5766.5  520.75
  5816.9  523.07    5869   526.3  5951.3   529.2  5958.4  529.85  6024.4  530.96
#Mann= 3 ,-1 , 0
  4630.2     .05       0  4995.1     .03       0  5001.1     .05       0
Bank Sta=4983.5,5006.3
XS Rating Curve= 0 ,0
Exp/Cntr=0.3,0.1

Type RM Length L Ch R = 1 ,55677   ,497,497,497
BEGIN DESCRIPTION:
FROST CREEK 67.0
END DESCRIPTION:
XS GIS Cut Line= 4
      3455519.13      10543765.4      3456281.29     10543231.91
      3456252.64     10543114.73      3456627.39     10542492.75
#Sta/Elev= 30
  4034.9  510.24    4125  509.03  4154.6  509.13  4312.5  507.61    4363  507.92
  4514.6  506.73  4657.7  505.03  4735.3  504.59  4750.2  504.17  4893.1  503.93
  4975.8  503.35  4996.4  501.88    5017  502.97  5037.6   502.5  5055.1  501.45
  5057.9  500.95  5061.1  501.45  5078.7  502.33  5124.5  501.87  5195.9  501.78
  5407.5  504.21  5502.7  506.27  5533.1  507.43  5634.7  508.89  5640.5  508.55
  5656.1  509.13  5661.9  508.85  5677.4  508.98  5751.2  511.87    5812  512.75
#Mann= 3 ,-1 , 0
  4034.9     .05       0  5055.1     .03       0  5061.1     .05       0
Bank Sta=5037.6,5078.7
XS Rating Curve= 0 ,0
Exp/Cntr=0.3,0.1

Type RM Length L Ch R = 1 ,55180   ,78,78,78
BEGIN DESCRIPTION:
FROST CREEK 66.0
END DESCRIPTION:
XS GIS Cut Line= 4
      3455785.62     10543646.85      3456856.81     10542856.91
      3457083.37     10542687.64      3457171.89     10542567.88
#Sta/Elev= 30
    3982  508.25  4354.8  504.93  4369.5  505.39  4434.2  504.54  4484.3  504.93
  4505.2  504.18  4519.8  504.65  4555.3  503.83  4569.9  504.41  4590.8  503.67
  4605.4  504.28  4640.9  503.57  4705.7  503.74  4785.1  502.97  4791.3  502.36
  4841.4  502.86  4862.3  501.93  4870.7  502.49  4876.9  501.65  4891.5  502.48
    4927  501.67  4956.3  502.38  5006.4  501.11  5009.6  500.73  5012.4  500.23
  5015.6  500.73  5027.3  501.03  5413.4  501.85  5548.9  500.97  5744.7  503.42
#Mann= 3 ,-1 , 0
    3982     .05       0  5009.6     .03       0  5015.6     .05       0
Bank Sta=5006.4,5027.3
XS Rating Curve= 0 ,0
Exp/Cntr=0.3,0.1

Type RM Length L Ch R = 1 ,55102   ,257,257,257
BEGIN DESCRIPTION:
FROST CREEK 64.0
END DESCRIPTION:
XS GIS Cut Line= 5
      3455862.01     10543690.26      3457052.12     10542799.62
      3457182.33     10542677.23      3457237.02     10542573.06
      3457296.46     10542459.28
#Sta/Elev= 30
  4002.3  508.43  4102.3  507.28  4387.8  505.65  4452.1  504.71  4751.8  503.18
  4837.9  501.83  4887.9  500.42  4894.2  501.06  4908.8  500.58  4929.6  501.23
    4988   500.7  5015.1  500.77    5088  500.37  5165.1  500.88  5194.3  499.83
  5265.1  500.67  5479.8  500.61  5515.8  500.14  5522.7  500.56    5572  499.98
  5579.3  499.41  5600.4  499.96  5618.8  499.19  5621.6  498.69  5624.8  499.19
  5642.9  499.98  5667.5  499.79  5871.5   502.6  5893.6  502.09  5913.5  502.83
#Mann= 3 ,-1 , 0
  4002.3     .05       0  5618.8     .03       0  5624.8     .05       0
#XS Ineff= 2 , 0
                         5164.81          500.91
Permanent Ineff=
       F       F
Bank Sta=4988,5015.1
XS Rating Curve= 0 ,0
Exp/Cntr=0.3,0.1

Type RM Length L Ch R = 1 ,54845   ,1618,1618,1618
BEGIN DESCRIPTION:
FROST CREEK 63.0
END DESCRIPTION:
XS GIS Cut Line= 6
      3455916.71     10543698.05      3456737.19     10543155.18
      3456909.06     10542945.11      3457226.77     10542684.69
      3457284.06     10542563.16      3457343.73     10542425.64
#Sta/Elev= 30
  3820.3  507.84  4188.9  505.09  4522.2  503.38  4622.2  502.34  4673.4   502.4
  4709.5  500.26  4730.5  501.17  4796.7  500.65  4823.9  499.73  4831.8  499.89
  4838.3  500.82  4846.2   500.9  4910.1  500.07  4980.4  499.86  4999.5  498.26
  5002.2  497.76  5005.5  498.26  5015.6  499.98  5250.3  500.27  5272.6  499.71
    5279  500.02  5286.4  499.39  5328.6  499.52  5336.4  499.07  5357.3  499.55
  5414.7  498.98    5442  499.76  5449.8  499.31    5514  499.59  5770.6   502.2
#Mann= 3 ,-1 , 0
  3820.3     .05       0  4999.5     .03       0  5005.5     .05       0
Bank Sta=4980.4,5015.6
XS Rating Curve= 0 ,0
Exp/Cntr=0.3,0.1

Type RM Length L Ch R = 1 ,53227   ,1104,1104,1104
BEGIN DESCRIPTION:
FROST CREEK 61.0
END DESCRIPTION:
XS GIS Cut Line= 4
      3458299.49     10544236.91      3458331.02     10542709.72
       3458138.9     10542348.85      3456719.63     10542079.75
#Sta/Elev= 30
  3253.3  513.42  3288.6  512.95  3318.6  513.94  3388.6  511.53  3768.7  505.35
  3928.7  503.68  4128.8  503.15  4388.8  500.71  4458.8  500.84  4528.8  499.39
  4896.6  495.98  4984.4  493.05  4997.7  491.46  5000.5  490.96  5003.7  491.46
  5022.7  493.13  5073.2  494.25  5288.2   495.9  5525.5  496.06  5593.5  498.12
  5756.4  499.32  5901.6   501.9  5939.6  503.52    6021  504.74  6220.4   510.3
    6325  512.22  6330.1  511.76  6434.7  513.73  6544.3  513.45  6634.2  514.22
#Mann= 3 ,-1 , 0
  3253.3     .05       0  4997.7     .03       0  5003.7     .05       0
Bank Sta=4984.4,5022.7
XS Rating Curve= 0 ,0
Exp/Cntr=0.3,0.1

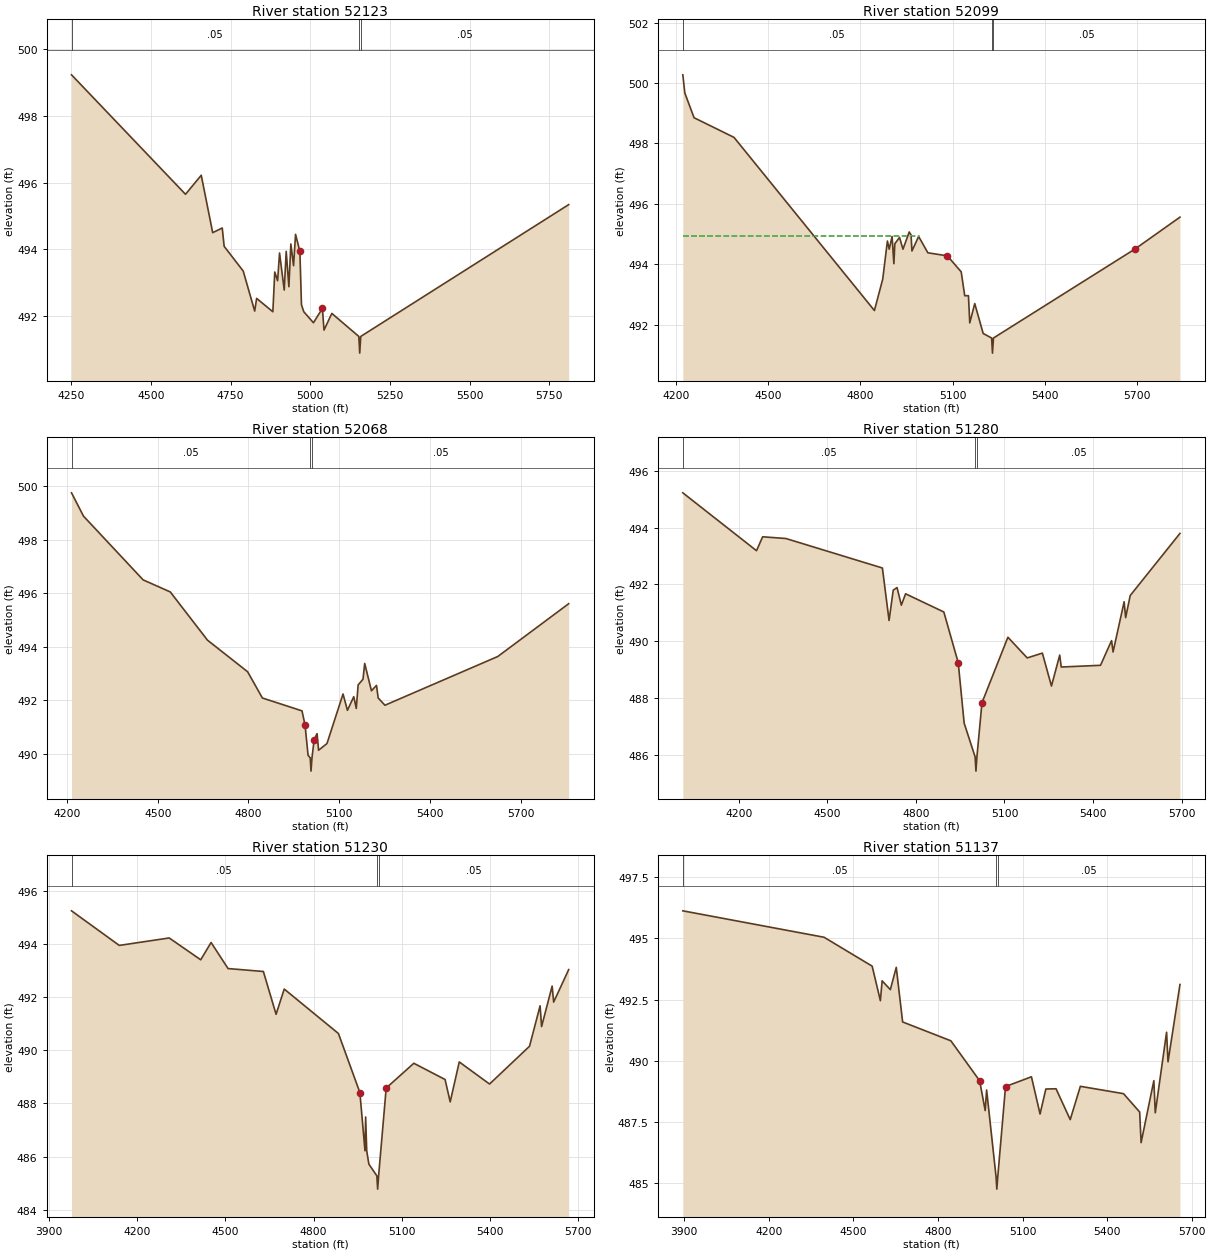
Type RM Length L Ch R = 1 ,52123   ,24,24,24
BEGIN DESCRIPTION:
FROST CREEK 60.01
END DESCRIPTION:
XS GIS Cut Line= 6
      3458741.89     10543067.99      3459108.62     10542525.49
        3459139.     10542484.26      3459125.98     10542393.11
      3458843.86     10541865.77      3458722.03      10541756.1
#Sta/Elev= 30
    4251  499.23  4608.7  495.65  4658.1  496.22    4694   494.5    4724  494.64
    4730  494.09  4789.8  493.35  4825.8  492.15  4831.9  492.53  4882.8  492.13
  4888.8  493.32  4897.7  493.06  4903.8  493.89  4918.5  492.78  4924.7  493.94
  4933.1  492.88  4939.3  494.16  4947.8  493.51    4954  494.45  4967.6  493.94
  4972.6  492.34  4979.9  492.13  5010.2   491.8  5038.3  492.23  5043.3  491.58
  5067.9  492.08  5152.6  491.39  5155.4  490.89  5158.6  491.39  5811.1  495.34
#Mann= 3 ,-1 , 0
    4251     .05       0  5152.6     .03       0  5158.6     .05       0
Bank Sta=4967.6,5038.3
XS Rating Curve= 0 ,0
Exp/Cntr=0.3,0.1

Type RM Length L Ch R = 1 ,52099   ,31,31,31
BEGIN DESCRIPTION:
FROST CREEK 60.0
END DESCRIPTION:
XS GIS Cut Line= 6
      3458767.16     10543107.13      3459140.44     10542525.49
      3459158.53     10542471.24      3459154.19      10542386.6
      3458863.39     10541846.24      3458726.39     10541741.92
#Sta/Elev= 30
  4221.7  500.27  4228.2  499.67  4258.3  498.85  4388.4   498.2  4845.6  492.47
  4872.7  493.51  4887.9  494.77  4893.8   494.5  4903.1  494.92    4909  494.02
  4912.1  494.68  4927.4  494.89  4938.6   494.5    4959  495.07  4964.9  494.97
  4967.8  494.44  4989.6  494.92  5019.7  494.38    5083  494.28  5128.2  493.75
  5139.7  492.96  5151.8  492.96  5156.1  492.06  5172.3   492.7  5199.8  491.71
  5227.3  491.56  5230.1  491.06  5233.3  491.56  5694.8  494.51  5840.6  495.56
#Mann= 3 ,-1 , 0
  4221.7     .05       0  5227.3     .03       0  5233.3     .05       0
#XS Ineff= 2 , 0
          4990.2  494.92
Permanent Ineff=
       F       F
Bank Sta=5083,5694.8
XS Rating Curve= 0 ,0
Exp/Cntr=0.3,0.1

Type RM Length L Ch R = 1 ,52068   ,788,788,788
BEGIN DESCRIPTION:
FROST CREEK 60.02
END DESCRIPTION:
XS GIS Cut Line= 6
      3458819.97     10543115.81      3459180.23     10542503.79
      3459188.91     10542369.24      3459123.81     10542282.44
      3458895.94     10541831.05      3458740.91     10541729.47
#Sta/Elev= 30
  4214.8  499.75  4254.4  498.88  4451.7   496.5  4541.5  496.05  4664.5  494.25
  4797.3  493.07  4846.2  492.09  4977.2  491.61  4987.3  491.08  4997.3  489.95
  5004.3  489.86    5007  489.36  5010.3  489.86  5017.3  490.53    5027  490.76
  5032.1  490.14  5059.8  490.39  5112.9  492.24  5127.5  491.63  5148.4  492.14
  5156.7   491.7  5162.9  492.58    5179  492.79  5184.6  493.38  5206.9  492.36
  5223.6  492.56  5229.2  492.09  5251.5  491.82  5624.9  493.64  5859.3  495.61
#Mann= 3 ,-1 , 0
  4214.8     .05       0  5004.3     .03       0  5010.3     .05       0
Bank Sta=4987.3,5017.3
XS Rating Curve= 0 ,0
Exp/Cntr=0.3,0.1

Type RM Length L Ch R = 1 ,51280   ,50,50,50
BEGIN DESCRIPTION:
FROST CREEK 59.01
END DESCRIPTION:
XS GIS Cut Line= 4
      3459262.15     10542832.18      3459759.53     10542199.39
      3459782.97     10541965.02      3459928.79     10541337.45
#Sta/Elev= 30
  4010.1  495.23  4259.8  493.19  4280.6  493.68  4359.3  493.62  4686.4  492.58
    4709  490.73  4723.1   491.8  4736.1  491.89  4750.6  491.27    4765  491.67
  4894.6  491.03  4943.4  489.24  4963.5  487.11  5000.7  485.92  5003.4  485.42
  5006.7  485.92  5023.8  487.83  5111.7  490.14  5177.2  489.41  5228.5  489.58
  5259.3  488.42  5287.3  489.51  5292.5  489.09  5425.5  489.15    5463  490.02
  5468.1  489.62  5505.6  491.39  5510.7  490.83  5526.2  491.61  5694.8   493.8
#Mann= 3 ,-1 , 0
  4010.1     .05       0  5000.7     .03       0  5006.7     .05       0
Bank Sta=4943.4,5023.8
XS Rating Curve= 0 ,0
Exp/Cntr=0.3,0.1

Type RM Length L Ch R = 1 ,51230   ,93,93,93
BEGIN DESCRIPTION:
FROST CREEK 59.0
END DESCRIPTION:
XS GIS Cut Line= 5
       3459293.4     10542850.41      3459777.76     10542235.85
      3459827.24     10542022.31      3459819.42     10541949.39
      3459970.46     10541350.46
#Sta/Elev= 30
  3975.8  495.24  4138.4  493.94  4308.3  494.22  4415.7   493.4    4451  494.05
  4508.8  493.07    4629  492.96  4672.3  491.35    4700   492.3  4884.5  490.63
  4957.6  488.41    4975  486.22  4977.2  487.49  4980.9  486.22  4988.2  485.72
  5015.4  485.28  5018.1  484.78  5021.4  485.28  5047.2  488.58  5141.3  489.51
  5247.7   488.9  5265.1  488.06    5296  489.56  5399.1  488.73  5535.2  490.15
  5571.2  491.67  5576.3  490.89  5612.2  492.41  5617.4  491.81  5668.5  493.03
#Mann= 3 ,-1 , 0
  3975.8     .05       0  5015.4     .03       0  5021.4     .05       0
Bank Sta=4957.6,5047.2
XS Rating Curve= 0 ,0
Exp/Cntr=0.3,0.1

Type RM Length L Ch R = 1 ,51137   ,44,44,44
BEGIN DESCRIPTION:
FROST CREEK 58.11
END DESCRIPTION:
XS GIS Cut Line= 3
      3459363.66     10542905.16      3459853.28     10542259.29
      3460045.76     10541325.49
#Sta/Elev= 30
  3894.8  496.13    4396  495.05  4566.6  493.87  4595.7  492.46    4602  493.27
  4631.1  492.91  4652.1  493.82  4674.7  491.59  4845.8  490.82  4947.9  489.19
  4967.6  487.97  4972.7  488.81  5006.2  485.26  5008.9  484.76  5012.2  485.26
  5039.8  488.95  5131.7  489.35  5162.3  487.83  5182.8  488.85    5219  488.86
  5269.3   487.6  5305.3  488.96  5458.4  488.66  5515.7  487.91  5520.8  486.66
    5566  489.19  5571.1  487.88  5611.2  491.17  5616.3  489.96  5658.7  493.12
#Mann= 3 ,-1 , 0
  3894.8     .05       0  5006.2     .04       0  5012.2     .05       0
Bank Sta=4947.9,5039.8
XS Rating Curve= 0 ,0
Exp/Cntr=0.3,0.1

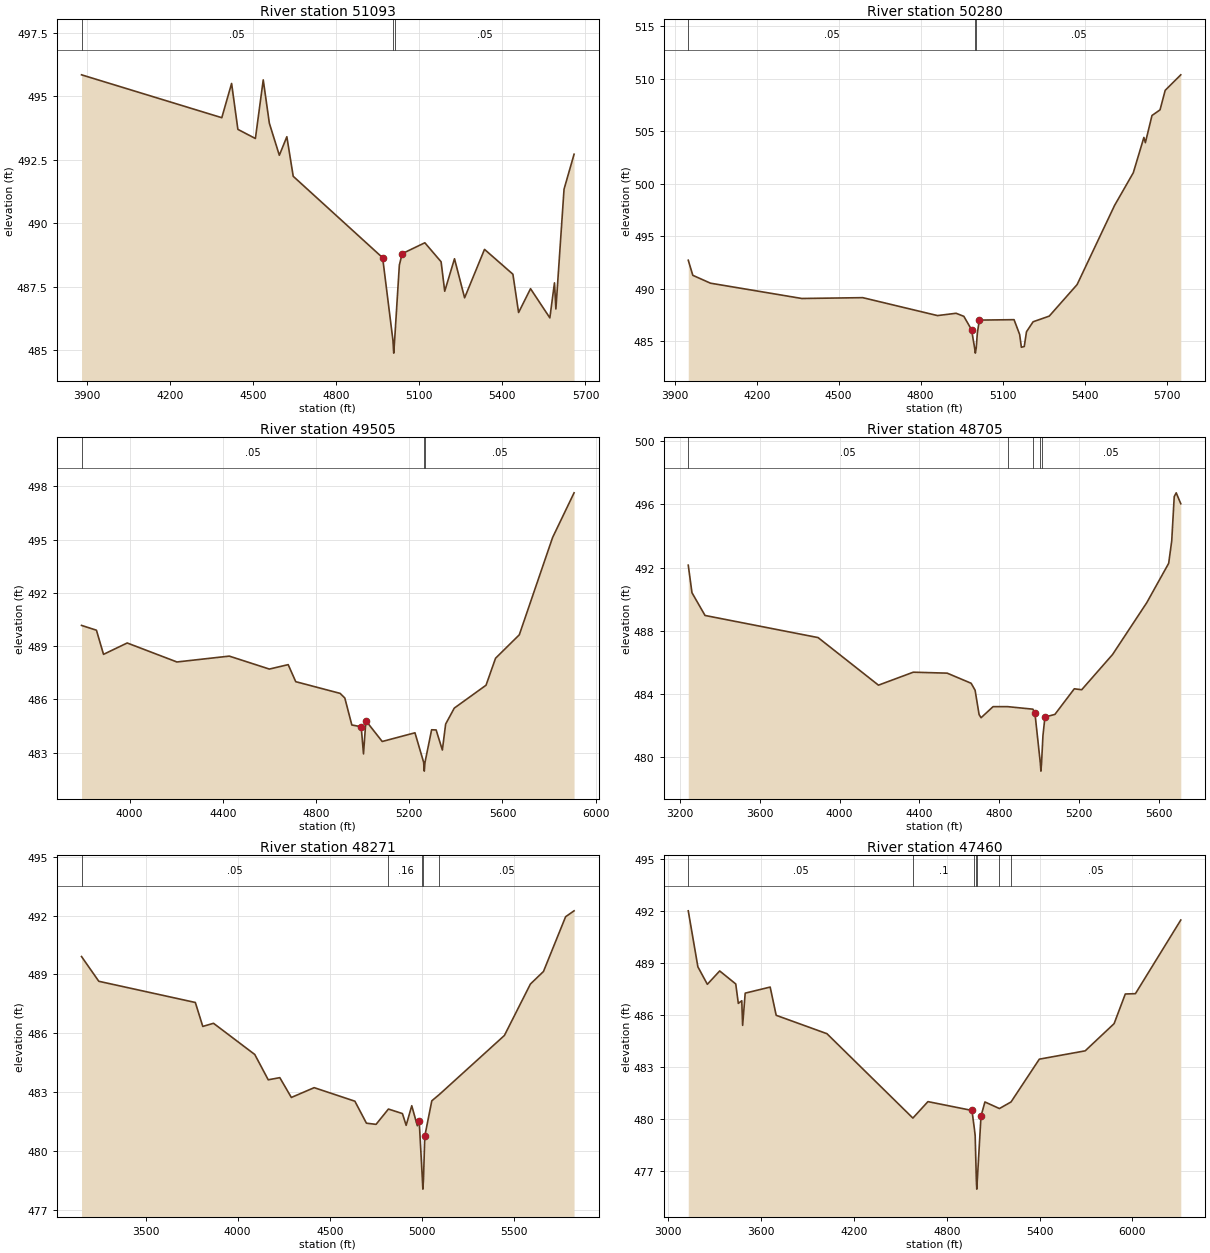
Type RM Length L Ch R = 1 ,51093   ,813,813,813
BEGIN DESCRIPTION:
FROST CREEK 58.1
END DESCRIPTION:
XS GIS Cut Line= 5
      3459410.55     10542899.93       3459868.9     10542300.95
      3459957.44     10542004.08      3459947.03     10541905.12
       3460082.4     10541306.36
#Sta/Elev= 30
  3881.5  495.85  4387.6  494.16    4423  495.51  4445.7   493.7  4508.9  493.34
  4537.2  495.65  4559.3  493.94  4595.3  492.68  4622.4  493.41  4645.4  491.85
  4968.1  488.64  5005.3  485.38  5008.1  484.88  5011.3  485.38  5028.4  488.35
  5038.5   488.8  5120.4  489.23  5179.1  488.48  5192.1  487.32  5227.4   488.6
  5263.9  487.06  5335.7  488.97  5438.2  487.99  5458.7  486.48  5501.8  487.42
  5571.5  486.27  5588.2  487.65  5593.3  486.62  5622.7  491.34  5658.9  492.72
#Mann= 3 ,-1 , 0
  3881.5     .05       0  5005.3     .04       0  5011.3     .05       0
Bank Sta=4968.1,5038.5
XS Rating Curve= 0 ,0
Exp/Cntr=0.3,0.1

Type RM Length L Ch R = 1 ,50280   ,775,775,775
BEGIN DESCRIPTION:
FROST CREEK 58.0
END DESCRIPTION:
XS GIS Cut Line= 4
      3460739.59     10542562.91      3460599.84     10541615.34
      3460417.55     10541437.39      3460197.05     10540890.43
#Sta/Elev= 30
  3949.6  492.71  3966.3  491.27  4030.9  490.52  4365.3  489.06  4588.1  489.14
  4861.6  487.43  4929.7  487.65    4958  487.36  4986.3  486.08  4997.4  484.35
  5000.2  483.85  5003.4  484.35  5007.4  485.74  5014.6     487  5141.8  487.04
  5162.2  485.63  5168.6  484.41  5179.1  484.48  5187.3  485.89  5211.5  486.84
  5270.6  487.38  5372.6  490.39  5509.5  497.93  5578.1  501.05  5616.9  504.42
  5622.3  503.92  5646.5  506.51    5676  507.05  5694.8  508.91  5751.9  510.39
#Mann= 3 ,-1 , 0
  3949.6     .05       0  4997.4     .03       0  5003.4     .05       0
Bank Sta=4986.3,5014.6
XS Rating Curve= 0 ,0
Exp/Cntr=0.3,0.1

Type RM Length L Ch R = 1 ,49505   ,800,800,800
BEGIN DESCRIPTION:
FROST CREEK 57.0
END DESCRIPTION:
XS GIS Cut Line= 4
      3461046.89     10542574.53      3461233.52     10541524.19
       3461198.8     10541103.19      3461077.26     10540491.16
#Sta/Elev= 30
    3794  490.17  3857.9   489.9  3888.3  488.54  3989.9  489.18  4203.2  488.11
  4427.9  488.44  4599.9  487.71  4680.6  487.96    4713     487  4903.5  486.34
  4923.6  486.08  4953.7  484.56  4993.8  484.46  5003.8  482.93  5013.9   484.8
  5084.1  483.63  5224.6  484.12  5261.7  482.46  5264.5  481.96  5267.7  482.46
    5296  484.29  5315.4  484.28  5342.1  483.15  5356.2  484.61  5393.2  485.51
  5529.5   486.8  5570.3  488.32  5672.2  489.64    5815  495.12  5907.2  497.64
#Mann= 3 ,-1 , 0
    3794     .05       0  5261.7    .035       0  5267.7     .05       0
Bank Sta=4993.8,5013.9
XS Rating Curve= 0 ,0
Exp/Cntr=0.3,0.1

Type RM Length L Ch R = 1 ,48705   ,434,434,434
BEGIN DESCRIPTION:
FROST CREEK 56.0
END DESCRIPTION:
XS GIS Cut Line= 4
      3461158.18     10542682.97      3461615.46     10541845.37
      3461637.17     10540864.47      3461389.77     10540391.39
#Sta/Elev= 30
  3241.2  492.15  3259.8  490.41  3325.3  488.97  3892.1  487.57  4194.8  484.56
  4369.3  485.38  4539.3  485.32  4659.3  484.68  4679.3  484.24  4699.3   482.7
  4709.3   482.5  4769.4   483.2  4842.3   483.2  4969.2  483.04  4979.4  482.77
  5006.4  479.62  5009.2  479.12  5012.4  479.62  5019.4  481.36  5029.4  482.54
  5079.4  482.71  5176.6  484.33  5213.7  484.27  5368.5   486.5  5539.5  489.77
  5649.8  492.27  5665.1  493.69  5677.6  496.49  5687.6  496.73  5710.5  496.04
#Mann= 5 ,-1 , 0
  3241.2     .05       0  4842.3      .1       0  4969.2     .05       0
  5006.4    .035       0  5012.4     .05       0
Bank Sta=4979.4,5029.4
XS Rating Curve= 0 ,0
Exp/Cntr=0.3,0.1

Type RM Length L Ch R = 1 ,48271   ,811,811,811
BEGIN DESCRIPTION:
FROST CREEK 55.0
END DESCRIPTION:
XS GIS Cut Line= 4
      3461578.33     10542781.47      3462057.24     10541207.65
      3461989.53     10540775.36      3461554.65     10540374.33
#Sta/Elev= 30
  3152.4  489.91  3246.1  488.65  3770.3  487.57  3810.7  486.35  3868.9  486.51
    4093  484.92  4166.1  483.63  4228.9  483.74  4291.6  482.73  4415.5  483.23
  4636.5  482.54  4699.2  481.42  4751.5  481.36  4818.6  482.14  4894.7  481.91
  4914.9  481.31  4945.3  482.31  4975.6  481.29  4985.8  481.52    5003  478.56
  5005.7  478.06    5009  478.56  5016.1  480.76  5054.2  482.56  5094.9  482.88
  5448.4  485.89  5589.6  488.51  5660.5  489.15  5780.7  491.94  5826.6  492.24
#Mann= 5 ,-1 , 0
  3152.4     .05       0  4818.6     .16       0    5003     .07       0
    5009     .16       0  5094.9     .05       0
Bank Sta=4985.8,5016.1
XS Rating Curve= 0 ,0
Exp/Cntr=0.3,0.1

Type RM Length L Ch R = 1 ,47460   ,884,884,884
BEGIN DESCRIPTION:
FROST CREEK 54.0
END DESCRIPTION:
XS GIS Cut Line= 4
      3461879.27     10542892.81      3462664.88     10541347.63
      3462544.94     10540964.89      3461666.76     10540390.43
#Sta/Elev= 30
  3128.8  491.99    3191  488.76  3252.2  487.75    3332  488.52  3435.8  487.77
  3452.4  486.65  3474.7   486.8  3480.3  485.38  3496.9  487.24  3658.3  487.59
  3697.2  485.96  4025.3   484.9  4580.9  480.03  4678.2  480.98  4962.8  480.47
    4978  479.44  4983.5  479.02  4991.2  476.43    4994  475.93  4997.2  476.43
  5021.2  480.14  5046.6  480.96  5140.3  480.58  5215.3  480.96  5398.2  483.43
  5694.7  483.91  5881.7  485.48    5954  487.19  6019.5  487.21  6312.7  491.46
#Mann= 7 ,-1 , 0
  3128.8     .05       0  4580.9      .1       0    4978     .16       0
  4991.2     .07       0  4997.2     .16       0  5140.3      .1       0
  5215.3     .05       0
Bank Sta=4962.8,5021.2
XS Rating Curve= 0 ,0
Exp/Cntr=0.3,0.1

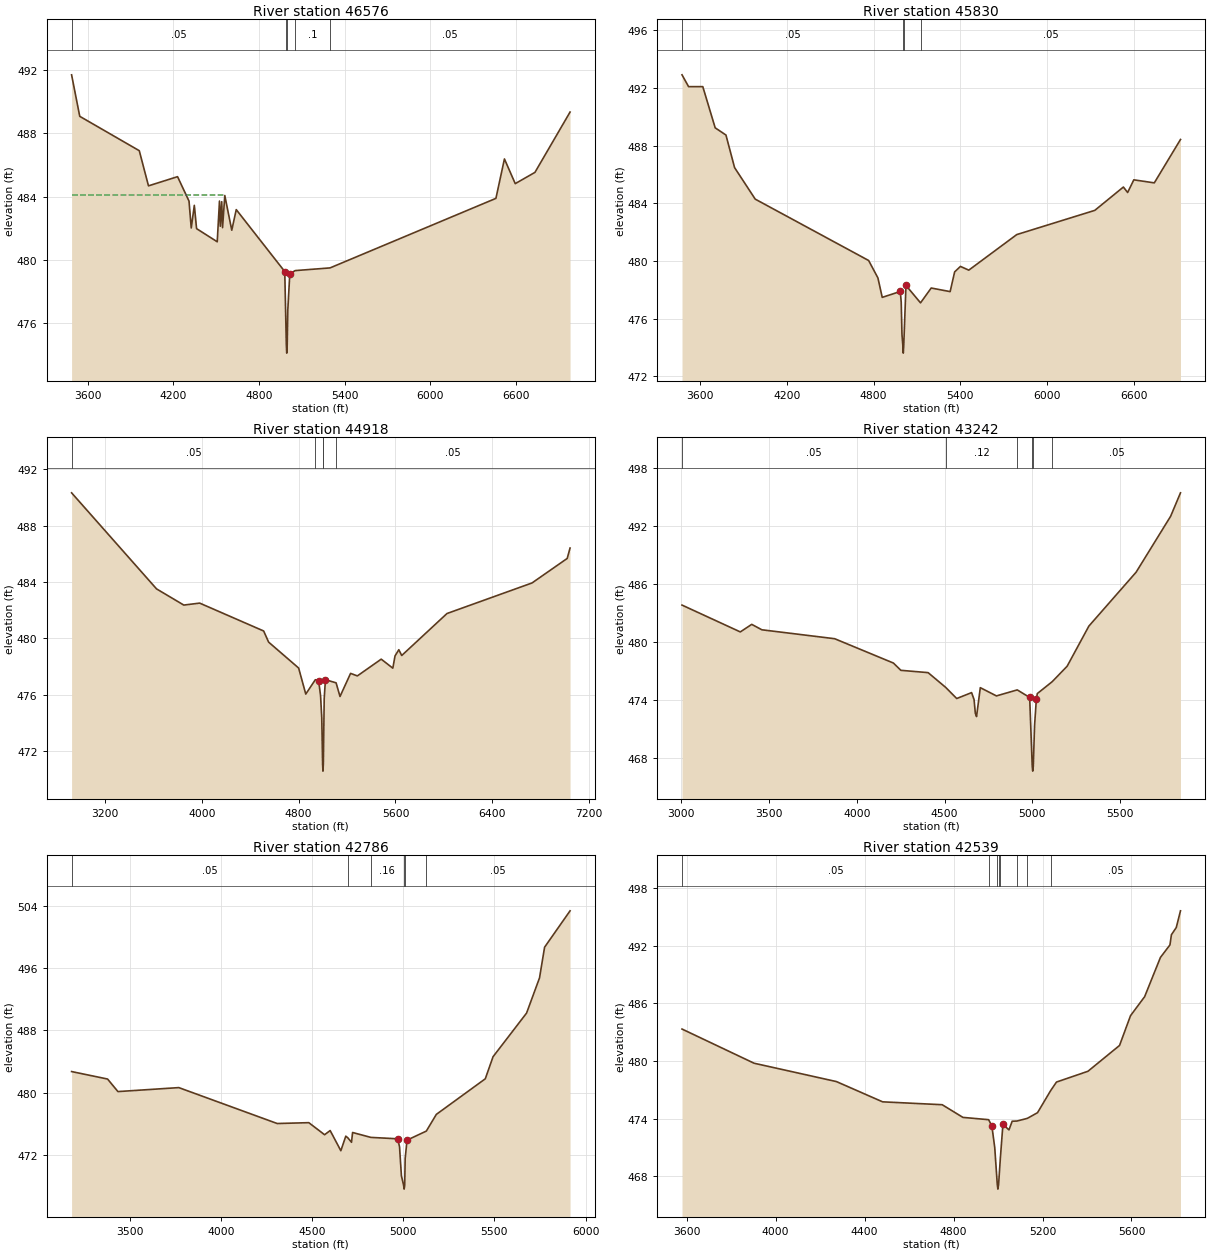
Type RM Length L Ch R = 1 ,46576   ,746,746,746
BEGIN DESCRIPTION:
FROST CREEK 53.0
END DESCRIPTION:
XS GIS Cut Line= 5
      3462036.29     10542942.45      3462745.46     10541718.97
      3462979.84     10541488.93      3463047.11     10541111.33
      3461845.94     10540454.37
#Sta/Elev= 30
  3486.2  491.69  3543.4  489.07  3960.8   486.9  4025.4  484.68  4229.2  485.26
  4309.5  483.72  4325.2  482.02  4346.8  483.45  4362.5  481.98  4507.4  481.15
  4523.2  483.72    4529  482.13  4538.9  483.68  4544.7  482.04  4560.5  484.07
  4609.3  481.88  4640.8  483.18  4980.9  479.27    4992  474.62  4994.8  474.12
    4998  474.62  5002.2  476.84  5016.3  479.14  5054.4  479.33  5298.4   479.5
  6461.5  483.89  6521.2  486.38    6597  484.82    6735  485.53  6981.4  489.34
#Mann= 5 ,-1 , 0
  3486.2     .05       0    4992    .035       0    4998     .05       0
  5054.4      .1       0  5298.4     .05       0
#XS Ineff= 2 , 0
         4560.67  484.12
Permanent Ineff=
       F       F
Bank Sta=4980.9,5016.3
XS Rating Curve= 0 ,0
Exp/Cntr=0.3,0.1

Type RM Length L Ch R = 1 ,45830   ,912,912,912
BEGIN DESCRIPTION:
FROST CREEK 52.0
END DESCRIPTION:
XS GIS Cut Line= 4
      3462900.17     10542852.36      3463464.42     10541619.68
      3463282.13     10541020.72      3461922.95     10540466.78
#Sta/Elev= 30
  3474.2  492.92  3519.7   492.1    3618   492.1  3703.8  489.24  3778.3  488.74
  3837.9  486.48  3980.9  484.29  4765.7  480.03  4829.9  478.82  4859.7  477.47
  4984.6  477.88  4991.1  477.14  4996.4  474.88  5002.5   474.1  5005.3   473.6
  5008.5   474.1    5024   478.3  5124.7  477.09  5198.7  478.12  5329.6  477.87
  5360.9  479.24    5401  479.62  5458.7  479.36  5790.8  481.83  6330.7  483.51
  6528.5  485.13    6558  484.75  6600.7  485.63  6742.5  485.42  6923.7  488.43
#Mann= 4 ,-1 , 0
  3474.2     .05       0  5002.5    .035       0  5008.5     .05       0
  5124.7     .05       0
Bank Sta=4984.6,5024
XS Rating Curve= 0 ,0
Exp/Cntr=0.3,0.1

Type RM Length L Ch R = 1 ,44918   ,1676,1676,1676
BEGIN DESCRIPTION:
FROST CREEK 51.0
END DESCRIPTION:
XS GIS Cut Line= 5
      3463091.15     10543147.48      3463837.69     10541476.45
      3463794.28     10541038.08      3463776.92     10540955.62
      3462079.26     10540484.17
#Sta/Elev= 30
    2925  490.34  3626.5  483.52  3851.8  482.37  3982.8  482.51  4511.3  480.53
  4552.3  479.74  4800.2   477.9  4859.1  476.05    4938  477.07  4965.1     477
  4981.1  475.96  4991.2  474.36  4998.2  471.08    5001  470.58  5004.2  471.08
  5011.3  475.71  5021.3  477.07  5109.5  476.85  5141.9  475.88  5229.2  477.52
  5285.1  477.34  5482.2  478.53    5578  477.89  5596.3  478.76  5627.5   479.2
  5651.7  478.79  6025.3  481.77  6727.6  483.94  7018.2  485.68  7041.9  486.42
#Mann= 5 ,-1 , 0
    2925     .05       0    4938     .16       0  4998.2     .07       0
  5004.2     .16       0  5109.5     .05       0
Bank Sta=4965.1,5021.3
XS Rating Curve= 0 ,0
Exp/Cntr=0.3,0.1

Type RM Length L Ch R = 1 ,43242   ,456,456,456
BEGIN DESCRIPTION:
FROST CREEK 50.0
END DESCRIPTION:
XS GIS Cut Line= 5
      3463487.85     10542524.02      3463998.76     10541698.87
      3464643.24     10541088.72      3464587.69     10540838.72
      3464775.18     10540137.35
#Sta/Elev= 30
    3004  483.82  3336.1  481.05  3401.2  481.83  3459.1  481.27  3873.8  480.35
  4208.4  477.84  4250.9  477.09  4406.2  476.85  4506.2  475.33  4569.2  474.18
  4653.9  474.79    4668  474.07  4675.2  472.66  4682.1  472.32  4703.6   475.3
  4795.4  474.45    4914  475.07  4984.8  474.29  4999.4  467.19  5002.2  466.69
  5005.4  467.19  5012.7  471.39  5022.9  474.14  5028.3  474.69  5113.3  475.92
  5198.2  477.51  5322.1  481.65  5591.2  487.21  5787.9  492.98  5844.1   495.4
#Mann= 6 ,-1 , 0
    3004     .05       0  4506.2     .12       0    4914     .16       0
  4999.4     .07       0  5005.4     .16       0  5113.3     .05       0
Bank Sta=4984.8,5022.9
XS Rating Curve= 0 ,0
Exp/Cntr=0.3,0.1

Type RM Length L Ch R = 1 ,42786   ,247,247,247
BEGIN DESCRIPTION:
FROST CREEK 49.0
END DESCRIPTION:
XS GIS Cut Line= 5
      3463597.21     10542414.67      3464369.98     10541466.34
      3464740.46     10541248.44      3464998.82     10541183.37
      3465594.62     10540626.92
#Sta/Elev= 30
  3180.3  482.69  3377.7  481.73  3434.6  480.12  3768.5  480.63  4308.5  476.02
  4481.7  476.13  4568.5  474.58  4598.9  475.12  4657.5  472.53  4684.7   474.4
  4696.4  474.17  4716.1  473.61  4721.9  474.87  4822.1  474.24  4969.2  474.06
  4979.5  473.04  4989.8  469.31  5001.9   468.1  5004.7   467.6  5007.9   468.1
  5010.4  471.52  5020.7  473.89  5126.6  475.05  5181.3  477.19    5450  481.76
  5492.5  484.59  5676.6   490.2  5747.5  494.71  5775.3  498.65  5915.1  503.32
#Mann= 6 ,-1 , 0
  3180.3     .05       0  4696.4     .12       0  4822.1     .16       0
  5001.9     .07       0  5007.9     .16       0  5126.6     .05       0
Bank Sta=4969.2,5020.7
XS Rating Curve= 0 ,0
Exp/Cntr=0.3,0.1

Type RM Length L Ch R = 1 ,42539   ,867,867,867
BEGIN DESCRIPTION:
FROST CREEK 48.0
END DESCRIPTION:
XS GIS Cut Line= 4
      3464202.25     10542592.23      3464941.85     10541470.66
      3465094.63     10541279.69      3465583.68     10540846.14
#Sta/Elev= 30
  3578.8  483.33  3902.9  479.77  4273.1  477.86  4480.8  475.75  4748.8  475.45
  4842.1  474.13  4957.6  473.89  4972.2  473.23  4985.1  470.99  4996.5  467.16
  4999.2  466.66  5002.5  467.16  5010.1   469.8  5021.9   473.4  5049.1  472.83
  5063.5  473.73  5085.1  473.75  5131.9  474.03  5177.5  474.62  5236.6  476.92
  5262.8  477.81  5404.1  478.93  5546.3  481.62  5595.7  484.72  5659.2   486.7
  5730.3  490.79    5773  492.09  5779.6  493.15  5801.4   493.9  5820.4  495.64
#Mann= 8 ,-1 , 0
  3578.8     .05       0  4957.6     .16       0  4996.5     .07       0
  5002.5     .16       0  5010.1     .12       0  5085.1     .16       0
  5131.9     .12       0  5236.6     .05       0
Bank Sta=4972.2,5021.9
XS Rating Curve= 0 ,0
Exp/Cntr=0.3,0.1