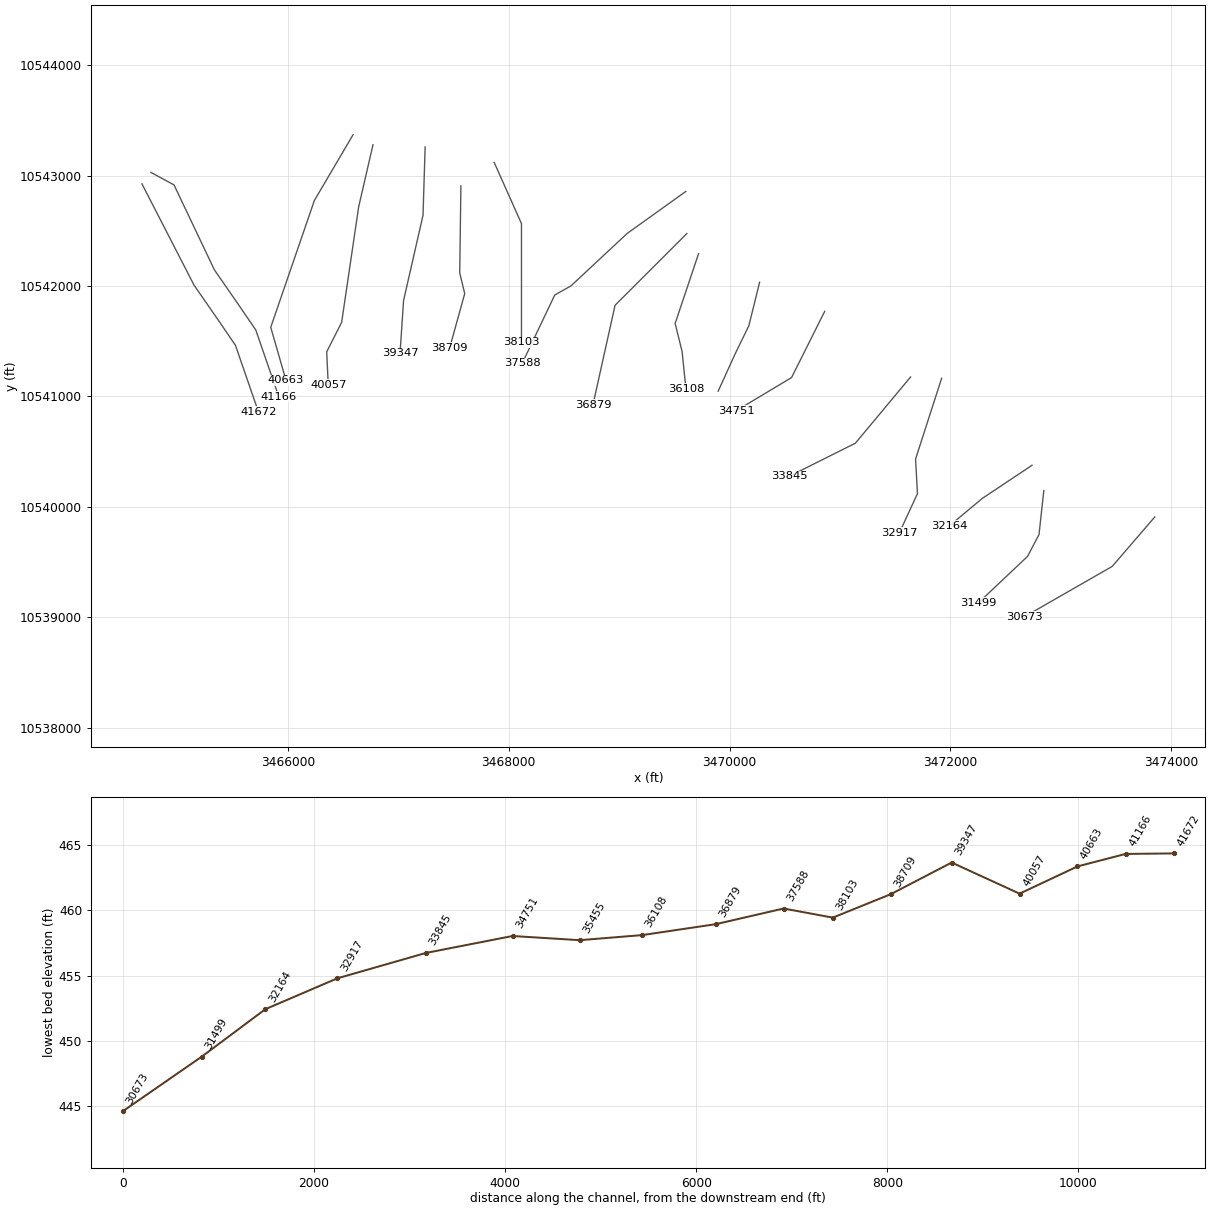
HEC-RAS study FROST CREEK.prj: FROST CREEK Base Level Engineering

--- FROST CREEK.g01 (geometry) --- (continued)

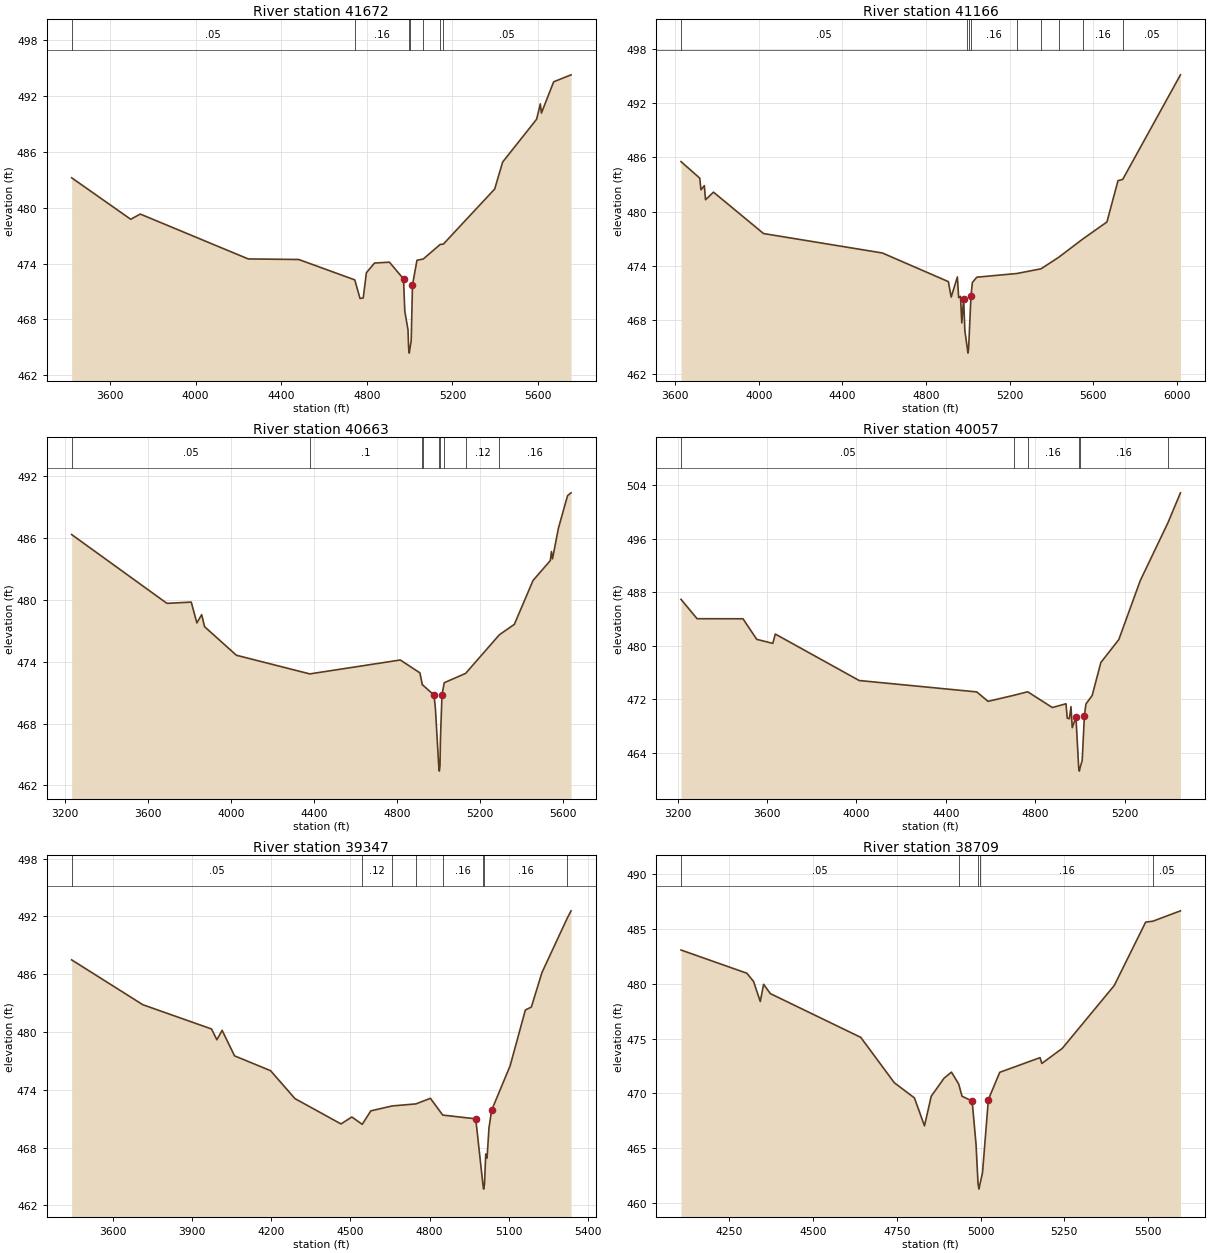
Type RM Length L Ch R = 1 ,41672   ,506,506,506
BEGIN DESCRIPTION:
FROST CREEK 47.1
END DESCRIPTION:
XS GIS Cut Line= 5
      3464678.06      10542927.2      3465150.19     10542008.86
      3465368.94     10541692.88      3465525.19     10541463.72
      3465733.54      10540859.5
#Sta/Elev= 30
  3420.9  483.22    3697  478.76  3741.6  479.32  4246.1   474.5  4481.9  474.44
  4743.8  472.25  4768.4  470.25  4783.2  470.31  4798.1  473.02  4836.2  474.06
  4905.7  474.15  4971.5  472.36  4977.5   468.9  4992.5  466.88  4995.5  464.88
  4998.3  464.38  5001.5  464.88  5007.4  465.71  5013.4   471.7  5034.4  474.36
  5063.6  474.49    5143  476.06  5157.5  476.09  5397.4  482.01  5434.7  484.91
  5593.4  489.51  5610.6  491.16  5615.8  490.17    5673  493.53  5754.3  494.28
#Mann= 7 ,-1 , 0
  3420.9     .05       0  4743.8     .16       0  4995.5     .07       0
  5001.5     .16       0  5063.6     .12       0    5143     .16       0
  5157.5     .05       0
Bank Sta=4971.5,5013.4
XS Rating Curve= 0 ,0
Exp/Cntr=0.3,0.1

Type RM Length L Ch R = 1 ,41166   ,503,503,503
BEGIN DESCRIPTION:
FROST CREEK 47.0
END DESCRIPTION:
XS GIS Cut Line= 6
      3464760.11     10543030.41      3464968.55     10542917.57
      3465334.21     10542147.75      3465552.96     10541831.77
      3465709.21     10541602.61      3465917.31     10540999.13
#Sta/Elev= 30
  3627.5  485.53  3717.2   483.7  3722.9  482.41  3739.1  482.87  3744.8  481.31
  3782.9  482.15  4022.4  477.57  4590.7  475.42  4906.6  472.25    4920  470.54
  4949.7  472.77  4955.8  470.48  4964.6  470.62  4970.7  467.68  4979.5  470.37
  4985.5  466.82  4997.4  464.84  5000.2  464.34  5003.4  464.84  5014.7  470.67
  5021.4  472.15  5042.3  472.74  5234.5  473.15  5350.1  473.67  5434.8  474.95
  5549.3  476.96  5665.1  478.85    5718  483.42  5740.6  483.56  6016.8  495.13
#Mann= 9 ,-1 , 0
  3627.5     .05       0  4997.4    .035       0  5003.4     .05       0
  5014.7     .16       0  5234.5     .12       0  5350.1     .16       0
  5434.8     .12       0  5549.3     .16       0  5740.6     .05       0
Bank Sta=4979.5,5014.7
XS Rating Curve= 0 ,0
Exp/Cntr=0.3,0.1

Type RM Length L Ch R = 1 ,40663   ,606,606,606
BEGIN DESCRIPTION:
FROST CREEK 46.0
END DESCRIPTION:
XS GIS Cut Line= 4
      3466590.26     10543372.07       3466239.8     10542776.01
      3465844.63     10541626.91      3465983.18     10541145.45
#Sta/Elev= 30
  3232.9  486.35  3692.3  479.67  3809.5  479.79  3836.7  477.77  3859.8  478.57
  3873.9   477.4  4027.2  474.63    4381  472.82  4817.3  474.17  4911.9  472.92
  4923.8  471.74  4925.6  471.74  4979.7  470.76  4986.5  469.48  5002.6  463.88
  5005.4  463.38  5008.6  463.88  5010.9  466.54  5018.2  470.74  5028.8  471.96
  5132.3  472.87  5294.9  476.62  5367.1  477.63  5457.2  481.89  5540.4  483.82
  5545.9   484.7  5551.1  483.99  5579.6  486.97  5623.7  490.13  5640.5   490.4
#Mann= 9 ,-1 , 0
  3232.9     .05       0    4381      .1       0  4923.8     .16       0
  4925.6     .12       0  5002.6     .07       0  5008.6     .12       0
  5028.8     .16       0  5132.3     .12       0  5294.9     .16       0
Bank Sta=4979.7,5018.2
XS Rating Curve= 0 ,0
Exp/Cntr=0.3,0.1

Type RM Length L Ch R = 1 ,40057   ,710,710,710
BEGIN DESCRIPTION:
FROST CREEK 45.0
END DESCRIPTION:
XS GIS Cut Line= 5
      3466770.83     10543281.78      3466640.95       10542718.
      3466486.99     10541672.05      3466351.58     10541404.69
      3466365.45     10541106.38
#Sta/Elev= 30
  3215.5  486.94  3287.5  484.05  3492.7  484.04  3554.3  480.97  3626.1  480.37
  3637.2  481.76  4012.7  474.82  4538.3  473.12  4588.9  471.71  4706.4  472.63
  4766.2  473.14  4876.5  470.79  4937.7  471.35  4943.3   469.2  4952.6  469.11
  4959.9  470.92  4965.6  467.78  4982.2  469.35  4994.5  461.79  4997.2  461.29
  5000.5  461.79  5010.1  462.88  5019.9  469.52  5026.8  471.32  5054.7  472.58
  5093.6  477.51    5174  480.94  5269.6  489.72  5393.8  498.39  5449.6  502.85
#Mann= 6 ,-1 , 0
  3215.5     .05       0  4706.4      .1       0  4766.2     .16       0
  4994.5     .07       0  5000.5     .16       0  5393.8     .05       0
Bank Sta=4982.2,5019.9
XS Rating Curve= 0 ,0
Exp/Cntr=0.3,0.1

Type RM Length L Ch R = 1 ,39347   ,638,638,638
BEGIN DESCRIPTION:
FROST CREEK 43.0
END DESCRIPTION:
XS GIS Cut Line= 4
      3467243.06     10543261.04      3467223.96     10542642.55
      3467047.69     10541869.55      3467015.72     10541391.65
#Sta/Elev= 30
  3444.9  487.49  3714.4  482.83  3974.6  480.31  3994.6  479.19  4014.6  480.17
  4061.6  477.52    4198  475.98  4290.3  473.08  4464.6  470.45  4505.7  471.17
  4545.1  470.41  4577.5  471.81  4659.1  472.32  4748.2  472.53  4803.1  473.11
  4849.7  471.37  4974.7  470.98  5001.8  464.18  5004.5  463.68  5007.8  464.18
  5012.5  467.33  5017.5   466.9  5024.8  470.04  5034.8  471.87    5105   476.5
  5162.5  482.28  5185.2  482.59  5225.3  486.17  5320.7   491.8  5335.5  492.58
#Mann= 8 ,-1 , 0
  3444.9     .05       0  4545.1     .12       0  4659.1     .16       0
  4748.2     .12       0  4849.7     .16       0  5001.8     .07       0
  5007.8     .16       0  5320.7     .05       0
Bank Sta=4974.7,5034.8
XS Rating Curve= 0 ,0
Exp/Cntr=0.3,0.1

Type RM Length L Ch R = 1 ,38709   ,606,606,606
BEGIN DESCRIPTION:
FROST CREEK 42.0
END DESCRIPTION:
XS GIS Cut Line= 4
      3467566.85     10542908.13      3467556.44     10542119.97
      3467601.58     10541932.47      3467465.71     10541441.62
#Sta/Elev= 30
  4106.2  483.09  4302.7  480.97  4322.7  480.22  4342.7  478.39  4352.7  479.96
  4372.7  479.11  4642.7  475.11  4742.7  470.97  4802.8  469.58  4832.8  467.03
  4852.8  469.73  4891.1  471.38  4913.3  471.94    4935  470.84  4944.7  469.74
    4975  469.29  4986.6  465.35  4992.6  461.75  4995.3  461.25  4998.6  461.75
  5005.9  462.74  5023.4  469.43  5057.3  471.92  5177.7  473.26  5182.9  472.73
  5243.8   474.1  5399.1  479.85  5492.8  485.64  5514.2  485.72  5596.6  486.67
#Mann= 5 ,-1 , 0
  4106.2     .05       0    4935     .16       0  4992.6     .07       0
  4998.6     .16       0  5514.2     .05       0
Bank Sta=4975,5023.4
XS Rating Curve= 0 ,0
Exp/Cntr=0.3,0.1

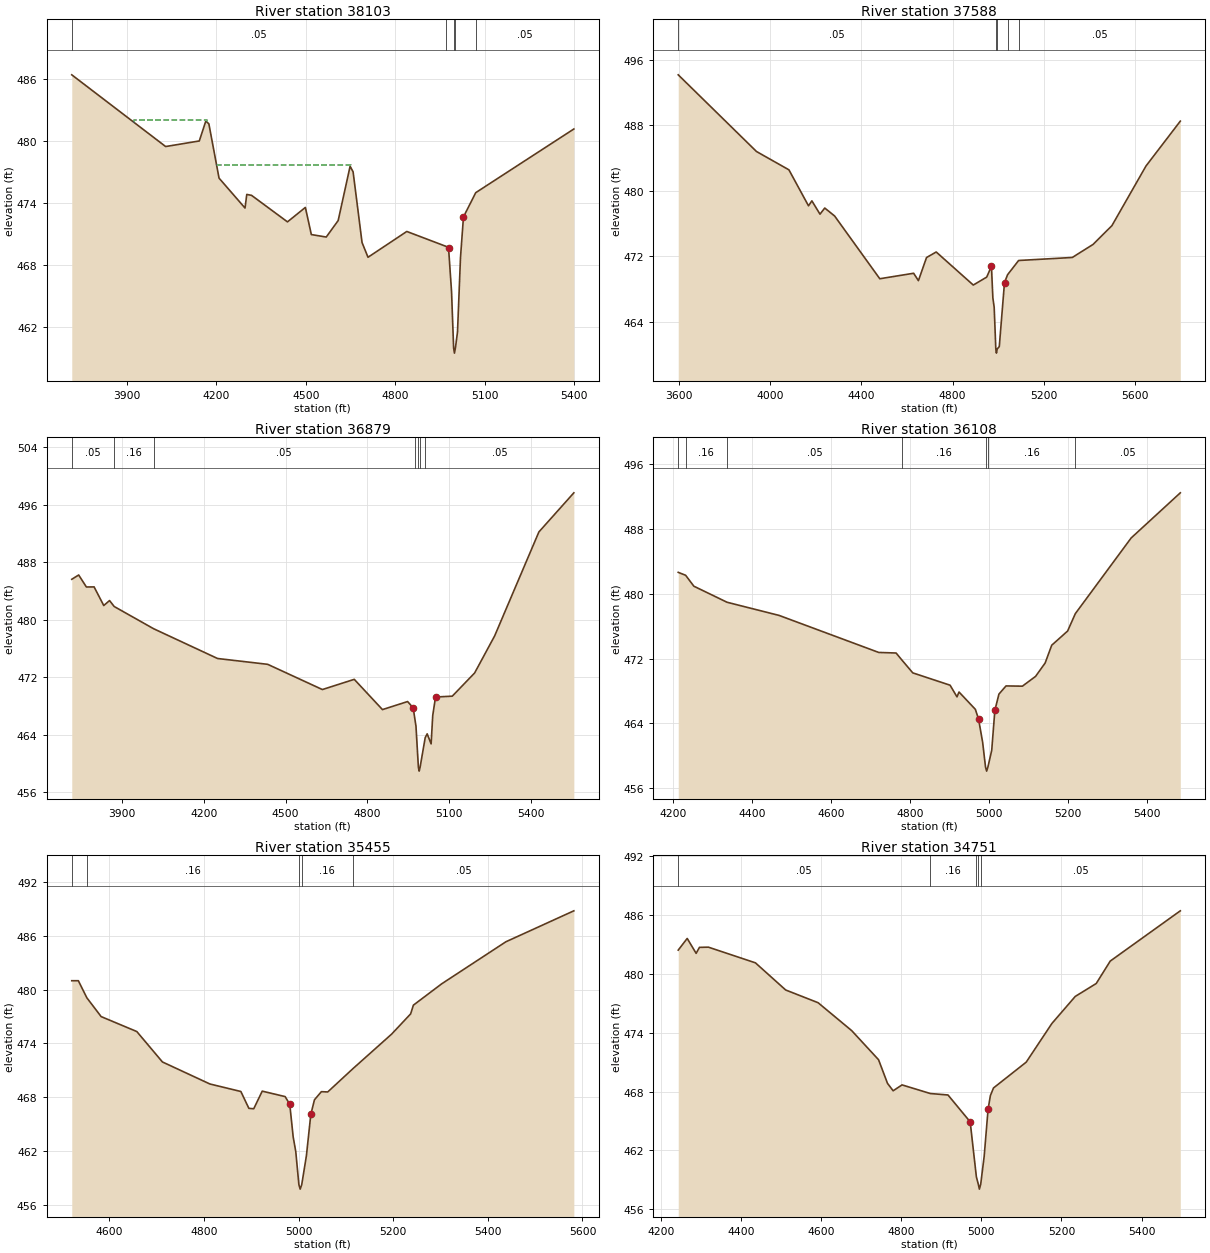
Type RM Length L Ch R = 1 ,38103   ,515,515,515
BEGIN DESCRIPTION:
FROST CREEK 40.0
END DESCRIPTION:
XS GIS Cut Line= 4
      3467868.07     10543122.09      3468115.72     10542566.55
      3468115.72     10541941.64      3468115.72     10541491.69
#Sta/Elev= 30
  3715.3  486.42    4030  479.47  4142.8  480.01  4164.7  481.94  4174.9  481.67
    4209  476.41  4296.1  473.51    4302  474.83    4318  474.74  4438.4  472.17
  4498.4  473.57  4518.4  470.94  4568.4   470.7  4608.4   472.3  4648.4  477.56
  4658.4  477.02  4688.4  470.17  4708.4  468.74  4838.4  471.24  4971.4  469.78
  4978.4  469.65  4988.4  465.43  4995.4  459.95  4998.2  459.45  5001.4  459.95
  5008.4   461.5  5018.4  468.71  5028.4  472.65  5069.5     475  5398.4  481.17
#Mann= 5 ,-1 , 0
  3715.3     .05       0  4971.4     .12       0  4995.4     .07       0
  5001.4     .12       0  5069.5     .05       0
#XS Ineff= 2 ,-1
 3925.34 4168.58  482.05 4197.41  4650.1  477.68
Permanent Ineff=
       F       F
Bank Sta=4978.4,5028.4
XS Rating Curve= 0 ,0
Exp/Cntr=0.3,0.1

Type RM Length L Ch R = 1 ,37588   ,709,709,709
BEGIN DESCRIPTION:
FROST CREEK 39.0
END DESCRIPTION:
XS GIS Cut Line= 5
      3469604.16      10542858.2      3469073.99     10542478.36
      3468563.38     10542001.91      3468416.88     10541919.54
      3468122.42     10541300.55
#Sta/Elev= 30
  3595.7  494.16  3939.2  484.79  4081.6  482.55  4167.6  478.15  4182.4  478.76
    4218  477.13  4238.9  477.88  4282.2  476.91  4480.5  469.24  4629.1  469.91
  4650.1  469.01  4685.7  471.83  4728.2  472.51  4890.9  468.47  4949.9  469.44
  4970.7  470.77  4976.9  466.91  4982.7  465.75  4989.9  460.65  4992.6  460.15
  4995.9  460.65  5005.1  460.95    5028  468.78  5041.5  469.73    5090  471.47
  5325.6  471.84  5416.5  473.43  5499.6  475.73  5649.2  483.02  5799.8   488.5
#Mann= 5 ,-1 , 0
  3595.7     .05       0  4989.9    .035       0  4995.9     .05       0
  5041.5     .12       0    5090     .05       0
Bank Sta=4970.7,5028
XS Rating Curve= 0 ,0
Exp/Cntr=0.3,0.1

Type RM Length L Ch R = 1 ,36879   ,771,771,771
BEGIN DESCRIPTION:
FROST CREEK 38.0
END DESCRIPTION:
XS GIS Cut Line= 3
      3469613.21     10542476.38      3468963.37     10541826.54
      3468763.39      10540926.6
#Sta/Elev= 30
  3716.1  485.64  3741.4  486.24  3769.7  484.57    3798  484.58  3833.4  481.99
  3854.6  482.68  3871.8  481.85  4016.3  478.76  4250.6  474.62  4434.4  473.81
    4635   470.3  4751.9  471.72  4855.3  467.51  4947.4  468.63  4967.9  467.76
  4974.1  466.21  4978.2  465.19  4987.1  459.45  4989.9  458.95  4993.1  459.45
    5012  463.61  5019.2  464.14  5033.7  462.74  5039.6  466.68  5049.9  469.26
  5111.3  469.38  5193.3  472.61  5266.7  477.77  5428.9  492.23    5557  497.67
#Mann= 7 ,-1 , 0
  3716.1     .05       0  3871.8     .16       0  4016.3     .05       0
  4974.1     .16       0  4987.1     .07       0  4993.1     .16       0
    5012     .05       0
Bank Sta=4967.9,5049.9
XS Rating Curve= 0 ,0
Exp/Cntr=0.3,0.1

Type RM Length L Ch R = 1 ,36108   ,653,653,653
BEGIN DESCRIPTION:
FROST CREEK 36.0
END DESCRIPTION:
XS GIS Cut Line= 4
      3469719.65     10542294.28      3469507.41     10541661.84
      3469570.33     10541408.16      3469605.05      10541067.9
#Sta/Elev= 30
  4213.5  482.63  4232.2  482.27  4253.1  480.92  4337.1  478.94  4468.6  477.32
  4720.9  472.75  4764.8  472.68  4780.6  471.75    4807  470.23  4901.4  468.71
  4918.9  467.27    4924  467.87  4965.4  465.73  4973.5  464.52  4983.8  461.67
  4991.1  458.61  4993.9  458.11  4997.1  458.61  5006.8  460.68  5014.7   465.6
    5025  467.61    5043  468.62  5084.4  468.59  5117.8   469.8    5142  471.45
  5158.6  473.64  5198.8  475.39  5218.4  477.54  5359.6  486.87    5484  492.44
#Mann= 7 ,-1 , 0
  4213.5     .05       0  4232.2     .16       0  4337.1     .05       0
  4780.6     .16       0  4991.1     .07       0  4997.1     .16       0
  5218.4     .05       0
Bank Sta=4973.5,5014.7
XS Rating Curve= 0 ,0
Exp/Cntr=0.3,0.1

Type RM Length L Ch R = 1 ,35455   ,704,704,704
BEGIN DESCRIPTION:
FROST CREEK 34.0
END DESCRIPTION:
XS GIS Cut Line= 4
      3470272.43     10542035.13      3470175.36     10541641.78
      3470052.96      10541390.8      3469896.91     10541047.49
#Sta/Elev= 30
  4520.3  481.01  4534.2  481.01  4552.2   479.1  4582.4     477  4657.8  475.33
    4712  471.93  4812.3  469.47  4877.8  468.63  4894.7  466.75    4905   466.7
    4923  468.67  4971.4  468.06  4981.2   467.2  4988.4  463.56  4993.9  461.91
  5000.5  458.22  5003.2  457.72  5006.5  458.22  5016.4  461.46  5025.7  466.07
  5033.4   467.7    5048  468.61  5061.5  468.58  5114.7  471.18  5196.7  475.05
  5236.7   477.3  5242.6  478.28  5302.6  480.67  5438.1  485.36  5581.8  488.82
#Mann= 5 ,-1 , 0
  4520.3     .05       0  4552.2     .16       0  5000.5     .07       0
  5006.5     .16       0  5114.7     .05       0
Bank Sta=4981.2,5025.7
XS Rating Curve= 0 ,0
Exp/Cntr=0.3,0.1

Type RM Length L Ch R = 1 ,34751   ,906,906,906
BEGIN DESCRIPTION:
FROST CREEK 33.0
END DESCRIPTION:
XS GIS Cut Line= 3
      3470862.05     10541771.65      3470562.06     10541171.66
      3470062.05     10540871.66
#Sta/Elev= 30
    4243  482.44  4265.4  483.63  4287.7  482.11    4296  482.72  4318.4  482.74
  4435.8  481.14  4511.3  478.37  4592.3  477.07  4676.2  474.22  4743.3  471.25
  4765.6  468.84  4779.7  468.08    4802  468.68  4872.5   467.8  4916.7  467.65
  4972.1  464.91  4987.6  459.29  4992.4  458.54  4995.1  458.04  4998.4  458.54
  5007.1   461.4  5016.8  466.19  5022.6  467.59  5030.4  468.37    5112     471
  5176.2  474.95  5234.5  477.71  5286.9  479.03  5321.9  481.32  5496.9  486.45
#Mann= 5 ,-1 , 0
    4243     .05       0  4872.5     .16       0  4987.6     .05       0
  4992.4     .03       0  4998.4     .05       0
Bank Sta=4972.1,5016.8
XS Rating Curve= 0 ,0
Exp/Cntr=0.3,0.1

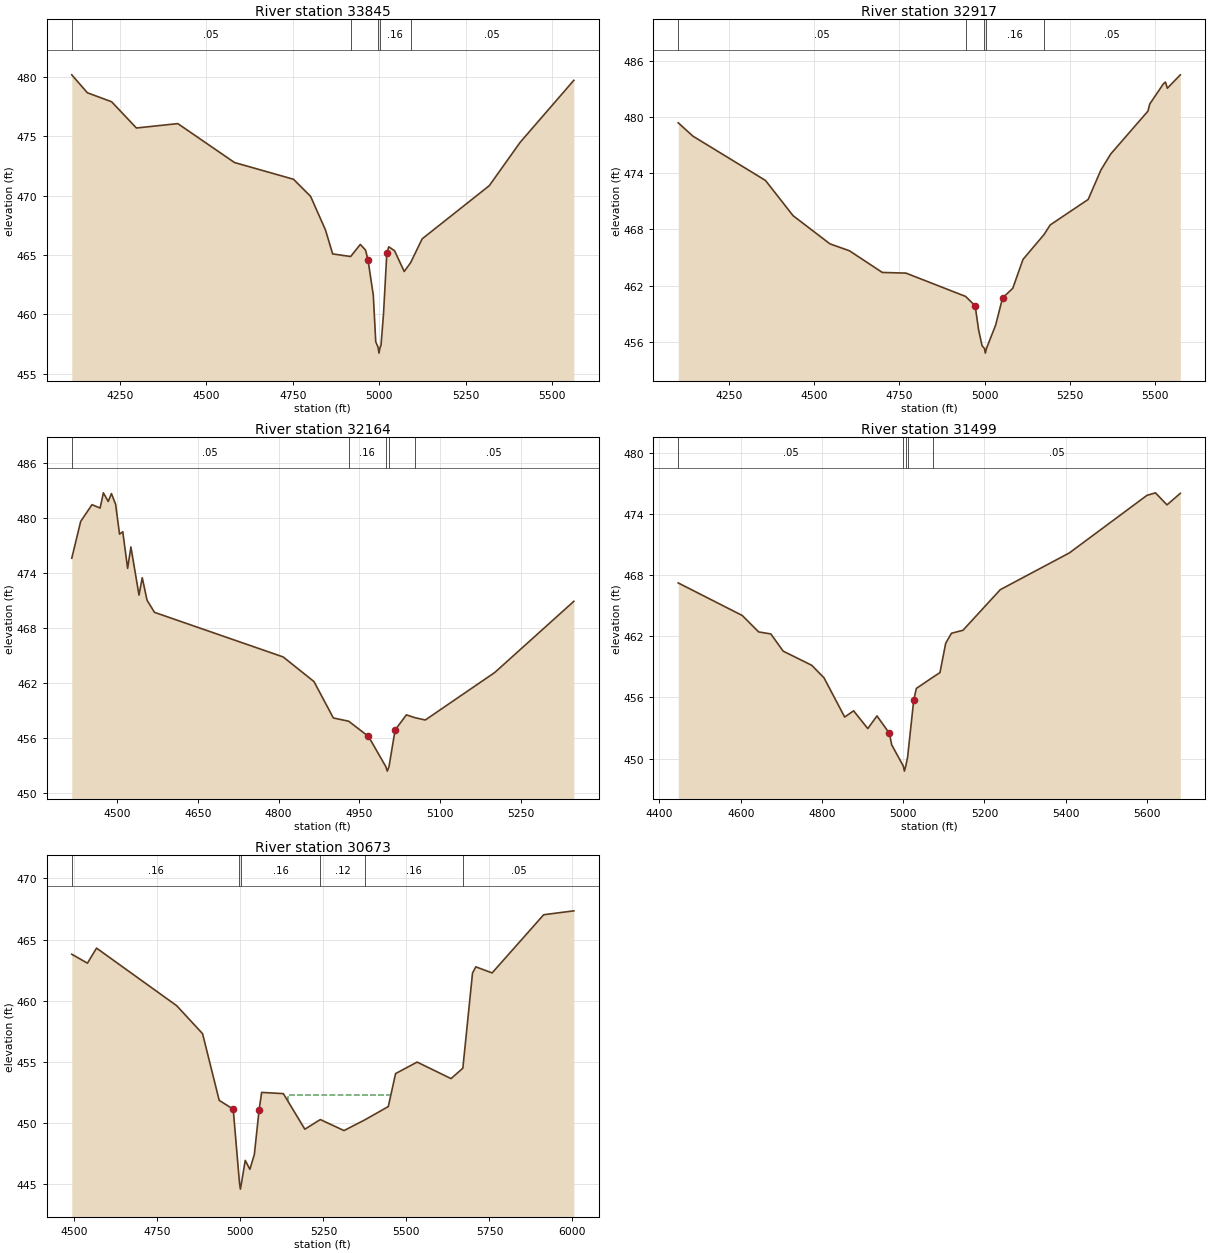
Type RM Length L Ch R = 1 ,33845   ,928,928,928
BEGIN DESCRIPTION:
FROST CREEK 31.0
END DESCRIPTION:
XS GIS Cut Line= 3
      3471639.78     10541176.55      3471139.76     10540576.54
      3470539.82     10540276.57
#Sta/Elev= 30
  4111.1  480.19  4156.1  478.68  4226.4  477.92    4298  475.71  4417.7  476.08
  4581.7   472.8  4752.3  471.39  4801.7  469.95  4844.7  467.12  4865.5   465.1
  4917.5  464.88  4945.4   465.9  4960.6  465.42  4967.8  464.58    4983  461.62
  4990.1   457.7  4996.7  457.24  4999.5  456.74  5002.7  457.24  5005.3  457.38
  5012.5  460.05  5022.1  465.15  5027.7   465.7  5044.4  465.37  5072.4  463.62
  5090.7  464.35  5124.3  466.37  5318.4  470.85  5407.8  474.51  5562.9  479.73
#Mann= 5 ,-1 , 0
  4111.1     .05       0  4917.5     .16       0  4996.7     .07       0
  5002.7     .16       0  5090.7     .05       0
Bank Sta=4967.8,5022.1
XS Rating Curve= 0 ,0
Exp/Cntr=0.3,0.1

Type RM Length L Ch R = 1 ,32917   ,753,753,753
BEGIN DESCRIPTION:
FROST CREEK 29.0
END DESCRIPTION:
XS GIS Cut Line= 4
      3471921.02     10541165.11      3471684.91     10540432.47
      3471702.27     10540119.97      3471539.28     10539766.25
#Sta/Elev= 30
  4101.7  479.37  4144.6  477.95  4357.5  473.22  4438.4  469.46  4546.6  466.45
  4603.9  465.71  4700.1   463.4  4769.5  463.33  4944.4  460.84  4972.4  459.84
  4982.4  457.29  4992.5   455.6  4999.5  455.29  5002.2  454.79  5005.5  455.29
  5032.5  457.79  5052.6  460.67  5082.6  461.71  5112.6  464.79  5174.2  467.44
  5192.4  468.47  5303.7  471.19  5341.2  474.34  5369.8  476.04  5478.9  480.61
  5484.4  481.38  5523.9  483.51  5530.4  483.72  5535.9  483.06  5573.9  484.49
#Mann= 5 ,-1 , 0
  4101.7     .05       0  4944.4     .16       0  4999.5     .07       0
  5005.5     .16       0  5174.2     .05       0
Bank Sta=4972.4,5052.6
XS Rating Curve= 0 ,0
Exp/Cntr=0.3,0.1

Type RM Length L Ch R = 1 ,32164   ,665,665,665
BEGIN DESCRIPTION:
FROST CREEK 27.0
END DESCRIPTION:
XS GIS Cut Line= 3
      3472739.75     10540376.53      3472289.76     10540076.54
      3471989.86     10539826.62
#Sta/Elev= 30
  4416.4  475.62  4432.9  479.62  4453.9  481.45    4469  481.08    4475  482.74
    4484   481.8    4490  482.66  4497.7  481.49    4505  478.24    4511   478.5
    4520  474.51  4526.1  476.84  4541.1   471.6  4547.1  473.49  4556.1  471.03
  4569.8  469.72  4808.5  464.86  4865.6  462.18  4901.6  458.21  4929.9  457.86
  4966.7   456.2  4998.8  452.92  5001.6  452.42  5004.8  452.92  5016.1   456.9
    5037  458.55  5052.4  458.25  5072.1  457.99    5201  463.17  5347.6  470.92
#Mann= 5 ,-1 , 0
  4416.4     .05       0  4929.9     .16       0  4998.8     .07       0
  5004.8     .16       0  5052.4     .05       0
Bank Sta=4966.7,5016.1
XS Rating Curve= 0 ,0
Exp/Cntr=0.3,0.1

Type RM Length L Ch R = 1 ,31499   ,826,826,826
BEGIN DESCRIPTION:
FROST CREEK 25.0
END DESCRIPTION:
XS GIS Cut Line= 4
      3472846.83     10540148.32      3472802.96     10539748.44
       3472698.8     10539550.52      3472255.75     10539131.71
#Sta/Elev= 30
  4446.3  467.22  4603.9  464.03  4644.2  462.42  4674.3  462.22  4704.5  460.54
  4774.9  459.15  4805.1  457.92  4855.9  454.08  4877.9  454.69  4912.8  452.95
  4935.4  454.19  4966.1  452.48  4971.7  451.35  5000.2  449.28  5002.9  448.78
  5006.2  449.28  5010.7  450.13  5025.8  455.71  5032.2  456.88  5072.5  457.97
  5090.4  458.43  5104.5  461.31  5118.7  462.29    5147  462.58  5238.8  466.56
  5408.8  470.16  5599.7   475.8  5620.7  476.05  5649.1  474.87  5681.9     476
#Mann= 5 ,-1 , 0
  4446.3     .05       0  5000.2     .04       0  5006.2     .05       0
  5010.7     .16       0  5072.5     .05       0
Bank Sta=4966.1,5025.8
XS Rating Curve= 0 ,0
Exp/Cntr=0.3,0.1

Type RM Length L Ch R = 1 ,30673   ,355,355,355
BEGIN DESCRIPTION:
FROST CREEK 24.0
END DESCRIPTION:
XS GIS Cut Line= 3
      3473851.55     10539908.13      3473466.16     10539460.25
      3472667.51     10539001.89
#Sta/Elev= 30
  4492.4   463.8  4539.6  463.07    4567   464.3  4808.4  459.59  4886.3   457.3
  4936.3  451.85  4978.5  451.13  4997.4  445.09  5000.2  444.59  5003.4  445.09
  5014.7  446.94  5028.7  446.21  5042.1  447.42  5056.4  451.05  5064.1   452.5
  5129.5   452.4  5194.2  449.49  5240.7  450.28  5312.1  449.38  5374.4  450.25
  5445.4  451.34  5467.4  454.04  5532.2  454.98  5634.3  453.63  5669.9  454.48
    5699  462.26    5709  462.77    5758  462.27  5913.3  467.03  6004.1  467.35
#Mann= 6 ,-1 , 0
  4492.4     .16       0  4997.4     .07       0  5003.4     .16       0
  5240.7     .12       0  5374.4     .16       0  5669.9     .05       0
#XS Ineff= 1 ,-1
 5144.55 5453.41  452.32
Permanent Ineff=
       F
Bank Sta=4978.5,5056.4
XS Rating Curve= 0 ,0
Exp/Cntr=0.3,0.1