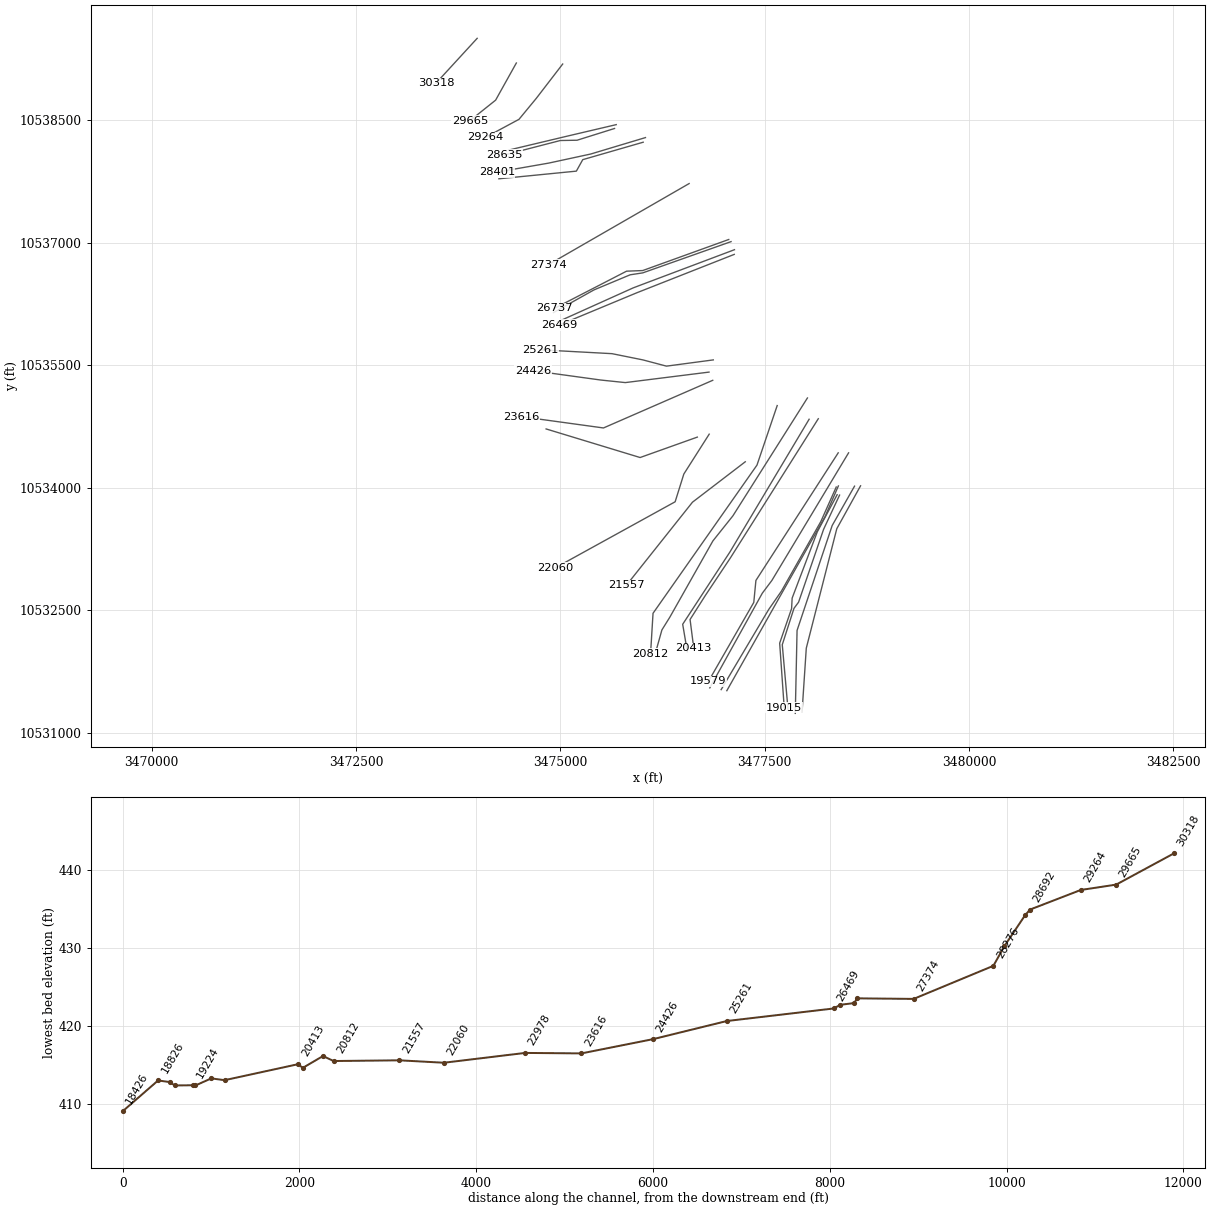
HEC-RAS study FROST CREEK.prj: FROST CREEK Base Level Engineering

--- FROST CREEK.g01 (geometry) --- (continued)

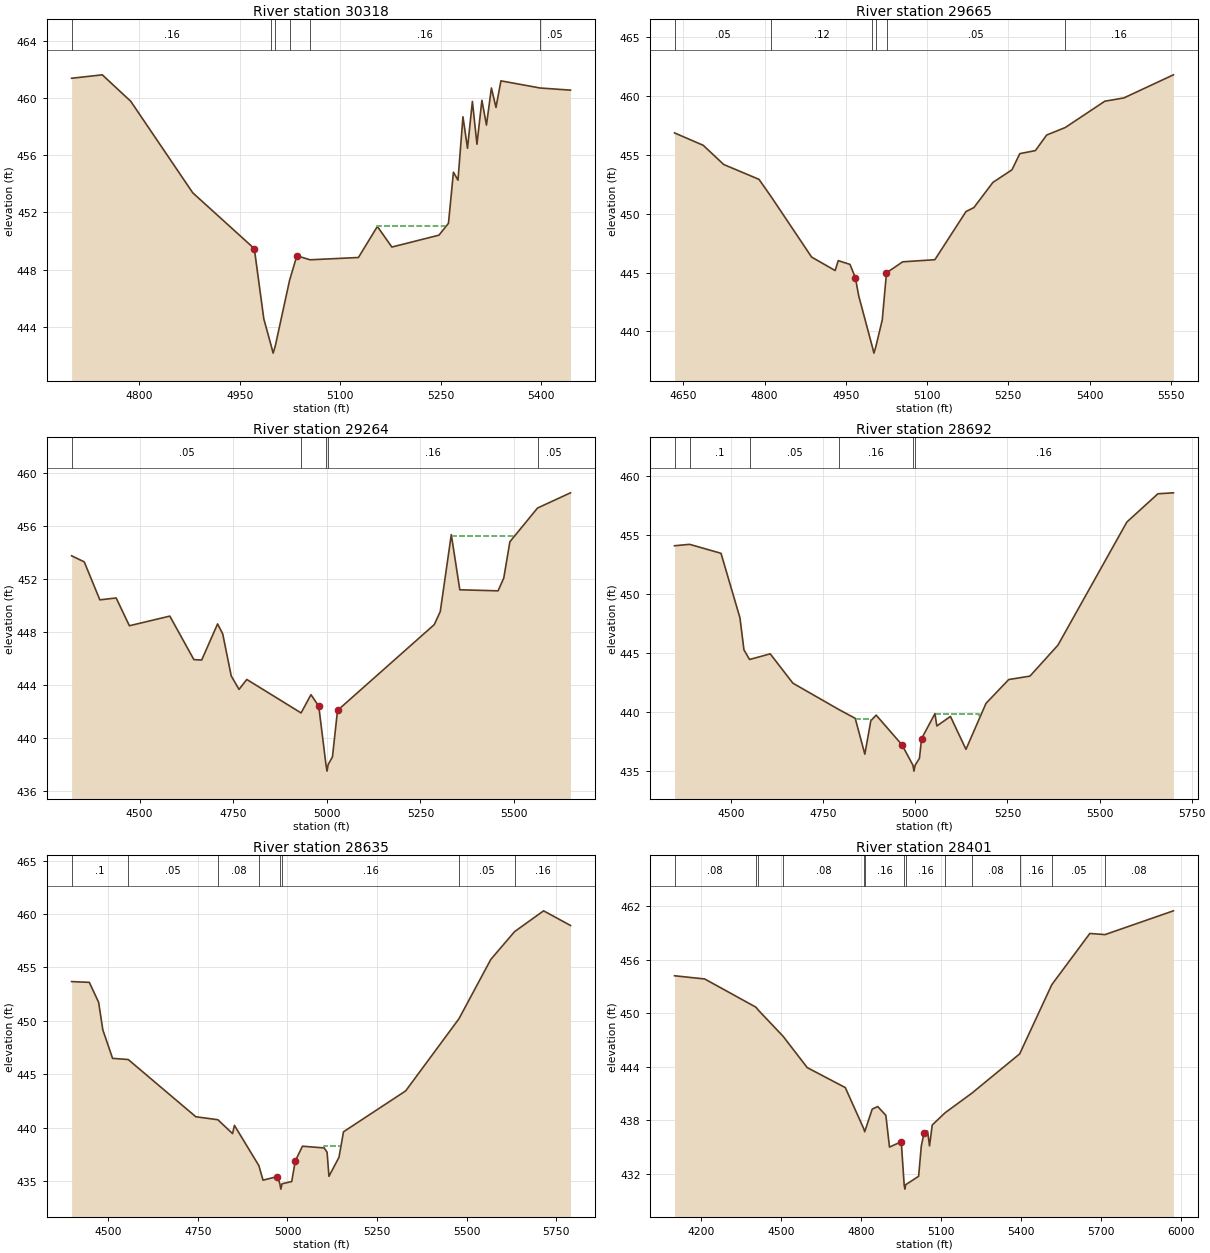
Type RM Length L Ch R = 1 ,30318   ,653,653,653
BEGIN DESCRIPTION:
FROST CREEK 23.0
END DESCRIPTION:
XS GIS Cut Line= 2
      3473983.49     10539505.36      3473480.04     10538956.76
#Sta/Elev= 30
    4699  461.37  4744.8  461.61  4787.3  459.76  4879.8  453.37  4971.7  449.47
  4985.9  444.56    4997  442.67  4999.8  442.17    5003  442.67  5024.4  447.27
  5035.2  448.97    5055  448.69  5127.1  448.85  5155.4  451.02    5177  449.58
  5247.3  450.41  5261.5  451.24  5268.9  454.81  5275.7  454.25  5283.1  458.68
  5289.9  456.48  5297.2  459.75    5304  456.76  5311.4  459.83  5318.2   458.1
  5325.6  460.69  5332.4  459.33  5339.8  461.19  5398.3  460.69  5443.6  460.54
#Mann= 6 ,-1 , 0
    4699     .16       0    4997     .07       0    5003     .16       0
  5024.4     .12       0    5055     .16       0  5398.3     .05       0
#XS Ineff= 1 ,-1
 5154.83 5260.17  451.08
Permanent Ineff=
       F
Bank Sta=4971.7,5035.2
XS Rating Curve= 0 ,0
Exp/Cntr=0.3,0.1

Type RM Length L Ch R = 1 ,29665   ,401,401,401
BEGIN DESCRIPTION:
FROST CREEK 22.0
END DESCRIPTION:
XS GIS Cut Line= 3
      3474462.67     10539203.27      3474209.21     10538748.44
      3473896.93     10538498.61
#Sta/Elev= 30
    4634  456.85  4686.9   455.8  4724.7  454.17  4789.8  452.91  4812.1  451.45
    4887  446.31  4930.4  445.17  4936.1  446.01  4957.8  445.69  4967.8  444.54
  4973.8  443.03  4999.2  438.66  5001.9  438.16  5005.2  438.66  5017.3  440.98
  5025.1  444.97  5025.3  444.98    5055  445.91  5114.4  446.09  5171.9  450.18
  5186.3  450.51  5221.5  452.65  5256.7  453.72  5271.1  455.09  5299.9  455.35
  5320.7  456.67  5355.1  457.31    5428  459.54  5463.2  459.82  5554.6  461.78
#Mann= 6 ,-1 , 0
    4634     .05       0  4812.1     .12       0  4999.2     .07       0
  5005.2     .12       0  5025.3     .05       0  5355.1     .16       0
Bank Sta=4967.8,5025.1
XS Rating Curve= 0 ,0
Exp/Cntr=0.3,0.1

Type RM Length L Ch R = 1 ,29264   ,572,572,572
BEGIN DESCRIPTION:
FROST CREEK 21.1
END DESCRIPTION:
XS GIS Cut Line= 4
      3475029.77     10539190.72      3474706.86     10538770.58
      3474495.05     10538513.64       3474081.9     10538291.44
#Sta/Elev= 30
  4318.6  453.75  4352.4  453.29    4394  450.42  4437.6  450.56  4472.9  448.46
  4580.8  449.19  4645.1   445.9  4665.9  445.87  4708.4   448.6  4722.1  447.84
  4744.8  444.67  4765.6  443.65  4786.4   444.4  4931.3  441.87  4957.7  443.25
  4978.5  442.38  4997.7  437.97  5000.5  437.47  5003.7  437.97  5015.1  438.55
  5028.6  442.06    5287  448.55  5302.9  449.53  5332.4  455.35  5355.1  451.18
  5457.3   451.1  5472.5  452.07  5488.8  454.81  5562.6  457.36  5650.6  458.51
#Mann= 5 ,-1 , 0
  4318.6     .05       0  4931.3     .16       0  4997.7     .07       0
  5003.7     .16       0  5562.6     .05       0
#XS Ineff= 1 ,-1
 5332.73 5499.09  455.24
Permanent Ineff=
       F
Bank Sta=4978.5,5028.6
XS Rating Curve= 0 ,0
Exp/Cntr=0.3,0.1

Type RM Length L Ch R = 1 ,28692   ,57,57,57
BEGIN DESCRIPTION:
FROST CREEK 21.01
END DESCRIPTION:
XS GIS Cut Line= 3
       3475684.9     10538448.69      3475108.47     10538313.27
      3474367.25     10538136.62
#Sta/Elev= 30
  4346.4  454.08  4387.3   454.2  4472.5  453.44  4523.9  447.97  4534.8  445.25
    4550  444.43  4606.1  444.91  4667.7  442.42  4793.3  440.17  4836.8  439.44
  4862.9   436.4  4879.2  439.24  4893.7  439.71  4963.8  437.19  4993.5  435.46
  4996.2  434.96  4999.5  435.46  5011.1  436.05    5017  437.72  5053.2  439.84
  5058.3  438.79  5095.3   439.6  5137.4  436.81  5191.8  440.71  5253.5  442.73
  5311.1  443.02  5387.1  445.65  5574.1  456.09  5658.4  458.49  5700.5  458.57
#Mann= 6 ,-1 , 0
  4346.4     .05       0  4387.3      .1       0    4550     .05       0
  4793.3     .16       0  4993.5     .07       0  4999.5     .16       0
#XS Ineff= 2 ,-1
 4835.45 4879.09  439.42 5052.73 5172.73  439.84
Permanent Ineff=
       F       F
Bank Sta=4963.8,5017
XS Rating Curve= 0 ,0
Exp/Cntr=0.3,0.1

Type RM Length L Ch R = 1 ,28635   ,234,234,234
BEGIN DESCRIPTION:
FROST CREEK 21.0
END DESCRIPTION:
XS GIS Cut Line= 4
      3475664.07     10538401.48       3475205.7     10538257.71
      3475000.84     10538254.24      3474316.96      10538077.2
#Sta/Elev= 30
  4397.9  453.67  4447.3   453.6  4473.3  451.73    4485  449.15  4512.2  446.48
  4555.9  446.37  4744.4  441.01  4805.9  440.73  4846.9  439.43  4852.2   440.2
  4920.3  436.43  4931.9  435.07  4971.9  435.41  4978.9  434.73  4981.6  434.23
  4984.9  434.73  5011.9  434.94  5021.9  436.87  5041.9  438.25  5102.5  438.09
  5110.6  437.69  5115.8  435.43  5143.8  437.21  5156.4   439.6  5329.8  443.43
  5478.5  450.19  5567.4  455.75  5633.6  458.35  5714.6   460.3  5789.6  458.93
#Mann= 8 ,-1 , 0
  4397.9      .1       0  4555.9     .05       0  4805.9     .08       0
  4920.3     .16       0  4978.9     .07       0  4984.9     .16       0
  5478.5     .05       0  5633.6     .16       0
#XS Ineff= 1 ,-1
 5101.82 5151.82  438.24
Permanent Ineff=
       F
Bank Sta=4971.9,5021.9
XS Rating Curve= 0 ,0
Exp/Cntr=0.3,0.1

Type RM Length L Ch R = 1 ,28401   ,125,125,125
BEGIN DESCRIPTION:
FROST CREEK 20.0
END DESCRIPTION:
XS GIS Cut Line= 4
      3476042.51     10538290.09      3475372.41     10538088.72
      3474858.52     10537977.61      3474223.52     10537866.57
#Sta/Elev= 30
  4101.5  454.22  4214.6  453.86  4406.8  450.69    4415  450.38  4508.9  447.41
  4598.9  443.91  4741.5  441.67  4810.8  437.05  4814.4  436.71  4842.4  439.25
  4863.2  439.54  4893.6  438.55  4907.3  434.99  4951.4  435.59  4962.2  430.77
    4965  430.27  4968.2  430.77  5016.4  431.71  5026.6  435.13  5036.8  436.57
  5049.9  436.79  5057.3  435.12  5067.5  437.47  5115.7  438.84    5216  441.04
  5395.2  445.45  5515.7  453.22  5658.3  458.97  5715.1  458.84  5971.6  461.51
#Mann= 13 ,-1 , 0
  4101.5     .08       0  4406.8      .1       0    4415     .05       0
  4508.9     .08       0  4810.8     .05       0  4814.4     .16       0
  4962.2     .07       0  4968.2     .16       0  5115.7     .05       0
    5216     .08       0  5395.2     .16       0  5515.7     .05       0
  5715.1     .08       0
Bank Sta=4951.4,5036.8
XS Rating Curve= 0 ,0
Exp/Cntr=0.3,0.1

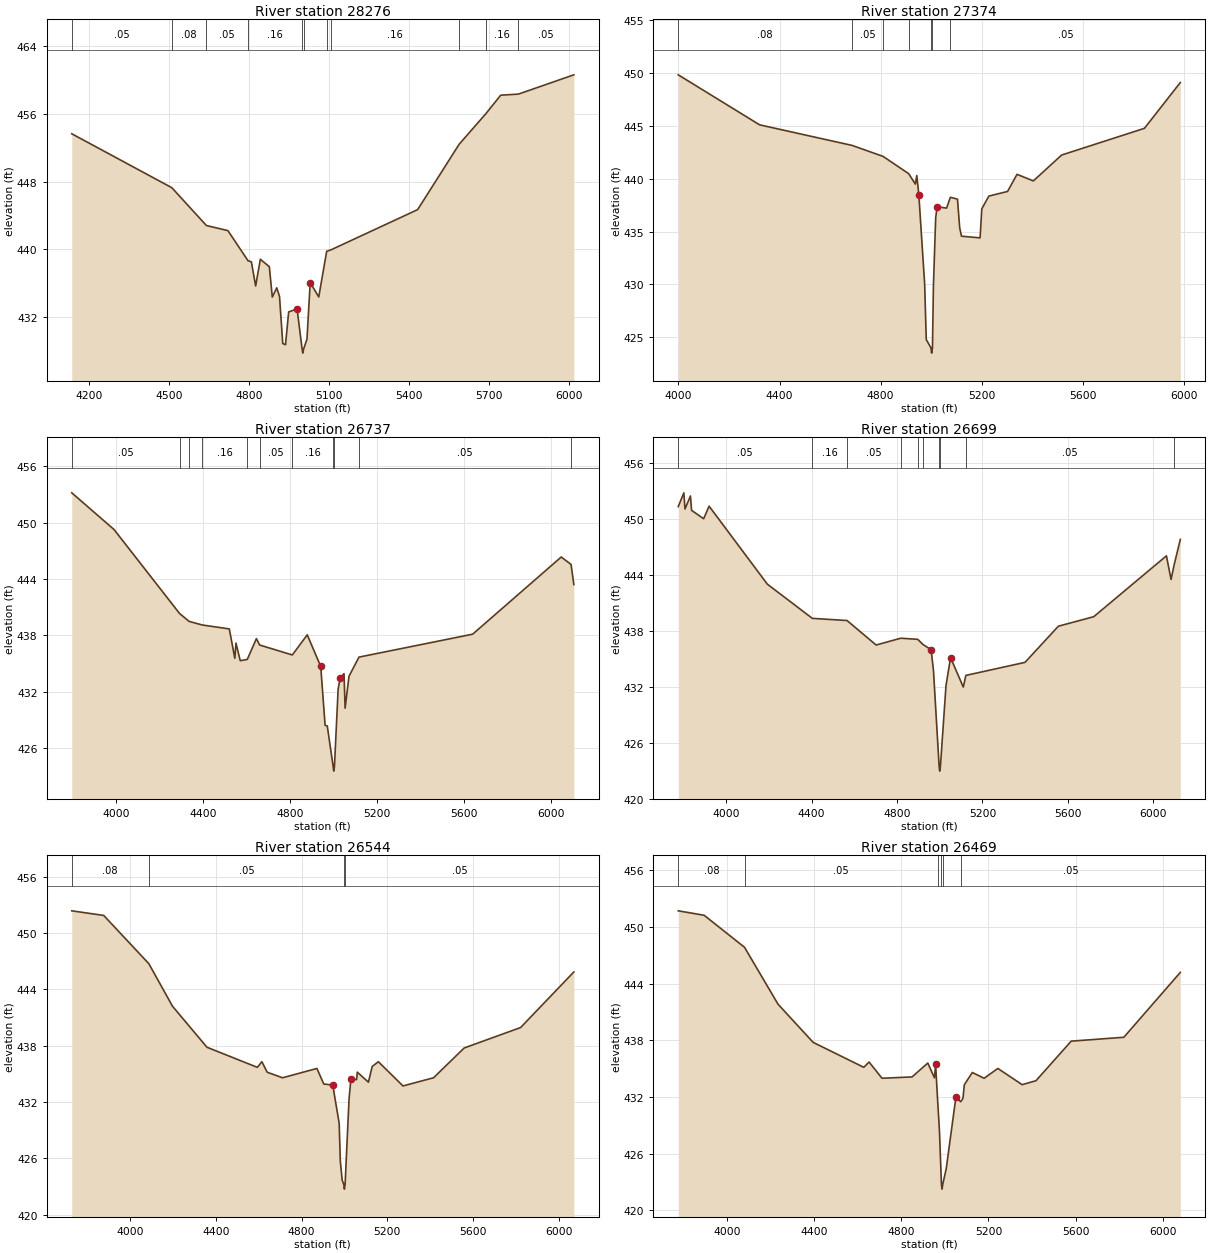
Type RM Length L Ch R = 1 ,28276   ,902,902,902
BEGIN DESCRIPTION:
FROST CREEK 19.0
END DESCRIPTION:
XS GIS Cut Line= 4
      3476014.74     10538233.41      3475275.14     10538019.86
      3475197.02     10537879.24      3474249.12     10537785.49
#Sta/Elev= 30
  4134.8  453.67  4510.2  447.29  4639.8  442.82  4720.4  442.22  4795.9  438.66
  4808.5  438.52  4824.5  435.67  4842.1  438.83  4875.8  437.95    4887  434.36
  4903.6  435.45    4914  434.43  4926.2  428.87  4936.5  428.72  4948.3   432.6
  4979.9  432.96  4998.7  428.23  5001.4  427.73  5004.7  428.23    5017  429.38
  5029.1  436.07  5061.2  434.37  5090.9  439.77  5106.2  439.93  5432.2   444.7
  5587.8  452.43  5686.8     456  5743.7  458.23  5810.1  458.36    6018  460.64
#Mann= 11 ,-1 , 0
  4134.8     .05       0  4510.2     .08       0  4639.8     .05       0
  4795.9     .16       0  4998.7     .07       0  5004.7     .16       0
  5090.9     .05       0  5106.2     .16       0  5587.8     .05       0
  5686.8     .16       0  5810.1     .05       0
Bank Sta=4979.9,5029.1
XS Rating Curve= 0 ,0
Exp/Cntr=0.3,0.1

Type RM Length L Ch R = 1 ,27374   ,637,637,637
BEGIN DESCRIPTION:
FROST CREEK 18.1
END DESCRIPTION:
XS GIS Cut Line= 2
       3476576.8     10537727.12       3474855.8     10536734.77
#Sta/Elev= 30
  3999.2  449.85  4321.3  445.11  4687.5  443.16  4809.8  442.12  4910.7  440.49
  4937.5   439.5  4943.2  440.31  4951.2  438.48  4974.3     430  4980.6  424.77
  4999.1  423.98  5001.9  423.48  5005.1  423.98  5008.9  429.85  5017.9  436.32
  5023.7  437.35    5061  437.22    5076  438.25  5104.1  438.07  5112.8  435.37
  5119.9  434.56  5193.6   434.4  5200.3  437.15  5228.2  438.36  5302.3   438.8
  5339.7  440.42  5404.3   439.8  5516.3  442.25  5843.8  444.78  5985.8  449.12
#Mann= 7 ,-1 , 0
  3999.2     .08       0  4687.5     .05       0  4809.8     .08       0
  4910.7     .16       0  4999.1     .07       0  5005.1     .16       0
    5076     .05       0
Bank Sta=4951.2,5023.7
XS Rating Curve= 0 ,0
Exp/Cntr=0.3,0.1

Type RM Length L Ch R = 1 ,26737   ,38,38,38
BEGIN DESCRIPTION:
FROST CREEK 17.11
END DESCRIPTION:
XS GIS Cut Line= 4
      3477061.12      10537042.2      3476009.08     10536662.01
      3475811.16      10536654.2      3474928.36     10536198.47
#Sta/Elev= 30
  3796.2  453.16  3990.5  449.26  4292.7  440.31  4336.2  439.48  4396.4   439.1
  4521.1  438.68  4546.5  435.55  4551.8  437.17  4571.4   435.3  4603.7  435.43
  4645.8  437.65  4660.5  436.97    4811  435.91  4879.7  438.05  4941.8  434.69
  4961.8  428.43  4971.9  428.35  4998.9  424.05  5001.6  423.55  5004.9  424.05
  5021.9   432.3  5031.9  433.49  5048.9  433.92  5053.9  430.25  5071.9  433.65
  5117.7  435.68  5640.8  438.12  6048.3  446.33  6093.6  445.54  6106.4   443.4
#Mann= 11 ,-1 , 0
  3796.2     .05       0  4292.7     .16       0  4336.2     .05       0
  4396.4     .16       0  4603.7     .07       0  4660.5     .05       0
    4811     .16       0  4998.9     .07       0  5004.9     .16       0
  5117.7     .05       0  6093.6     .16       0
Bank Sta=4941.8,5031.9
XS Rating Curve= 0 ,0
Exp/Cntr=0.3,0.1

Type RM Length L Ch R = 1 ,26699   ,155,155,155
BEGIN DESCRIPTION:
FROST CREEK 17.1
END DESCRIPTION:
XS GIS Cut Line= 5
      3477089.79     10537016.17      3476009.08     10536633.36
      3475855.44     10536609.93      3475412.73     10536425.03
      3474916.48     10536147.03
#Sta/Elev= 30
  3775.6  451.32  3801.9   452.8  3807.2  451.07  3832.8  452.46  3838.1  450.92
  3894.6  450.02  3920.1  451.37  4192.8     443  4403.5  439.33  4565.9   439.1
    4702  436.47  4817.3   437.2  4896.9  437.08  4920.7  436.54  4959.5  435.97
  4970.7  433.69    4997  423.44  4999.7  422.94    5003  423.44  5029.1  432.11
  5050.5  435.12  5110.1  431.96  5122.2  433.21  5399.1  434.61  5555.2  438.49
  5720.9  439.51  6061.1  446.04  6082.8   443.5  6097.5   445.1  6126.1   447.8
#Mann= 10 ,-1 , 0
  3775.6     .05       0  4403.5     .16       0  4565.9     .05       0
  4817.3     .16       0  4896.9     .05       0  4920.7     .16       0
    4997     .07       0    5003     .16       0  5122.2     .05       0
  6097.5     .16       0
Bank Sta=4959.5,5050.5
XS Rating Curve= 0 ,0
Exp/Cntr=0.3,0.1

Type RM Length L Ch R = 1 ,26544   ,75,75,75
BEGIN DESCRIPTION:
FROST CREEK 16.1
END DESCRIPTION:
XS GIS Cut Line= 4
      3477131.49     10536917.22      3476003.01     10536491.87
      3475889.29     10536448.47      3474965.94     10536032.31
#Sta/Elev= 30
  3728.8  452.36  3877.8  451.87  4088.1  446.73  4198.4   442.2  4359.1  437.83
  4593.8  435.69  4615.1  436.29  4639.8  435.17  4711.3  434.58  4871.6  435.57
  4903.7  433.91  4945.3  433.82  4975.3  429.74  4980.7  425.71  4989.3  423.68
    4997  423.22  4999.7  422.72    5003  423.22  5021.4  432.32  5030.2  434.49
  5056.5  434.38  5059.9  435.18  5111.7  434.11  5129.3  435.78    5158  436.29
  5272.8  433.71  5415.4  434.58    5558  437.75  5821.2  439.93  6069.3  445.85
#Mann= 4 ,-1 , 0
  3728.8     .08       0  4088.1     .05       0    4997     .04       0
    5003     .05       0
Bank Sta=4945.3,5030.2
XS Rating Curve= 0 ,0
Exp/Cntr=0.3,0.1

Type RM Length L Ch R = 1 ,26469   ,1208,1208,1208
BEGIN DESCRIPTION:
FROST CREEK 16.11
END DESCRIPTION:
XS GIS Cut Line= 3
      3477128.84     10536859.91      3475933.56     10536388.57
      3474989.81     10535995.99
#Sta/Elev= 30
  3774.5  451.72  3893.5  451.25    4079  447.86  4233.2  441.83  4394.5  437.79
    4627  435.15  4651.4  435.71  4710.9  433.99  4848.9  434.13  4921.2   435.6
  4951.8  434.04  4957.2  435.45  4967.7  431.14  4974.9  428.38  4983.9  422.75
  4986.7  422.25  4989.9  422.75  5005.9  424.41  5050.2  431.96  5072.4  431.51
  5082.6  431.84  5089.2  433.31  5125.9   434.6  5180.1  433.99  5243.1  435.03
  5354.8  433.31  5418.3  433.73  5580.2  437.92    5822  438.33  6081.5   445.2
#Mann= 6 ,-1 , 0
  3774.5     .08       0    4079     .05       0  4967.7     .12       0
  4983.9     .07       0  4989.9     .12       0  5072.4     .05       0
Bank Sta=4957.2,5050.2
XS Rating Curve= 0 ,0
Exp/Cntr=0.3,0.1

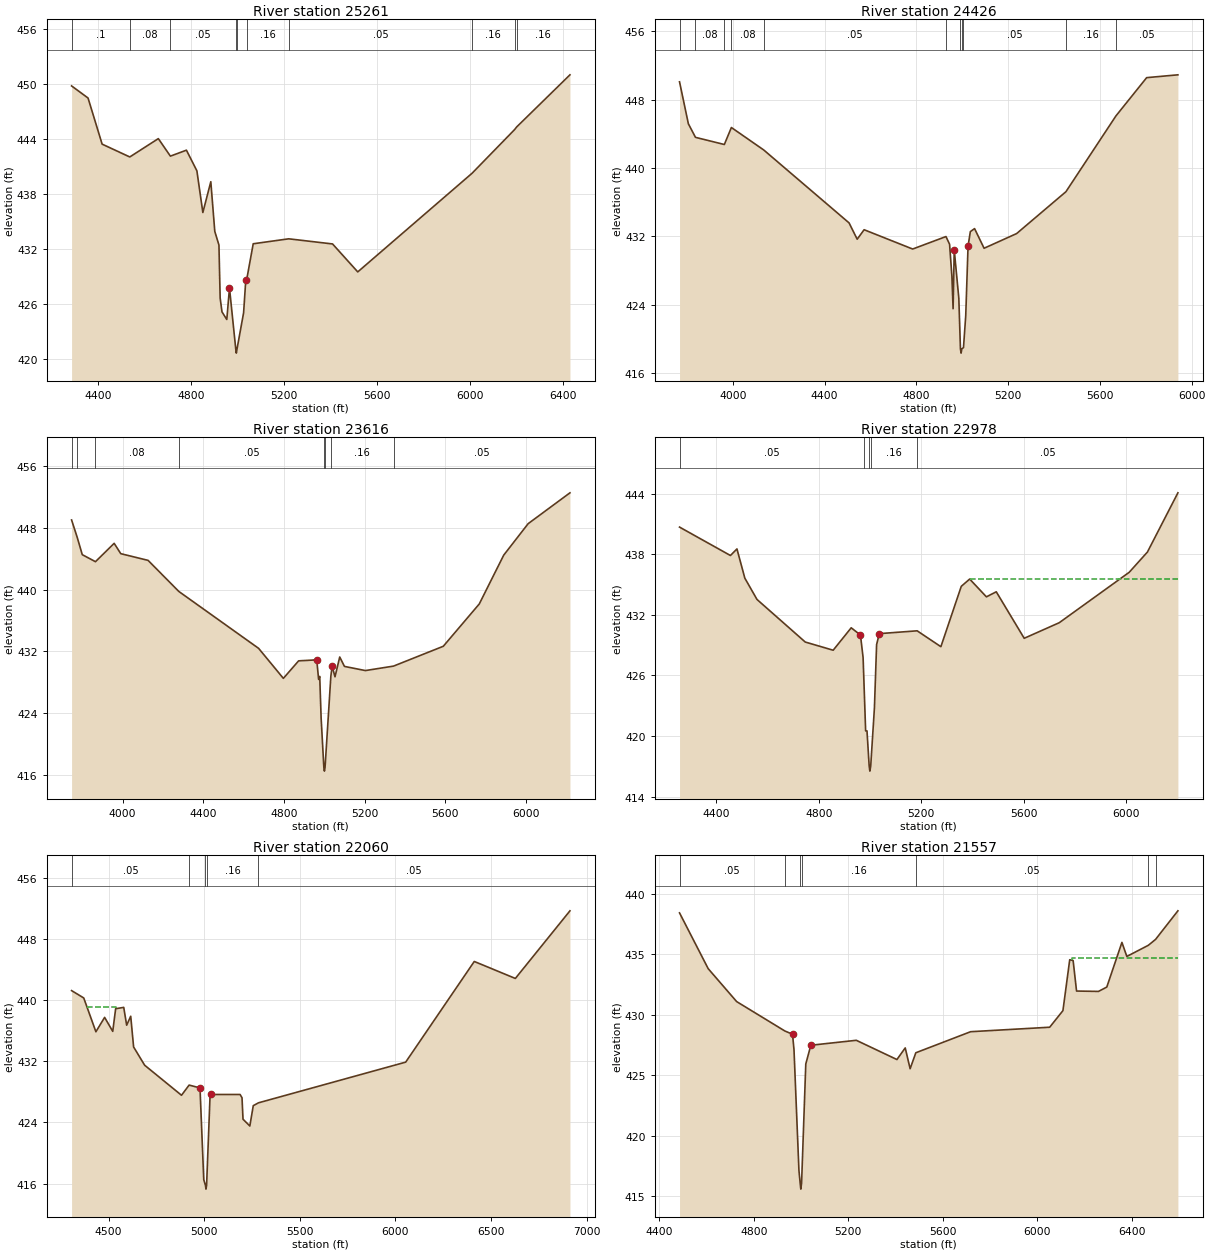
Type RM Length L Ch R = 1 ,25261   ,835,835,835
BEGIN DESCRIPTION:
FROST CREEK 15.2
END DESCRIPTION:
XS GIS Cut Line= 5
      3476872.42     10535567.89      3476299.49      10535491.5
       3476011.3     10535567.88      3475632.83     10535644.27
      3474750.15      10535691.9
#Sta/Elev= 30
  4285.6  449.79  4356.5  448.47  4417.1  443.44  4536.2  442.04  4659.2  444.04
  4711.1  442.13  4780.2  442.78  4825.2  440.53  4850.9  435.98  4885.2  439.34
  4902.3  433.92  4920.2  432.43  4925.4  426.66  4933.3  425.14    4954  424.31
  4965.6  427.74  4992.4  421.14  4995.1  420.64  4998.4  421.14  5026.4  425.04
  5035.7  428.59  5041.2  428.87  5067.8  432.57  5220.7  433.11  5409.5  432.55
    5518   429.5  6010.2  440.26  6193.2  445.02  6202.2  445.31  6431.8     451
#Mann= 10 ,-1 , 0
  4285.6      .1       0  4536.2     .08       0  4711.1     .05       0
  4992.4    .035       0  4998.4     .05       0  5041.2     .16       0
  5220.7     .05       0  6010.2     .16       0  6193.2     .05       0
  6202.2     .16       0
Bank Sta=4965.6,5035.7
XS Rating Curve= 0 ,0
Exp/Cntr=0.3,0.1

Type RM Length L Ch R = 1 ,24426   ,810,810,810
BEGIN DESCRIPTION:
FROST CREEK 15.0
END DESCRIPTION:
XS GIS Cut Line= 4
      3476820.35     10535418.58      3475796.02     10535290.11
      3475497.97     10535321.07      3474665.74     10535435.69
#Sta/Elev= 30
  3768.1  450.08  3806.6  445.17  3837.6  443.58  3963.4  442.74  3994.1  444.73
  4135.1   442.1    4507  433.56  4542.4  431.65  4572.6  432.76  4784.2   430.5
  4929.3  431.96  4945.1  431.06  4955.2  427.31  4960.4  423.51  4965.4  430.39
  4985.4  424.73  4992.4  418.81  4995.2  418.31  4998.4  418.81  5005.7  418.96
  5015.5  422.69  5025.6  430.83  5035.6  432.54    5054  432.89  5095.5  430.59
  5237.3  432.31  5452.1  437.21  5670.2  446.09  5804.1  450.57  5940.2   450.9
#Mann= 11 ,-1 , 0
  3768.1      .1       0  3837.6     .08       0  3963.4      .1       0
  3994.1     .08       0  4135.1     .05       0  4929.3     .16       0
  4992.4     .07       0  4998.4     .16       0  5005.7     .05       0
  5452.1     .16       0  5670.2     .05       0
Bank Sta=4965.4,5025.6
XS Rating Curve= 0 ,0
Exp/Cntr=0.3,0.1

Type RM Length L Ch R = 1 ,23616   ,638,638,638
BEGIN DESCRIPTION:
FROST CREEK 15.1
END DESCRIPTION:
XS GIS Cut Line= 3
      3476865.48     10535317.89      3475528.66     10534734.55
      3474526.97      10534872.5
#Sta/Elev= 30
  3747.6  449.05  3775.6  446.79  3800.6  444.55    3866  443.64  3958.6  446.02
  3991.3  444.68  4126.7  443.81  4279.1  439.78  4674.5   432.4  4797.1  428.51
  4872.7  430.78  4962.4  430.91  4971.9  428.37  4977.3  428.76  4984.2  423.39
  4997.7  416.98  5000.5  416.48  5003.7  416.98  5032.5  428.81  5038.7   430.1
    5053  428.71  5076.4  431.28  5099.8  430.06  5203.5  429.52  5343.1   430.1
  5589.6  432.67    5768  438.16  5889.1  444.49  6010.2  448.57  6217.3  452.57
#Mann= 8 ,-1 , 0
  3747.6     .15       0  3775.6      .1       0    3866     .08       0
  4279.1     .05       0  4997.7    .035       0  5003.7     .05       0
  5032.5     .16       0  5343.1     .05       0
Bank Sta=4962.4,5038.7
XS Rating Curve= 0 ,0
Exp/Cntr=0.3,0.1

Type RM Length L Ch R = 1 ,22978   ,918,918,918
BEGIN DESCRIPTION:
FROST CREEK 14.0
END DESCRIPTION:
XS GIS Cut Line= 3
      3476676.87      10534622.5      3475976.91     10534372.51
      3474827.05     10534722.47
#Sta/Elev= 30
  4256.8  440.68  4455.5  437.87  4480.9  438.52  4511.7  435.63  4559.2  433.52
  4747.5  429.31  4856.5   428.5  4926.9  430.72    4963     430  4973.3  427.77
  4975.7  426.01  4983.2  420.52  4988.5  420.52    4997  417.04  4999.7  416.54
    5003  417.04  5017.5   422.8    5026  429.05  5036.4  430.14  5184.3  430.42
  5276.9  428.85  5356.5  434.82  5389.3  435.54  5454.6  433.78  5493.1  434.28
  5602.1  429.68  5738.8  431.22    6012  436.21    6083  438.21    6202  444.07
#Mann= 5 ,-1 , 0
  4256.8     .05       0  4975.7     .16       0    4997     .07       0
    5003     .16       0  5184.3     .05       0
#XS Ineff= 2 , 0
                         5389.34          435.56
Permanent Ineff=
       F       F
Bank Sta=4963,5036.4
XS Rating Curve= 0 ,0
Exp/Cntr=0.3,0.1

Type RM Length L Ch R = 1 ,22060   ,503,503,503
BEGIN DESCRIPTION:
FROST CREEK 18.0
END DESCRIPTION:
XS GIS Cut Line= 4
      3476822.24     10534658.65      3476511.91     10534170.37
      3476405.59     10533830.56      3474942.08     10533023.28
#Sta/Elev= 30
  4306.7  441.23  4370.3  440.27  4433.8  435.85  4479.5  437.73  4521.9   435.9
  4537.1  438.86  4579.4  439.04  4594.7  436.71  4615.9  437.88  4631.1  433.86
  4688.7  431.48  4881.5  427.55  4921.3  428.88  4978.2  428.51  4997.9  416.51
  5006.7  415.78  5009.4  415.28  5012.7  415.78  5030.3  427.18  5035.6  427.65
  5187.8  427.65  5197.9  427.23  5203.1  424.42  5238.8  423.53  5256.7  426.19
  5283.7  426.56  6053.7  431.88  6412.4  445.04  6627.2  442.82  6912.7  451.66
#Mann= 5 ,-1 , 0
  4306.7     .05       0  4921.3     .16       0  5006.7     .07       0
  5012.7     .16       0  5283.7     .05       0
#XS Ineff= 1 ,-1
 4385.23 4538.64  439.13
Permanent Ineff=
       F
Bank Sta=4978.2,5035.6
XS Rating Curve= 0 ,0
Exp/Cntr=0.3,0.1

Type RM Length L Ch R = 1 ,21557   ,745,745,745
BEGIN DESCRIPTION:
FROST CREEK 13.0
END DESCRIPTION:
XS GIS Cut Line= 3
      3477263.56     10534320.41       3476617.7     10533825.59
      3475810.42     10532809.97
#Sta/Elev= 30
  4485.2  438.42  4606.6  433.81  4727.1  431.09  4931.3  428.66  4963.8  428.39
  4970.1   427.1    4991  417.13  4996.2  416.09  4998.9  415.59  5002.2  416.09
    5020  425.93  5041.3  427.48    5234  427.89    5406   426.3  5441.2  427.26
    5462  425.54  5486.1  426.86  5718.3   428.6  6053.1  428.97  6109.2  430.34
    6138  434.55  6152.4  434.48  6166.9  431.96  6259.8  431.93    6295  432.29
  6359.1  435.98  6379.9  434.82  6470.9  435.74  6501.7  436.23  6596.2  438.59
#Mann= 7 ,-1 , 0
  4485.2     .05       0  4931.3     .16       0  4996.2     .07       0
  5002.2     .16       0  5486.1     .05       0  6470.9     .16       0
  6501.7     .05       0
#XS Ineff= 2 , 0
                         6146.02          434.68
Permanent Ineff=
       F       F
Bank Sta=4963.8,5041.3
XS Rating Curve= 0 ,0
Exp/Cntr=0.3,0.1

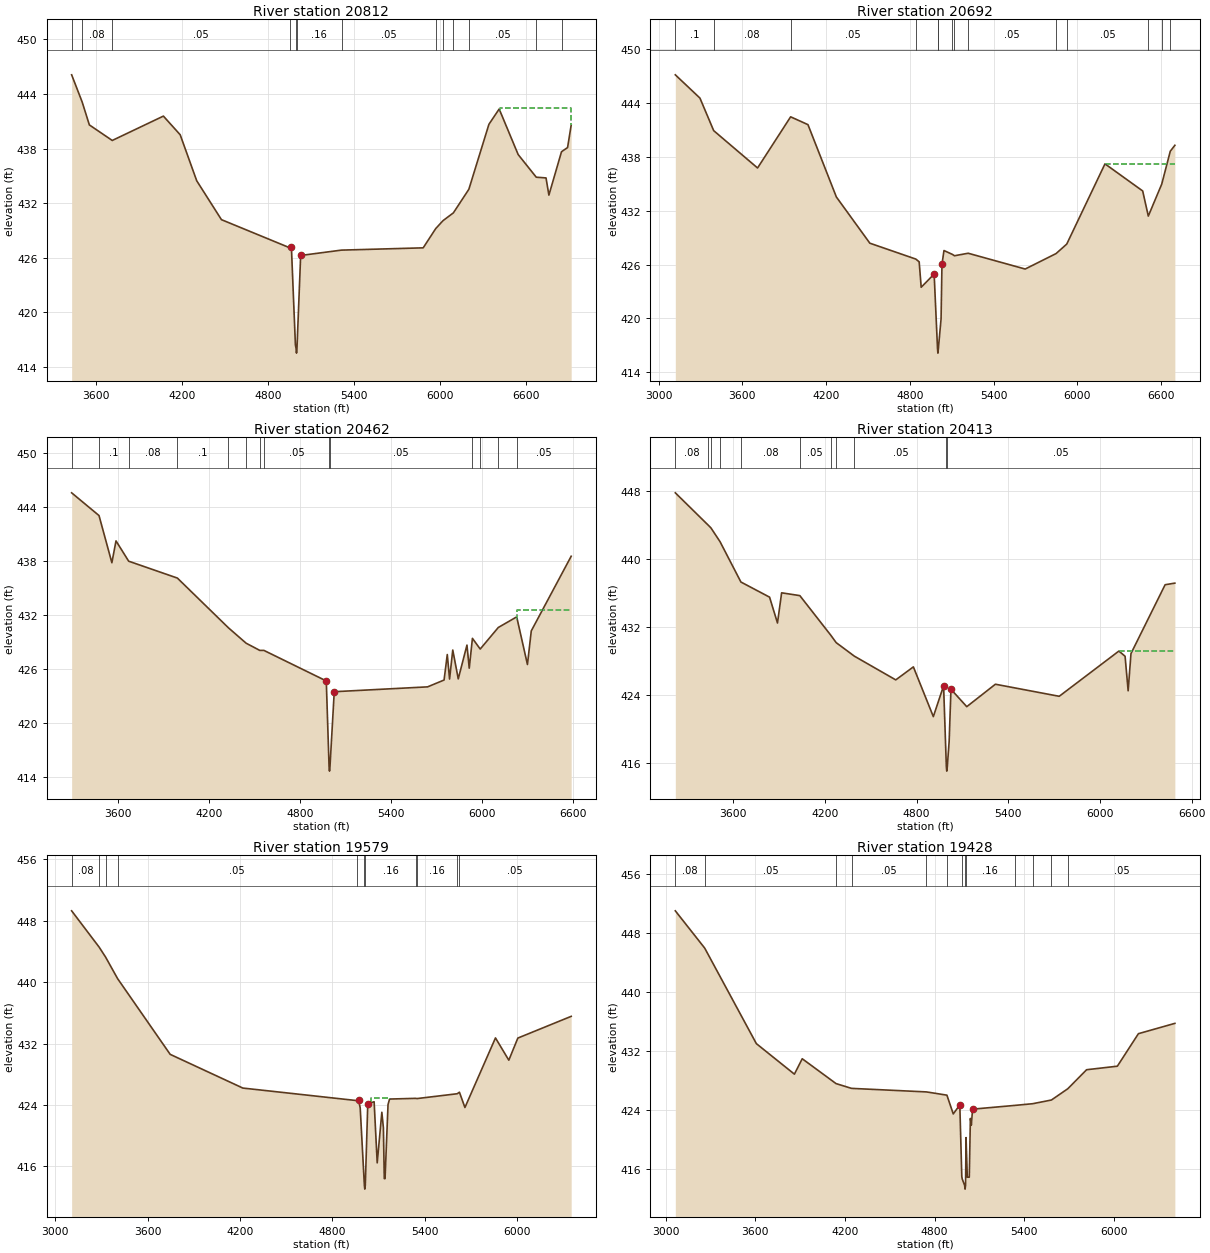
Type RM Length L Ch R = 1 ,20812   ,120,120,120
BEGIN DESCRIPTION:
FROST CREEK 17.0
END DESCRIPTION:
XS GIS Cut Line= 4
      3477654.17     10535008.78      3477406.77     10534279.59
      3476135.07     10532465.35       3476104.7     10531966.44
#Sta/Elev= 30
  3430.3  446.11  3503.5  443.13    3554   440.6  3713.6  438.89  4070.5  441.57
  4187.6  439.52  4302.9  434.46  4475.5  430.18  4956.3  427.06  4963.7  427.13
  4991.6   416.4  4996.4     416  4999.2   415.5  5002.4     416  5028.2  426.24
  5313.3  426.83  5883.1  427.08  5970.7   429.2  6021.5  430.07  6093.9  430.93
  6201.7  433.52  6341.8  440.67  6413.3  442.35  6545.8  437.34    6672  434.85
  6740.2  434.77  6760.2  432.88  6848.2  437.65  6890.5  438.11  6915.7  440.58
#Mann= 13 ,-1 , 0
  3430.3      .1       0  3503.5     .08       0  3713.6     .05       0
  4956.3     .16       0  4996.4     .07       0  5002.4     .16       0
  5313.3     .05       0  5970.7     .16       0  6021.5     .05       0
  6093.9     .16       0  6201.7     .05       0    6672      .1       0
  6848.2     .05       0
#XS Ineff= 2 , 0
                         6418.18          442.42
Permanent Ineff=
       F       F
Bank Sta=4963.7,5028.2
XS Rating Curve= 0 ,0
Exp/Cntr=0.3,0.1

Type RM Length L Ch R = 1 ,20692   ,230,230,230
BEGIN DESCRIPTION:
FROST CREEK 16.0
END DESCRIPTION:
XS GIS Cut Line= 6
      3478023.97     10535101.66       3477112.5     10533658.93
       3476867.7     10533351.64      3476341.66     10532419.34
      3476243.57     10532261.36      3476183.13     10532045.49
#Sta/Elev= 30
  3119.4  447.15  3295.8  444.56  3394.4  440.93  3708.8  436.77  3945.8  442.47
    4070   441.6  4273.5  433.54  4513.5  428.39    4843  426.62    4867  426.31
  4881.4  423.48  4974.3  424.95  4998.5  416.64  5001.2  416.14  5004.5  416.64
  5023.9  419.95  5030.3  426.02  5044.7  427.57  5105.4  427.14  5120.1  426.99
    5218  427.27  5626.7  425.51  5847.8  427.23  5924.6  428.29  6198.7  437.23
  6468.8  434.21  6509.1  431.41  6605.5  434.98  6666.5  438.63  6699.4   439.3
#Mann= 14 ,-1 , 0
  3119.4      .1       0  3394.4     .08       0  3945.8     .05       0
    4843     .16       0  4998.5     .07       0  5004.5     .16       0
  5105.4     .05       0  5120.1     .16       0    5218     .05       0
  5847.8     .16       0  5924.6     .05       0  6509.1      .1       0
  6605.5     .05       0  6666.5      .1       0
#XS Ineff= 2 , 0
                         6197.73          437.25
Permanent Ineff=
       F       F
Bank Sta=4974.3,5030.3
XS Rating Curve= 0 ,0
Exp/Cntr=0.3,0.1

Type RM Length L Ch R = 1 ,20462   ,49,49,49
BEGIN DESCRIPTION:
FROST CREEK 12.01
END DESCRIPTION:
XS GIS Cut Line= 4
      3478044.78     10534841.21      3477076.04     10533216.22
      3476497.91      10532330.8       3476555.2      10531992.3
#Sta/Elev= 30
  3294.2  445.59  3474.6  443.06  3559.4  437.81  3586.6  440.24  3670.1  437.98
  3991.2   436.1  4327.3  430.57  4444.3  428.85  4534.2  428.05  4561.3  428.05
  4972.6  424.65    4991  415.11  4993.7  414.61    4997  415.11  5025.1  423.45
  5640.4  423.99    5749  424.75  5770.1  427.59  5785.2  424.86  5806.3  428.09
  5842.5  424.88  5899.8  428.64  5914.9  426.07  5935.9  429.39  5987.2   428.2
  6106.4   430.6  6227.7  431.78  6298.5  426.48  6323.8  430.22  6586.8  438.53
#Mann= 14 ,-1 , 0
  3294.2     .08       0  3474.6      .1       0  3670.1     .08       0
  3991.2      .1       0  4327.3     .08       0  4444.3     .05       0
  4534.2     .08       0  4561.3     .05       0    4991     .04       0
    4997     .05       0  5935.9     .08       0  5987.2     .05       0
  6106.4     .08       0  6227.7     .05       0
#XS Ineff= 2 , 0
                         6231.82          432.53
Permanent Ineff=
       F       F
Bank Sta=4972.6,5025.1
XS Rating Curve= 0 ,0
Exp/Cntr=0.3,0.1

Type RM Length L Ch R = 1 ,20413   ,834,834,834
BEGIN DESCRIPTION:
FROST CREEK 12.0
END DESCRIPTION:
XS GIS Cut Line= 5
      3478156.96     10534847.55      3477078.82     10533139.19
      3476775.69     10532684.33      3476588.19     10532389.19
      3476633.33     10532038.38
#Sta/Elev= 30
    3220  447.83  3433.5  444.06  3452.9  443.71  3512.6  442.09  3649.4  437.34
    3837  435.56  3888.8  432.52  3915.9  436.07  4035.1  435.74    4237   431.1
  4273.1  430.21  4392.1  428.62  4663.1  425.83  4778.4  427.36    4909  421.51
  4976.1  425.13  4994.3   415.6    4997   415.1  5000.3   415.6  5012.6  418.61
  5024.4  424.73  5127.9  422.68  5315.3  425.32    5733   423.9  6123.7  429.22
  6164.2  428.61  6184.3  424.55  6202.9  428.93  6426.3  437.02  6490.1  437.21
#Mann= 11 ,-1 , 0
    3220     .08       0  3433.5     .05       0  3452.9     .08       0
  3512.6      .1       0  3649.4     .08       0  4035.1     .05       0
    4237      .1       0  4273.1     .08       0  4392.1     .05       0
  4994.3     .04       0  5000.3     .05       0
#XS Ineff= 2 , 0
                         6124.15          429.24
Permanent Ineff=
       F       F
Bank Sta=4976.1,5024.4
XS Rating Curve= 0 ,0
Exp/Cntr=0.3,0.1

Type RM Length L Ch R = 1 ,19579   ,151,151,151
BEGIN DESCRIPTION:
FROST CREEK 11.11
END DESCRIPTION:
XS GIS Cut Line= 4
      3478400.71     10534429.79      3477393.75     10532867.26
       3477367.7     10532598.16      3476812.17     10531630.31
#Sta/Elev= 30
    3106  449.28  3284.8  444.55  3326.7  443.25  3404.6  440.45  3746.2  430.59
  4218.2   426.2  4958.3  424.57  4970.5  424.59  4980.6  423.62  5007.7  413.54
  5010.5  413.04  5013.7  413.54  5029.8  424.14    5071  424.42  5091.1  416.46
  5121.2  423.05  5131.3  421.02    5137  414.41    5142   414.4  5161.4  424.06
  5171.5  424.77  5340.1  424.86  5349.3  424.83  5610.5  425.46  5625.2  425.66
    5661  423.67  5859.4  432.73  5946.1  429.83  6004.7  432.71  6351.2  435.54
#Mann= 11 ,-1 , 0
    3106     .08       0  3284.8     .05       0  3326.7     .08       0
  3404.6     .05       0  4958.3     .16       0  5007.7     .07       0
  5013.7     .16       0  5340.1     .12       0  5349.3     .16       0
  5610.5     .12       0  5625.2     .05       0
#XS Ineff= 1 ,-1
  5048.3 5171.59  424.87
Permanent Ineff=
       F
Bank Sta=4970.5,5029.8
XS Rating Curve= 0 ,0
Exp/Cntr=0.3,0.1

Type RM Length L Ch R = 1 ,19428   ,179,179,179
BEGIN DESCRIPTION:
FROST CREEK 11.1
END DESCRIPTION:
XS GIS Cut Line= 4
      3478527.43     10534429.76      3477589.06     10532867.26
      3477471.87     10532711.01      3476829.51     10531552.17
#Sta/Elev= 30
  3064.7  451.03  3261.4  445.97    3607  433.01  3861.6  428.87    3914  430.96
  4140.1  427.59  4243.9  426.94  4745.2  426.46  4882.1  426.02  4924.7  423.47
  4968.5   424.7  4981.8  414.97  4984.9  414.64  5000.9  413.77  5003.7  413.27
  5006.9  413.77  5010.2  420.26  5018.5  414.89  5031.8  414.89  5039.3  422.86
  5045.6  421.95  5053.9  424.12  5336.9  424.63  5456.2  424.86  5581.5  425.36
  5691.2  426.89  5816.9  429.47  6022.9  429.95  6163.7  434.36  6407.6  435.76
#Mann= 13 ,-1 , 0
  3064.7     .08       0  3261.4     .05       0  4140.1     .16       0
  4243.9     .05       0  4745.2     .12       0  4882.1     .05       0
  4984.9     .16       0  5000.9     .07       0  5006.9     .16       0
  5336.9     .12       0  5456.2     .16       0  5581.5     .12       0
  5691.2     .05       0
Bank Sta=4968.5,5053.9
XS Rating Curve= 0 ,0
Exp/Cntr=0.3,0.1

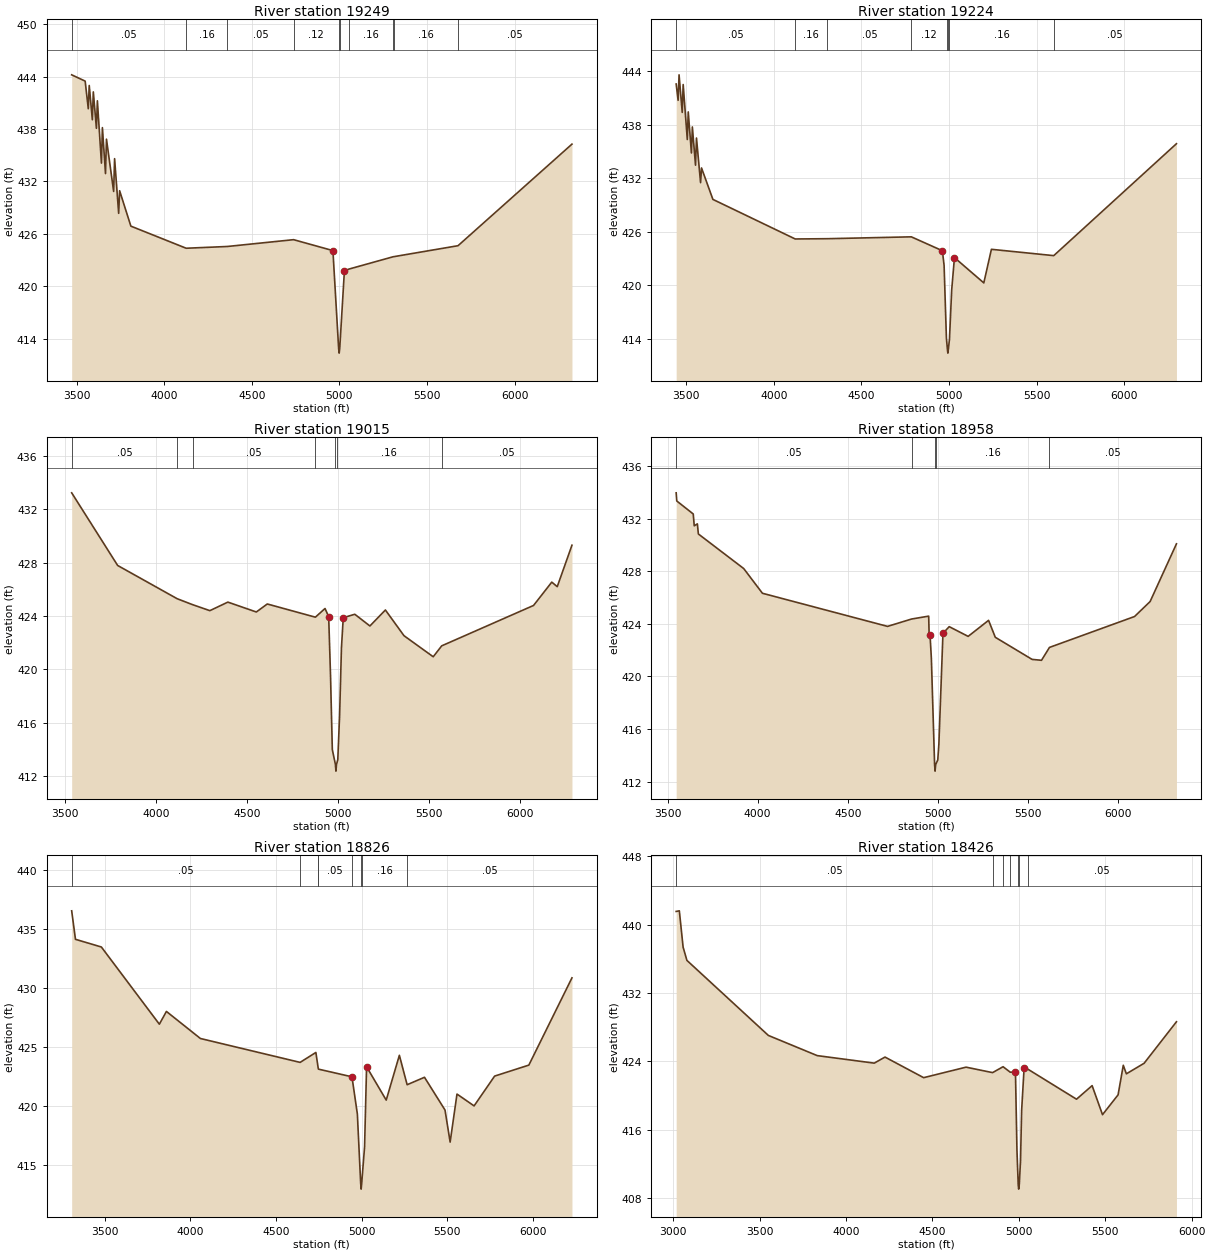
Type RM Length L Ch R = 1 ,19249   ,25,25,25
BEGIN DESCRIPTION:
FROST CREEK 11.12
END DESCRIPTION:
XS GIS Cut Line= 5
      3478376.53     10534011.36      3478187.73     10533588.18
      3477706.25     10532737.05        3477550.     10532511.36
      3476968.41     10531530.48
#Sta/Elev= 30
  3471.4   444.2  3548.4  443.48  3566.2  440.32  3571.6  442.98  3589.4  439.06
  3594.9  442.25  3612.6  438.08  3618.1  441.23  3641.3   434.1  3646.8  438.16
  3664.5   432.9    3670  436.84    3711  430.86  3716.4  434.61  3739.7  428.35
  3745.1  430.94  3809.3  426.89    4125  424.36  4359.9  424.56  4738.3  425.34
  4962.8  424.09  4995.6  412.86  4998.4  412.36  5001.6  412.86  5028.4  421.79
  5055.1  421.98  5305.8  423.38  5311.5   423.4  5677.1  424.65  6327.5  436.27
#Mann= 10 ,-1 , 0
  3471.4     .05       0    4125     .16       0  4359.9     .05       0
  4738.3     .12       0  4995.6     .07       0  5001.6     .12       0
  5055.1     .16       0  5305.8     .12       0  5311.5     .16       0
  5677.1     .05       0
Bank Sta=4962.8,5028.4
XS Rating Curve= 0 ,0
Exp/Cntr=0.3,0.1

Type RM Length L Ch R = 1 ,19224   ,209,209,209
BEGIN DESCRIPTION:
FROST CREEK 11.13
END DESCRIPTION:
XS GIS Cut Line= 4
      3478402.57     10534024.38      3478239.81     10533648.94
      3477597.74     10532511.36      3477037.82     10531517.39
#Sta/Elev= 30
    3442  442.59  3453.1  440.76  3458.5  443.62  3476.6   439.4    3482  442.53
  3505.5  436.36  3510.9  439.46    3529  434.85  3534.4  437.77  3552.4  433.48
  3557.9  436.53  3581.3  431.52  3586.8  433.17  3651.7  429.64  4121.5   425.2
  4305.2  425.23  4784.6  425.44  4961.9  423.88  4971.7  422.22  4984.9  414.07
  4990.3  412.89  4993.1  412.39  4996.3  412.89  5002.3  413.94    5015  419.47
  5030.8  423.11  5198.4  420.27  5241.8  424.04  5597.7  423.33  6298.3  435.89
#Mann= 8 ,-1 , 0
    3442     .05       0  4121.5     .16       0  4305.2     .05       0
  4784.6     .12       0  4990.3     .07       0  4996.3     .12       0
  5002.3     .16       0  5597.7     .05       0
Bank Sta=4961.9,5030.8
XS Rating Curve= 0 ,0
Exp/Cntr=0.3,0.1

Type RM Length L Ch R = 1 ,19015   ,57,57,57
BEGIN DESCRIPTION:
FROST CREEK 9.12
END DESCRIPTION:
XS GIS Cut Line= 6
      3478387.55     10533916.92      3478144.47     10533462.02
      3477837.18     10532651.26      3477830.23     10532522.79
       3477684.4     10532099.18      3477739.95     10531311.02
#Sta/Elev= 30
  3537.4  433.24  3790.1  427.79  4116.5   425.3  4201.6  424.85  4296.9   424.4
  4395.8  425.04  4552.2   424.3  4612.5   424.9  4876.8  423.91  4929.8  424.56
  4949.9  423.95  4959.9  419.61  4969.9  413.98  4986.9  412.86  4989.7  412.36
  4992.9  412.86  4999.9  413.22    5010  416.54    5020  421.59    5030  423.87
  5093.4  424.13  5176.5  423.25  5261.6  424.45  5363.9  422.52  5524.5  420.94
  5571.2  421.76  6075.9  424.79  6176.1  426.54  6206.2   426.2    6287  429.31
#Mann= 7 ,-1 , 0
  3537.4     .05       0  4116.5     .16       0  4201.6     .05       0
  4876.8     .16       0  4986.9     .07       0  4992.9     .16       0
  5571.2     .05       0
Bank Sta=4949.9,5030
XS Rating Curve= 0 ,0
Exp/Cntr=0.3,0.1

Type RM Length L Ch R = 1 ,18958   ,132,132,132
BEGIN DESCRIPTION:
FROST CREEK 9.11
END DESCRIPTION:
XS GIS Cut Line= 6
       3478417.2     10533912.35      3478221.87     10533493.49
      3477915.88     10532601.56      3477859.46     10532525.61
      3477716.23     10532080.73       3477787.8     10531276.11
#Sta/Elev= 30
  3547.9  433.97  3551.2  433.35  3642.6  432.36  3648.1  431.46  3665.5  431.61
    3671  430.84  3922.5  428.21  4026.3  426.33  4720.4  423.81  4853.6  424.37
  4948.5  424.59  4951.1  423.14  4956.1  423.14  4963.4  421.37  4981.3   413.3
    4984   412.8  4987.3   413.3  4998.9  413.65  5005.1  414.87  5027.7  423.28
  5062.3  423.79  5167.4  423.05  5280.7  424.27    5318  422.98    5522   421.3
  5574.3  421.23  5618.4  422.21  6090.3  424.56  6176.7   425.7  6322.8  430.09
#Mann= 5 ,-1 , 0
  3547.9     .05       0  4853.6     .16       0  4981.3     .07       0
  4987.3     .16       0  5618.4     .05       0
Bank Sta=4956.1,5027.7
XS Rating Curve= 0 ,0
Exp/Cntr=0.3,0.1

Type RM Length L Ch R = 1 ,18826   ,400,400,400
BEGIN DESCRIPTION:
FROST CREEK 10.0
END DESCRIPTION:
XS GIS Cut Line= 4
      3478600.37     10534021.82      3478326.91       10533540.
      3477897.22     10532255.28      3477875.52     10531239.69
#Sta/Elev= 30
  3305.6  436.54  3327.8  434.13  3479.2  433.48  3818.1  426.95  3859.4  428.03
  4058.2  425.74    4641  423.72  4733.1  424.56  4745.2  423.38  4745.9  423.31
    4748  423.15    4944   422.5  4944.4  422.47  4975.6  419.36    4995   413.5
  4997.7     413    5001   413.5  5017.8  416.58  5029.5  423.35  5144.3  420.53
  5221.2  424.32  5266.5  421.83    5368  422.46    5488  419.69    5518  416.98
    5558  421.04    5658  420.04    5778  422.56  5978.1  423.49  6230.1  430.87
#Mann= 9 ,-1 , 0
  3305.6     .05       0    4641     .16       0  4745.2     .05       0
  4745.9     .16       0    4748     .05       0  4944.4     .16       0
    4995     .07       0    5001     .16       0  5266.5     .05       0
Bank Sta=4944,5029.5
XS Rating Curve= 0 ,0
Exp/Cntr=0.3,0.1

Type RM Length L Ch R = 1 ,18426   ,713,713,713
BEGIN DESCRIPTION:
FROST CREEK 9.1
END DESCRIPTION:
XS GIS Cut Line= 4
      3478674.11     10534026.08      3478383.33     10533500.94
      3478010.07     10532038.27      3477958.11     10531254.61
#Sta/Elev= 30
  3016.9  441.54  3035.2  441.61    3057  437.36  3079.1  435.81  3550.5  427.03
  3833.2  424.67  4163.2  423.79  4225.4   424.5  4449.2  422.09  4694.4  423.32
  4847.9  422.68  4908.7  423.37  4950.2  422.73  4980.4  422.76  4989.1  413.56
  4996.4  409.55  4999.1  409.05  5002.4  409.55  5009.7  412.36  5016.1  418.25
  5030.4   423.2  5052.5  423.08  5333.8  419.57    5424  421.16  5484.1  417.76
  5574.3  420.08  5604.4  423.54  5622.2  422.54  5724.7  423.77  5912.1  428.63
#Mann= 7 ,-1 , 0
  3016.9     .05       0  4847.9     .16       0  4908.7     .05       0
  4950.2     .16       0  4996.4     .07       0  5002.4     .16       0
  5052.5     .05       0
Bank Sta=4980.4,5030.4
XS Rating Curve= 0 ,0
Exp/Cntr=0.3,0.1