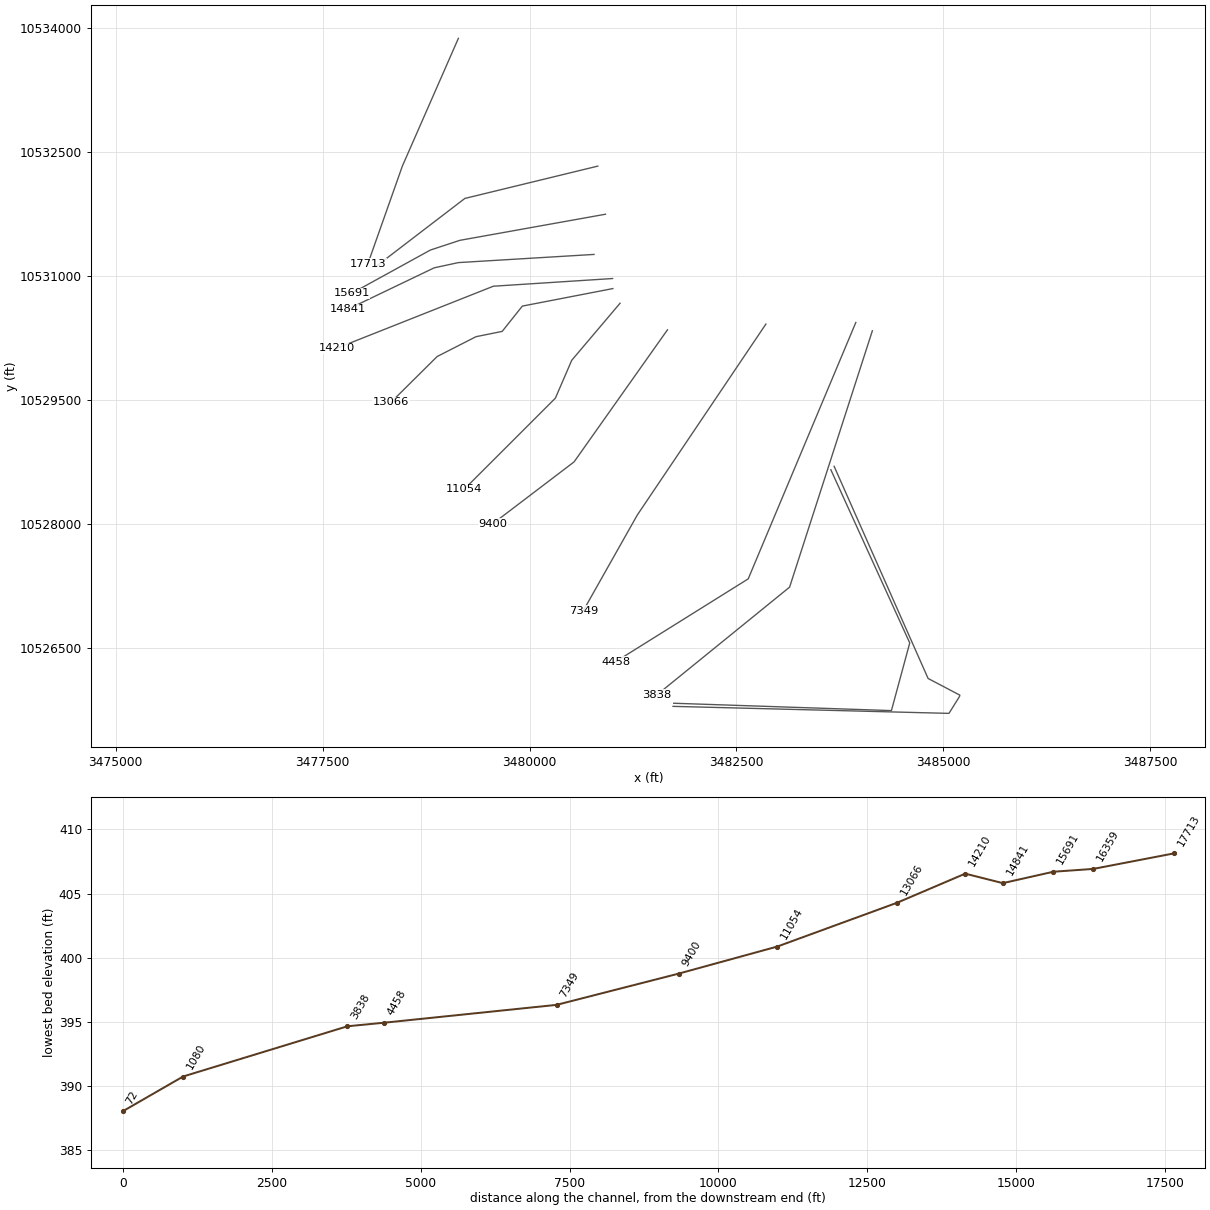
HEC-RAS study FROST CREEK.prj: FROST CREEK Base Level Engineering

--- FROST CREEK.g01 (geometry) --- (continued)

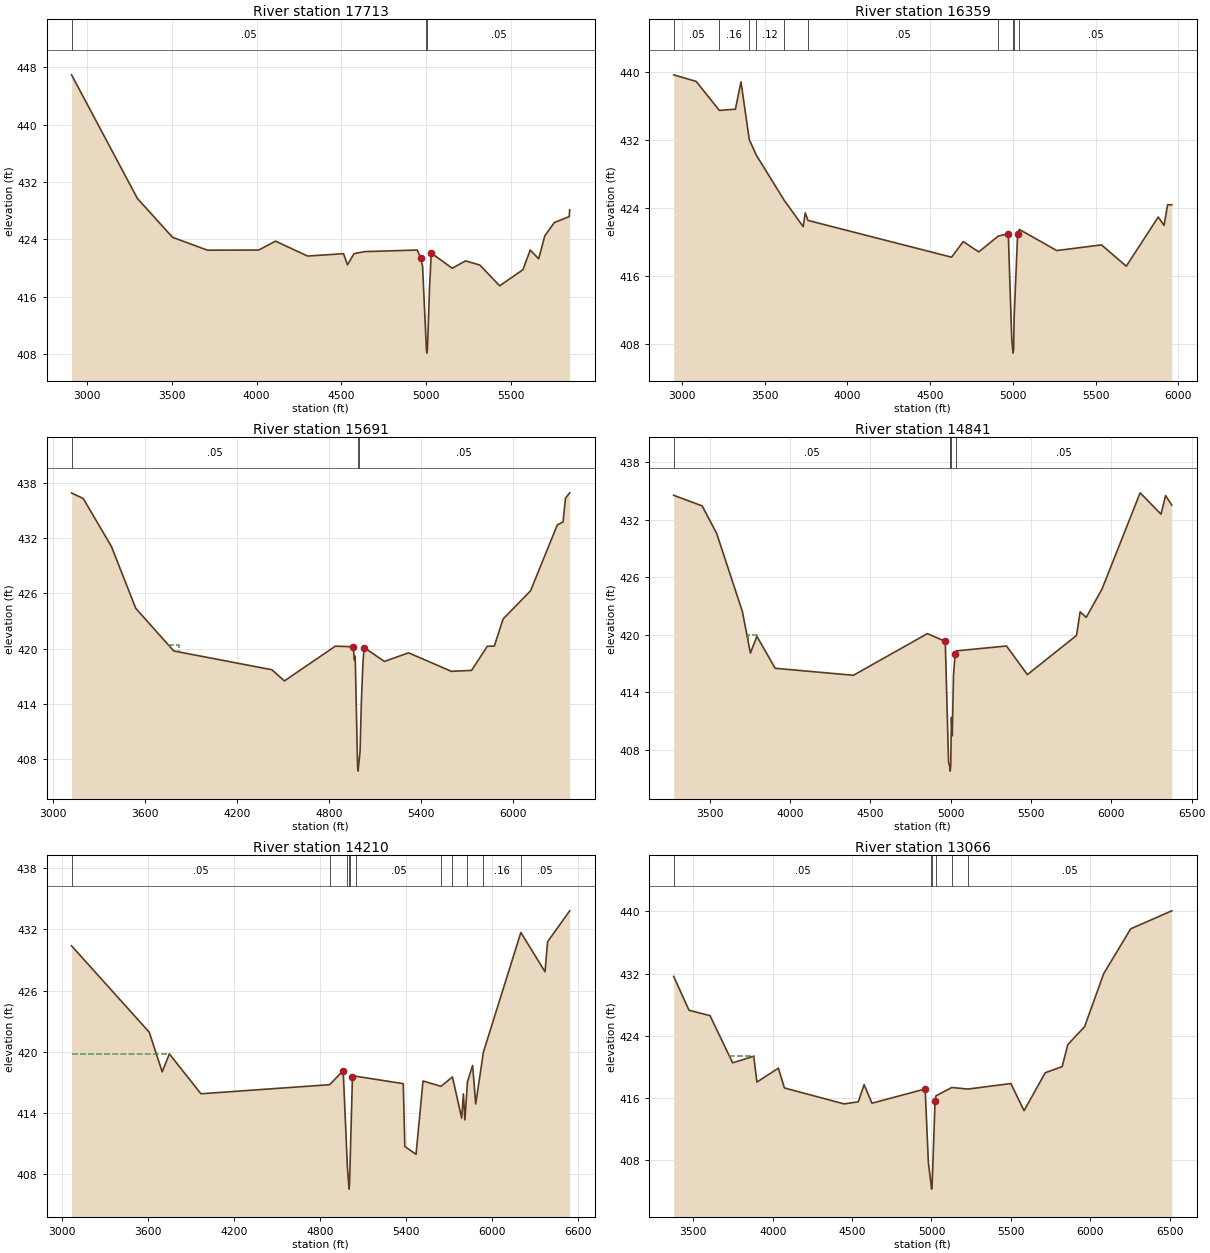
Type RM Length L Ch R = 1 ,17713   ,1354,1354,1354
BEGIN DESCRIPTION:
FROST CREEK 8.01
END DESCRIPTION:
XS GIS Cut Line= 3
      3479140.43     10533877.37      3478463.34     10532332.21
      3478046.88     10531152.25
#Sta/Elev= 30
  2908.2  446.95  3296.6   429.7    3504  424.28  3709.9  422.49  4012.2  422.51
  4111.2  423.75    4301  421.67  4512.5     422  4535.9  420.44    4574     422
  4638.2  422.29  4947.7  422.51    4967  421.43  4978.7  420.26  5001.3  408.63
  5004.1  408.13  5007.3  408.63    5020  417.34  5029.9  422.09  5153.7  419.97
  5232.1     421  5316.9  420.41  5433.6  417.52  5570.8  419.77  5613.8  422.51
  5663.6  421.28  5699.8   424.5  5756.3  426.35  5843.8  427.17  5846.5  428.12
#Mann= 3 ,-1 , 0
  2908.2     .05       0  5001.3     .03       0  5007.3     .05       0
Bank Sta=4967,5029.9
XS Rating Curve= 0 ,0
Exp/Cntr=0.3,0.1

Type RM Length L Ch R = 1 ,16359   ,668,668,668
BEGIN DESCRIPTION:
FROST CREEK 8.0
END DESCRIPTION:
XS GIS Cut Line= 3
      3480824.43     10532332.21      3479218.54     10531941.59
      3478142.14     10531116.92
#Sta/Elev= 30
    2951   439.7  3087.2  438.92  3226.8  435.51  3323.9  435.65  3357.6  438.87
  3407.4  432.09  3449.8  430.25  3619.4   424.9  3733.3  421.82  3745.8  423.44
  3762.3  422.55  4629.5  418.22  4700.2  420.06  4793.6  418.84  4912.2  420.72
  4972.2  420.95    4993  408.61  4998.3  407.42    5001  406.92  5004.3  407.42
  5007.6  411.19  5028.4  420.92  5038.9  421.49  5265.1     419  5535.2  419.67
  5684.8  417.16  5877.9  422.95  5913.2  421.97  5934.5   424.4  5959.7  424.39
#Mann= 10 ,-1 , 0
    2951     .05       0  3226.8     .16       0  3407.4     .05       0
  3449.8     .12       0  3619.4     .16       0  3762.3     .05       0
  4912.2     .16       0  4998.3     .07       0  5004.3     .16       0
  5038.9     .05       0
Bank Sta=4972.2,5028.4
XS Rating Curve= 0 ,0
Exp/Cntr=0.3,0.1

Type RM Length L Ch R = 1 ,15691   ,850,850,850
BEGIN DESCRIPTION:
FROST CREEK 9.3
END DESCRIPTION:
XS GIS Cut Line= 4
      3480917.97     10531750.69      3479158.45     10531434.96
      3478802.55     10531317.77       3477851.7     10530794.38
#Sta/Elev= 30
  3122.1  436.88  3197.9  436.29    3382  431.08  3540.4  424.37  3788.4  419.74
  4428.5   417.7  4509.8  416.49  4841.8  420.26  4958.5   420.2    4966  418.77
  4971.3  419.18  4987.1   407.2  4989.8   406.7  4993.1   407.2  5003.1  408.84
  5011.2  414.02  5021.7  418.42  5029.6  420.11    5162   418.6  5319.2  419.54
  5598.3  417.53  5730.1  417.63  5832.8  420.25  5878.5  420.27  5935.6  423.21
  6114.4  426.26  6289.4  433.42  6326.5  433.73  6342.6  436.33  6369.8   436.9
#Mann= 3 ,-1 , 0
  3122.1     .05       0  4987.1    .035       0  4993.1     .05       0
#XS Ineff= 1 ,-1
 3763.64 3819.32  420.42
Permanent Ineff=
       F
Bank Sta=4958.5,5029.6
XS Rating Curve= 0 ,0
Exp/Cntr=0.3,0.1

Type RM Length L Ch R = 1 ,14841   ,631,631,631
BEGIN DESCRIPTION:
FROST CREEK 8.1
END DESCRIPTION:
XS GIS Cut Line= 4
      3480779.11     10531264.58      3479141.09     10531165.86
      3478848.39     10531102.66      3477801.63     10530600.31
#Sta/Elev= 30
  3274.8  434.53  3452.1  433.43  3542.3  430.57  3702.6  422.43  3752.7   418.1
  3792.7  419.85  3906.7  416.52  4393.8  415.79  4854.7  420.13  4965.9  419.32
  4986.4   406.7  4992.5  406.37  4993.6  406.31  4996.3  405.81  4999.6  406.31
  5004.3   411.4  5009.4  409.49  5017.1  415.79  5027.3  418.05  5033.6  418.33
  5347.2  418.84  5477.3  415.86  5783.1  419.94  5805.7   422.4  5843.4  421.82
  5941.6  424.76  6179.2  434.79  6309.2  432.57  6337.7   434.5  6376.3  433.51
#Mann= 5 ,-1 , 0
  3274.8     .05       0  4992.5     .16       0  4993.6     .07       0
  4999.6     .16       0  5033.6     .05       0
#XS Ineff= 1 ,-1
  3735.8 3795.45  419.94
Permanent Ineff=
       F
Bank Sta=4965.9,5027.3
XS Rating Curve= 0 ,0
Exp/Cntr=0.3,0.1

Type RM Length L Ch R = 1 ,14210   ,1144,1144,1144
BEGIN DESCRIPTION:
FROST CREEK 9.2
END DESCRIPTION:
XS GIS Cut Line= 3
      3481003.41     10530973.15      3479563.33     10530880.26
      3477672.26     10530130.36
#Sta/Elev= 30
  3066.1  430.38  3608.5  421.92  3698.7  418.04  3748.8   419.8  3969.3  415.89
    4868  416.78  4962.3  418.16    4992  408.66  5000.6  407.05  5003.4  406.55
  5006.6  407.05  5026.9  417.52  5053.8   417.6  5381.8  416.88  5392.6  410.73
  5470.9  409.96  5519.5  417.14  5645.4  416.62  5725.1  417.54  5789.6  413.51
  5801.4  415.88  5812.2  413.33  5829.8  417.07  5865.9  418.66  5887.5  414.89
  5941.2  419.97  6202.7  431.69  6371.5  427.84  6389.2  430.78  6543.5  433.81
#Mann= 11 ,-1 , 0
  3066.1     .05       0    4868     .12       0    4992     .16       0
  5000.6     .07       0  5006.6     .16       0  5053.8     .05       0
  5645.4     .12       0  5725.1     .16       0  5829.8     .12       0
  5941.2     .16       0  6202.7     .05       0
#XS Ineff= 2 , 0
         3745.45  419.79
Permanent Ineff=
       F       F
Bank Sta=4962.3,5026.9
XS Rating Curve= 0 ,0
Exp/Cntr=0.3,0.1

Type RM Length L Ch R = 1 ,13066   ,2012,2012,2012
BEGIN DESCRIPTION:
FROST CREEK 8.2
END DESCRIPTION:
XS GIS Cut Line= 6
      3481006.87     10530851.62      3479913.13     10530639.82
      3479669.45     10530333.97       3479352.7      10530269.8
      3478883.86     10530030.15      3478328.33     10529478.97
#Sta/Elev= 30
  3376.1  431.64  3472.6  427.28    3605  426.59  3747.6  420.52  3880.4  421.37
  3900.4  418.04  4035.7  419.84  4073.6  417.29  4449.8  415.24    4539  415.51
  4575.5  417.72  4625.1  415.33  4960.1  417.16  4980.5  407.65  4997.9  404.78
  5000.7  404.28  5003.9  404.78  5022.6  415.66  5027.7  416.27  5127.8  417.35
  5229.9  417.15  5499.8  417.86  5583.1  414.37  5716.4  419.25    5823  420.03
  5858.4  422.86  5964.5  425.18  6084.7  431.99  6254.4  437.75  6513.5  440.07
#Mann= 6 ,-1 , 0
  3376.1     .05       0  4997.9    .035       0  5003.9     .05       0
  5027.7     .12       0  5127.8     .16       0  5229.9     .05       0
#XS Ineff= 2 ,-1
 3722.73 3881.82   421.4 3886.36 4034.09  419.77
Permanent Ineff=
       F       F
Bank Sta=4960.1,5022.6
XS Rating Curve= 0 ,0
Exp/Cntr=0.3,0.1

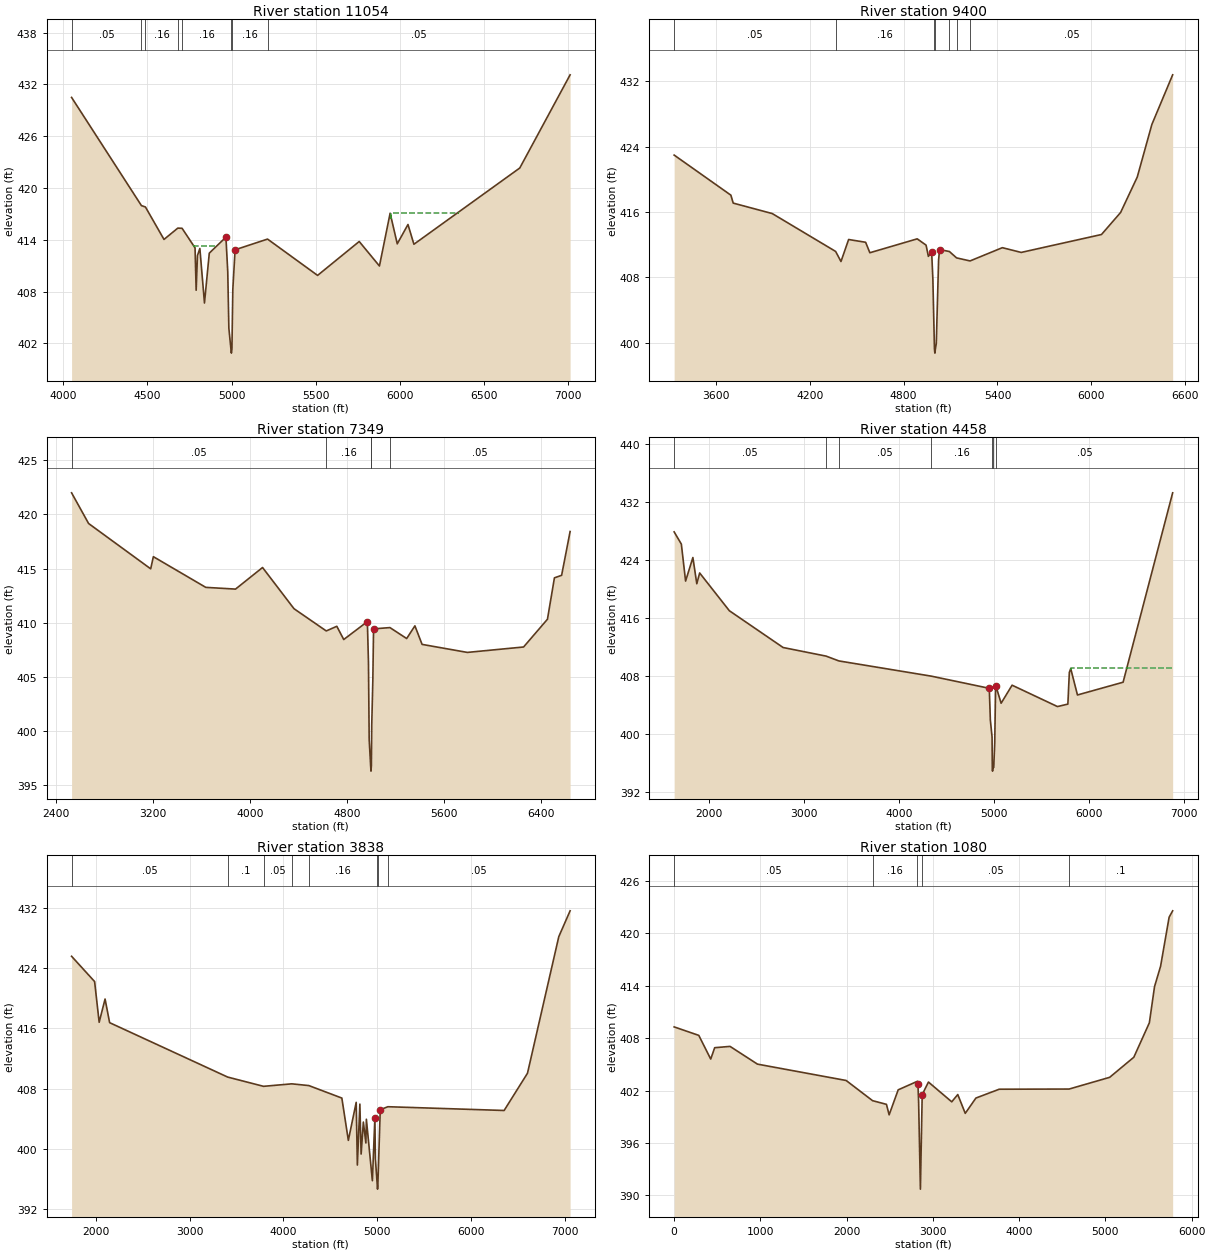
Type RM Length L Ch R = 1 ,11054   ,1654,1654,1654
BEGIN DESCRIPTION:
FROST CREEK 7.1
END DESCRIPTION:
XS GIS Cut Line= 4
      3481093.57     10530674.26      3480510.21     10529984.99
      3480312.29     10529526.66       3479208.1     10528422.47
#Sta/Elev= 30
  4049.1   430.5  4464.3  417.96  4488.1   417.8  4598.5  414.04  4680.5  415.35
    4706  415.33  4783.1  413.06  4789.7  408.15  4797.4  412.17  4811.7  412.99
  4839.1  406.67  4867.7  412.45  4966.6   414.3  4977.5  410.32  4984.1  403.75
  4996.3  401.36  4999.1  400.86  5002.3  401.36  5007.6  408.22  5021.1  412.84
  5214.1  414.08  5511.6  409.87  5759.1   413.8  5879.3  410.96  5942.9  417.08
  5985.3  413.53    6049  415.77  6084.3  413.48  6713.7  422.32  7012.9  433.12
#Mann= 8 ,-1 , 0
  4049.1     .05       0  4464.3     .12       0  4488.1     .16       0
  4680.5     .12       0    4706     .16       0  4996.3     .07       0
  5002.3     .16       0  5214.1     .05       0
#XS Ineff= 2 ,-1
 4771.59 4908.81  413.32 5950.85 6350.57  417.13
Permanent Ineff=
       F       F
Bank Sta=4966.6,5021.1
XS Rating Curve= 0 ,0
Exp/Cntr=0.3,0.1

Type RM Length L Ch R = 1 ,9400    ,2051,2051,2051
BEGIN DESCRIPTION:
FROST CREEK 5.0
END DESCRIPTION:
XS GIS Cut Line= 3
      3481666.46     10530353.05      3480537.99     10528755.82
       3479557.1     10528009.31
#Sta/Elev= 30
  3332.3  422.96  3695.2  418.06    3710  417.09  3959.8  415.81  4365.1  411.18
  4399.3  409.95  4448.2  412.64    4557   412.3    4584  411.02  4886.9  412.72
  4943.5  411.95  4958.3  410.58  4979.2  411.11    4987   407.8  4997.1  399.25
  4999.9  398.75  5003.1  399.25  5008.8  399.91  5023.6  410.13  5029.7  411.41
  5092.8  411.17  5138.7  410.39  5224.9  410.02  5431.3  411.64  5551.9  411.06
  6065.4  413.25  6187.6  415.94  6294.1  420.27  6387.6   426.7  6520.6  432.77
#Mann= 7 ,-1 , 0
  3332.3     .05       0  4365.1     .16       0  4997.1     .07       0
  5003.1     .16       0  5092.8     .05       0  5138.7     .16       0
  5224.9     .05       0
Bank Sta=4979.2,5029.7
XS Rating Curve= 0 ,0
Exp/Cntr=0.3,0.1

Type RM Length L Ch R = 1 ,7349    ,2891,2891,2891
BEGIN DESCRIPTION:
FROST CREEK 4.0
END DESCRIPTION:
XS GIS Cut Line= 3
      3482855.68     10530422.46      3481301.88     10528113.46
      3480650.86     10526958.99
#Sta/Elev= 30
  2532.1  421.98  2672.3  419.15    3184  414.97  3206.1  416.09    3638  413.26
  3883.1   413.1  4105.9  415.09  4365.2  411.29    4631  409.24  4717.8  409.67
    4775  408.45  4969.7   410.1  4978.7  406.37  4984.7  399.21  4996.7  396.81
  4999.4  396.31  5002.7  396.81  5005.7  400.55  5014.7  404.65  5020.7  409.43
  5155.6  409.55  5293.6  408.54  5361.6  409.71  5420.6     408  5793.5  407.26
  6257.2  407.76  6453.9  410.32  6511.4  414.14  6570.6  414.37  6640.6  418.41
#Mann= 5 ,-1 , 0
  2532.1     .05       0    4631     .16       0  4996.7     .07       0
  5002.7     .16       0  5155.6     .05       0
Bank Sta=4969.7,5020.7
XS Rating Curve= 0 ,0
Exp/Cntr=0.3,0.1

Type RM Length L Ch R = 1 ,4458    ,620,620,620
BEGIN DESCRIPTION:
FROST CREEK 3.0
END DESCRIPTION:
XS GIS Cut Line= 3
       3483942.1     10530441.62      3482642.11     10527341.64
      3481042.12     10526341.65
#Sta/Elev= 30
  1631.5  427.94  1707.4  426.25    1752  421.15  1828.8   424.4    1870  420.78
  1900.1  422.27  2212.5  417.06  2778.8  411.98  3229.7   410.8  3365.7  410.13
  4338.2  408.03  4949.2  406.35  4960.5  401.97  4978.4  399.64  4980.9  395.42
  4983.6  394.92  4986.9  395.42    4996  395.43  5006.6  398.78    5016  406.66
  5023.1  406.49  5073.8  404.29  5189.4  406.78    5667  403.83  5776.6  404.17
    5792  408.54  5806.7  409.07  5877.5  405.43    6358  407.19  6879.8  433.33
#Mann= 7 ,-1 , 0
  1631.5     .05       0  3229.7      .1       0  3365.7     .05       0
  4338.2     .16       0  4980.9     .07       0  4986.9     .16       0
  5023.1     .05       0
#XS Ineff= 2 , 0
                         5810.23          409.09
Permanent Ineff=
       F       F
Bank Sta=4949.2,5016
XS Rating Curve= 0 ,0
Exp/Cntr=0.3,0.1

Type RM Length L Ch R = 1 ,3838    ,2759,2759,2759
BEGIN DESCRIPTION:
FROST CREEK 2.0
END DESCRIPTION:
XS GIS Cut Line= 3
       3484142.1     10530341.64      3483142.11     10527241.64
      3481542.07     10525941.61
#Sta/Elev= 30
  1739.4  425.58    1985  422.22  2033.6  416.81  2096.6   419.9  2145.2  416.76
  3404.4  409.53  3787.1   408.3  4088.6  408.63  4270.5   408.4  4622.9  406.74
  4692.2  401.12    4776  406.17  4788.4  397.84  4815.2  405.94  4828.6   399.3
  4852.5  403.55  4879.3  400.77  4884.5  403.93  4948.6  395.76  4975.4  404.14
  4980.7  398.68  5000.9  395.14  5003.6  394.64  5006.9  395.14  5032.6  405.19
  5114.2  405.59  6354.3  405.09  6603.6  410.04  6937.6  428.19  7058.3  431.62
#Mann= 8 ,-1 , 0
  1739.4     .05       0  3404.4      .1       0  3787.1     .05       0
  4088.6     .12       0  4270.5     .16       0  5000.9     .07       0
  5006.9     .16       0  5114.2     .05       0
Bank Sta=4975.4,5032.6
XS Rating Curve= 0 ,0
Exp/Cntr=0.3,0.1

Type RM Length L Ch R = 1 ,1080    ,1012,1012,1012
BEGIN DESCRIPTION:
FROST CREEK 1.0
END DESCRIPTION:
XS GIS Cut Line= 4
      3483640.62     10528660.81      3484593.75     10526567.06
      3484372.39     10525748.91      3481742.18     10525837.89
#Sta/Elev= 30
       0  409.28   285.7  408.31     424   405.6   470.1   406.9     648  407.05
     966  405.02  1994.1  403.15  2300.5  400.84  2461.5  400.42  2492.6  399.22
  2597.6  402.08  2821.3  403.06  2826.5  402.77  2834.4  400.69  2855.2  390.72
  2875.9  401.53  2948.4  402.97  3218.4  400.71  3288.4  401.54    3375  399.39
  3498.5  401.14  3768.7  402.15  4579.1  402.17  5049.4  403.51  5329.6  405.81
  5509.7  409.75  5569.7  413.89  5639.8  416.22  5738.8  421.83  5779.8  422.56
#Mann= 5 ,-1 , 0
       0     .05       0  2300.5     .16       0  2821.3     .07       0
  2875.9     .05       0  4579.1      .1       0
Bank Sta=2826.5,2875.9
XS Rating Curve= 0 ,0
Exp/Cntr=0.3,0.1

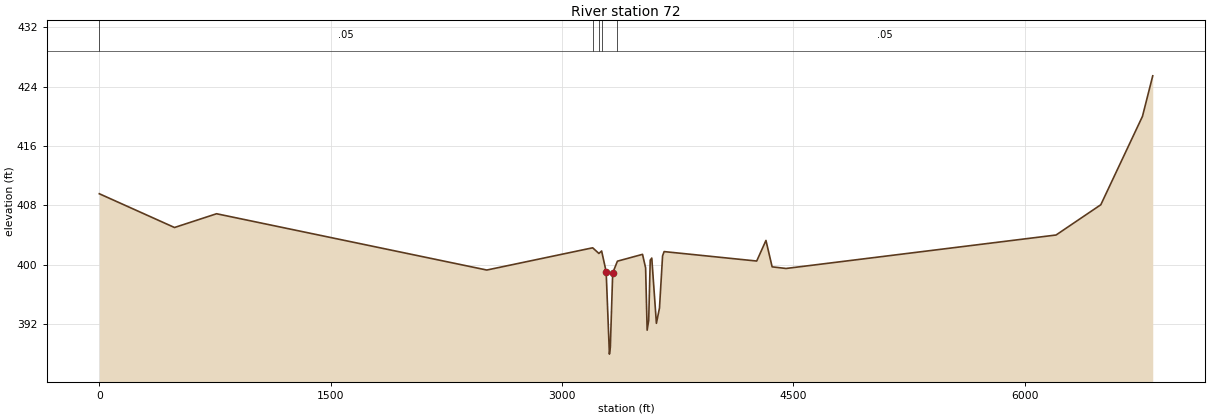
Type RM Length L Ch R = 1 ,72      ,0,0,0
XS GIS Cut Line= 6
      3483680.03     10528702.66      3484815.45     10526137.56
      3485198.95     10525935.73      3485194.42     10525918.68
       3485067.5     10525715.36      3481733.94     10525800.13
#Sta/Elev= 30
       0  409.58   487.3  405.04   759.9  406.89  2511.8  399.32  3198.1  402.31
  3238.5  401.55  3256.2  401.88  3285.5  399.11  3306.7  388.01  3312.6  388.94
    3328  398.92  3358.6  400.51  3521.3  401.43  3541.3  399.61  3551.3  391.23
  3561.3  392.54  3571.3  400.65  3581.3  400.93  3611.3  392.15  3631.3  394.22
  3651.3  401.22  3661.3   401.8  4261.5  400.53  4321.5   403.3  4361.5  399.75
  4451.6  399.53  6202.1  404.03  6492.2   408.1  6762.3  419.99  6828.9  425.44
#Mann= 5 ,-1 , 0
       0     .05       0  3198.1     .16       0  3238.5     .07       0
  3256.2     .16       0  3358.6     .05       0
Bank Sta=3285.5,3328
XS Rating Curve= 0 ,0
Exp/Cntr=0.3,0.1

Chan Stop Cuts=-1
Use User Specified Reach Order=0
Composite Channel Slope=5