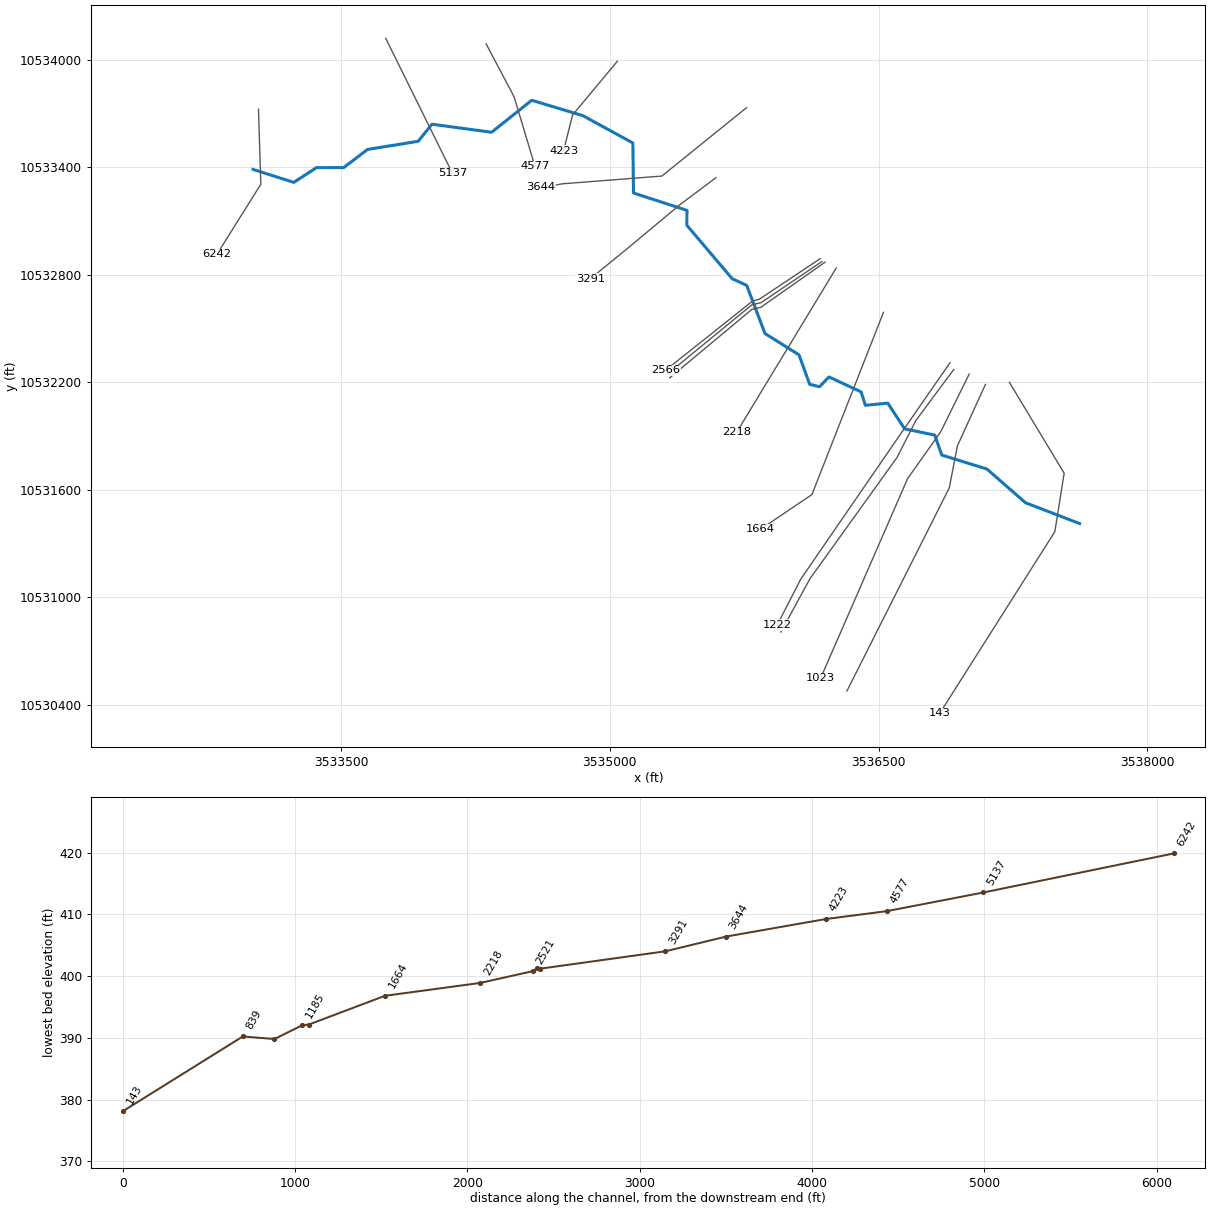
--- GIBSON BRANCH.prj (project) ---

Proj Title=GIBSON BRANCH Base Level Engineering
Current Plan=p01
Default Exp/Contr=0.3,0.1
English Units
Geom File=g01
Flow File=f01
Plan File=p01
BEGIN DESCRIPTION:
GIBSON BRANCH
END DESCRIPTION:

--- GIBSON BRANCH.p01 (plan) ---

Plan Title=Multiple Run
Short Identifier=Multiple
Geom File=g01
Flow File=f01
Subcritical Flow
K Sum by GR= 0
Std Step Tol= 0.01
Critical Tol= 0.01
Num of Std Step Trials= 20
Max Error Tol= 0.3
Flow Tol Ratio= 0.001
Split Flow NTrial= 30
Split Flow Tol= 0.02
Split Flow Ratio= 0.02
Log Output Level= 0
Friction Slope Method= 1
Unsteady Friction Slope Method= 2
Unsteady Bridges Friction Slope Method= 1
Parabolic Critical Depth
Global Vel Dist=  1 , 1 , 1
Global Log Level= 0
CheckData=True
Encroach Param= -1, 0, 0, 0
BEGIN DESCRIPTION:
Multiple Run
END DESCRIPTION:

--- GIBSON BRANCH.f01 (steady flow) ---

Flow Title=Multiple
Number of Profiles=7
Profile Names=10-year,25-year,50-year,1pct_min,100-year,1pct_plu,500-year
River Rch & RM= GIBSON BRANCH,Reach-1,6242
     409     531     626     540     731     988     991
River Rch & RM= GIBSON BRANCH,Reach-1,4223
     492     647     769     669     904    1223    1245
River Rch & RM= GIBSON BRANCH,Reach-1,3291
     870    1184    1441    1279    1730    2339    2486
Boundary for River Rch & Prof#=GIBSON BRANCH,Reach-1,1
Up Type=0
Dn Type=3
Dn Slope=0.005
Boundary for River Rch & Prof#=GIBSON BRANCH,Reach-1,2
Up Type=0
Dn Type=3
Dn Slope=0.005
Boundary for River Rch & Prof#=GIBSON BRANCH,Reach-1,3
Up Type=0
Dn Type=3
Dn Slope=0.005
Boundary for River Rch & Prof#=GIBSON BRANCH,Reach-1,4
Up Type=0
Dn Type=3
Dn Slope=0.005
Boundary for River Rch & Prof#=GIBSON BRANCH,Reach-1,5
Up Type=0
Dn Type=3
Dn Slope=0.005
Boundary for River Rch & Prof#=GIBSON BRANCH,Reach-1,6
Up Type=0
Dn Type=3
Dn Slope=0.005
Boundary for River Rch & Prof#=GIBSON BRANCH,Reach-1,7
Up Type=0
Dn Type=3
Dn Slope=0.005

--- GIBSON BRANCH.g01 (geometry) ---

Geom Title=Existing Conditions

River Reach=GIBSON BRANCH,Reach-1
Reach XY= 30
      3533009.06     10533388.19      3533236.38     10533315.68
      3533363.31     10533398.07      3533514.91     10533398.12
      3533647.99     10533499.49      3533930.93     10533544.98
      3534007.45     10533640.25      3534340.48     10533595.45
      3534564.42     10533774.03      3534850.49     10533687.75
      3535128.84     10533535.51      3535132.32     10533256.40
      3535430.68     10533159.52      3535430.16     10533076.24
      3535682.75     10532778.34      3535764.03     10532741.02
      3535866.11     10532472.27      3536055.93     10532353.05
      3536115.57     10532188.58      3536170.39     10532175.20
      3536223.06     10532229.91      3536402.23     10532146.58
      3536426.53     10532071.58      3536551.62     10532083.56
      3536645.11     10531940.59      3536813.34     10531905.19
      3536852.69     10531793.90      3537104.63     10531716.04
      3537320.08     10531527.79      3537622.11     10531411.64

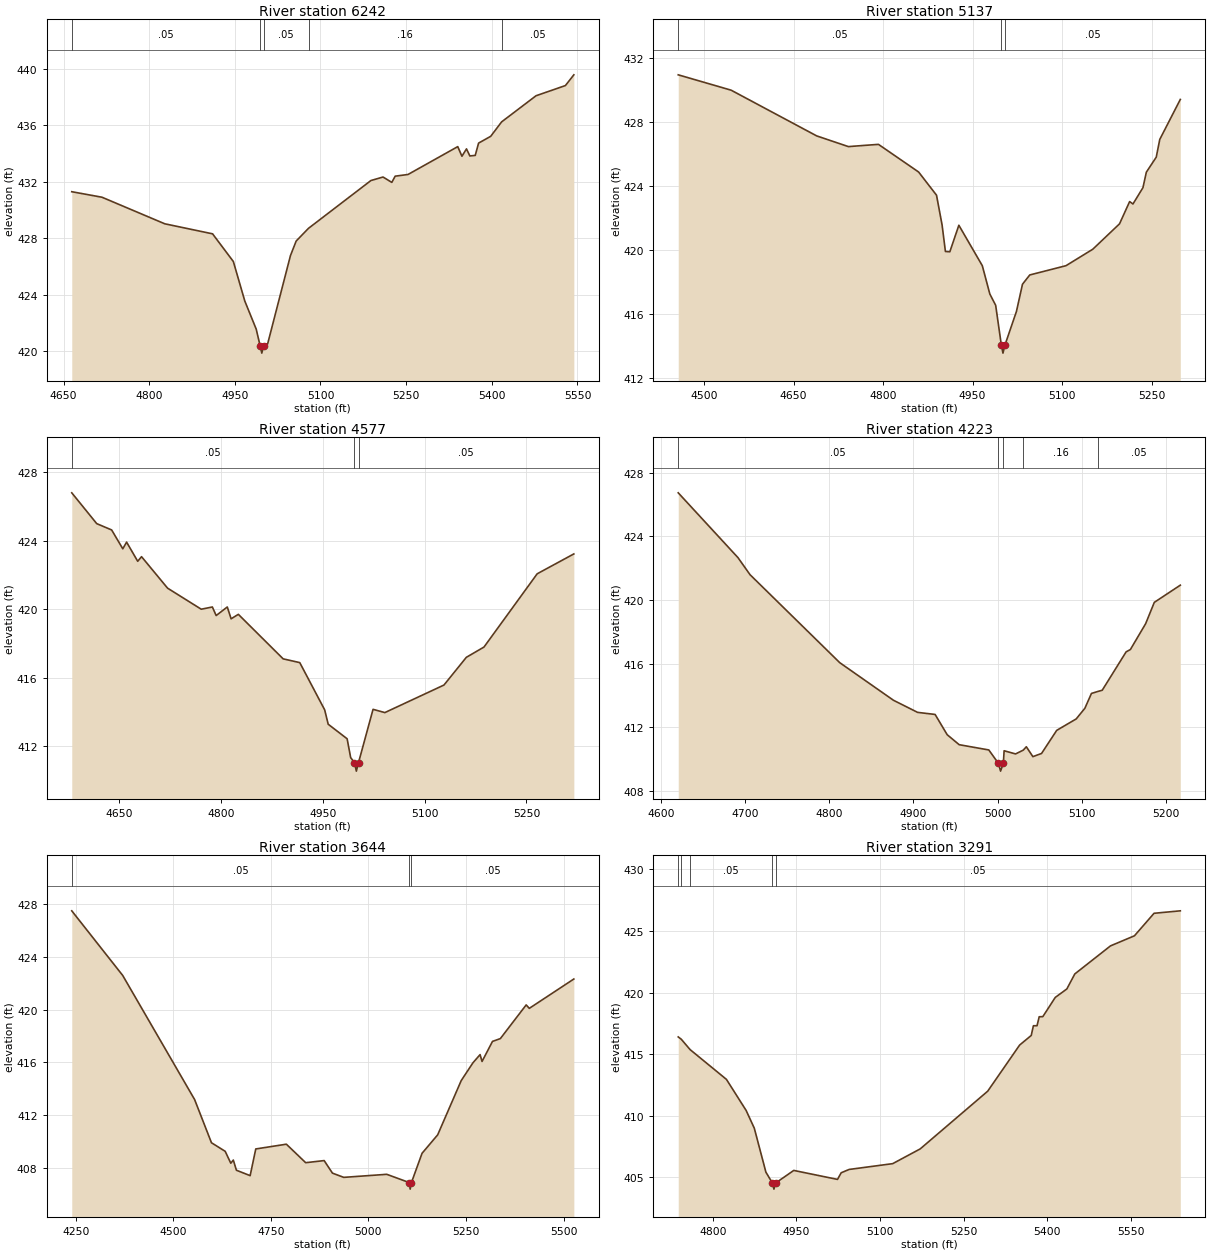
Type RM Length L Ch R = 1,6242,1105,1105,1105
BEGIN DESCRIPTION:
GIBSON BRANCH 13.0
END DESCRIPTION:
XS GIS Cut Line= 3
      3533039.49     10533724.49      3533052.52     10533305.19
      3532808.36     10532915.58
#Sta/Elev= 30
  4664.4  431.30  4717.3  430.91  4827.3  429.03  4911.0  428.32  4947.4  426.36
  4967.4  423.57  4987.4  421.58  4994.4  420.38  4997.2  419.88  5000.4  420.38
  5007.4  420.53  5047.4  426.78  5057.4  427.81  5079.0  428.71  5188.3  432.09
  5209.5  432.34  5224.9  431.96  5230.8  432.40  5253.3  432.52  5340.4  434.49
  5347.7  433.81  5355.7  434.33  5361.6  433.83  5371.0  433.87  5376.9  434.74
  5398.1  435.22  5417.2  436.24  5477.5  438.09  5528.9  438.81  5543.7  439.57
#Mann=5,-1,0
  4664.4    0.05       0  4994.4    0.03       0  5000.4    0.05       0
  5079.0    0.16       0  5417.2    0.05       0
Bank Sta=4994.4,5000.4
Exp/Cntr=0.3,0.1

Type RM Length L Ch R = 1,5137,560,560,560
BEGIN DESCRIPTION:
GIBSON BRANCH 11.0
END DESCRIPTION:
XS GIS Cut Line= 2
      3533749.58     10534119.57      3534122.26     10533365.54
#Sta/Elev= 30
  4456.9  430.96  4545.5  430.00  4688.8  427.14  4741.9  426.47  4792.3  426.61
  4859.6  424.88  4889.6  423.43  4898.9  421.57  4904.5  419.91  4911.9  419.89
  4927.0  421.55  4966.3  419.02  4978.9  417.25  4988.7  416.54  4998.2  414.05
  5000.9  413.55  5004.2  414.05  5023.5  416.16  5033.6  417.86  5045.8  418.44
  5106.5  419.02  5151.4  420.05  5196.2  421.64  5213.1  423.03  5218.7  422.88
  5235.4  423.90  5241.1  424.87  5257.7  425.81  5263.6  426.92  5298.0  429.42
#Mann=3,-1,0
  4456.9    0.05       0  4998.2    0.03       0  5004.2    0.05       0
Bank Sta=4998.2,5004.2
Exp/Cntr=0.3,0.1

Type RM Length L Ch R = 1,4577,354,354,354
BEGIN DESCRIPTION:
GIBSON BRANCH 10.0
END DESCRIPTION:
XS GIS Cut Line= 3
      3534309.70     10534088.83      3534465.93     10533793.72
      3534582.59     10533404.86
#Sta/Elev= 30
  4580.0  426.79  4616.8  424.99  4638.8  424.62  4655.2  423.52  4660.8  423.91
  4677.2  422.79  4682.8  423.06  4721.2  421.22  4770.8  419.99  4787.2  420.12
  4792.8  419.62  4809.2  420.12  4814.8  419.43  4825.5  419.69  4891.5  417.09
  4916.0  416.87  4952.7  414.11  4957.9  413.27  4985.8  412.42  4991.0  411.32
  4996.6  411.03  4999.4  410.53  5002.6  411.03  5024.0  414.14  5041.4  413.95
  5128.5  415.56  5161.5  417.18  5187.5  417.78  5265.9  422.06  5319.9  423.22
#Mann=3,-1,0
  4580.0    0.05       0  4996.6    0.03       0  5002.6    0.05       0
Bank Sta=4996.6,5002.6
Exp/Cntr=0.3,0.1

Type RM Length L Ch R = 1,4223,579,579,579
BEGIN DESCRIPTION:
GIBSON BRANCH 9.0
END DESCRIPTION:
XS GIS Cut Line= 3
      3535042.13     10533991.67      3534792.11     10533691.64
      3534742.11     10533491.65
#Sta/Elev= 30
  4620.4  426.73  4691.4  422.66  4705.7  421.59  4812.4  416.06  4876.2  413.70
  4904.9  412.94  4925.7  412.81  4940.0  411.54  4954.3  410.91  4989.5  410.58
  5000.8  409.75  5003.5  409.25  5006.8  409.75  5007.7  410.53  5021.3  410.33
  5030.5  410.57  5034.1  410.78  5041.9  410.16  5052.2  410.36  5070.2  411.81
  5093.4  412.53  5103.7  413.20  5111.5  414.13  5118.9  414.25  5124.3  414.33
  5152.7  416.74  5157.8  416.89  5175.9  418.51  5186.2  419.85  5217.1  420.93
#Mann=5,-1,0
  4620.4    0.05       0  5000.8    0.03       0  5006.8    0.05       0
  5030.5    0.16       0  5118.9    0.05       0
Bank Sta=5000.8,5006.8
Exp/Cntr=0.3,0.1

Type RM Length L Ch R = 1,3644,353,353,353
BEGIN DESCRIPTION:
GIBSON BRANCH 8.0
END DESCRIPTION:
XS GIS Cut Line= 4
      3535763.67     10533732.95      3535290.59     10533351.01
      3534735.03     10533307.61      3534615.64     10533287.75
#Sta/Elev= 30
  4240.0  427.47  4370.5  422.58  4554.7  413.19  4597.9  409.92  4633.1  409.27
  4647.4  408.37  4653.9  408.61  4661.8  407.84  4697.0  407.43  4711.4  409.45
  4789.8  409.81  4839.3  408.41  4886.6  408.57  4907.9  407.62  4936.8  407.30
  5047.1  407.53  5104.3  406.91  5107.0  406.41  5110.3  406.91  5137.4  409.12
  5177.5  410.52  5237.7  414.62  5267.8  415.97  5286.1  416.59  5291.1  416.07
  5317.9  417.59  5338.0  417.80  5404.2  420.35  5412.2  420.09  5526.3  422.31
#Mann=3,-1,0
  4240.0    0.05       0  5104.3    0.03       0  5110.3    0.05       0
Bank Sta=5104.3,5110.3
Exp/Cntr=0.3,0.1

Type RM Length L Ch R = 1,3291,725,725,725
BEGIN DESCRIPTION:
GIBSON BRANCH 7.0
END DESCRIPTION:
XS GIS Cut Line= 4
      3535592.14     10533341.67      3535392.11     10533191.64
      3535092.11     10532941.64      3534890.33     10532777.13
#Sta/Elev= 30
  4738.1  416.39  4743.6  416.20  4759.4  415.36  4824.6  412.94  4860.0  410.41
  4874.6  408.97  4895.4  405.40  4907.0  404.52  4909.8  404.02  4913.0  404.52
  4945.4  405.54  5023.9  404.81  5030.5  405.35  5044.8  405.62  5122.9  406.09
  5172.3  407.29  5293.4  411.98  5350.7  415.73  5371.5  416.51  5375.4  417.30
  5381.9  417.30  5385.8  418.03  5392.3  418.04  5414.6  419.60  5435.4  420.29
  5449.7  421.51  5513.7  423.79  5556.7  424.61  5591.9  426.44  5639.0  426.64
#Mann=5,-1,0
  4738.1    0.05       0  4743.6    0.16       0  4759.4    0.05       0
  4907.0    0.03       0  4913.0    0.05       0
Bank Sta=4907,4913
Exp/Cntr=0.3,0.1

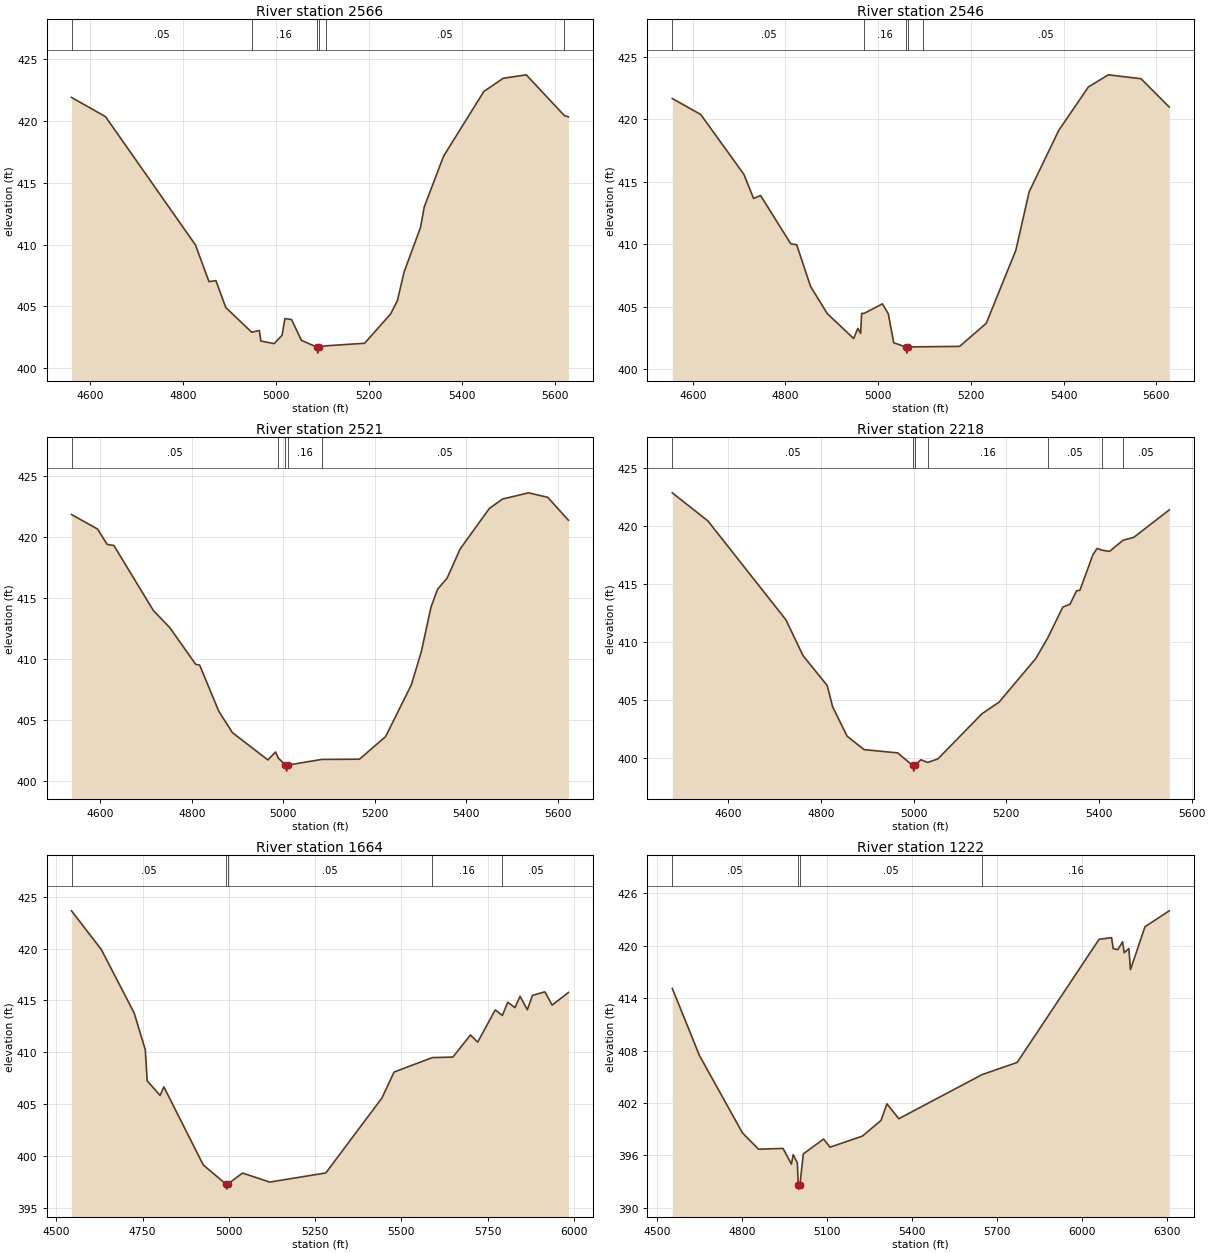
Type RM Length L Ch R = 1,2566,20,20,20
BEGIN DESCRIPTION:
GIBSON BRANCH 6.03
END DESCRIPTION:
XS GIS Cut Line= 4
      3536174.07     10532889.86      3535833.47     10532662.98
      3535796.67     10532653.60      3535310.70     10532266.54
#Sta/Elev= 30
  4560.6  421.92  4633.8  420.36  4827.3  409.96  4856.2  407.00  4871.2  407.08
  4892.2  404.91  4948.1  402.90  4964.4  403.04  4967.7  402.19  4996.3  401.98
  5013.4  402.66  5019.5  404.01  5033.9  403.93  5054.8  402.25  5087.4  401.71
  5090.1  401.21  5093.4  401.71  5107.4  401.80  5190.9  402.01  5246.9  404.39
  5261.4  405.47  5275.8  407.79  5311.0  411.38  5319.0  413.04  5360.6  417.16
  5447.2  422.40  5488.8  423.47  5538.4  423.75  5620.6  420.44  5629.1  420.35
#Mann=6,-1,0
  4560.6    0.05       0  4948.1    0.16       0  5087.4    0.07       0
  5093.4    0.16       0  5107.4    0.05       0  5620.6     0.1       0
Bank Sta=5087.4,5093.4
Exp/Cntr=0.3,0.1

Type RM Length L Ch R = 1,2546,25,25,25
BEGIN DESCRIPTION:
GIBSON BRANCH 6.0
END DESCRIPTION:
XS GIS Cut Line= 4
      3536183.81     10532873.85      3535843.92     10532644.10
      3535794.00     10532633.25      3535322.18     10532246.20
#Sta/Elev= 30
  4556.0  421.67  4617.4  420.39  4710.3  415.60  4731.3  413.66  4746.3  413.90
  4811.5  410.03  4824.3  409.95  4854.2  406.61  4890.1  404.44  4947.1  402.44
  4956.0  403.25  4962.1  402.85  4964.3  404.45  4970.1  404.46  5009.1  405.22
  5021.8  404.42  5033.5  402.10  5059.2  401.77  5061.9  401.27  5065.2  401.77
  5097.4  401.78  5175.6  401.81  5233.0  403.66  5296.8  409.51  5325.5  414.19
  5389.4  419.12  5453.3  422.60  5496.3  423.57  5566.7  423.26  5627.6  420.99
#Mann=5,-1,0
  4556.0    0.05       0  4970.1    0.16       0  5059.2    0.07       0
  5065.2    0.16       0  5097.4    0.05       0
Bank Sta=5059.2,5065.2
Exp/Cntr=0.3,0.1

Type RM Length L Ch R = 1,2521,303,303,303
BEGIN DESCRIPTION:
GIBSON BRANCH 6.01
END DESCRIPTION:
XS GIS Cut Line= 4
      3536201.85     10532870.63      3535842.83     10532618.55
      3535792.83     10532606.75      3535335.18     10532225.49
#Sta/Elev= 30
  4537.4  421.85  4594.3  420.66  4615.2  419.40  4630.0  419.31  4716.3  413.97
  4752.0  412.58  4808.7  409.56  4817.4  409.50  4859.2  405.71  4888.9  403.96
  4966.4  401.72  4983.2  402.37  4989.1  401.88  5004.6  401.30  5007.4  400.80
  5010.6  401.30  5083.8  401.76  5166.6  401.78  5223.6  403.63  5279.9  407.88
  5301.7  410.60  5322.8  414.25  5337.2  415.72  5358.0  416.63  5386.6  419.03
  5450.4  422.35  5479.1  423.12  5536.0  423.63  5578.0  423.26  5623.1  421.38
#Mann=5,-1,0
  4537.4    0.05       0  4989.1    0.16       0  5004.6    0.07       0
  5010.6    0.16       0  5083.8    0.05       0
Bank Sta=5004.6,5010.6
Exp/Cntr=0.3,0.1

Type RM Length L Ch R = 1,2218,554,554,554
BEGIN DESCRIPTION:
GIBSON BRANCH 4.0
END DESCRIPTION:
XS GIS Cut Line= 2
      3536263.50     10532837.35      3535707.94     10531920.67
#Sta/Elev= 30
  4479.7  422.85  4556.5  420.43  4724.8  411.92  4761.7  408.84  4813.8  406.27
  4825.7  404.42  4856.7  401.91  4893.5  400.75  4965.8  400.47  4997.9  399.40
  5000.6  398.90  5003.9  399.40  5015.7  399.88  5030.7  399.65  5052.5  399.95
  5147.5  403.83  5184.4  404.83  5263.9  408.60  5289.6  410.37  5322.1  413.02
  5337.6  413.26  5351.7  414.42  5358.9  414.46  5386.8  417.50  5395.7  418.06
  5407.1  417.91  5422.9  417.81  5451.9  418.77  5475.2  419.02  5551.6  421.38
#Mann=7,-1,0
  4479.7    0.05       0  4997.9    0.03       0  5003.9    0.05       0
  5030.7    0.16       0  5289.6    0.05       0  5407.1    0.16       0
  5451.9    0.05       0
Bank Sta=4997.9,5003.9
Exp/Cntr=0.3,0.1

Type RM Length L Ch R = 1,1664,442,442,442
BEGIN DESCRIPTION:
GIBSON BRANCH 3.01
END DESCRIPTION:
XS GIS Cut Line= 3
      3536527.37     10532590.78      3536128.07     10531573.43
      3535839.84     10531378.96
#Sta/Elev= 30
  4543.7  423.64  4630.3  419.90  4725.4  413.79  4757.6  410.24  4763.2  407.25
  4800.6  405.84  4811.3  406.67  4925.9  399.13  4991.0  397.31  4993.7  396.81
  4997.0  397.31  5039.7  398.36  5118.4  397.49  5281.0  398.37  5443.7  405.60
  5478.9  408.10  5589.8  409.49  5649.3  409.54  5700.2  411.67  5721.2  410.98
  5772.2  414.09  5792.8  413.55  5808.2  414.83  5829.2  414.31  5844.1  415.40
  5865.1  414.10  5880.1  415.49  5916.1  415.83  5937.1  414.55  5984.3  415.77
#Mann=5,-1,0
  4543.7    0.05       0  4991.0    0.03       0  4997.0    0.05       0
  5589.8    0.16       0  5792.8    0.05       0
Bank Sta=4991,4997
Exp/Cntr=0.3,0.1

Type RM Length L Ch R = 1,1222,37,37,37
BEGIN DESCRIPTION:
GIBSON BRANCH 3.0
END DESCRIPTION:
XS GIS Cut Line= 4
      3536898.89     10532309.53      3536600.29     10531878.99
      3536065.57     10531101.21      3535934.24     10530845.47
#Sta/Elev= 30
  4553.0  415.12  4648.9  407.44  4800.9  398.58  4857.6  396.72  4944.1  396.81
  4973.8  395.01  4979.9  396.09  4994.7  395.16  4997.8  392.65  5000.6  392.15
  5003.8  392.65  5015.7  396.18  5087.3  397.88  5110.1  396.95  5224.6  398.22
  5290.2  400.01  5311.2  401.91  5353.1  400.21  5647.6  405.26  5771.2  406.65
  6060.5  420.74  6104.8  420.93  6110.4  419.67  6127.0  419.56  6143.6  420.46
  6149.2  419.20  6165.8  419.69  6171.4  417.27  6222.7  422.18  6308.3  424.00
#Mann=4,-1,0
  4553.0    0.05       0  4997.8    0.03       0  5003.8    0.05       0
  5647.6    0.16       0
Bank Sta=4997.8,5003.8
Exp/Cntr=0.3,0.1

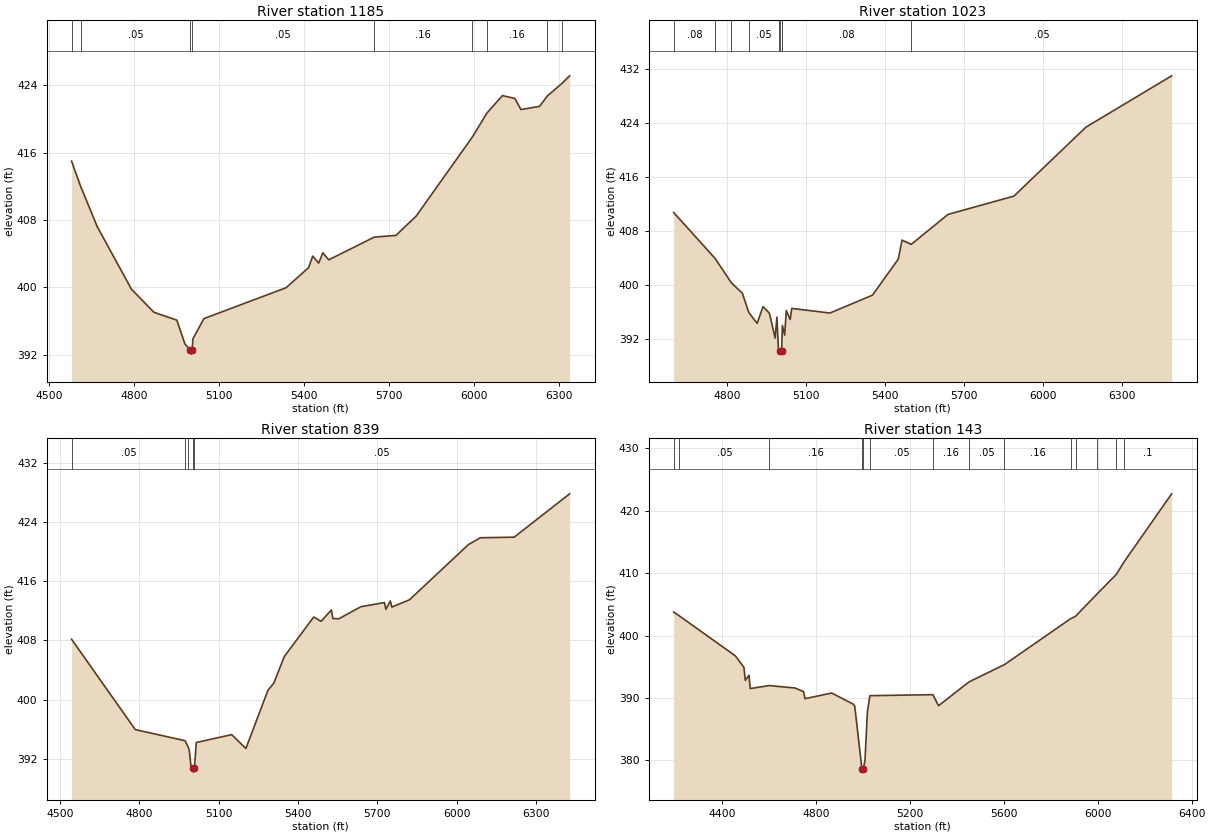
Type RM Length L Ch R = 1,1185,162,162,162
BEGIN DESCRIPTION:
GIBSON BRANCH 3.1
END DESCRIPTION:
XS GIS Cut Line= 5
      3536919.76     10532271.39      3536707.93     10531986.62
      3536603.76     10531781.76      3536117.65     10531104.68
      3535954.62     10530806.37
#Sta/Elev= 30
  4578.0  414.99  4610.2  411.98  4668.7  407.20  4789.6  399.76  4868.9  397.02
  4949.7  396.09  4978.3  393.24  4997.6  392.55  5000.3  392.05  5003.6  392.55
  5006.2  393.85  5045.1  396.27  5335.2  399.94  5414.7  402.33  5429.5  403.70
  5450.3  402.87  5465.1  404.10  5485.9  403.26  5646.7  405.96  5722.9  406.16
  5794.1  408.44  5992.8  417.85  6044.2  420.70  6099.1  422.78  6142.8  422.44
  6164.6  421.12  6230.0  421.50  6257.7  422.74  6309.0  424.22  6336.2  425.13
#Mann=9,-1,0
  4578.0    0.08       0  4610.2    0.05       0  4997.6    0.03       0
  5003.6    0.05       0  5646.7    0.16       0  5992.8    0.08       0
  6044.2    0.16       0  6257.7    0.08       0  6309.0    0.16       0
Bank Sta=4997.6,5003.6
Exp/Cntr=0.3,0.1

Type RM Length L Ch R = 1,1023,184,184,184
BEGIN DESCRIPTION:
GIBSON BRANCH 2.0
END DESCRIPTION:
XS GIS Cut Line= 4
      3537005.75     10532245.87      3536845.78     10531922.15
      3536662.12     10531662.65      3536176.56     10530548.46
#Sta/Elev= 30
  4595.2  410.81  4752.8  404.01  4815.1  400.38  4856.5  398.85  4881.3  395.98
  4913.0  394.37  4935.4  396.86  4959.7  395.87  4981.4  392.19  4988.1  395.29
  4994.2  390.35  4996.8  390.33  4999.9  390.31  5002.6  389.81  5005.9  390.31
  5007.7  392.48  5009.0  394.05  5017.6  392.63  5023.8  396.28  5038.5  394.95
  5044.7  396.59  5189.7  395.90  5351.7  398.55  5449.8  403.89  5464.1  406.71
  5499.2  406.08  5639.0  410.52  5889.6  413.23  6163.6  423.45  6489.6  431.06
#Mann=9,-1,0
  4595.2    0.08       0  4752.8    0.05       0  4815.1    0.08       0
  4881.3    0.05       0  4996.8    0.16       0  4999.9    0.07       0
  5005.9    0.16       0  5007.7    0.08       0  5499.2    0.05       0
Bank Sta=4999.9,5005.9
Exp/Cntr=0.3,0.1

Type RM Length L Ch R = 1,839,696,696,696
BEGIN DESCRIPTION:
GIBSON BRANCH 2.1
END DESCRIPTION:
XS GIS Cut Line= 4
      3537096.15     10532187.84      3536939.88     10531844.95
      3536894.53     10531610.56      3536323.58     10530477.77
#Sta/Elev= 30
  4543.8  408.16  4784.8  395.96  4973.3  394.46  4983.4  393.73  4989.0  393.20
  4995.3  391.08  5002.5  390.72  5005.2  390.22  5008.5  390.72  5015.7  394.22
  5149.5  395.28  5203.3  393.41  5286.9  401.29  5309.2  402.25  5348.3  405.81
  5459.8  411.16  5487.7  410.58  5526.7  412.11  5532.3  410.96  5554.6  410.92
  5638.3  412.55  5727.5  413.11  5733.1  412.20  5749.8  413.33  5755.4  412.50
  5822.3  413.49  6045.4  420.95  6090.0  421.86  6218.3  421.94  6427.9  427.79
#Mann=5,-1,0
  4543.8    0.05       0  4973.3    0.16       0  4983.4    0.05       0
  5002.5    0.03       0  5008.5    0.05       0
Bank Sta=5002.5,5008.5
Exp/Cntr=0.3,0.1

Type RM Length L Ch R = 1,143,0,0,0
BEGIN DESCRIPTION:
GIBSON BRANCH 1.0
END DESCRIPTION:
XS GIS Cut Line= 4
      3537230.22     10532199.61      3537535.78     10531692.66
      3537483.70     10531366.27      3536841.34     10530352.37
#Sta/Elev= 30
  4192.0  403.77  4216.9  403.13  4454.8  396.75  4491.6  394.91  4497.5  392.82
  4513.0  393.63  4518.8  391.50  4599.8  391.98  4709.1  391.59  4746.0  391.01
  4751.8  389.88  4866.0  390.78  4957.1  389.01  4964.0  388.71  4994.6  378.61
  4997.4  378.11  5000.6  378.61  5007.7  380.02  5017.9  387.69  5028.4  390.36
  5297.2  390.52  5321.2  388.75  5450.8  392.56  5602.3  395.34  5884.4  402.70
  5905.0  403.07  5996.5  406.64  6078.9  409.79  6110.9  411.74  6314.7  422.70
#Mann=14,-1,0
  4192.0    0.16       0  4216.9    0.05       0  4599.8    0.16       0
  4994.6    0.07       0  5000.6    0.16       0  5028.4    0.05       0
  5297.2    0.16       0  5450.8    0.05       0  5602.3    0.16       0
  5884.4     0.1       0  5905.0    0.16       0  5996.5     0.1       0
  6078.9    0.16       0  6110.9     0.1       0
Bank Sta=4994.6,5000.6
Exp/Cntr=0.3,0.1

Chan Stop Cuts=-1