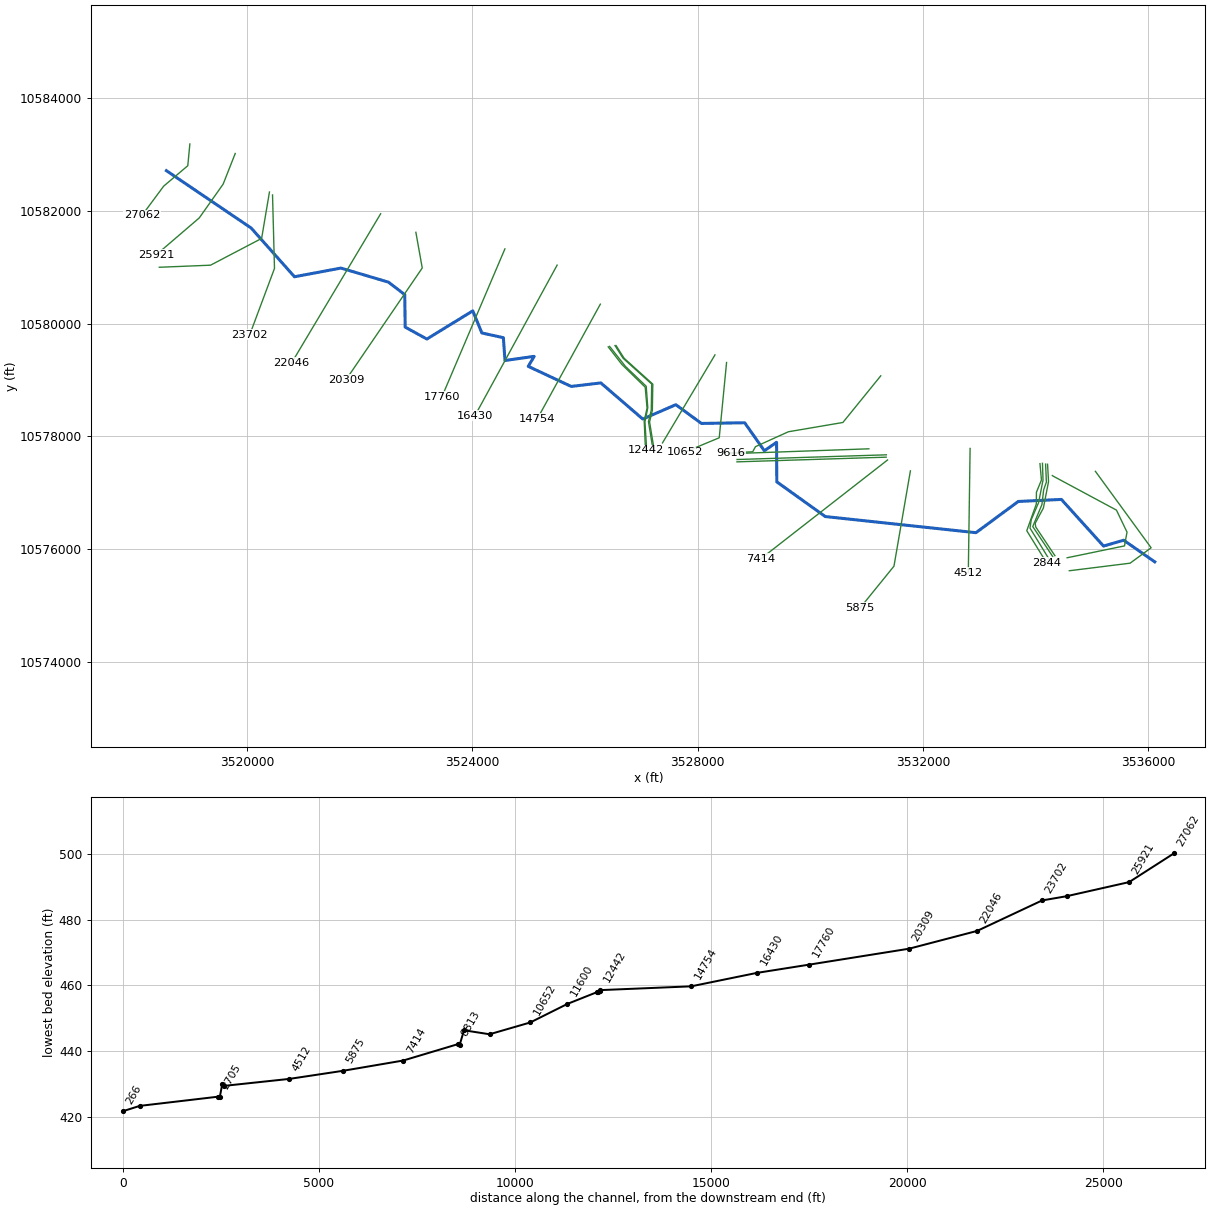
--- GROVE ISLAND CREEK.prj (project) ---

Proj Title=GROVE ISLAND CREEK Base Level Engineering
Current Plan=p01
Default Exp/Contr=0.3,0.1
English Units
Geom File=g01
Flow File=f01
Plan File=p01
Y Axis Title=Elevation
X Axis Title(PF)=Main Channel Distance
X Axis Title(XS)=Station
BEGIN DESCRIPTION:
GROVE ISLAND CREEK
END DESCRIPTION:
DSS Export Rating Curves= 0
DSS Export Rating Curve Sorted= 0
DSS Export Volume Flow Curves= 0
DXF OffsetX= 0
DXF OffsetY= 0
DXF ScaleX= 1
DXF ScaleY= 10

--- GROVE ISLAND CREEK.p01 (plan) ---

Plan Title=Multiple Run
Short Identifier=Multiple
Geom File=g01
Flow File=f01
Subcritical Flow
K Sum by GR= 0
Std Step Tol= 0.01
Critical Tol= 0.01
Num of Std Step Trials= 20
Max Error Tol= 0.3
Flow Tol Ratio= 0.001
Split Flow NTrial= 30
Split Flow Tol= 0.02
Split Flow Ratio= 0.02
Log Output Level= 0
Friction Slope Method= 1
Unsteady Friction Slope Method= 2
Unsteady Bridges Friction Slope Method= 1
Parabolic Critical Depth
Global Vel Dist=  1 , 1 , 1
Global Log Level= 0
CheckData=True
Encroach Param= -1, 0, 0, 0
BEGIN DESCRIPTION:
Multiple Run
END DESCRIPTION:

--- GROVE ISLAND CREEK.f01 (steady flow) ---

Flow Title=Multiple
Program Version=4.10
Number of Profiles= 7
Profile Names=10-year,25-year,50-year,1pct_min,100-year,1pct_plu,500-year
River Rch & RM=GROVE ISLAND CRE,Reach-1         ,27062
    1062    1464    1796    1607    2173    2938    3173
River Rch & RM=GROVE ISLAND CRE,Reach-1         ,23702
    1521    2129    2638    2380    3219    4353    4783
River Rch & RM=GROVE ISLAND CRE,Reach-1         ,16430
    1572    2196    2717    2447    3309    4475    4898
River Rch & RM=GROVE ISLAND CRE,Reach-1         ,12371
    1916    2708    3377    3063    4143    5602    6224
River Rch & RM=GROVE ISLAND CRE,Reach-1         ,9616
    2601    3714    4662    4252    5750    7776    8735
Boundary for River Rch & Prof#=GROVE ISLAND CRE,Reach-1         , 1
Up Type= 0
Dn Type= 3
Dn Slope=0.005
Boundary for River Rch & Prof#=GROVE ISLAND CRE,Reach-1         , 2
Up Type= 0
Dn Type= 3
Dn Slope=0.005
Boundary for River Rch & Prof#=GROVE ISLAND CRE,Reach-1         , 3
Up Type= 0
Dn Type= 3
Dn Slope=0.005
Boundary for River Rch & Prof#=GROVE ISLAND CRE,Reach-1         , 4
Up Type= 0
Dn Type= 3
Dn Slope=0.005
Boundary for River Rch & Prof#=GROVE ISLAND CRE,Reach-1         , 5
Up Type= 0
Dn Type= 3
Dn Slope=0.005
Boundary for River Rch & Prof#=GROVE ISLAND CRE,Reach-1         , 6
Up Type= 0
Dn Type= 3
Dn Slope=0.005
Boundary for River Rch & Prof#=GROVE ISLAND CRE,Reach-1         , 7
Up Type= 0
Dn Type= 3
Dn Slope=0.005
DSS Import GetInterval= 0
DSS Import GetPeak= 0
DSS Import FillOption= 0

--- GROVE ISLAND CREEK.g01 (geometry) ---

Geom Title=Existing Conditions
Program Version=4.10

River Reach=GROVE ISLAND CRE,Reach-1
Reach XY= 30
      3518569.12     10582717.72      3520072.97     10581699.37
      3520842.07     10580833.69      3521666.94     10580987.79
      3522510.19     10580737.92      3522799.46     10580516.07
      3522807.14      10579939.2       3523192.3     10579727.63
      3524007.12     10580227.86      3524168.85     10579834.93
      3524549.79     10579751.21      3524578.73     10579346.18
      3525097.42     10579419.52      3524991.42     10579242.22
       3525754.1     10578885.66      3526279.91     10578948.02
      3527024.15     10578306.55      3527611.13     10578561.24
       3528065.3     10578228.42      3528833.19     10578240.41
      3529182.67      10577742.7      3529399.33     10577893.39
      3529403.04     10577191.09      3530263.45      10576574.7
      3532938.34       10576288.      3533689.07     10576842.63
       3534454.7     10576878.74      3535202.62     10576050.61
      3535560.95     10576154.08      3536112.22       10575770.

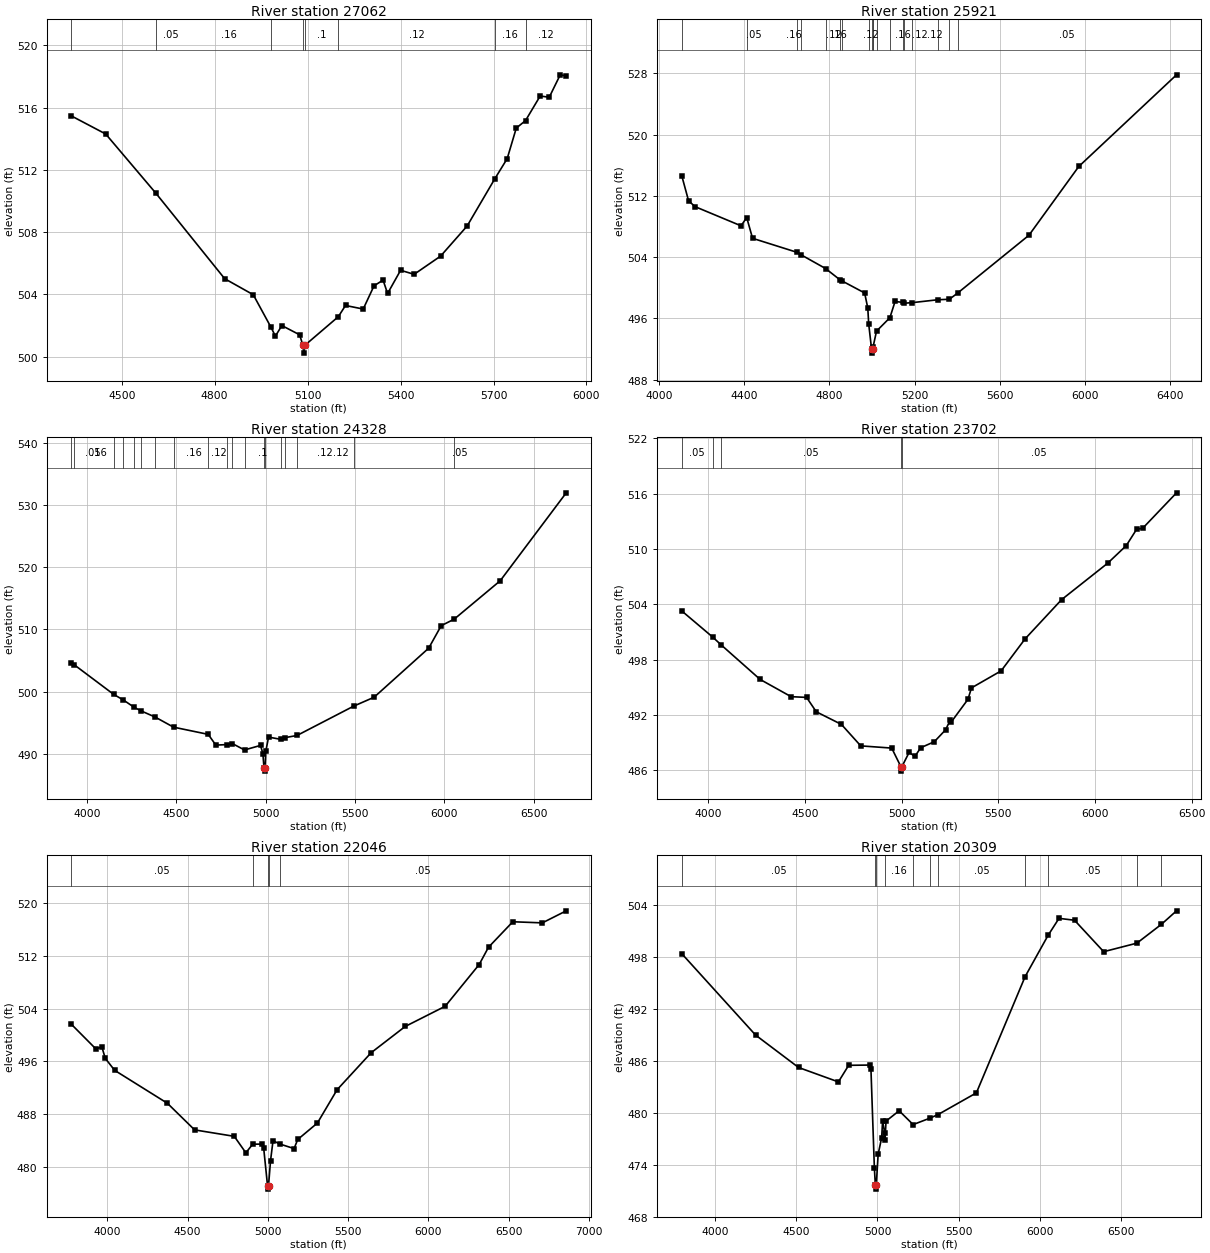
Type RM Length L Ch R = 1 ,27062   ,1141,1141,1141
BEGIN DESCRIPTION:
GROVE ISLAND CREEK 1.1
END DESCRIPTION:
XS GIS Cut Line= 4
      3518985.32     10583191.82      3518948.43     10582805.57
      3518520.91     10582443.16      3518134.63     10581922.33
#Sta/Elev= 30
  4337.7  515.46  4448.4   514.3  4609.8  510.51  4832.3  505.01  4924.6  503.98
  4981.8  501.89    4996  501.32  5016.9     502    5074  501.41    5085  500.73
  5087.7  500.23    5091  500.73  5199.1  502.57  5222.3  503.29  5279.4  503.06
  5314.3  504.55  5343.5  504.92  5358.1  504.06  5400.1  505.55  5443.7  505.29
  5529.2  506.46  5614.7  508.39  5703.7  511.41  5744.1  512.72  5773.4  514.68
  5803.2  515.16  5850.5  516.74  5879.8  516.66  5915.2   518.1  5934.6  518.03
#Mann= 8 ,-1 , 0
  4337.7     .05       0  4981.8     .16       0  4609.8     .16       0
    5085     .07       0    5091      .1       0  5199.1     .12       0
  5703.7     .16       0  5803.2     .12       0
Bank Sta=5085,5091
XS Rating Curve= 0 ,0
Exp/Cntr=0.3,0.1

Type RM Length L Ch R = 1 ,25921   ,1593,1593,1593
BEGIN DESCRIPTION:
GROVE ISLAND CREEK 1.3
END DESCRIPTION:
XS GIS Cut Line= 4
      3519790.45      10583022.6       3519575.6     10582477.88
      3519152.42     10581878.92      3518391.22     10581226.15
#Sta/Elev= 30
    4107  514.65  4139.1  511.37  4168.9   510.6  4385.4  508.09    4412  509.17
  4439.5  506.46    4646  504.65  4666.4  504.32  4781.9  502.52  4848.5  501.07
  4859.3   500.9  4965.3  499.33  4980.1  497.37  4984.4  495.28    4998  491.98
  5000.8  491.48    5004  491.98    5005   492.3  5021.1  494.35  5083.8   496.1
  5108.1  498.22  5144.7   498.1  5149.6  497.99  5189.7  498.07  5307.6  498.44
    5363  498.51  5401.5  499.31  5736.3  506.86  5970.1  515.83  6428.7  527.79
#Mann= 19 ,-1 , 0
    4107     .05       0  4781.9     .16       0    4412     .16       0
  4859.3     .05       0    4646     .12       0    4998     .03       0
    5004     .12       0    5005     .16       0  4666.4     .16       0
  5021.1      .1       0  4848.5     .12       0  5144.7     .05       0
  4984.4     .16       0  5307.6      .1       0  5083.8     .12       0
    5363     .05       0  5149.6     .16       0  5189.7     .12       0
  5401.5     .05       0
Bank Sta=4998,5004
XS Rating Curve= 0 ,0
Exp/Cntr=0.3,0.1

Type RM Length L Ch R = 1 ,24328   ,626,626,626
BEGIN DESCRIPTION:
GROVE ISLAND CREEK 1.2
END DESCRIPTION:
XS GIS Cut Line= 4
      3520398.08     10582338.99      3520259.19     10581514.34
      3519352.08     10581039.08      3518442.77     10581002.18
#Sta/Elev= 30
  3912.6  504.51  3927.1  504.33  4149.1  499.54  4204.1  498.62  4265.4  497.43
  4304.3  496.86  4381.8  495.88  4484.4  494.26  4678.6   493.1  4721.2  491.37
  4782.8  491.45  4813.3  491.62  4881.8  490.59  4971.4  491.32  4984.6  490.01
  4990.9  487.68  4993.7  487.18  4996.9  487.68    5001  490.38  5016.5  492.66
  5084.6   492.3  5106.3  492.56  5175.7  492.92  5492.7  497.64  5607.5  499.08
    5913  506.98  5983.1   510.6  6055.8  511.65  6313.4  517.83    6683  531.99
#Mann= 19 ,-1 , 0
  3912.6     .05       0  4149.1     .16       0  3927.1     .16       0
  4204.1     .12       0  4265.4     .12       0  4304.3     .05       0
  4381.8     .16       0  4813.3     .16       0  4484.4     .12       0
  4990.9     .07       0  4996.9     .12       0  5106.3     .05       0
  4678.6     .16       0  4782.8     .12       0  6055.8     .05       0
  4881.8      .1       0  5084.6     .16       0  5175.7     .12       0
  5492.7     .05       0
Bank Sta=4990.9,4996.9
XS Rating Curve= 0 ,0
Exp/Cntr=0.3,0.1

Type RM Length L Ch R = 1 ,23702   ,1656,1656,1656
BEGIN DESCRIPTION:
GROVE ISLAND CREEK 1.0
END DESCRIPTION:
XS GIS Cut Line= 3
       3520452.7     10582287.15      3520487.42     10580981.58
      3520049.93       10579808.
#Sta/Elev= 30
  3863.3  503.28  4023.3  500.44  4068.3  499.57  4268.9  495.84    4429  493.97
    4509  493.89  4559.1  492.33  4689.1  490.96  4789.1  488.63  4949.2  488.39
  4996.2  486.39    4999  485.89  5002.2  486.39  5039.2  487.92  5069.2  487.49
  5099.2  488.43  5169.3  489.08  5227.7  490.37  5252.7  491.47    5258  491.25
  5343.7  493.69  5361.4  494.92  5514.9  496.77  5638.8  500.24  5827.1  504.49
  6065.7  508.45  6161.8  510.36  6215.1  512.12  6247.2  512.25  6421.8  516.09
#Mann= 5 ,-1 , 0
  3863.3     .05       0  4023.3     .12       0  4068.3     .05       0
  4996.2     .03       0  5002.2     .05       0
Bank Sta=4996.2,5002.2
XS Rating Curve= 0 ,0
Exp/Cntr=0.3,0.1

Type RM Length L Ch R = 1 ,22046   ,1737,1737,1737
BEGIN DESCRIPTION:
GROVE ISLAND CREEK 2.0
END DESCRIPTION:
XS GIS Cut Line= 2
      3522372.07     10581952.83      3520792.62     10579305.96
#Sta/Elev= 30
  3775.7  501.64  3928.5  497.89  3965.1  498.22  3986.7  496.47  4044.9  494.65
  4373.8  489.64  4543.2   485.6  4790.2  484.62  4862.3  482.12  4905.2  483.43
  4964.9  483.44  4973.3  482.86  4997.5   477.1  5000.2   476.6  5003.5   477.1
  5016.1  480.92  5031.6  483.96  5073.1  483.46  5162.8  482.76  5185.4  484.14
    5308  486.64  5430.7   491.7  5642.7  497.32  5854.9  501.31    6104  504.38
  6315.7  510.72  6373.9  513.35  6525.3  517.22  6709.2  517.05    6858  518.88
#Mann= 5 ,-1 , 0
  3775.7     .05       0  4905.2     .12       0  4997.5     .07       0
  5003.5     .12       0  5073.1     .05       0
Bank Sta=4997.5,5003.5
XS Rating Curve= 0 ,0
Exp/Cntr=0.3,0.1

Type RM Length L Ch R = 1 ,20309   ,2549,2549,2549
BEGIN DESCRIPTION:
GROVE ISLAND CREEK 3.0
END DESCRIPTION:
XS GIS Cut Line= 3
      3522997.08     10581622.94      3523109.92      10580989.3
      3521756.09     10579003.73
#Sta/Elev= 30
  3794.4  498.43  4249.3     489  4513.9  485.25  4759.2  483.58  4822.5   485.5
  4953.7  485.53  4959.7  485.03  4980.7  473.66  4986.6  471.67  4989.3  471.17
  4992.6  471.67    5004  475.21  5025.5  477.11  5031.5  479.07  5043.8  477.71
  5046.5  476.89  5052.5  479.04  5133.2  480.24  5219.4  478.64  5320.9  479.37
  5372.9   479.8  5608.9  482.31  5909.1  495.77    6050  500.53  6117.6  502.51
  6213.2  502.29  6392.7  498.65  6597.4  499.64  6747.6  501.81  6841.2  503.38
#Mann= 11 ,-1 , 0
  3794.4     .05       0  4986.6     .07       0  4992.6     .05       0
  5043.8     .16       0  5219.4     .05       0  5320.9     .16       0
  5372.9     .05       0  5909.1      .1       0    6050     .05       0
  6597.4      .1       0  6747.6     .05       0
Bank Sta=4986.6,4992.6
XS Rating Curve= 0 ,0
Exp/Cntr=0.3,0.1

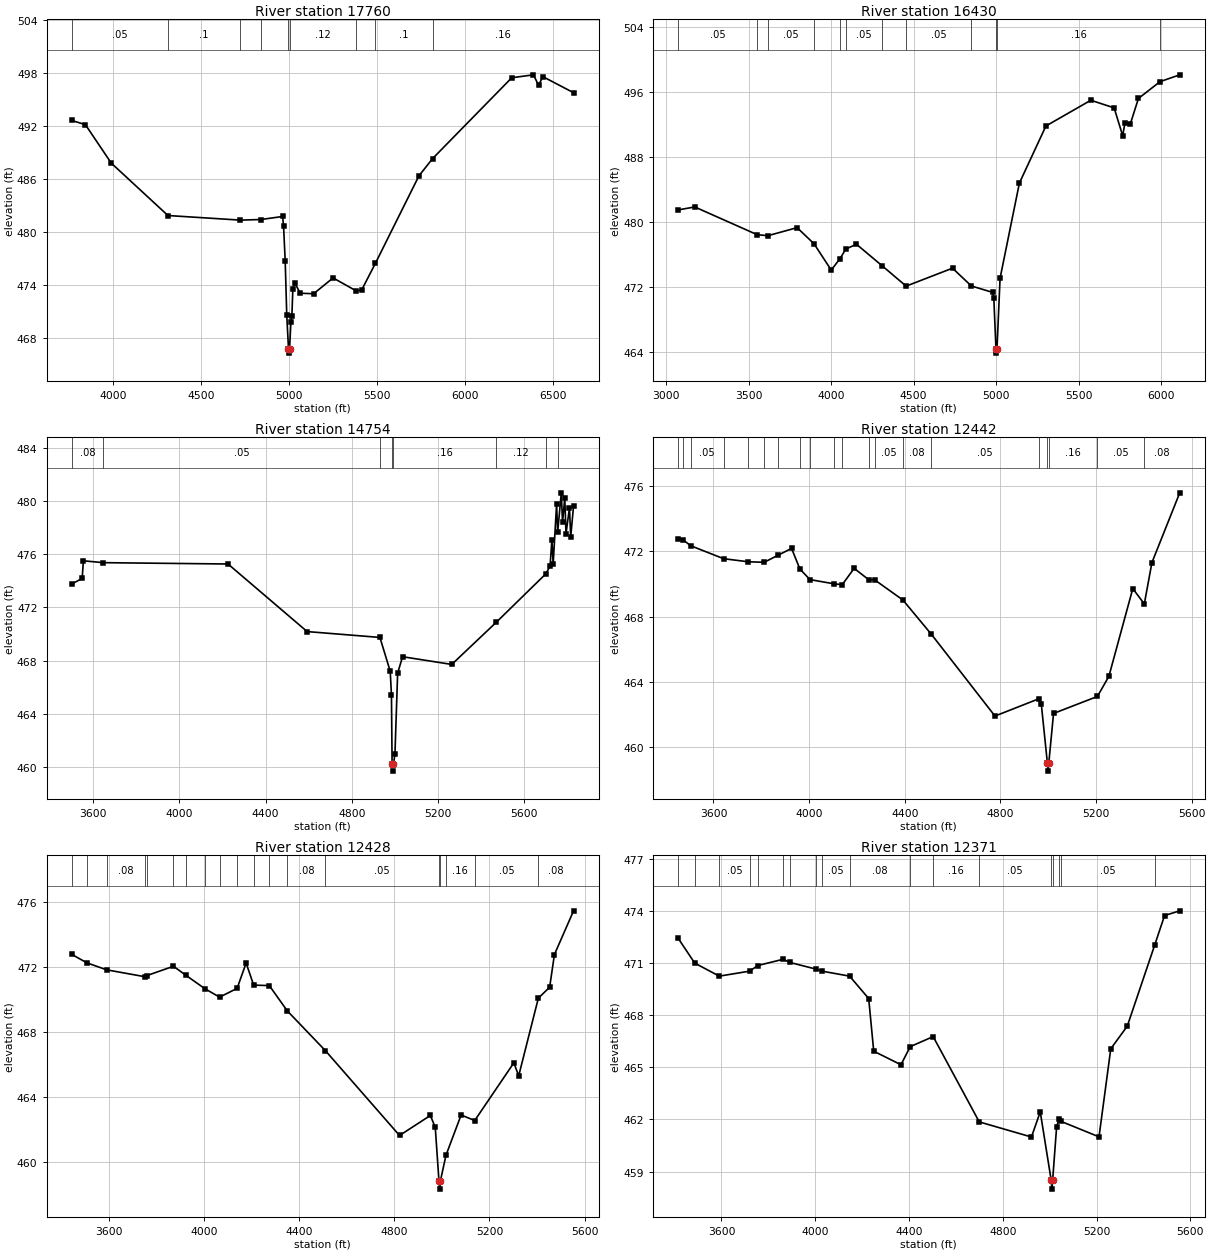
Type RM Length L Ch R = 1 ,17760   ,1330,1330,1330
BEGIN DESCRIPTION:
GROVE ISLAND CREEK 4.0
END DESCRIPTION:
XS GIS Cut Line= 2
      3524577.28     10581328.52      3523459.66     10578702.67
#Sta/Elev= 30
  3765.6   492.6  3843.2  492.13  3990.4  487.78  4312.6  481.86  4725.2  481.34
  4841.7  481.41  4964.7  481.75  4970.1  480.69  4979.4  476.74  4988.3  470.63
  4998.2  466.81  5000.9  466.31  5004.2  466.81  5011.9  469.82  5017.4   470.5
  5022.9  473.51  5033.8  474.26  5064.6  473.08    5141  473.02  5251.8  474.81
  5383.8  473.34  5414.2  473.44  5492.2  476.45  5740.2  486.35  5817.5  488.29
  6267.9  497.43  6391.5  497.76  6420.6  496.56  6444.2  497.56  6619.4  495.74
#Mann= 9 ,-1 , 0
  3765.6     .05       0  4312.6      .1       0  4725.2     .05       0
  4841.7     .12       0  4998.2     .07       0  5004.2     .12       0
  5383.8     .16       0  5492.2      .1       0  5817.5     .16       0
Bank Sta=4998.2,5004.2
XS Rating Curve= 0 ,0
Exp/Cntr=0.3,0.1

Type RM Length L Ch R = 1 ,16430   ,1676,1676,1676
BEGIN DESCRIPTION:
GROVE ISLAND CREEK 5.0
END DESCRIPTION:
XS GIS Cut Line= 2
      3525503.95     10581039.95      3524046.42     10578367.81
#Sta/Elev= 30
  3070.1  481.43  3172.2   481.8  3550.2  478.39  3615.6  478.26    3793  479.25
  3895.5  477.27  3999.9  474.03  4053.2  475.43  4088.1  476.61  4152.7  477.21
  4307.9  474.57  4454.3  472.05  4735.6  474.26    4850  472.07  4980.5  471.27
  4986.2  470.53  4999.3   464.3    5002   463.8  5005.3   464.3  5024.1  473.02
  5141.3  484.74  5302.3  491.77  5574.7  494.94  5716.1     494  5767.8  490.57
  5781.6  492.15  5813.4  491.97  5863.3  495.16  5994.4  497.23  6113.9  498.07
#Mann= 12 ,-1 , 0
  3070.1     .05       0  3550.2     .16       0  3615.6     .05       0
  3895.5     .16       0  4053.2     .12       0  4088.1     .05       0
  4307.9     .16       0  4454.3     .05       0    4850     .16       0
  4999.3     .07       0  5005.3     .16       0  5994.4     .05       0
Bank Sta=4999.3,5005.3
XS Rating Curve= 0 ,0
Exp/Cntr=0.3,0.1

Type RM Length L Ch R = 1 ,14754   ,2312,2312,2312
BEGIN DESCRIPTION:
GROVE ISLAND CREEK 6.0
END DESCRIPTION:
XS GIS Cut Line= 2
      3526271.32     10580347.25       3525150.1     10578306.13
#Sta/Elev= 30
  3500.7  473.77    3549  474.18  3554.7  475.51  3647.7  475.37  4225.9  475.27
  4593.1  470.19  4930.8  469.75  4978.7   467.2  4984.4  465.41  4987.3   460.2
  4990.1   459.7  4993.3   460.2  5000.5  460.96  5013.1  467.07    5036   468.3
  5264.2  467.72  5470.2  470.88  5701.4  474.54  5720.5  475.13    5729   477.1
  5734.8  475.24  5750.8  479.81  5755.6  477.64  5772.6  480.62  5778.3  478.39
  5788.7  480.23  5794.4  477.54  5810.5   479.5  5816.2   477.3  5829.5  479.64
#Mann= 8 ,-1 , 0
  3500.7     .08       0  3647.7     .05       0  4930.8     .16       0
  4987.3     .07       0  4993.3     .16       0  5470.2     .12       0
  5701.4      .1       0  5755.6     .16       0
Bank Sta=4987.3,4993.3
XS Rating Curve= 0 ,0
Exp/Cntr=0.3,0.1

Type RM Length L Ch R = 1 ,12442   ,14,14,14
BEGIN DESCRIPTION:
GROVE ISLAND CREEK 7.01
END DESCRIPTION:
XS GIS Cut Line= 6
      3526411.17      10579588.5      3526653.34     10579276.02
       3527067.4     10578872.38      3527100.22     10578502.07
      3527049.87     10578267.69      3527072.43     10577755.22
#Sta/Elev= 30
  3451.3  472.78  3472.1  472.71    3505  472.34  3642.3  471.55  3745.8  471.36
  3812.4  471.33  3868.6  471.75  3926.7  472.18  3961.4  470.92  4003.6  470.27
  4105.1  470.01  4138.7  469.96  4188.3  470.96  4248.8  470.27  4273.7  470.26
  4392.5  469.02  4511.7  466.92  4777.5  461.92  4959.8  462.97  4971.4  462.64
  4996.7  459.05  4999.4  458.55  5002.7  459.05  5022.5  462.08    5206  463.12
    5254  464.35    5354  469.72  5402.2  468.78    5434  471.31  5550.4  475.58
#Mann= 20 ,-1 , 0
  3451.3      .1       0  3472.1     .08       0    3505     .05       0
  3642.3     .08       0  3745.8     .05       0  3812.4     .08       0
  3868.6     .05       0  3961.4     .08       0  4003.6     .05       0
  4105.1     .08       0  4138.7     .05       0  4248.8     .08       0
  4273.7     .05       0  4392.5     .08       0  4511.7     .05       0
  4959.8     .16       0  4996.7     .07       0  5002.7     .16       0
    5206     .05       0  5402.2     .08       0
Bank Sta=4996.7,5002.7
XS Rating Curve= 0 ,0
Exp/Cntr=0.3,0.1

Type RM Length L Ch R = 1 ,12428   ,57,57,57
BEGIN DESCRIPTION:
GROVE ISLAND CREEK 7.0
END DESCRIPTION:
XS GIS Cut Line= 6
      3526435.29      10579597.2       3526717.4     10579240.78
      3527085.46     10578888.35      3527113.24     10578506.41
      3527062.89     10578256.41      3527094.14     10577751.18
#Sta/Elev= 30
  3443.8  472.76  3507.5  472.24  3590.6  471.81  3750.1  471.39  3758.4  471.45
  3871.4  472.03  3922.1  471.49  4003.6  470.65  4065.3  470.13    4139  470.67
  4176.9  472.23  4208.6  470.87  4274.4  470.84  4350.3  469.28  4510.1  466.84
  4821.9  461.62  4951.5  462.85  4972.1  462.12  4987.7  458.82  4990.5  458.32
  4993.7  458.82  5017.1   460.4  5080.8  462.88    5138  462.54  5302.5  466.09
  5322.9  465.29  5405.6  470.07  5453.1  470.74  5473.1  472.75  5553.6  475.44
#Mann= 19 ,-1 , 0
  3443.8     .08       0  3507.5     .05       0  3590.6     .08       0
  3750.1     .05       0  3758.4     .08       0  3871.4     .05       0
  3922.1     .08       0  4003.6     .05       0  4065.3     .08       0
    4139     .05       0  4208.6     .08       0  4274.4     .05       0
  4350.3     .08       0  4510.1     .05       0  4987.7     .04       0
  4993.7     .05       0  5017.1     .16       0    5138     .05       0
  5405.6     .08       0
Bank Sta=4987.7,4993.7
XS Rating Curve= 0 ,0
Exp/Cntr=0.3,0.1

Type RM Length L Ch R = 1 ,12371   ,19,19,19
BEGIN DESCRIPTION:
GROVE ISLAND CREEK 8.0
END DESCRIPTION:
XS GIS Cut Line= 6
      3526531.72     10579611.58      3526673.65     10579387.61
      3527182.77     10578927.98      3527174.95     10578463.13
      3527125.48     10578258.71      3527206.82     10577755.66
#Sta/Elev= 30
  3414.4  472.45  3486.1     471  3590.7  470.25    3721  470.54  3754.6  470.86
  3862.8  471.22  3891.3  471.04  4004.7  470.65    4028  470.54  4146.6  470.25
    4228  468.96  4249.4  465.93  4365.6  465.15  4404.9  466.19  4502.9  466.77
  4699.5  461.86  4922.1  460.99  4959.6  462.44  5006.4  458.49  5009.1  457.99
  5012.4  458.49  5029.4  461.57  5039.9  462.05  5046.3   461.9  5210.2     461
  5260.4  466.07  5330.7  467.37  5448.2  472.06  5489.9  473.74  5554.5  474.01
#Mann= 18 ,-1 , 0
  3414.4     .16       0  3486.1     .08       0  3590.7     .05       0
    3721     .08       0  3754.6     .05       0  3862.8     .08       0
  3891.3     .05       0  4004.7     .08       0    4028     .05       0
  4146.6     .08       0  4404.9     .05       0  4502.9     .16       0
  4699.5     .05       0  5006.4     .04       0  5012.4     .05       0
  5039.9     .16       0  5046.3     .05       0  5448.2     .08       0
Bank Sta=5006.4,5012.4
XS Rating Curve= 0 ,0
Exp/Cntr=0.3,0.1

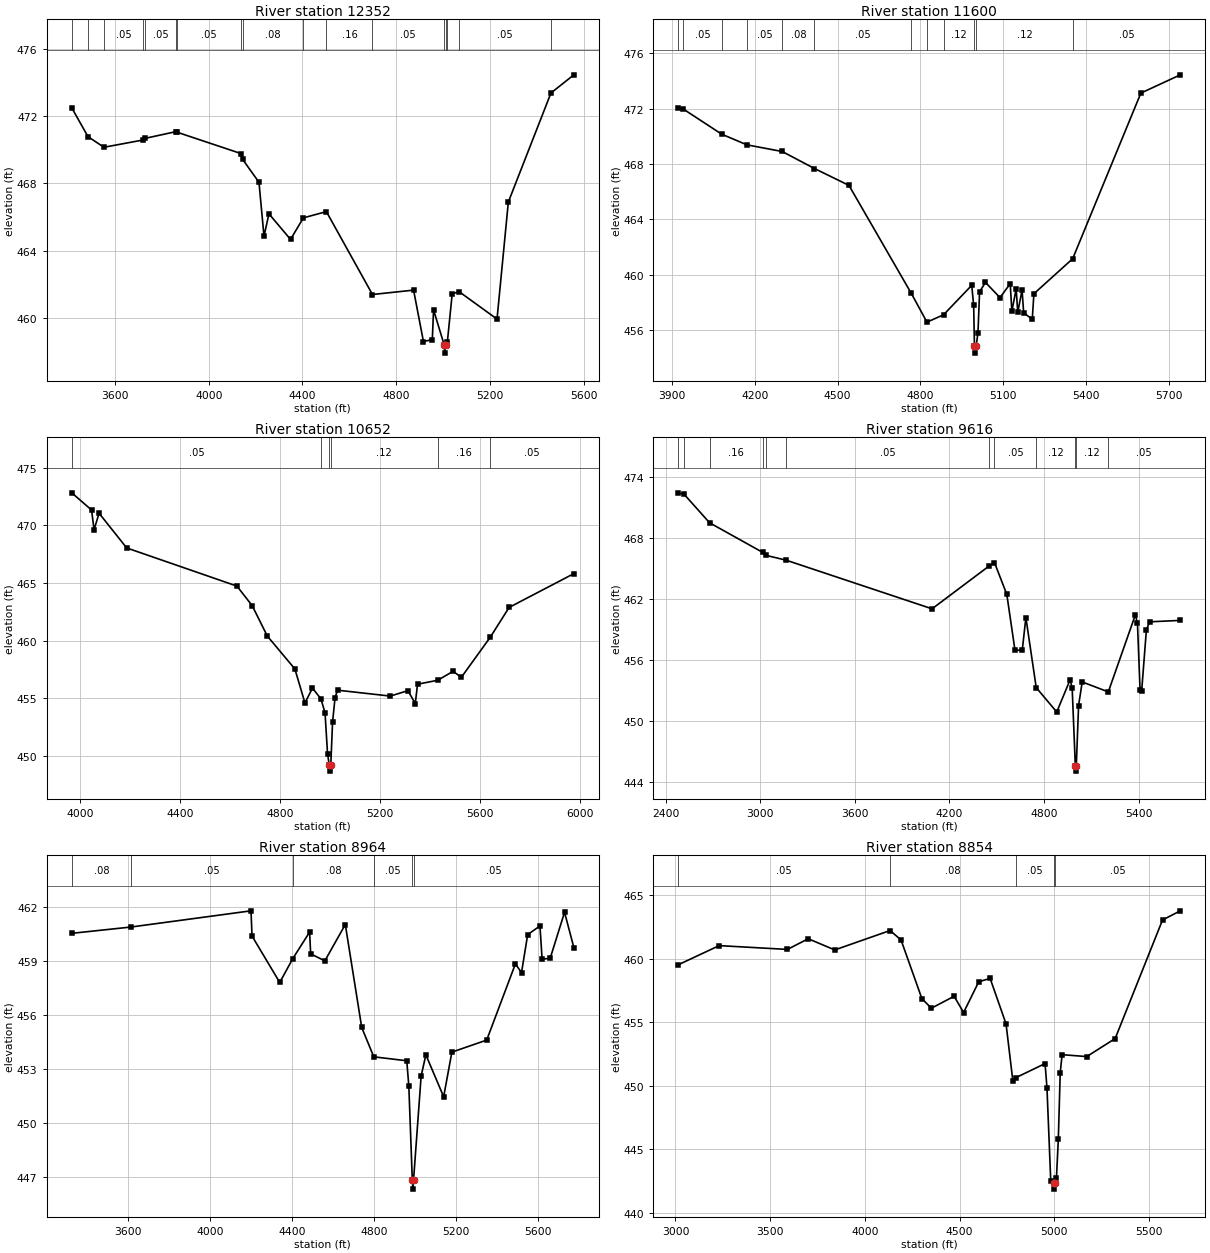
Type RM Length L Ch R = 1 ,12352   ,752,752,752
BEGIN DESCRIPTION:
GROVE ISLAND CREEK 8.01
END DESCRIPTION:
XS GIS Cut Line= 6
      3526551.28     10579610.24      3526693.18     10579386.31
       3527202.3     10578926.68      3527194.49     10578461.83
      3527145.01     10578257.41      3527227.03     10577752.22
#Sta/Elev= 30
  3415.6  472.48  3484.8  470.77    3553  470.14  3719.1  470.57  3728.8  470.67
    3861  471.07  3865.6  471.03    4139  469.76  4144.7  469.42  4214.4  468.06
  4235.8  464.86  4256.9  466.19    4349  464.67  4403.9  465.95    4502  466.32
  4698.6   461.4  4874.1  461.66  4916.1  458.61    4954  458.72  4959.3  460.49
  5004.4  458.42  5007.2  457.92  5010.4  458.42  5018.1  458.57  5038.9  461.45
  5069.2  461.56  5230.1  459.94  5278.4  466.89  5460.2  473.36  5557.9  474.44
#Mann= 17 ,-1 , 0
  3415.6     .16       0  3484.8     .08       0    3553     .05       0
  3719.1     .08       0  3728.8     .05       0    3861     .08       0
  3865.6     .05       0    4139     .16       0  4144.7     .08       0
  4403.9     .05       0    4502     .16       0  4698.6     .05       0
  5004.4     .04       0  5010.4     .05       0  5018.1     .16       0
  5069.2     .05       0  5460.2     .08       0
Bank Sta=5004.4,5010.4
XS Rating Curve= 0 ,0
Exp/Cntr=0.3,0.1

Type RM Length L Ch R = 1 ,11600   ,948,948,948
BEGIN DESCRIPTION:
GROVE ISLAND CREEK 9.0
END DESCRIPTION:
XS GIS Cut Line= 2
      3528305.29     10579445.02      3527374.74     10577882.53
#Sta/Elev= 30
  3922.5  472.04  3941.3  471.97    4080  470.16  4171.3  469.39    4299  468.91
  4415.9  467.68  4540.9  466.46  4766.6  458.66  4823.4  456.58  4883.5  457.11
  4985.6  459.24  4992.6  457.79  4995.4  454.84  4998.2  454.34  5001.4  454.84
  5008.2   455.8    5014  458.77  5035.4  459.45    5088  458.35    5125  459.36
  5130.9  457.36  5146.5  458.98  5152.3  457.29  5167.9   458.9  5173.7  457.25
  5204.9  456.79  5210.7  458.63  5351.2  461.16  5598.2  473.13  5741.1  474.45
#Mann= 12 ,-1 , 0
  3922.5      .1       0  3941.3     .05       0    4080      .1       0
  4171.3     .05       0    4299     .08       0  4415.9     .05       0
  4766.6     .16       0  4823.4     .05       0  4883.5     .12       0
  4995.4     .07       0  5001.4     .12       0  5351.2     .05       0
Bank Sta=4995.4,5001.4
XS Rating Curve= 0 ,0
Exp/Cntr=0.3,0.1

Type RM Length L Ch R = 1 ,10652   ,1036,1036,1036
BEGIN DESCRIPTION:
GROVE ISLAND CREEK 9.01
END DESCRIPTION:
XS GIS Cut Line= 3
      3528511.58     10579310.42      3528381.38     10577973.64
      3527766.08     10577717.99
#Sta/Elev= 30
    3967  472.82  4046.2  471.33  4056.2  469.62  4076.3  471.05  4186.8  468.04
    4628  464.73  4689.2  463.03  4749.5   460.4    4860  457.54  4900.2  454.59
  4930.3  455.88  4963.9  454.96  4980.6  453.74  4990.6   450.2  4997.6  449.18
  5000.4  448.68  5003.6  449.18  5010.7  452.91  5020.7  455.06  5030.8   455.7
  5241.8  455.19  5312.4  455.66  5341.8  454.54  5350.8  456.22  5431.4  456.56
  5493.4  457.34  5525.9  456.81  5642.1   460.3  5717.3  462.88  5976.4  465.81
#Mann= 6 ,-1 , 0
    3967     .05       0  4963.9     .12       0  4997.6     .07       0
  5003.6     .12       0  5431.4     .16       0  5642.1     .05       0
Bank Sta=4997.6,5003.6
XS Rating Curve= 0 ,0
Exp/Cntr=0.3,0.1

Type RM Length L Ch R = 1 ,9616    ,652,652,652
BEGIN DESCRIPTION:
GROVE ISLAND CREEK 14.0
END DESCRIPTION:
XS GIS Cut Line= 6
      3531248.96     10579074.42      3530576.19      10578245.4
      3529608.31     10578080.47      3529024.36     10577815.71
      3528975.77     10577724.74      3528586.81     10577707.82
#Sta/Elev= 30
  2480.6  472.49  2518.9  472.33  2679.4  469.54    3017  466.62    3036  466.34
  3166.5  465.85    4090  461.07  4450.4  465.27  4485.6  465.63    4564  462.49
  4615.6  457.01  4661.8  456.98  4684.9  460.21  4750.5  453.31  4880.6  450.91
  4965.1  454.08  4978.4  453.28  4998.5  445.59  5001.3  445.09  5004.5  445.59
  5019.1  451.55    5042  453.87  5207.5  452.89  5378.7  460.46  5392.3  459.69
  5408.8  453.12  5418.8  452.93  5448.8  458.96  5468.8  459.79  5664.1  459.93
#Mann= 12 ,-1 , 0
  2480.6     .05       0  2518.9     .12       0  2679.4     .16       0
    3017     .12       0    3036     .16       0  3166.5     .05       0
  4450.4     .16       0  4485.6     .05       0  4750.5     .12       0
  4998.5     .07       0  5004.5     .12       0  5207.5     .05       0
Bank Sta=4998.5,5004.5
XS Rating Curve= 0 ,0
Exp/Cntr=0.3,0.1

Type RM Length L Ch R = 1 ,8964    ,110,110,110
BEGIN DESCRIPTION:
GROVE ISLAND CREEK 10.0
END DESCRIPTION:
XS GIS Cut Line= 2
      3531037.21     10577777.79      3528586.75       10577691.
#Sta/Elev= 30
  3324.4  460.51  3613.4  460.86  4199.7  461.76  4204.7  460.36  4340.1  457.78
    4404  459.11    4486  460.58  4491.1  459.37  4560.3  458.98  4660.3     461
  4740.4  455.28  4799.4  453.65  4960.5  453.43  4970.5  452.02  4987.5   446.8
  4990.3   446.3  4993.5   446.8  5030.6  452.58  5053.7  453.76  5140.6  451.43
  5180.7  453.91  5350.8  454.58  5490.9  458.81  5520.9  458.33  5550.9  460.44
  5610.9  460.92  5621.4  459.07    5661  459.13    5731  461.68  5776.4  459.72
#Mann= 6 ,-1 , 0
  3324.4     .08       0  3613.4     .05       0    4404     .08       0
  4799.4     .05       0  4987.5     .04       0  4993.5     .05       0
Bank Sta=4987.5,4993.5
XS Rating Curve= 0 ,0
Exp/Cntr=0.3,0.1

Type RM Length L Ch R = 1 ,8854    ,41,41,41
BEGIN DESCRIPTION:
GROVE ISLAND CREEK 11.0
END DESCRIPTION:
XS GIS Cut Line= 2
      3531348.24     10577671.02      3528698.25     10577587.69
#Sta/Elev= 30
  3014.6  459.53  3230.8  461.04    3591  460.74  3701.1  461.58  3841.1   460.7
  4133.6  462.23  4191.3  461.48  4301.4  456.86  4351.4  456.11  4471.5  457.05
  4521.5  455.77  4601.5  458.19  4661.5  458.46  4745.6  454.88  4781.6  450.39
  4796.2  450.63  4951.7  451.75  4961.7  449.85  4981.7  442.51  4998.7  442.36
  5001.5  441.86  5004.7  442.36  5011.7   442.7  5021.7  445.79  5031.7  451.01
  5041.7  452.45  5171.8   452.3  5321.9  453.72    5572  463.06  5665.9  463.78
#Mann= 5 ,-1 , 0
  3014.6     .05       0  4133.6     .08       0  4796.2     .05       0
  4998.7     .04       0  5004.7     .05       0
Bank Sta=4998.7,5004.7
XS Rating Curve= 0 ,0
Exp/Cntr=0.3,0.1

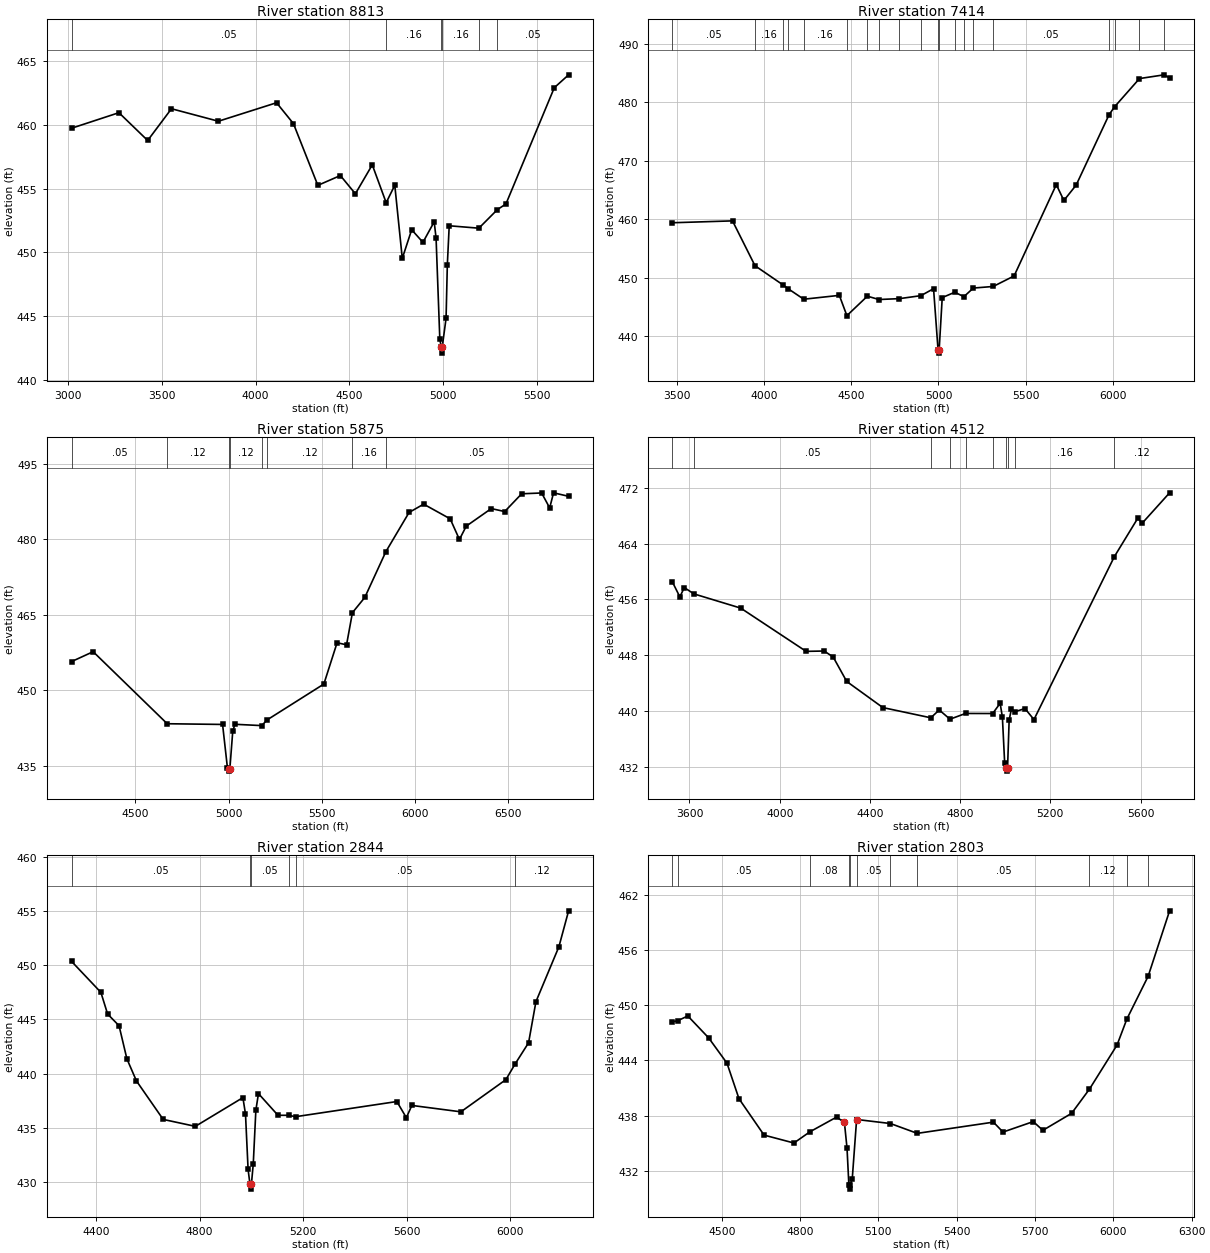
Type RM Length L Ch R = 1 ,8813    ,1399,1399,1399
BEGIN DESCRIPTION:
GROVE ISLAND CREEK 11.01
END DESCRIPTION:
XS GIS Cut Line= 2
      3531344.68     10577629.35      3528695.89     10577546.05
#Sta/Elev= 30
  3018.6  459.73  3271.3  460.95  3424.6  458.77  3551.4  461.26  3801.6  460.28
  4111.7  461.73  4201.8  460.09  4331.8  455.25  4451.9  456.02  4531.9  454.59
    4622  456.86  4696.1  453.89    4742  455.26    4782  449.52  4832.1  451.77
  4892.1  450.78  4952.1  452.39  4962.1  451.12  4982.1  443.19  4989.2  442.59
  4991.9  442.09  4995.2  442.59  5015.4  444.82  5022.2  449.03  5032.2  452.08
  5190.3  451.89  5289.1  453.35  5334.6  453.79  5592.4  462.91  5668.7  463.92
#Mann= 6 ,-1 , 0
  3018.6     .05       0  4696.1     .16       0  4989.2     .03       0
  4995.2     .16       0  5190.3     .12       0  5289.1     .05       0
Bank Sta=4989.2,4995.2
XS Rating Curve= 0 ,0
Exp/Cntr=0.3,0.1

Type RM Length L Ch R = 1 ,7414    ,1539,1539,1539
BEGIN DESCRIPTION:
GROVE ISLAND CREEK 12.0
END DESCRIPTION:
XS GIS Cut Line= 2
       3531368.4      10577578.8      3529118.35     10575823.56
#Sta/Elev= 30
    3473  459.38  3817.5   459.7  3946.6  452.03  4104.9   448.8  4138.2  448.07
  4226.6   446.3  4430.8  446.96  4474.1  443.49  4591.7  446.82  4658.3  446.25
    4776   446.4  4899.1  446.91  4971.7   448.1  4997.7  437.58  5000.4  437.08
  5003.7  437.58  5021.5  446.58  5093.3  447.49    5146  446.74  5200.1  448.21
    5314  448.48  5434.1  450.28  5676.4   465.9  5719.8  463.19  5790.4  465.82
  5979.5  477.87  6011.7  479.24  6153.9  484.04  6295.3  484.68  6326.7  484.14
#Mann= 20 ,-1 , 0
    3473     .05       0  3946.6     .16       0  4104.9     .05       0
  4138.2     .12       0  4226.6     .16       0  4474.1     .12       0
  4591.7     .16       0  4658.3     .12       0    4776     .16       0
  4899.1     .12       0  4997.7     .07       0  5003.7     .12       0
  5093.3     .16       0    5146     .05       0  5200.1     .16       0
    5314     .05       0  5979.5     .12       0  6011.7     .05       0
  6153.9     .16       0  6295.3     .12       0
Bank Sta=4997.7,5003.7
XS Rating Curve= 0 ,0
Exp/Cntr=0.3,0.1

Type RM Length L Ch R = 1 ,5875    ,1363,1363,1363
BEGIN DESCRIPTION:
GROVE ISLAND CREEK 13.0
END DESCRIPTION:
XS GIS Cut Line= 3
      3531774.63     10577386.08      3531482.96     10575693.37
      3530885.17     10574955.23
#Sta/Elev= 30
  4156.9  455.71    4273  457.68  4670.4  443.36  4967.5  443.22  4993.5  434.61
  5000.6  434.44  5003.4  433.94  5006.6  434.44  5022.3  441.93  5034.1  443.25
  5177.1  442.99  5208.1  444.16    5511  451.25    5582  459.46  5632.8  459.05
  5664.3  465.44  5730.8  468.47  5843.7  477.56  5968.3  485.36  6046.6  487.01
  6188.9  484.09  6238.5  479.99  6275.2  482.64  6409.5  486.13  6481.4  485.54
  6572.6  489.07  6679.7  489.23  6722.8  486.26  6743.6  489.26  6824.4  488.57
#Mann= 8 ,-1 , 0
  4156.9     .05       0  4670.4     .12       0  5000.6     .07       0
  5006.6     .12       0  5177.1     .16       0  5208.1     .12       0
  5664.3     .16       0  5843.7     .05       0
Bank Sta=5000.6,5006.6
XS Rating Curve= 0 ,0
Exp/Cntr=0.3,0.1

Type RM Length L Ch R = 1 ,4512    ,1668,1668,1668
BEGIN DESCRIPTION:
GROVE ISLAND CREEK 15.0
END DESCRIPTION:
XS GIS Cut Line= 2
      3532834.36      10577784.1      3532802.57     10575580.43
#Sta/Elev= 30
  3524.7  458.48  3557.2  456.38  3577.2   457.7  3619.7   456.8  3827.2  454.77
  4117.2  448.59  4197.2  448.64  4237.2  447.78  4297.2  444.29  4457.3  440.56
    4670   439.1  4707.3  440.22    4755   438.9    4824  439.72  4944.2  439.71
  4977.3  441.17  4987.3  439.22  4997.3  432.71  5004.3  431.98  5007.1  431.48
  5010.3  431.98  5017.3  438.78  5027.3  440.34  5042.4  439.96  5087.3  440.42
  5127.3  438.85  5483.7  462.12  5587.4   467.6  5607.4  466.91  5728.6  471.24
#Mann= 10 ,-1 , 0
  3524.7     .08       0  3619.7     .05       0    4670     .16       0
    4755     .05       0    4824     .16       0  4944.2     .12       0
  5004.3     .07       0  5010.3     .12       0  5042.4     .16       0
  5483.7     .12       0
Bank Sta=5004.3,5010.3
XS Rating Curve= 0 ,0
Exp/Cntr=0.3,0.1

Type RM Length L Ch R = 1 ,2844    ,41,41,41
BEGIN DESCRIPTION:
GROVE ISLAND CREEK 17.03
END DESCRIPTION:
XS GIS Cut Line= 6
      3534074.59     10577514.45      3534100.63      10577223.7
      3534011.66     10577006.69      3534009.49     10576796.19
      3533840.21      10576323.1      3534193.93     10575750.21
#Sta/Elev= 30
    4306  450.36  4419.3   447.5  4445.3   445.5  4489.5  444.42  4519.7  441.37
  4556.6  439.33  4659.8  435.78  4783.9  435.14  4967.5  437.79  4977.5  436.27
  4987.5  431.17  4994.5  429.85  4997.3  429.35  5000.5  429.85  5007.5  431.69
  5017.5  436.63  5027.5  438.16  5102.9  436.16  5143.7  436.16  5170.7  436.03
  5561.7  437.43  5598.3  435.94  5619.6  437.07  5808.8  436.48  5982.6  439.45
  6017.5  440.87  6070.1  442.85  6098.5  446.64  6187.2  451.71  6224.6  455.02
#Mann= 6 ,-1 , 0
    4306     .05       0  4994.5     .03       0  5000.5     .05       0
  5143.7     .08       0  5170.7     .05       0  6017.5     .12       0
Bank Sta=4994.5,5000.5
XS Rating Curve= 0 ,0
Exp/Cntr=0.3,0.1

Type RM Length L Ch R = 1 ,2803    ,65,65,65
BEGIN DESCRIPTION:
GROVE ISLAND CREEK 17.0
END DESCRIPTION:
XS GIS Cut Line= 6
      3534118.71     10577520.19      3534128.48     10577222.62
      3534050.36     10576823.31      3533920.15     10576520.58
      3533897.36     10576369.75      3534270.63      10575762.1
#Sta/Elev= 30
  4311.1  448.22  4331.3  448.33  4369.7  448.85  4449.7  446.46  4519.8  443.71
  4565.8  439.84  4661.9  435.88  4776.3  435.02  4837.6  436.24  4939.7  437.84
  4969.7  437.26  4979.7  434.46  4986.7   430.5  4989.5     430  4992.7   430.5
  4999.8  431.15  5016.4  437.57  5019.7  437.57    5146  437.14  5248.9  436.07
  5540.5  437.29  5577.3  436.21  5693.2  437.35    5730   436.4  5840.1  438.25
  5908.6  440.89  6014.1  445.68  6051.9  448.52  6133.3  453.17  6215.4  460.29
#Mann= 11 ,-1 , 0
  4311.1     .08       0  4331.3     .05       0  4837.6     .08       0
  4986.7     .07       0  4992.7     .08       0  5019.7     .05       0
    5146     .08       0  5248.9     .05       0  5908.6     .12       0
  6051.9      .1       0  6133.3     .12       0
Bank Sta=4969.7,5016.4
XS Rating Curve= 0 ,0
Exp/Cntr=0.3,0.1

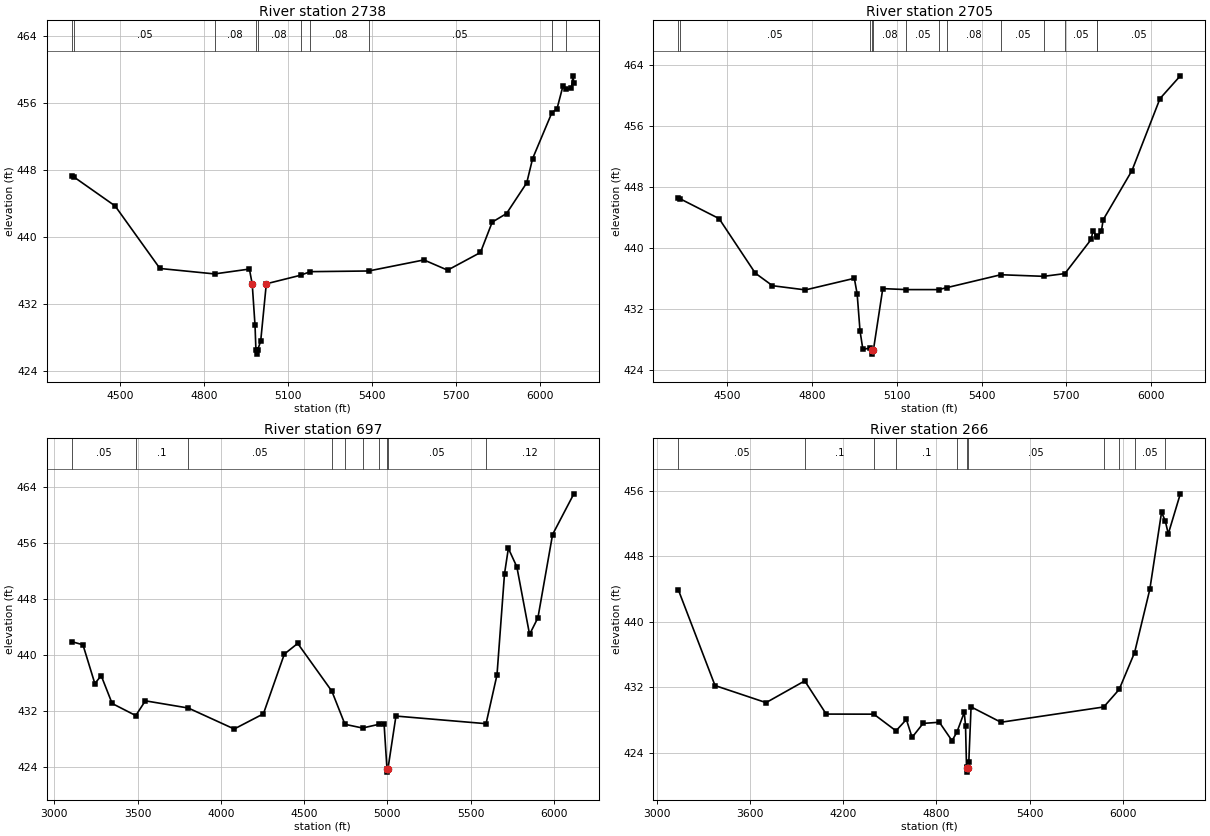
Type RM Length L Ch R = 1 ,2738    ,33,33,33
BEGIN DESCRIPTION:
GROVE ISLAND CREEK 17.01
END DESCRIPTION:
XS GIS Cut Line= 6
      3534174.42     10577506.24       3534188.3     10577186.81
      3534139.69     10577047.92      3534109.31     10576787.51
      3533946.55     10576396.88      3534299.82      10575865.9
#Sta/Elev= 30
  4328.7  447.22  4337.5  447.09  4483.4  443.66  4643.5  436.19  4838.4  435.54
    4963  436.12  4973.1  434.33  4983.1  429.39  4986.3  426.46  4989.1  425.96
  4992.3  426.46  5003.3   427.5  5023.4  434.36  5145.6  435.38  5180.3  435.81
  5388.6  435.89  5586.2  437.21  5670.8  435.99  5788.1   438.1  5830.1  441.73
  5881.2  442.75  5953.4  446.42  5974.4  449.32  6043.1  454.79  6061.6  455.28
  6082.6  457.97  6093.8  457.61  6112.7   457.7  6118.7   459.2  6121.6  458.33
#Mann= 10 ,-1 , 0
  4328.7     .08       0  4337.5     .05       0  4838.4     .08       0
  4986.3     .07       0  4992.3     .08       0  5145.6     .05       0
  5180.3     .08       0  5388.6     .05       0  6043.1      .1       0
  6093.8     .05       0
Bank Sta=4973.1,5023.4
XS Rating Curve= 0 ,0
Exp/Cntr=0.3,0.1

Type RM Length L Ch R = 1 ,2705    ,2008,2008,2008
BEGIN DESCRIPTION:
GROVE ISLAND CREEK 17.02
END DESCRIPTION:
XS GIS Cut Line= 6
      3534209.14     10577503.64       3534226.5     10577195.49
      3534135.35     10576726.74      3533989.95     10576455.47
      3533998.63     10576390.37      3534339.33     10575880.41
#Sta/Elev= 30
  4327.3  446.48  4332.2  446.47  4471.7  443.84  4599.7  436.69  4660.6  435.04
  4777.2  434.49    4950  436.01    4960  433.96  4970.1  429.12  4980.2  426.69
    5005  426.86  5011.3  426.57    5014  426.07  5017.3  426.57  5050.6  434.66
    5134  434.53  5247.7  434.53  5277.3  434.79  5468.2  436.48  5619.8  436.27
  5694.5  436.63  5787.6  441.12  5793.6  442.21  5809.1  441.44  5809.4   441.5
  5823.6  442.15  5829.7  443.67  5931.8  450.14  6030.9  459.58  6102.7  462.56
#Mann= 13 ,-1 , 0
  4327.3     .08       0  4332.2     .05       0    5005     .08       0
  5011.3     .03       0  5017.3     .08       0    5134     .05       0
  5247.7     .16       0  5277.3     .08       0  5468.2     .05       0
  5619.8     .12       0  5694.5     .05       0  5809.1     .12       0
  5809.4     .05       0
Bank Sta=5011.3,5017.3
XS Rating Curve= 0 ,0
Exp/Cntr=0.3,0.1

Type RM Length L Ch R = 1 ,697     ,431,431,431
BEGIN DESCRIPTION:
GROVE ISLAND CREEK 16.0
END DESCRIPTION:
XS GIS Cut Line= 6
      3534293.58     10577302.21      3534317.33     10577287.93
      3535431.91     10576688.97      3535619.41     10576298.35
      3535575.14     10576053.56      3534557.05     10575842.65
#Sta/Elev= 30
  3104.8  441.91  3171.9  441.47  3243.3  435.92  3281.5  437.05  3347.2  433.07
  3489.1  431.34  3546.6  433.45  3804.4  432.42  4080.2  429.42  4255.5  431.59
  4381.3  440.14  4461.5  441.66  4666.5  434.83  4745.1  430.09  4850.6  429.56
    4951   430.1  4980.2  430.09  4997.5  423.75  5000.3  423.25  5003.5  423.75
  5051.4  431.27  5592.4  430.18  5658.1  437.15  5703.2  451.61  5726.4  455.26
  5777.4  452.61  5853.7  442.95  5903.9  445.33  5991.9  457.24  6119.6  463.06
#Mann= 10 ,-1 , 0
  3104.8     .05       0  3489.1      .1       0  3804.4     .05       0
  4666.5      .1       0  4745.1     .05       0  4850.6      .1       0
    4951     .05       0  4997.5     .03       0  5003.5     .05       0
  5592.4     .12       0
Bank Sta=4997.5,5003.5
XS Rating Curve= 0 ,0
Exp/Cntr=0.3,0.1

Type RM Length L Ch R = 1 ,266     ,0,0,0
BEGIN DESCRIPTION:
GROVE ISLAND CREEK 16.01
END DESCRIPTION:
XS GIS Cut Line= 4
      3535057.99     10577378.29      3536047.56      10576019.8
       3535674.3     10575746.36      3534595.33     10575612.03
#Sta/Elev= 30
  3139.4  443.95  3376.1  432.21  3704.5  430.12  3953.5  432.78  4091.5  428.72
    4398  428.71  4540.6  426.67  4607.5  428.06    4644  425.87    4715  427.58
  4819.7  427.72  4901.2  425.46  4932.7  426.52  4979.8  428.93    4988  427.31
  4994.4  422.26  4997.6  422.12  5000.4  421.62  5003.6  422.12  5009.1  422.85
  5023.7   429.6    5216  427.72  5877.4  429.59  5976.6  431.73  6075.8  436.24
  6173.9  443.98  6249.6  453.43  6274.1  452.28  6292.7  450.76  6370.1  455.66
#Mann= 11 ,-1 , 0
  3139.4     .05       0  3953.5      .1       0    4398     .05       0
  4540.6      .1       0  4932.7     .05       0  4997.6     .03       0
  5003.6     .05       0  5877.4     .12       0  5976.6      .1       0
  6075.8     .05       0  6274.1      .1       0
Bank Sta=4997.6,5003.6
XS Rating Curve= 0 ,0
Exp/Cntr=0.3,0.1

Chan Stop Cuts=-1
Use User Specified Reach Order=0
Composite Channel Slope=5