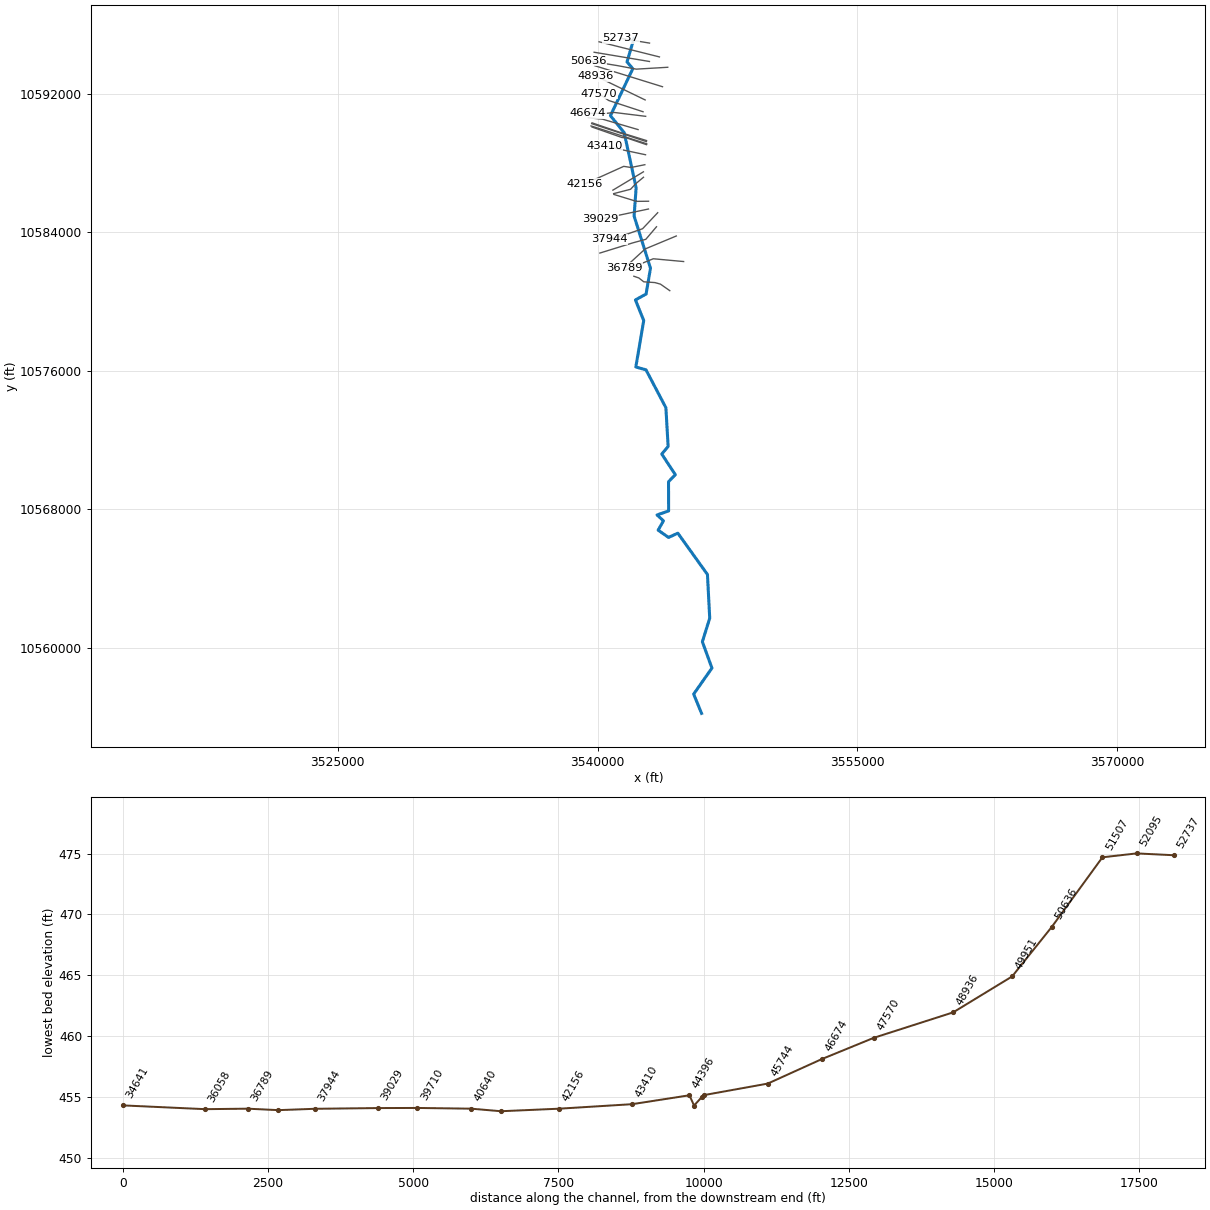
--- HOLMAN CREEK.prj (project) ---

Proj Title=HOLMAN CREEK Base Level Engineering
Current Plan=p01
Default Exp/Contr=0.3,0.1
English Units
Geom File=g01
Flow File=f01
Plan File=p01
Y Axis Title=Elevation
X Axis Title(PF)=Main Channel Distance
X Axis Title(XS)=Station
BEGIN DESCRIPTION:
HOLMAN CREEK
END DESCRIPTION:
DSS Export Rating Curves= 0
DSS Export Rating Curve Sorted= 0
DSS Export Volume Flow Curves= 0
DXF OffsetX= 0
DXF OffsetY= 0
DXF ScaleX= 1
DXF ScaleY= 10

--- HOLMAN CREEK.p01 (plan) ---

Plan Title=Multiple Run
Short Identifier=Multiple
Geom File=g01
Flow File=f01
Subcritical Flow
K Sum by GR= 0
Std Step Tol= 0.01
Critical Tol= 0.01
Num of Std Step Trials= 20
Max Error Tol= 0.3
Flow Tol Ratio= 0.001
Split Flow NTrial= 30
Split Flow Tol= 0.02
Split Flow Ratio= 0.02
Log Output Level= 0
Friction Slope Method= 1
Unsteady Friction Slope Method= 2
Unsteady Bridges Friction Slope Method= 1
Parabolic Critical Depth
Global Vel Dist=  1 , 1 , 1
Global Log Level= 0
CheckData=True
Encroach Param= -1, 0, 0, 0
BEGIN DESCRIPTION:
Multiple Run
END DESCRIPTION:

--- HOLMAN CREEK.f01 (steady flow) ---

Flow Title=Multiple
Program Version=4.10
Number of Profiles= 7
Profile Names=10-year,25-year,50-year,1pct_min,100-year,1pct_plu,500-year
River Rch & RM=HOLMAN CREEK,Reach-1         ,52737
     893    1212    1471    1303    1762    2383    2520
River Rch & RM=HOLMAN CREEK,Reach-1         ,50636
    1417    1961    2412    2160    2921    3950    4272
River Rch & RM=HOLMAN CREEK,Reach-1         ,44476
    1500    2081    2564    2299    3110    4205    4563
River Rch & RM=HOLMAN CREEK,Reach-1         ,42156
    2560    3629    4534    4116    5566    7527    8370
River Rch & RM=HOLMAN CREEK,Reach-1         ,37944
    2637    3738    4671    4239    5732    7752    8618
River Rch & RM=HOLMAN CREEK,Reach-1         ,36789
    2884    4101    5133    4666    6311    8534    9518
River Rch & RM=HOLMAN CREEK,Reach-1         ,34050
    2899    4120    5156    4685    6336    8569    9551
River Rch & RM=HOLMAN CREEK,Reach-1         ,33665
    3081    4398    5521    5032    6805    9204   10320
River Rch & RM=HOLMAN CREEK,Reach-1         ,30842
    3443    4926    6192    5648    7639   10330   11603
River Rch & RM=HOLMAN CREEK,Reach-1         ,16523
    7375   10731   13644   12559   16985   22970   26263
River Rch & RM=HOLMAN CREEK,Reach-1         ,12525
    8664   12662   16149   14908   20161   27265   31345
River Rch & RM=HOLMAN CREEK,Reach-1         ,9592
    8630   12597   16053   14806   20024   27080   31079
River Rch & RM=HOLMAN CREEK,Reach-1         ,7573
   10849   15920   20363   18845   25485   34466   39809
Boundary for River Rch & Prof#=HOLMAN CREEK,Reach-1         , 1
Up Type= 0
Dn Type= 1
Dn Known WS=397.08
Boundary for River Rch & Prof#=HOLMAN CREEK,Reach-1         , 2
Up Type= 0
Dn Type= 1
Dn Known WS=398.53
Boundary for River Rch & Prof#=HOLMAN CREEK,Reach-1         , 3
Up Type= 0
Dn Type= 1
Dn Known WS=399.75
Boundary for River Rch & Prof#=HOLMAN CREEK,Reach-1         , 4
Up Type= 0
Dn Type= 1
Dn Known WS=399.34
Boundary for River Rch & Prof#=HOLMAN CREEK,Reach-1         , 5
Up Type= 0
Dn Type= 1
Dn Known WS=401.08
Boundary for River Rch & Prof#=HOLMAN CREEK,Reach-1         , 6
Up Type= 0
Dn Type= 1
Dn Known WS=403.1
Boundary for River Rch & Prof#=HOLMAN CREEK,Reach-1         , 7
Up Type= 0
Dn Type= 1
Dn Known WS=404.22
DSS Import GetInterval= 0
DSS Import GetPeak= 0
DSS Import FillOption= 0

--- HOLMAN CREEK.g01 (geometry) ---

Geom Title=Existing Conditions
Program Version=4.10

River Reach=HOLMAN CREEK    ,Reach-1
Reach XY= 30
      3542101.13     10595211.36      3541697.19     10593851.95
      3542030.98     10593457.09        3540739.     10590741.24
      3541532.97      10589766.5      3542222.78     10586573.62
      3542105.88     10584945.14      3543052.11     10581931.64
      3542798.99     10580438.12      3542182.28     10580096.75
      3542662.32     10578907.51       3542205.6       10576223.
      3542793.88     10576058.17      3543941.49     10573871.08
      3544071.11     10571632.05      3543703.24     10571193.36
      3544486.32     10570001.64      3544093.81     10569596.11
      3544099.43     10567907.42      3543431.18     10567675.25
      3543801.74     10567336.57      3543493.84     10566797.47
      3544093.37     10566376.21      3544631.86     10566621.99
      3546340.94     10564236.12      3546472.12     10561711.87
      3546047.49     10560349.42      3546599.53     10558827.31
      3545544.05     10557325.47      3546002.11     10556211.64

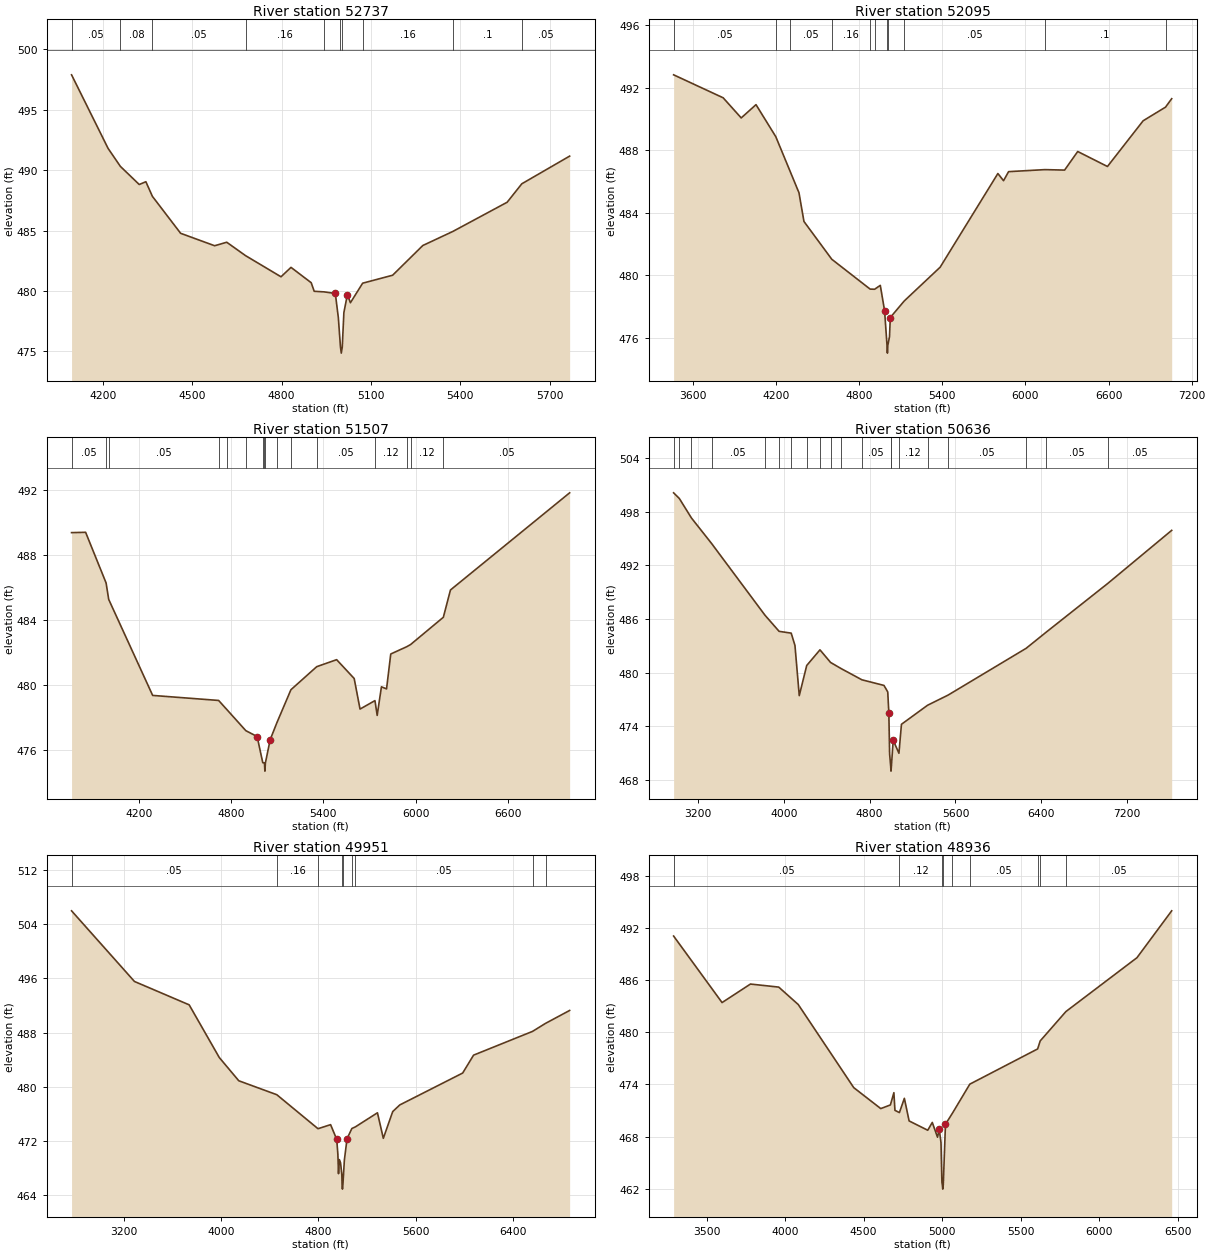
Type RM Length L Ch R = 1 ,52737   ,642,642,642
BEGIN DESCRIPTION:
HOLMAN CREEK 74.0
END DESCRIPTION:
XS GIS Cut Line= 2
      3542996.44     10594936.27      3541345.43     10595210.28
#Sta/Elev= 30
    4094   497.9  4216.7  491.81    4258  490.32  4321.4  488.82  4343.7  489.05
  4365.6  487.84  4460.5  484.78  4574.8  483.75  4615.4  484.04  4678.7  482.93
  4797.8  481.18  4831.3  481.96  4899.2  480.69  4909.3  479.98  4942.6  479.93
  4980.3   479.8  4990.4   477.8  4997.6  475.36  5000.3  474.86  5003.6  475.36
    5009  478.21  5020.8   479.7    5031  479.03  5072.1  480.65  5172.9  481.31
  5274.3  483.77  5374.9  484.93  5557.6  487.35    5607  488.88  5767.6  491.17
#Mann= 10 ,-1 , 0
    4094     .05       0    4258     .08       0  4365.6     .05       0
  4678.7     .16       0  4942.6     .12       0  4997.6     .07       0
  5003.6     .12       0  5072.1     .16       0  5374.9      .1       0
    5607     .05       0
Bank Sta=4980.3,5020.8
XS Rating Curve= 0 ,0
Exp/Cntr=0.3,0.1

Type RM Length L Ch R = 1 ,52095   ,588,588,588
BEGIN DESCRIPTION:
HOLMAN CREEK 72.0
END DESCRIPTION:
XS GIS Cut Line= 2
      3543568.71      10594137.5      3540082.55     10595012.51
#Sta/Elev= 30
  3461.1  492.83  3818.5  491.36  3948.9  490.07  4055.6  490.92  4198.4  488.87
  4301.4  486.66  4365.7  485.28  4401.7  483.44  4602.5  481.02  4879.1  479.11
  4911.7   479.1  4952.6  479.35  4983.5  477.73  5001.1  475.51  5003.9  475.01
  5007.1  475.51  5019.1  476.07  5024.7  477.29  5125.4  478.35  5384.3  480.51
  5801.1  486.51  5842.2  486.05  5878.2  486.63  6140.1  486.76  6282.6  486.73
  6377.3  487.92  6591.9  486.96  6849.7  489.89  7010.9  490.76  7055.4   491.3
#Mann= 11 ,-1 , 0
  3461.1     .05       0  4198.4     .08       0  4301.4     .05       0
  4602.5     .16       0  4879.1     .12       0  4911.7     .16       0
  5001.1     .07       0  5007.1     .16       0  5125.4     .05       0
  6140.1      .1       0  7010.9     .16       0
Bank Sta=4983.5,5024.7
XS Rating Curve= 0 ,0
Exp/Cntr=0.3,0.1

Type RM Length L Ch R = 1 ,51507   ,871,871,871
BEGIN DESCRIPTION:
HOLMAN CREEK 71.0
END DESCRIPTION:
XS GIS Cut Line= 2
      3542992.28     10593873.62      3539797.83     10594408.34
#Sta/Elev= 30
  3762.7  489.37  3854.1  489.39  3987.3  486.27  4004.2  485.26  4290.1  479.35
    4719  479.04  4774.4  478.46    4896  477.18  4969.4  476.82  5006.1  475.21
  5017.1  475.19  5019.9  474.69  5023.1  475.19  5054.3  476.63  5097.9  477.67
  5189.2   479.7  5357.1  481.12  5486.5  481.55  5600.6  480.39  5638.6  478.51
  5735.7  479.03  5750.1  478.12  5777.7  479.88    5811  479.75  5838.4   481.9
  5942.9  482.35  5967.1  482.48  6180.3  484.16  6226.7  485.84  7001.6  491.82
#Mann= 16 ,-1 , 0
  3762.7     .05       0  3987.3     .08       0  4004.2     .05       0
    4719     .16       0  4774.4     .05       0    4896      .1       0
  5006.1     .16       0  5017.1     .07       0  5023.1     .16       0
  5097.9     .05       0  5189.2     .16       0  5357.1     .05       0
  5735.7     .12       0  5942.9     .05       0  5967.1     .12       0
  6180.3     .05       0
Bank Sta=4969.4,5054.3
XS Rating Curve= 0 ,0
Exp/Cntr=0.3,0.1

Type RM Length L Ch R = 1 ,50636   ,685,685,685
BEGIN DESCRIPTION:
HOLMAN CREEK 70.0
END DESCRIPTION:
XS GIS Cut Line= 4
      3544050.27     10593539.74      3542231.71     10593431.23
       3541120.6     10593639.57      3539455.53     10593908.41
#Sta/Elev= 30
  2974.7  500.12  3028.3  499.48  3140.4  497.31  3328.4  494.45  3825.4  486.43
  3957.3  484.62  4069.8  484.42  4104.9  483.04  4144.9  477.43  4214.4   480.8
  4337.7  482.55  4436.6  481.14  4535.4  480.45  4728.2   479.2  4933.9  478.57
  4969.1  477.84  4979.2   475.5  4986.5  470.91  4996.6  469.48  4999.3  468.98
  5002.6  469.48  5019.9  472.43  5073.3  470.98  5096.7  474.22  5339.8  476.35
  5531.4  477.49  6257.9  482.72  6440.8  484.49  7019.3  489.99  7613.6  495.92
#Mann= 20 ,-1 , 0
  2974.7     .16       0  3028.3     .12       0  3140.4     .16       0
  3328.4     .05       0  3825.4     .16       0  3957.3     .05       0
  4069.8     .16       0  4214.4     .05       0  4337.7     .12       0
  4436.6      .1       0  4535.4     .05       0  4728.2     .05       0
  4996.6     .07       0  5002.6     .16       0  5073.3     .12       0
  5339.8     .05       0  5531.4     .05       0  6257.9      .1       0
  6440.8     .05       0  7019.3     .05       0
Bank Sta=4979.2,5019.9
XS Rating Curve= 0 ,0
Exp/Cntr=0.3,0.1

Type RM Length L Ch R = 1 ,49951   ,1015,1015,1015
BEGIN DESCRIPTION:
HOLMAN CREEK 69.0
END DESCRIPTION:
XS GIS Cut Line= 2
      3543746.43     10592415.62      3539831.51      10593630.9
#Sta/Elev= 30
  2768.9  505.99  3286.5  495.56  3736.7  492.11  3984.7  484.33  4145.1   480.9
  4458.1  478.84  4797.2  473.82  4900.8  474.42  4951.3  472.24  4960.7  470.03
  4965.9  467.18  4972.3  469.26  4982.7   468.8  4993.2  467.05  4995.5   465.4
  4998.3   464.9  5001.5   465.4  5014.2   469.2  5036.3  472.35  5075.8  473.85
  5103.7  474.08  5286.4  476.17  5334.7   472.4    5412  476.35  5470.2  477.33
  5987.9  482.04  6077.4  484.68  6562.8  488.19  6669.5  489.37  6868.1  491.28
#Mann= 9 ,-1 , 0
  2768.9     .05       0  4458.1     .16       0  4797.2     .12       0
  4995.5     .07       0  5001.5     .12       0  5075.8     .16       0
  5103.7     .05       0  6562.8      .1       0  6669.5     .05       0
Bank Sta=4951.3,5036.3
XS Rating Curve= 0 ,0
Exp/Cntr=0.3,0.1

Type RM Length L Ch R = 1 ,48936   ,1366,1366,1366
BEGIN DESCRIPTION:
HOLMAN CREEK 67.0
END DESCRIPTION:
XS GIS Cut Line= 2
      3542744.37     10591652.09      3539890.23     10593034.03
#Sta/Elev= 30
  3290.2  491.05  3598.6   483.4  3779.3  485.53  3959.4  485.18    4084  483.17
  4437.1  473.62    4609  471.21  4670.4  471.63  4692.6  473.04  4699.3  471.01
  4727.8  470.75  4759.3  472.39  4789.6  469.79  4908.1  468.72  4937.1  469.62
  4970.3  467.92  4981.5  468.81  4992.6   467.3  4998.4  462.76    5001  462.45
  5003.8  461.95    5007  462.45    5021  469.41    5064  470.64    5176  474.02
  5607.8  478.07  5624.2  478.99    5788  482.37  6240.2  488.56  6461.3  493.95
#Mann= 9 ,-1 , 0
  3290.2     .05       0  4727.8     .12       0    5001     .07       0
    5007     .12       0    5064     .16       0    5176     .05       0
  5607.8     .16       0  5624.2     .12       0    5788     .05       0
Bank Sta=4981.5,5021
XS Rating Curve= 0 ,0
Exp/Cntr=0.3,0.1

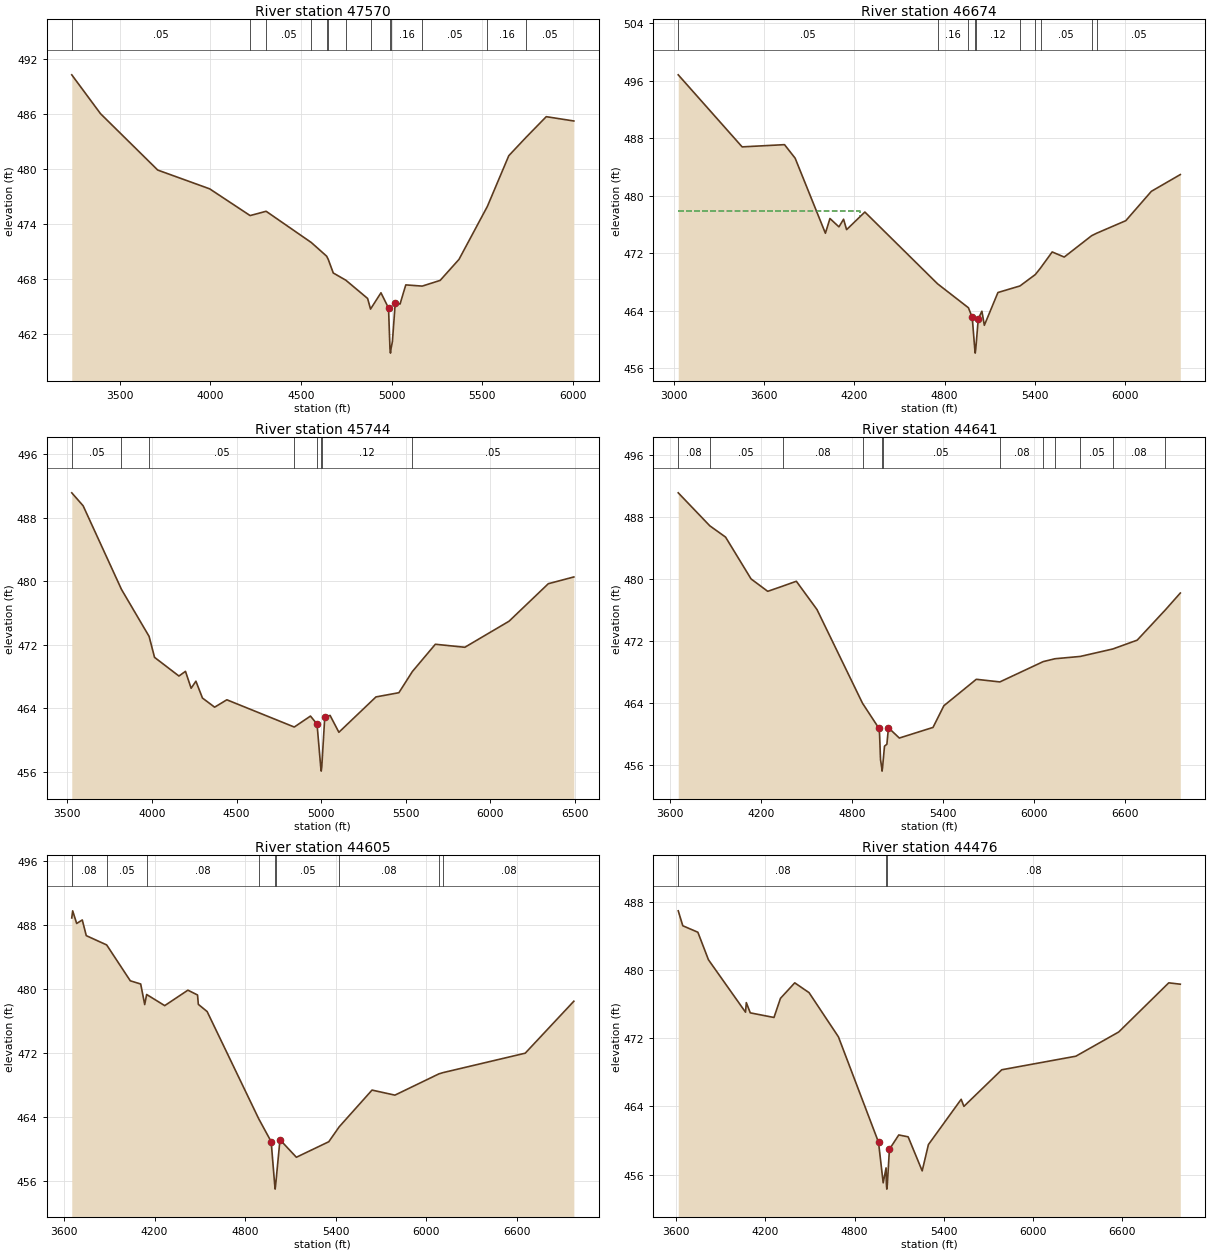
Type RM Length L Ch R = 1 ,47570   ,896,896,896
BEGIN DESCRIPTION:
HOLMAN CREEK 65.0
END DESCRIPTION:
XS GIS Cut Line= 3
      3542622.62     10590970.45      3540638.29     10591621.48
      3540076.59     10592006.34
#Sta/Elev= 30
  3235.6  490.25    3394  486.01  3709.8  479.85  3996.2   477.8  4219.4  474.88
  4307.6  475.35  4556.7  471.94  4641.3  470.45  4650.4  470.09    4678  468.61
  4746.8  467.83  4867.4  465.83  4883.5  464.67  4941.1  466.45  4982.8  464.78
  4990.7  460.36  4993.5  459.86  4996.7  460.36  5004.2  461.13  5019.9  465.36
  5046.3  465.22  5077.9  467.31  5168.6  467.18  5267.4   467.8  5371.2  470.09
  5527.9  475.88  5646.1  481.42  5742.1  483.44  5852.7  485.68  6004.9  485.21
#Mann= 13 ,-1 , 0
  3235.6     .05       0  4219.4      .1       0  4307.6     .05       0
  4556.7      .1       0  4641.3     .05       0  4650.4      .1       0
  4746.8     .05       0  4883.5     .16       0  4990.7     .07       0
  4996.7     .16       0  5168.6     .05       0  5527.9     .16       0
  5742.1     .05       0
Bank Sta=4982.8,5019.9
XS Rating Curve= 0 ,0
Exp/Cntr=0.3,0.1

Type RM Length L Ch R = 1 ,46674   ,930,930,930
BEGIN DESCRIPTION:
HOLMAN CREEK 62.0
END DESCRIPTION:
XS GIS Cut Line= 4
      3542774.24     10590705.54      3540959.49     10590928.77
       3540495.6     10590874.81      3539449.55     10590874.81
#Sta/Elev= 30
  3027.5  496.81  3452.8  486.79  3734.9   487.1  3805.5  485.22    4007  474.78
  4037.2  476.83    4097  475.67  4127.9  476.73    4148  475.28  4269.6  477.73
  4753.4  467.75  4958.8  464.42  4984.2  463.08  5001.3  458.61  5004.1  458.11
  5007.3  458.61  5024.4  462.88  5048.5  463.94  5064.7  461.98  5155.3  466.54
  5301.7  467.45  5404.2  469.04  5439.5  469.97  5516.4  472.18  5596.4  471.47
  5778.8  474.44  5812.8  474.79  6006.4  476.53  6176.4  480.61    6369  482.94
#Mann= 10 ,-1 , 0
  3027.5     .05       0  4753.4     .16       0  4958.8     .12       0
  5001.3     .07       0  5007.3     .12       0  5301.7     .05       0
  5404.2     .12       0  5439.5     .05       0  5778.8     .16       0
  5812.8     .05       0
#XS Ineff= 2 , 0
         4238.92  477.91
Permanent Ineff=
       F       F
Bank Sta=4984.2,5024.4
XS Rating Curve= 0 ,0
Exp/Cntr=0.3,0.1

Type RM Length L Ch R = 1 ,45744   ,1103,1103,1103
BEGIN DESCRIPTION:
HOLMAN CREEK 61.0
END DESCRIPTION:
XS GIS Cut Line= 3
      3542336.21     10589939.18       3540273.7     10590543.35
      3539461.23     10590621.48
#Sta/Elev= 30
    3527  491.13  3594.1   489.5  3820.7  478.97  3983.7  473.06  4015.9  470.42
    4160  468.07  4198.6  468.66    4232  466.53  4260.2  467.42  4298.9   465.3
  4370.9  464.15  4442.9  465.08  4841.1  461.65  4936.8  463.03  4974.4  462.05
  4975.5  462.05  4997.5   456.6  5000.3   456.1  5003.5   456.6  5021.4  462.94
  5052.7  463.11  5104.7  460.99  5323.6  465.44    5459  465.97  5538.5  468.63
  5674.4  472.07  5848.6  471.69  6109.8  474.97  6341.6  479.69  6492.4  480.54
#Mann= 8 ,-1 , 0
    3527     .05       0  3820.7      .1       0  3983.7     .05       0
  4841.1     .16       0  4974.4     .12       0  4997.5     .07       0
  5003.5     .12       0  5538.5     .05       0
Bank Sta=4975.5,5021.4
XS Rating Curve= 0 ,0
Exp/Cntr=0.3,0.1

Type RM Length L Ch R = 1 ,44641   ,36,36,36
BEGIN DESCRIPTION:
HOLMAN CREEK 60.0
END DESCRIPTION:
XS GIS Cut Line= 3
      3542825.57     10589304.65      3541266.58     10589787.28
      3539679.77     10590328.95
#Sta/Elev= 30
    3655  491.06  3863.3   486.8  3966.8  485.35    4135  479.95  4244.8  478.35
  4343.4  479.02  4433.3  479.65  4569.4     476  4869.4  463.91  4976.4  460.71
  4981.7  459.99  4988.1  456.63  4995.6  455.65  4998.3  455.15  5001.6  455.65
  5014.3  458.37    5030  458.62  5040.4  460.74  5112.1  459.42    5334  460.79
  5405.7  463.59  5619.3     467  5774.5  466.66  6060.2  469.28  6137.2  469.65
  6304.5  469.95  6518.7  470.91  6679.6  472.05  6865.4  475.96  6963.7  478.13
#Mann= 12 ,-1 , 0
    3655     .08       0  3863.3     .05       0  4343.4     .08       0
  4869.4     .05       0  4995.6     .04       0  5001.6     .05       0
  5774.5     .08       0  6060.2     .05       0  6137.2     .08       0
  6304.5     .05       0  6518.7     .08       0  6865.4     .05       0
Bank Sta=4976.4,5040.4
XS Rating Curve= 0 ,0
Exp/Cntr=0.3,0.1

Type RM Length L Ch R = 1 ,44605   ,129,129,129
BEGIN DESCRIPTION:
HOLMAN CREEK 59.0
END DESCRIPTION:
XS GIS Cut Line= 2
      3542815.24      10589245.6      3539656.29     10590283.54
#Sta/Elev= 30
  3651.6  488.84  3657.6  489.73  3684.1  488.15  3721.2  488.59  3747.7  486.63
  3882.8  485.47  4039.2  480.99  4108.1  480.59  4134.7  478.02  4147.5  479.28
  4267.2  477.89  4420.9  479.82  4484.5  479.22  4489.8  478.05  4548.1  477.15
  4889.7  463.76  4972.2   460.9  4995.7  455.47  4998.5  454.97  5001.7  455.47
  5030.5  461.14  5139.1  458.95  5353.8  460.89  5422.6  462.75  5640.1  467.34
  5791.7  466.71  6083.7  469.37  6112.1  469.53  6654.8  471.95  6976.7  478.44
#Mann= 9 ,-1 , 0
  3651.6     .08       0  3882.8     .05       0  4147.5     .08       0
  4889.7     .05       0  4995.7     .04       0  5001.7     .05       0
  5422.6     .08       0  6083.7     .05       0  6112.1     .08       0
Bank Sta=4972.2,5030.5
XS Rating Curve= 0 ,0
Exp/Cntr=0.3,0.1

Type RM Length L Ch R = 1 ,44476   ,80,80,80
BEGIN DESCRIPTION:
HOLMAN CREEK 58.0
END DESCRIPTION:
XS GIS Cut Line= 2
      3542835.98     10589117.15      3539617.31     10590151.85
#Sta/Elev= 30
    3613  486.92  3643.7  485.17  3745.2  484.41  3816.6  481.18  4066.1  475.04
  4071.4  476.16  4098.2  474.96  4257.8  474.42  4301.3  476.66  4397.6  478.48
  4493.9  477.33  4691.7  472.15  4961.6   459.8  4993.1  455.04  5012.6  456.79
  5014.9   454.8  5017.6   454.3  5020.9   454.8  5035.1  458.97  5098.1  460.65
  5161.2  460.43  5255.7  456.44  5297.7  459.52  5518.3  464.83  5536.6     464
  5791.4  468.29  6290.5  469.88  6579.2  472.72  6916.1  478.48  6993.9  478.32
#Mann= 3 ,-1 , 0
    3613     .08       0  5014.9     .07       0  5020.9     .08       0
Bank Sta=4961.6,5035.1
XS Rating Curve= 0 ,0
Exp/Cntr=0.3,0.1

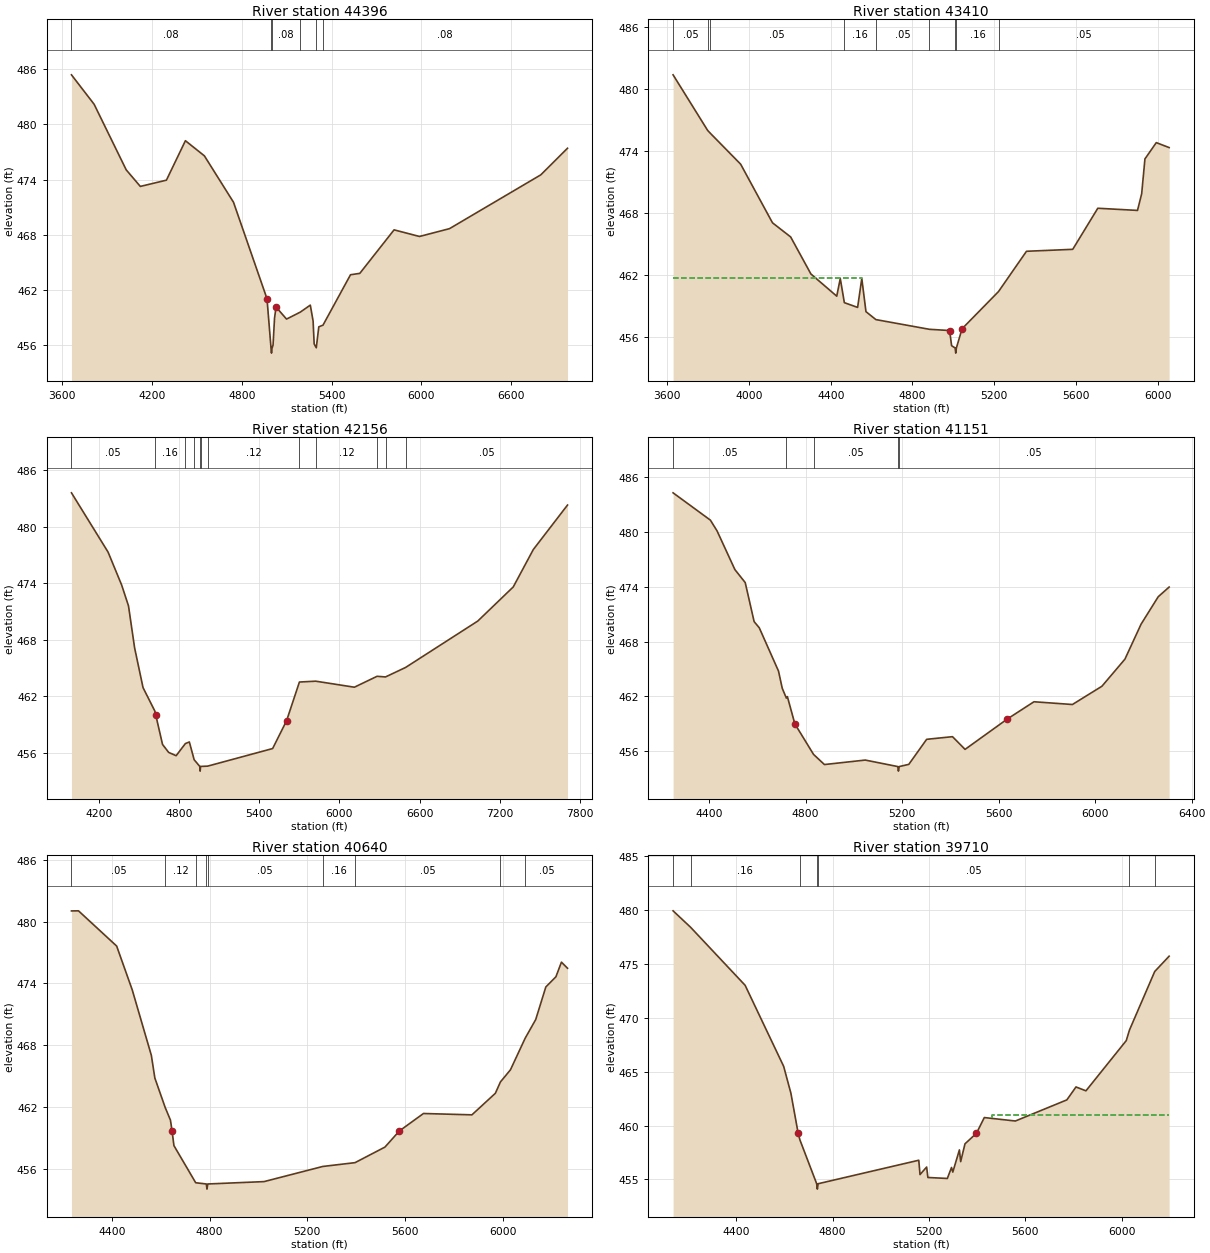
Type RM Length L Ch R = 1 ,44396   ,986,986,986
BEGIN DESCRIPTION:
HOLMAN CREEK 57.0
END DESCRIPTION:
XS GIS Cut Line= 4
      3542822.14     10589068.53      3541669.36     10589460.89
        3541402.     10589481.72      3539679.79     10590085.88
#Sta/Elev= 30
  3663.6  485.39  3814.9  482.19  4029.1  475.06  4123.2  473.26  4297.4  473.94
  4424.2  478.23    4551  476.58  4745.2  471.54  4968.8  461.05  4995.9  455.64
  4998.7  455.14  5001.9  455.64    5009     456    5019  458.93    5029  460.15
  5099.2  458.84  5191.3   459.6  5257.8  460.36  5276.5  458.63  5283.5  456.14
  5297.6  455.72  5314.5     458  5342.5  458.18  5526.2  463.66  5588.2  463.81
    5817  468.54  5986.6  467.82    6187  468.67  6796.5  474.52  6974.6  477.41
#Mann= 6 ,-1 , 0
  3663.6     .08       0  4995.9     .07       0  5001.9     .08       0
  5191.3     .16       0  5297.6     .12       0  5342.5     .08       0
Bank Sta=4968.8,5029
XS Rating Curve= 0 ,0
Exp/Cntr=0.3,0.1

Type RM Length L Ch R = 1 ,43410   ,1254,1254,1254
BEGIN DESCRIPTION:
HOLMAN CREEK 56.0
END DESCRIPTION:
XS GIS Cut Line= 2
      3542765.64     10588485.96      3540390.68     10588991.16
#Sta/Elev= 30
  3628.5  481.38  3797.8  475.99  3810.2  475.73  3959.3  472.72  4115.1  467.04
    4204  465.67  4303.2  462.08  4429.6  459.93  4446.9  461.64  4466.9   459.3
  4531.8  458.84  4552.2  461.65  4572.7  458.43  4621.1  457.66  4882.9  456.72
  4982.1   456.6  4991.9  455.13  5009.3  454.91  5012.1  454.41  5015.3  454.91
    5043  456.77  5221.6  460.38  5358.4  464.28  5584.8  464.47  5707.5  468.45
  5901.8  468.24  5922.2  469.85  5938.2  473.23  5993.8  474.81  6056.6  474.33
#Mann= 9 ,-1 , 0
  3628.5     .05       0  3797.8      .1       0  3810.2     .05       0
  4466.9     .16       0  4621.1     .05       0  4882.9     .16       0
  5009.3     .07       0  5015.3     .16       0  5221.6     .05       0
#XS Ineff= 2 , 0
          4551.7   461.7
Permanent Ineff=
       F       F
Bank Sta=4982.1,5043
XS Rating Curve= 0 ,0
Exp/Cntr=0.3,0.1

Type RM Length L Ch R = 1 ,42156   ,1005,1005,1005
BEGIN DESCRIPTION:
HOLMAN CREEK 55.0
END DESCRIPTION:
XS GIS Cut Line= 4
      3542726.47     10587910.39      3541927.89     10587749.81
      3541506.89     10587814.92      3539258.62     10586799.29
#Sta/Elev= 30
  3996.7  483.62  4270.4  477.32  4372.1  473.81    4423   471.6  4468.8  467.13
  4531.6  462.92    4620  460.42  4626.4  460.02  4677.3  456.88  4723.1  456.03
    4779  455.68  4848.2  456.97  4877.8  457.14  4913.8  455.25  4955.8  454.54
  4958.5  454.04  4961.8  454.54  5014.5  454.57  5500.3  456.44  5604.6   459.4
  5700.5  463.51  5822.4   463.6  6111.2  462.96    6281  464.12  6343.9  464.05
  6494.2  465.06  7033.6  469.99  7298.9  473.62  7448.6  477.59  7704.3  482.32
#Mann= 12 ,-1 , 0
  3996.7     .05       0    4620     .16       0  4848.2     .12       0
  4913.8     .16       0  4955.8     .07       0  4961.8     .16       0
  5014.5     .12       0  5700.5     .05       0  5822.4     .12       0
    6281     .05       0  6343.9     .12       0  6494.2     .05       0
Bank Sta=4626.4,5604.6
XS Rating Curve= 0 ,0
Exp/Cntr=0.3,0.1

Type RM Length L Ch R = 1 ,41151   ,511,511,511
BEGIN DESCRIPTION:
HOLMAN CREEK 54.0
END DESCRIPTION:
XS GIS Cut Line= 2
       3542644.7     10587499.85      3540882.55     10586440.82
#Sta/Elev= 30
  4250.7  484.28  4405.4  481.29  4433.1  480.11  4506.9  475.88  4549.7  474.46
  4586.6  470.19    4608  469.51  4687.6  464.78  4703.2  462.89  4720.2  461.82
  4724.5  461.98  4755.4     459  4832.9  455.66    4878  454.55  5047.1  455.04
    5182  454.33  5184.7  453.83    5188  454.33  5227.7  454.57  5301.6  457.31
  5408.8   457.6  5460.9  456.21  5635.8  459.53  5746.5  461.42  5905.8  461.12
  6028.2  463.12  6123.4  466.08  6190.4  469.91  6261.4  472.91  6306.6  473.97
#Mann= 5 ,-1 , 0
  4250.7     .05       0  4720.2     .12       0  4832.9     .05       0
    5182    .033       0    5188     .05       0
Bank Sta=4755.4,5635.8
XS Rating Curve= 0 ,0
Exp/Cntr=0.3,0.1

Type RM Length L Ch R = 1 ,40640   ,930,930,930
BEGIN DESCRIPTION:
HOLMAN CREEK 52.0
END DESCRIPTION:
XS GIS Cut Line= 4
      3542648.41      10587185.6      3542205.67     10586816.65
      3541901.85     10586491.13      3540926.24     10586239.64
#Sta/Elev= 30
  4235.2  481.04  4263.9  481.05  4420.1  477.63  4483.9  473.37    4562  467.02
  4576.3  464.82  4618.8  461.95  4640.1  460.74  4646.9  459.65  4654.4  458.26
  4743.4  454.66  4786.8  454.54  4789.5  454.04  4792.8  454.54    5023  454.77
  5263.2  456.24  5395.2  456.61  5517.5  458.12  5576.7  459.69  5675.1  461.38
  5873.3  461.25  5969.1  463.34  5990.1  464.45  6030.9  465.62  6091.2  468.69
  6134.3   470.5  6175.6  473.66  6216.9  474.65  6239.5  476.07  6264.3  475.48
#Mann= 9 ,-1 , 0
  4235.2     .05       0  4618.8     .12       0  4743.4     .05       0
  4786.8    .033       0  4792.8     .05       0  5263.2     .16       0
  5395.2     .05       0  5990.1     .08       0  6091.2     .05       0
Bank Sta=4646.9,5576.7
XS Rating Curve= 0 ,0
Exp/Cntr=0.3,0.1

Type RM Length L Ch R = 1 ,39710   ,681,681,681
BEGIN DESCRIPTION:
HOLMAN CREEK 51.0
END DESCRIPTION:
XS GIS Cut Line= 3
      3542941.22     10585799.96      3542240.39     10585792.35
      3540942.08     10586191.65
#Sta/Elev= 30
  4137.6  479.92  4210.1   478.4  4436.7  473.01  4596.7  465.49  4626.7     463
  4656.7   459.3  4664.1  458.67  4733.7   454.6  4736.5   454.1  4739.7   454.6
  5157.5  456.78  5162.7  455.45  5190.2  456.15  5195.4  455.18  5276.1  455.09
  5293.5  456.11  5298.8  455.68  5326.2  457.74  5331.5  456.65  5349.3   458.3
  5396.9  459.28  5429.6  460.74  5558.6  460.42  5772.3  462.38  5810.2  463.58
  5851.5  463.22  6018.9  467.88  6032.2  468.86    6137  474.29  6196.8  475.71
#Mann= 7 ,-1 , 0
  4137.6     .08       0  4210.1     .16       0  4664.1     .05       0
  4733.7    .033       0  4739.7     .05       0  6032.2     .08       0
    6137     .05       0
#XS Ineff= 2 , 0
                         5461.65          460.96
Permanent Ineff=
       F       F
Bank Sta=4656.7,5396.9
XS Rating Curve= 0 ,0
Exp/Cntr=0.3,0.1

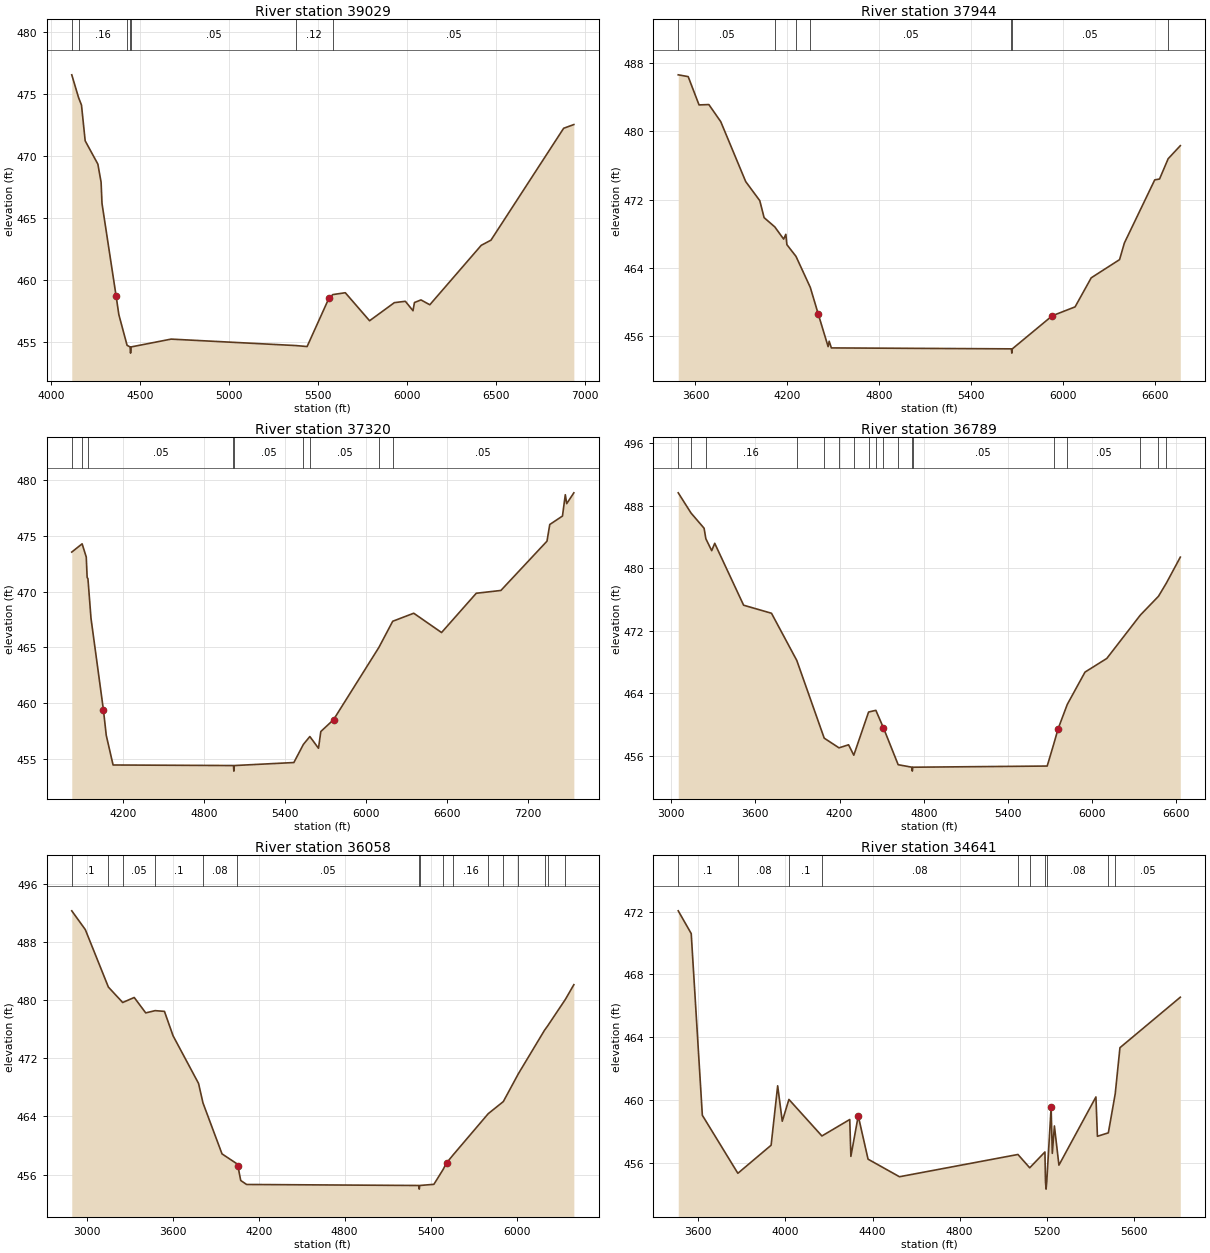
Type RM Length L Ch R = 1 ,39029   ,1085,1085,1085
BEGIN DESCRIPTION:
HOLMAN CREEK 49.0
END DESCRIPTION:
XS GIS Cut Line= 2
      3542935.52     10585351.16      3540176.11     10584769.77
#Sta/Elev= 30
  4116.4  476.53  4154.7  474.69    4171  474.09  4191.7  471.21    4263  469.33
  4281.1  467.87  4286.2  466.16  4365.2  458.72  4380.7   457.2  4427.1  454.72
  4443.9  454.59  4446.7  454.09  4449.9  454.59  4674.4  455.22  5374.9   454.7
  5438.2  454.62  5560.9  458.52  5582.8  458.81  5652.8  458.96  5789.1   456.7
  5928.3  458.16  5990.1  458.27    6033  457.51  6041.2  458.17  6077.7  458.38
  6127.5  457.99  6416.1  462.78    6471   463.2  6879.2  472.22  6936.4  472.52
#Mann= 7 ,-1 , 0
  4116.4     .08       0  4154.7     .16       0  4427.1     .05       0
  4443.9    .033       0  4449.9     .05       0  5374.9     .12       0
  5582.8     .05       0
Bank Sta=4365.2,5560.9
XS Rating Curve= 0 ,0
Exp/Cntr=0.3,0.1

Type RM Length L Ch R = 1 ,37944   ,624,624,624
BEGIN DESCRIPTION:
HOLMAN CREEK 48.0
END DESCRIPTION:
XS GIS Cut Line= 4
      3543468.72     10585136.99       3542596.3     10584212.48
      3541502.55     10583830.54       3540692.1     10583591.64
#Sta/Elev= 30
  3487.8  486.59  3552.7  486.38  3623.5  483.07  3687.5  483.11  3765.1  481.11
  3927.8   474.1  4019.6  471.87  4047.9  469.88  4117.5   468.8  4175.4  467.37
  4189.5  467.93  4196.4  466.72  4255.8  465.35  4348.9  461.73  4401.9  458.55
  4465.4  454.79  4472.3  455.42  4486.5  454.64  5660.7  454.53  5663.5  454.03
  5666.7  454.53  5927.2   458.4  6076.1  459.44  6181.3  462.84  6366.2  464.97
  6397.5  466.91  6595.6   474.3  6626.9   474.4    6683  476.77  6762.4   478.3
#Mann= 7 ,-1 , 0
  3487.8     .05       0  4117.5     .08       0  4255.8     .12       0
  4348.9     .05       0  5660.7    .033       0  5666.7     .05       0
    6683     .16       0
Bank Sta=4401.9,5927.2
XS Rating Curve= 0 ,0
Exp/Cntr=0.3,0.1

Type RM Length L Ch R = 1 ,37320   ,531,531,531
BEGIN DESCRIPTION:
HOLMAN CREEK 46.0
END DESCRIPTION:
XS GIS Cut Line= 4
      3543399.25     10584325.34      3542782.93     10583600.51
       3542036.4     10583396.51      3540131.65     10582806.43
#Sta/Elev= 30
  3818.4  473.55  3895.1  474.29  3925.7  473.11  3932.3  471.28  3938.3  471.16
  3960.9  467.61  4053.1  459.39    4074  457.12  4124.5  454.47  5016.5  454.42
  5019.2  453.92  5022.5  454.42  5463.7  454.69  5534.5  456.32  5582.2  457.02
  5646.2  455.97  5663.4  457.47  5757.6  458.53  6093.7  465.01    6196  467.35
  6351.7  468.07  6557.8  466.34    6815  469.86  6997.3  470.11    7339  474.53
  7359.4  476.02  7453.6  476.78  7474.6  478.69    7485  477.89  7537.8  478.86
#Mann= 9 ,-1 , 0
  3818.4     .05       0  3895.1     .08       0  3938.3     .05       0
  5016.5    .033       0  5022.5     .05       0  5534.5     .16       0
  5582.2     .05       0  6093.7     .08       0    6196     .05       0
Bank Sta=4053.1,5757.6
XS Rating Curve= 0 ,0
Exp/Cntr=0.3,0.1

Type RM Length L Ch R = 1 ,36789   ,731,731,731
BEGIN DESCRIPTION:
HOLMAN CREEK 45.0
END DESCRIPTION:
XS GIS Cut Line= 3
      3544542.12     10583791.65      3542742.11     10583041.64
       3541542.1     10581941.64
#Sta/Elev= 30
    3050  489.65  3141.4  487.06  3234.2  485.12  3246.9  483.77  3288.4  482.25
    3310  483.19  3515.9  475.27  3714.6  474.24  3894.9   468.2  4090.2  458.26
  4195.6  457.02  4263.9  457.41    4301  456.08  4406.4   461.6  4458.3  461.82
  4511.9   459.6  4617.3  454.86  4715.4  454.54  4718.1  454.04  4721.4  454.54
  5679.2  454.69  5725.7  457.49  5757.5  459.48  5822.5  462.58  5948.7  466.71
  6104.1  468.46  6342.7     474  6472.2  476.41  6528.5   478.1  6627.9  481.42
#Mann= 18 ,-1 , 0
    3050      .1       0  3141.4     .05       0  3246.9     .16       0
  3894.9     .12       0  4090.2     .05       0  4195.6      .1       0
    4301     .05       0  4406.4     .08       0  4458.3     .05       0
  4511.9     .08       0  4617.3     .05       0  4715.4    .033       0
  4721.4     .05       0  5725.7     .16       0  5822.5     .05       0
  6342.7      .1       0  6472.2     .12       0  6528.5      .1       0
Bank Sta=4511.9,5757.5
XS Rating Curve= 0 ,0
Exp/Cntr=0.3,0.1

Type RM Length L Ch R = 1 ,36058   ,1417,1417,1417
BEGIN DESCRIPTION:
HOLMAN CREEK 43.0
END DESCRIPTION:
XS GIS Cut Line= 3
      3544966.08     10582315.78      3543212.62     10582476.37
      3541598.06       10581821.
#Sta/Elev= 30
  2895.9  492.28  2990.3   489.7  3151.5  481.79  3251.2  479.67  3331.7  480.36
    3412  478.24  3477.4  478.55  3542.6  478.45  3602.8  475.09  3780.5  468.54
  3811.4  465.86  3944.2  458.85  4048.7  457.48  4054.7  457.23  4074.8  455.19
  4115.7  454.64  5317.8   454.5  5320.6     454  5323.8   454.5  5422.6  454.66
  5486.7  456.69    5511  457.61  5559.3  458.76  5801.9  464.38    5907  466.04
  6012.1  469.87  6194.5  475.85  6216.1  476.44  6340.2   480.1  6399.2  482.12
#Mann= 16 ,-1 , 0
  2895.9      .1       0  3151.5     .16       0  3251.2     .05       0
  3477.4      .1       0  3811.4     .08       0  4048.7     .05       0
  5317.8    .033       0  5323.8     .05       0  5486.7     .12       0
  5559.3     .16       0  5801.9     .12       0    5907     .05       0
  6012.1      .1       0  6194.5     .05       0  6216.1      .1       0
  6340.2     .05       0
Bank Sta=4054.7,5511
XS Rating Curve= 0 ,0
Exp/Cntr=0.3,0.1

Type RM Length L Ch R = 1 ,34641   ,29,29,29
BEGIN DESCRIPTION:
HOLMAN CREEK 42.0
END DESCRIPTION:
XS GIS Cut Line= 6
      3544166.43     10580633.49      3543628.42     10581009.83
      3543311.58     10581099.89      3542663.79     10581145.46
       3542379.5      10581367.9      3542093.09     10581465.54
#Sta/Elev= 30
  3507.9  472.06  3567.5  470.61  3618.6  459.02  3781.7  455.32  3934.4  457.11
  3964.5   460.9  3985.6  458.64  4016.2  460.03  4167.7   457.7  4295.5  458.75
  4300.7   456.4  4334.5  458.98  4379.6  456.22  4523.9   455.1  5067.9  456.52
  5121.9  455.67  5191.8  456.68  5194.3  454.81  5197.1  454.31  5200.3  454.81
  5220.2  459.52  5225.7  456.59  5235.3  458.34  5256.1  455.84    5426  460.19
  5432.9  457.68    5483   457.9  5514.6  460.39  5536.3  463.33  5813.5  466.55
#Mann= 10 ,-1 , 0
  3507.9      .1       0  3781.7     .08       0  4016.2      .1       0
  4167.7     .08       0  5067.9     .05       0  5121.9     .08       0
  5194.3     .07       0  5200.3     .08       0    5483     .16       0
  5514.6     .05       0
Bank Sta=4334.5,5220.2
XS Rating Curve= 0 ,0
Exp/Cntr=0.3,0.1