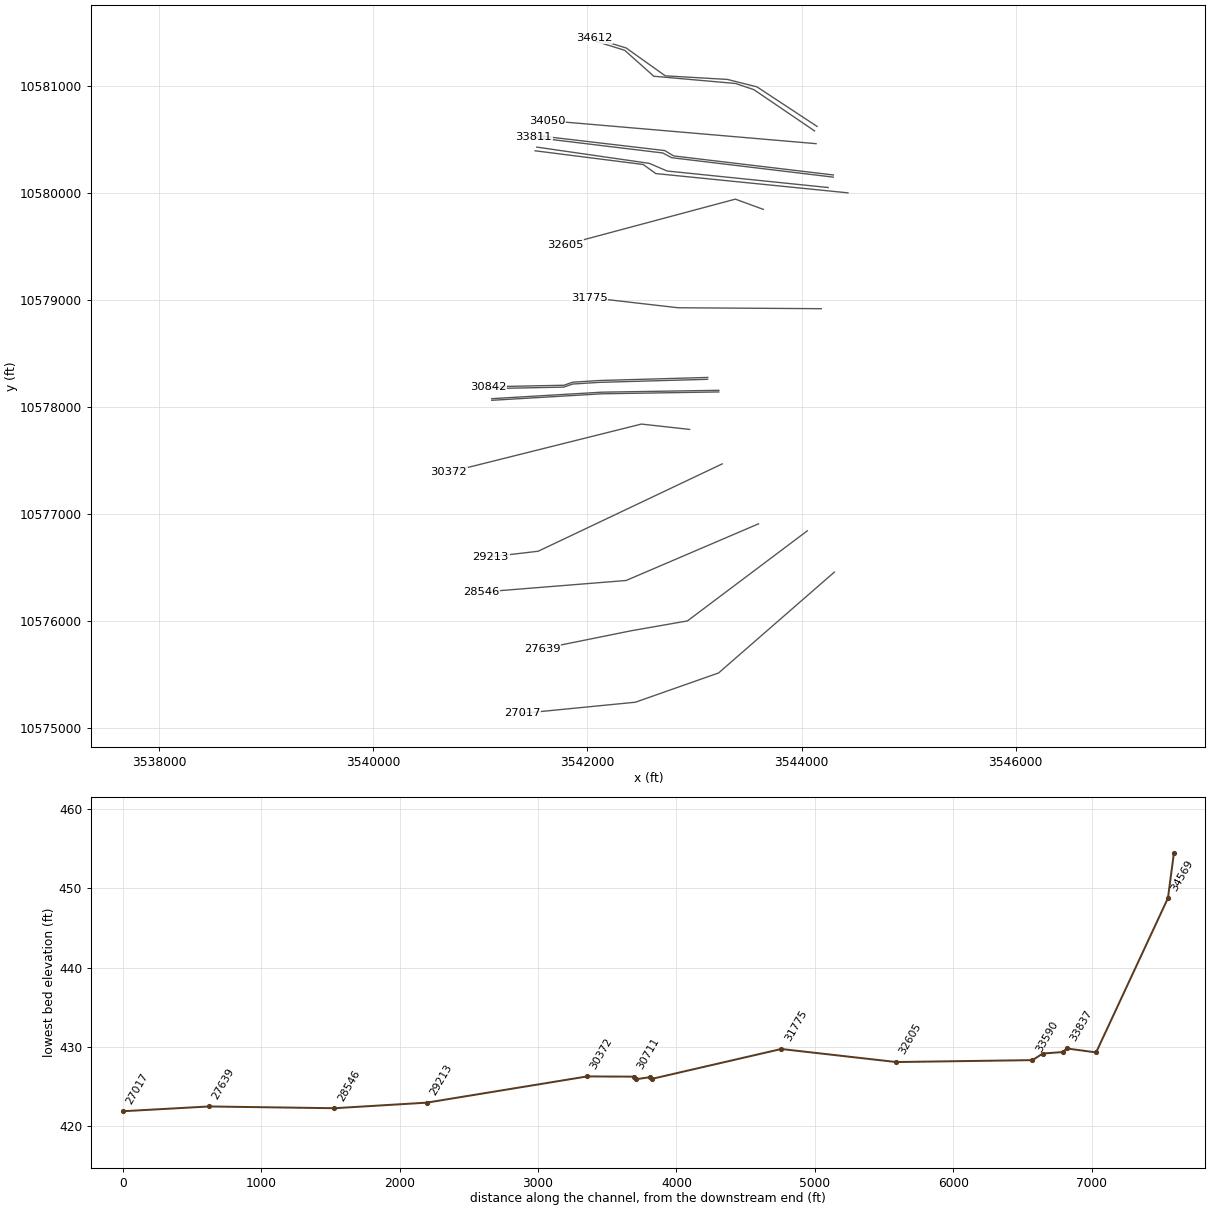
HEC-RAS study HOLMAN CREEK.prj: HOLMAN CREEK Base Level Engineering

--- HOLMAN CREEK.g01 (geometry) --- (continued)

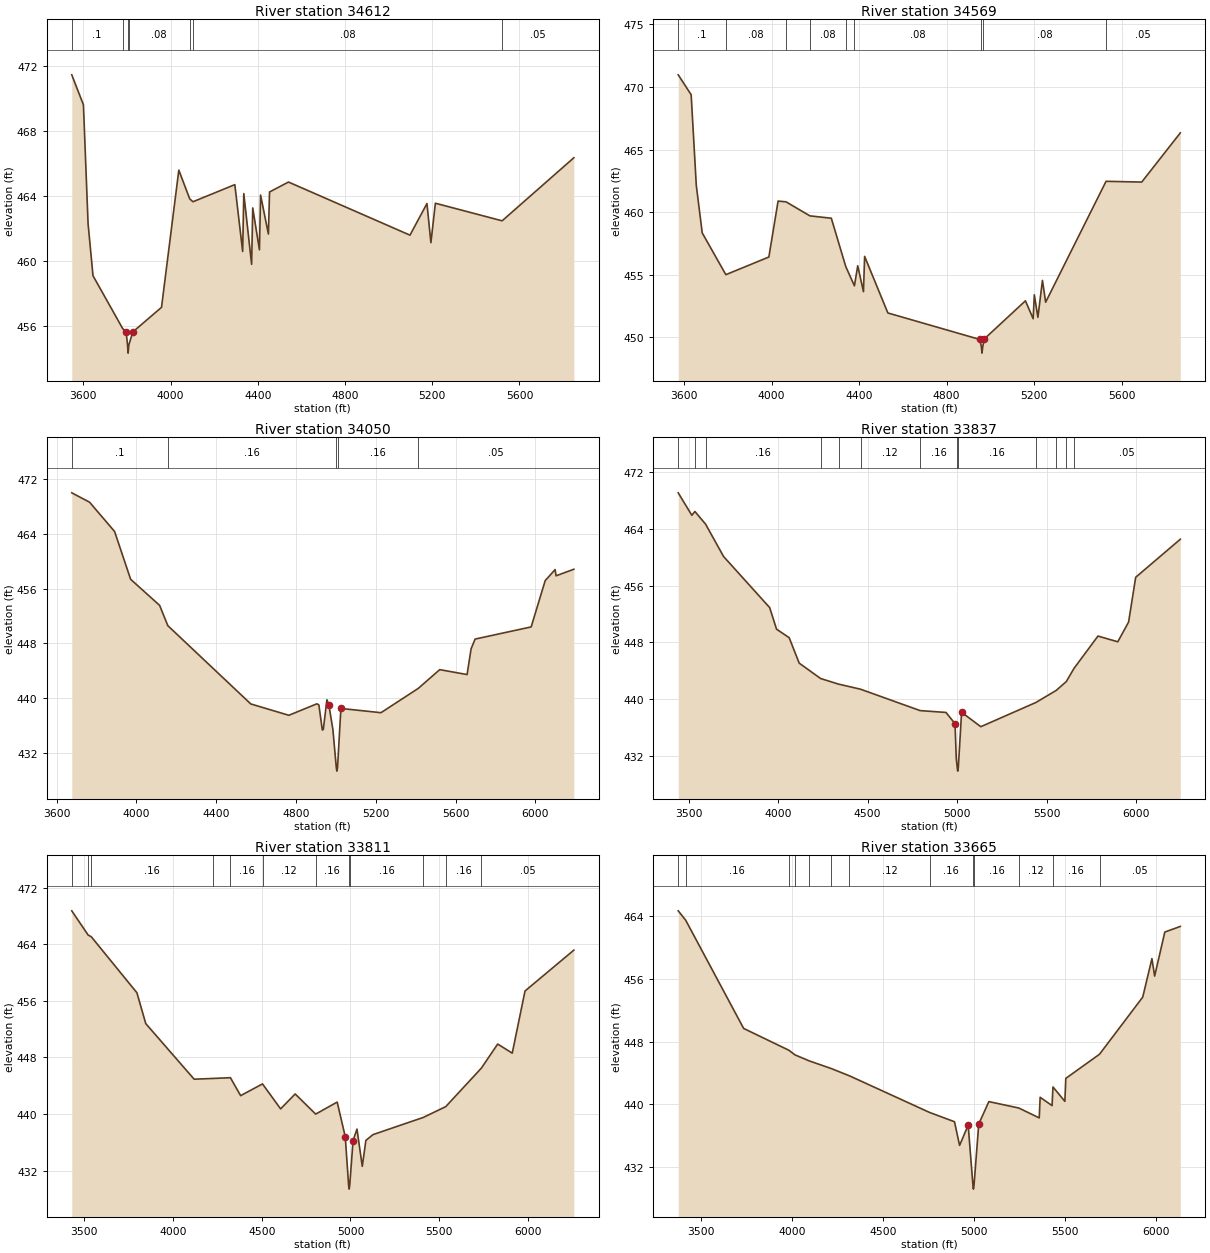
Type RM Length L Ch R = 1 ,34612   ,43,43,43
BEGIN DESCRIPTION:
HOLMAN CREEK 41.0
END DESCRIPTION:
XS GIS Cut Line= 6
      3544145.25     10580620.24      3543583.97     10580989.61
      3543308.36     10581059.05      3542727.85     10581092.69
      3542362.18     10581353.11      3542067.93     10581442.94
#Sta/Elev= 30
  3546.6  471.44  3600.1   469.6  3621.4   462.3    3644  459.11  3779.6  455.88
  3796.3  455.63  3802.3  454.86    3805  454.36  3808.3  454.86  3826.6  455.66
  3958.2  457.17  4037.6  465.59  4087.5  463.83  4102.5  463.65  4294.5   464.7
  4330.4   460.6  4335.6  464.15  4371.5  459.81  4376.6  463.27  4407.4   460.7
  4412.6  464.06  4448.5  461.67  4453.7  464.25  4540.5  464.86  5097.8   461.6
  5175.7  463.54  5193.8  461.14  5214.3  463.56  5520.4  462.48  5849.4  466.35
#Mann= 7 ,-1 , 0
  3546.6      .1       0  3779.6     .08       0  3802.3     .07       0
  3808.3     .08       0  4087.5      .1       0  4102.5     .08       0
  5520.4     .05       0
Bank Sta=3796.3,3826.6
XS Rating Curve= 0 ,0
Exp/Cntr=0.3,0.1

Type RM Length L Ch R = 1 ,34569   ,519,519,519
BEGIN DESCRIPTION:
HOLMAN CREEK 40.0
END DESCRIPTION:
XS GIS Cut Line= 6
      3544121.54     10580578.45      3543554.69     10580963.87
      3543384.55     10581021.17      3542620.66     10581088.87
      3542348.96     10581331.06      3542067.68     10581418.74
#Sta/Elev= 30
  3573.5  470.97  3632.6  469.38    3656  462.14  3683.1  458.34  3791.1     455
  3987.7  456.41  4029.8  460.88  4066.2  460.82  4175.1   459.7  4273.1  459.51
  4339.3  455.64  4378.7  454.11  4393.8  455.71    4420  453.64  4425.3  456.46
  4531.5  451.94    4952  449.82    4959  449.23  4961.7  448.73    4965  449.23
    4972  449.86  5160.2  452.91  5195.6  451.48  5200.8  453.39  5217.2  451.59
    5238  454.54  5252.6   452.8  5528.6  462.46  5691.7   462.4    5868  466.33
#Mann= 9 ,-1 , 0
  3573.5      .1       0  3791.1     .08       0  4066.2      .1       0
  4175.1     .08       0  4339.3      .1       0  4378.7     .08       0
    4959     .07       0    4965     .08       0  5528.6     .05       0
Bank Sta=4952,4972
XS Rating Curve= 0 ,0
Exp/Cntr=0.3,0.1

Type RM Length L Ch R = 1 ,34050   ,213,213,213
BEGIN DESCRIPTION:
HOLMAN CREEK 38.01
END DESCRIPTION:
XS GIS Cut Line= 2
        3544136.     10580459.02      3541629.03      10580674.3
#Sta/Elev= 30
  3676.4  470.04  3765.6  468.67  3891.1  464.38  3971.4  457.39  4116.5  453.58
  4157.9   450.6  4573.6  439.15  4764.3  437.49  4904.8  439.17  4914.8  439.01
  4932.1  435.33  4937.1  435.42    4955  439.76    4965  438.99  4985.1   435.4
  5002.2  429.82  5004.9  429.32  5008.2  429.82  5025.2  438.49    5226  437.87
  5412.7  441.42  5520.4  444.17  5657.6  443.45  5677.6  447.21  5697.7  448.64
  5978.7  450.42    6049  457.19  6098.6  458.81  6103.7   457.9  6192.6  458.86
#Mann= 5 ,-1 , 0
  3676.4      .1       0  4157.9     .16       0  5002.2     .07       0
  5008.2     .16       0  5412.7     .05       0
Bank Sta=4965,5025.2
XS Rating Curve= 0 ,0
Exp/Cntr=0.3,0.1

Type RM Length L Ch R = 1 ,33837   ,26,26,26
BEGIN DESCRIPTION:
HOLMAN CREEK 39.01
END DESCRIPTION:
XS GIS Cut Line= 4
      3544297.56     10580166.52      3542805.96     10580344.47
      3542723.49     10580394.39      3541525.22     10580535.23
#Sta/Elev= 30
  3442.3  469.09  3518.3  465.92  3535.4  466.46  3595.4  464.66  3695.5  460.11
  3953.1   452.9  3991.6  449.85  4062.1  448.65  4118.1  445.06  4237.7  442.89
  4337.7   442.1  4460.8  441.38  4793.9  438.36  4938.3   438.1  4988.6  436.52
  4995.7   431.6  5001.1  430.32  5003.8  429.82  5007.1  430.32  5025.4  438.12
  5132.9  436.09    5440   439.5  5553.5   441.2  5610.2  442.45  5653.6  444.32
  5787.4  448.88  5898.1  448.07  5958.5  450.86  5998.1  457.17  6247.4  462.54
#Mann= 13 ,-1 , 0
  3442.3     .05       0  3535.4      .1       0  3595.4     .16       0
  4237.7      .1       0  4337.7     .16       0  4460.8     .12       0
  4793.9     .16       0  5001.1     .07       0  5007.1     .16       0
    5440     .12       0  5553.5     .16       0  5610.2     .12       0
  5653.6     .05       0
Bank Sta=4988.6,5025.4
XS Rating Curve= 0 ,0
Exp/Cntr=0.3,0.1

Type RM Length L Ch R = 1 ,33811   ,146,146,146
BEGIN DESCRIPTION:
HOLMAN CREEK 39.0
END DESCRIPTION:
XS GIS Cut Line= 4
      3544296.48     10580146.34      3542788.02     10580327.76
      3542704.69     10580372.03      3541498.97     10580517.87
#Sta/Elev= 30
  3430.1  468.73  3522.5   465.3  3539.8  465.07  3797.1  457.14  3846.9  452.78
  4119.4  444.92  4223.7  445.02  4323.8  445.13  4381.3  442.59  4504.5  444.25
  4606.5  440.72  4688.6  442.83    4804  439.98  4925.2  441.68  4970.7  436.79
  4989.7  429.87  4992.5  429.37  4995.7  429.87  5014.7  436.23  5036.7  437.86
  5066.5  432.59  5086.9  436.26    5127  437.08  5410.3  439.51  5536.8  441.04
    5737  446.47  5829.4  449.89  5911.3   448.6  5983.2  457.39  6258.3  463.17
#Mann= 12 ,-1 , 0
  3430.1     .05       0  3522.5      .1       0  3539.8     .16       0
  4223.7      .1       0  4323.8     .16       0  4504.5     .12       0
    4804     .16       0  4989.7     .07       0  4995.7     .16       0
  5410.3     .12       0  5536.8     .16       0    5737     .05       0
Bank Sta=4970.7,5014.7
XS Rating Curve= 0 ,0
Exp/Cntr=0.3,0.1

Type RM Length L Ch R = 1 ,33665   ,75,75,75
BEGIN DESCRIPTION:
HOLMAN CREEK 39.02
END DESCRIPTION:
XS GIS Cut Line= 4
       3544249.1     10580049.33       3542745.2     10580203.59
       3542578.1     10580275.21      3541527.97     10580426.77
#Sta/Elev= 30
  3376.2   464.7  3417.2   463.5  3735.1  449.69  3983.7   446.9  4016.2  446.32
  4095.8  445.54  4215.8  444.57  4315.7  443.64  4754.8  438.97  4891.9  437.78
  4919.8  434.76    4967  437.35    4993  429.68  4995.7  429.18    4999  429.68
    5025  437.49  5080.4  440.35    5245  439.53  5356.8  438.27  5361.8   440.9
  5427.1  439.84  5432.2  442.22  5497.5  440.38  5502.5  443.31  5687.7   446.4
  5924.7  453.69  5975.1   458.6    5990  456.37  6045.8  461.99  6130.8  462.71
#Mann= 13 ,-1 , 0
  3376.2     .05       0  3417.2     .16       0  3983.7      .1       0
  4016.2     .05       0  4095.8     .16       0  4215.8      .1       0
  4315.7     .12       0  4754.8     .16       0    4993     .07       0
    4999     .16       0    5245     .12       0  5432.2     .16       0
  5687.7     .05       0
Bank Sta=4967,5025
XS Rating Curve= 0 ,0
Exp/Cntr=0.3,0.1

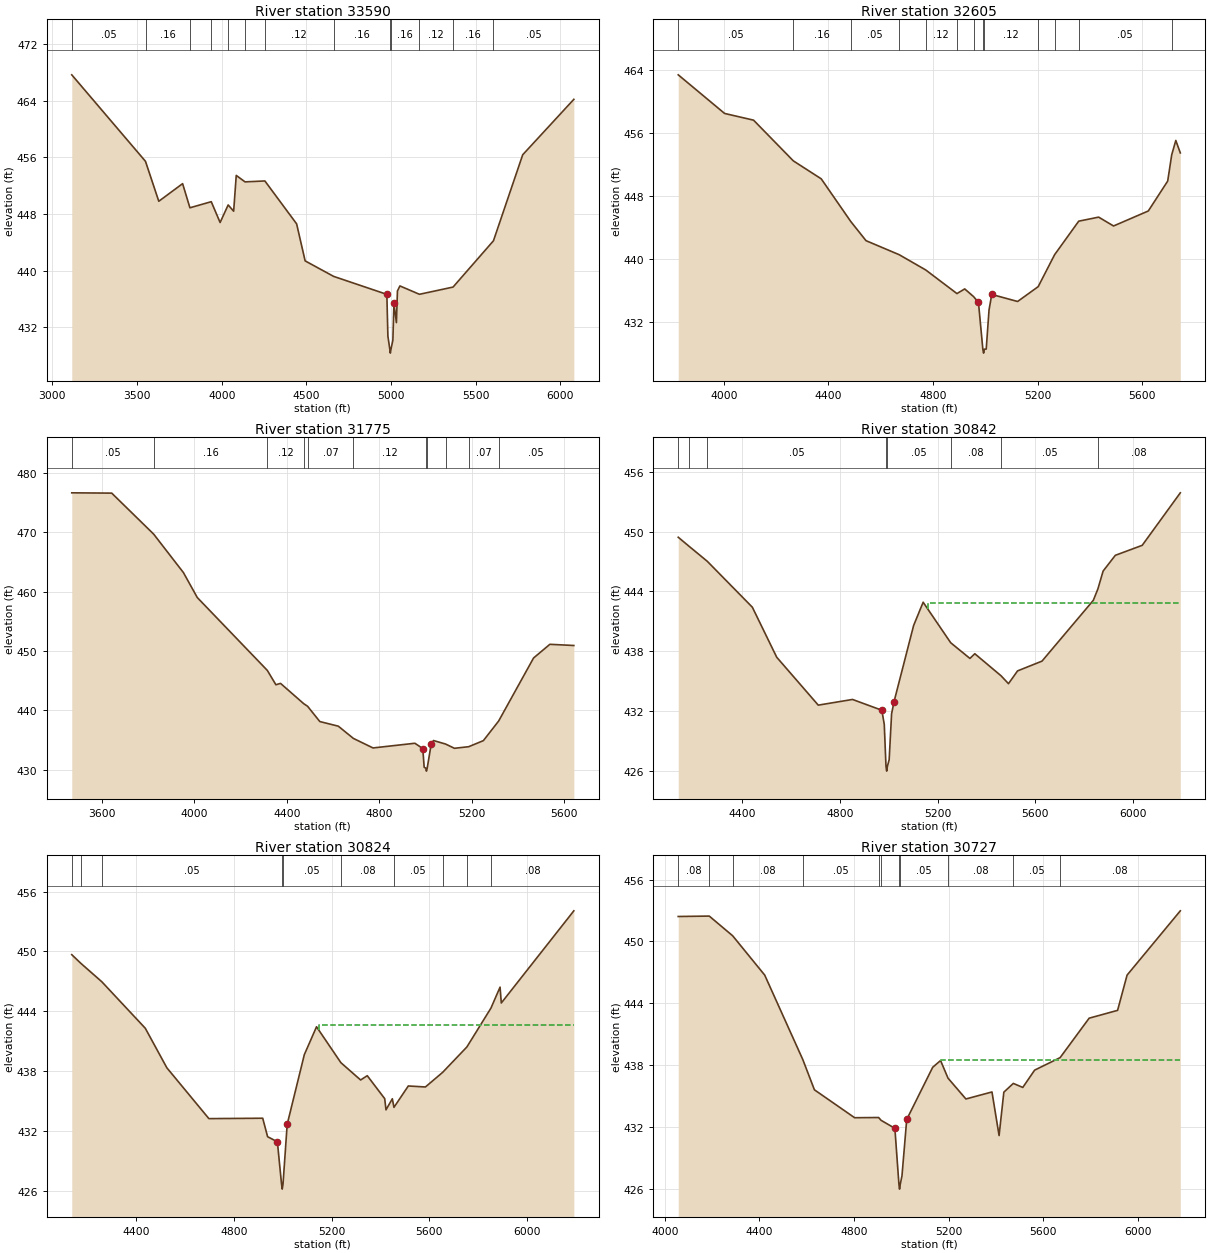
Type RM Length L Ch R = 1 ,33590   ,985,985,985
BEGIN DESCRIPTION:
HOLMAN CREEK 39.03
END DESCRIPTION:
XS GIS Cut Line= 4
      3544433.57      10579999.6      3542638.86     10580179.72
      3542521.67     10580264.36      3541512.55      10580392.4
#Sta/Elev= 30
  3114.4  467.66  3549.9  455.44  3628.4   449.8  3769.1  452.29  3812.2  448.88
  3938.3  449.74  3990.6   446.8  4038.1  449.28  4070.6   448.4  4085.9  453.45
  4137.9  452.54    4255  452.67  4442.5  446.61  4492.8  441.38  4661.1  439.19
  4975.4  436.65  4981.6  430.75  4993.3  428.85    4996  428.35  4999.3  428.85
    5011  430.18  5017.2  435.37  5031.9  432.66    5038  437.13  5052.7  437.84
    5168  436.66  5366.4  437.68  5605.1  444.22  5777.9  456.37  6079.9   464.2
#Mann= 13 ,-1 , 0
  3114.4     .05       0  3549.9     .16       0  3812.2      .1       0
  3938.3     .05       0  4038.1      .1       0  4137.9     .05       0
    4255     .12       0  4661.1     .16       0  4993.3     .07       0
  4999.3     .16       0    5168     .12       0  5366.4     .16       0
  5605.1     .05       0
Bank Sta=4975.4,5017.2
XS Rating Curve= 0 ,0
Exp/Cntr=0.3,0.1

Type RM Length L Ch R = 1 ,32605   ,830,830,830
BEGIN DESCRIPTION:
HOLMAN CREEK 38.0
END DESCRIPTION:
XS GIS Cut Line= 3
      3543642.86     10579845.32      3543382.48     10579940.79
      3541795.52     10579515.87
#Sta/Elev= 30
  3825.9  463.35  4003.2  458.46    4114  457.61  4265.9  452.46  4372.8  450.18
  4485.7  444.78  4544.1  442.35  4671.2  440.57  4772.5  438.64  4891.9  435.65
  4921.5  436.24  4955.4  435.27  4974.1  434.54  4990.9  428.61  4993.7  428.11
  4996.9  428.61  5003.8  428.62  5014.6  433.59    5025  435.54  5123.9  434.65
  5202.6  436.53  5265.3  440.57  5357.6  444.82  5433.8  445.33  5490.8  444.21
  5623.7  446.11  5697.9   449.9  5713.2  453.22  5728.9  455.04  5746.1  453.46
#Mann= 13 ,-1 , 0
  3825.9     .05       0  4265.9     .16       0  4485.7     .05       0
  4671.2     .16       0  4772.5     .12       0  4891.9     .16       0
  4955.4     .12       0  4990.9     .07       0  4996.9     .12       0
  5202.6     .07       0  5265.3     .12       0  5357.6     .05       0
  5713.2     .08       0
Bank Sta=4974.1,5025
XS Rating Curve= 0 ,0
Exp/Cntr=0.3,0.1

Type RM Length L Ch R = 1 ,31775   ,933,933,933
BEGIN DESCRIPTION:
HOLMAN CREEK 36.0
END DESCRIPTION:
XS GIS Cut Line= 3
      3544184.87     10578917.35      3542848.03     10578926.03
      3542019.08     10579021.51
#Sta/Elev= 30
  3469.5  476.69  3642.3  476.64  3823.8  469.72  3952.3  463.24  4012.3  459.03
  4315.2  446.74  4352.3  444.32  4372.3  444.55  4472.8  441.12  4489.4  440.69
  4542.3  438.11  4622.3  437.33  4687.3  435.27  4772.3  433.66  4953.3  434.45
  4987.5  433.56  4993.5   430.4  5000.6  430.25  5003.3  429.75  5006.6  430.25
  5023.7  434.25  5033.8  434.91    5086  434.32  5124.4   433.6  5186.1  433.87
  5249.5  434.89  5315.6   438.2  5466.6  448.83  5537.1  451.14  5640.8  450.94
#Mann= 11 ,-1 , 0
  3469.5     .05       0  3823.8     .16       0  4315.2     .12       0
  4472.8     .16       0  4489.4     .07       0  4687.3     .12       0
  5000.6     .07       0  5006.6     .12       0    5086     .16       0
  5186.1     .07       0  5315.6     .05       0
Bank Sta=4987.5,5023.7
XS Rating Curve= 0 ,0
Exp/Cntr=0.3,0.1

Type RM Length L Ch R = 1 ,30842   ,18,18,18
BEGIN DESCRIPTION:
HOLMAN CREEK 34.03
END DESCRIPTION:
XS GIS Cut Line= 5
       3543124.9     10578275.09       3542111.9     10578246.44
      3541864.51     10578230.82      3541781.18     10578202.17
      3541076.23     10578187.86
#Sta/Elev= 30
    4139  449.43    4185  448.49  4257.9  447.02  4442.3  442.42    4542  437.41
    4712  432.61  4852.1  433.18  4972.1   432.1  4982.1  430.68  4989.1   426.5
  4991.9     426  4995.1   426.5  5002.1  427.14  5012.1  431.75  5022.1  432.96
  5102.2  440.59  5141.2  442.92    5254  438.86  5332.6  437.29  5352.6  437.76
  5459.6  435.56  5490.4  434.76  5527.5  436.04  5627.5  437.02  5837.5  443.11
  5856.2  444.25  5877.6  446.04  5927.6  447.62  6037.6  448.62  6193.5  453.88
#Mann= 8 ,-1 , 0
    4139     .05       0    4185     .08       0  4257.9     .05       0
  4989.1     .04       0  4995.1     .05       0    5254     .08       0
  5459.6     .05       0  5856.2     .08       0
#XS Ineff= 2 , 0
                         5159.09          442.87
Permanent Ineff=
       F       F
Bank Sta=4972.1,5022.1
XS Rating Curve= 0 ,0
Exp/Cntr=0.3,0.1

Type RM Length L Ch R = 1 ,30824   ,97,97,97
BEGIN DESCRIPTION:
HOLMAN CREEK 34.0
END DESCRIPTION:
XS GIS Cut Line= 5
      3543122.71     10578257.72      3542109.73     10578229.08
      3541862.34     10578213.45      3541779.01     10578184.81
      3541075.24     10578170.53
#Sta/Elev= 30
  4137.6  449.68  4173.9  448.83  4260.4  446.97  4438.3  442.31  4526.5  438.35
  4698.4  433.26  4918.5   433.3  4938.5  431.45  4978.5  430.94  4995.5   426.7
  4998.3   426.2  5001.5   426.7  5018.6  432.69  5088.6  439.66  5138.6  442.46
  5238.3  438.86  5318.9  437.13  5346.1  437.56  5417.4  435.26  5422.7  434.14
  5448.6  435.25  5455.2  434.39  5513.9  436.53  5583.9  436.43  5654.2  437.89
  5753.6  440.44  5851.9  444.33  5889.2  446.43  5894.2  444.84  6190.9  454.07
#Mann= 10 ,-1 , 0
  4137.6     .05       0  4173.9     .08       0  4260.4     .05       0
  4995.5     .04       0  5001.5     .05       0  5238.3     .08       0
  5455.2     .05       0  5654.2     .08       0  5753.6     .05       0
  5851.9     .08       0
#XS Ineff= 2 , 0
                         5147.73          442.61
Permanent Ineff=
       F       F
Bank Sta=4978.5,5018.6
XS Rating Curve= 0 ,0
Exp/Cntr=0.3,0.1

Type RM Length L Ch R = 1 ,30727   ,16,16,16
BEGIN DESCRIPTION:
HOLMAN CREEK 34.01
END DESCRIPTION:
XS GIS Cut Line= 3
      3543227.66      10578154.9       3542136.1     10578137.54
      3541107.49     10578076.77
#Sta/Elev= 30
  4056.7  452.41  4187.8  452.45  4286.7  450.54  4422.3  446.72  4583.3  438.52
  4632.3  435.59  4802.3  432.88  4903.6   432.9    4914  432.63  4972.4  431.85
  4989.4  426.45  4992.1  425.95  4995.4  426.45  5002.4  427.24  5022.4  432.71
  5132.4  437.78  5165.5  438.43    5197  436.72  5272.6   434.7  5382.8  435.38
  5412.8  431.15  5432.9  435.36    5473  436.21    5513  435.82  5563.1   437.5
  5670.7  438.71  5793.5  442.54  5913.7   443.3  5953.8  446.72  6178.8  452.96
#Mann= 11 ,-1 , 0
  4056.7     .08       0  4187.8     .05       0  4286.7     .08       0
  4583.3     .05       0  4903.6     .16       0    4914     .05       0
  4989.4     .04       0  4995.4     .05       0    5197     .08       0
    5473     .05       0  5670.7     .08       0
#XS Ineff= 2 , 0
                         5166.19          438.48
Permanent Ineff=
       F       F
Bank Sta=4972.4,5022.4
XS Rating Curve= 0 ,0
Exp/Cntr=0.3,0.1

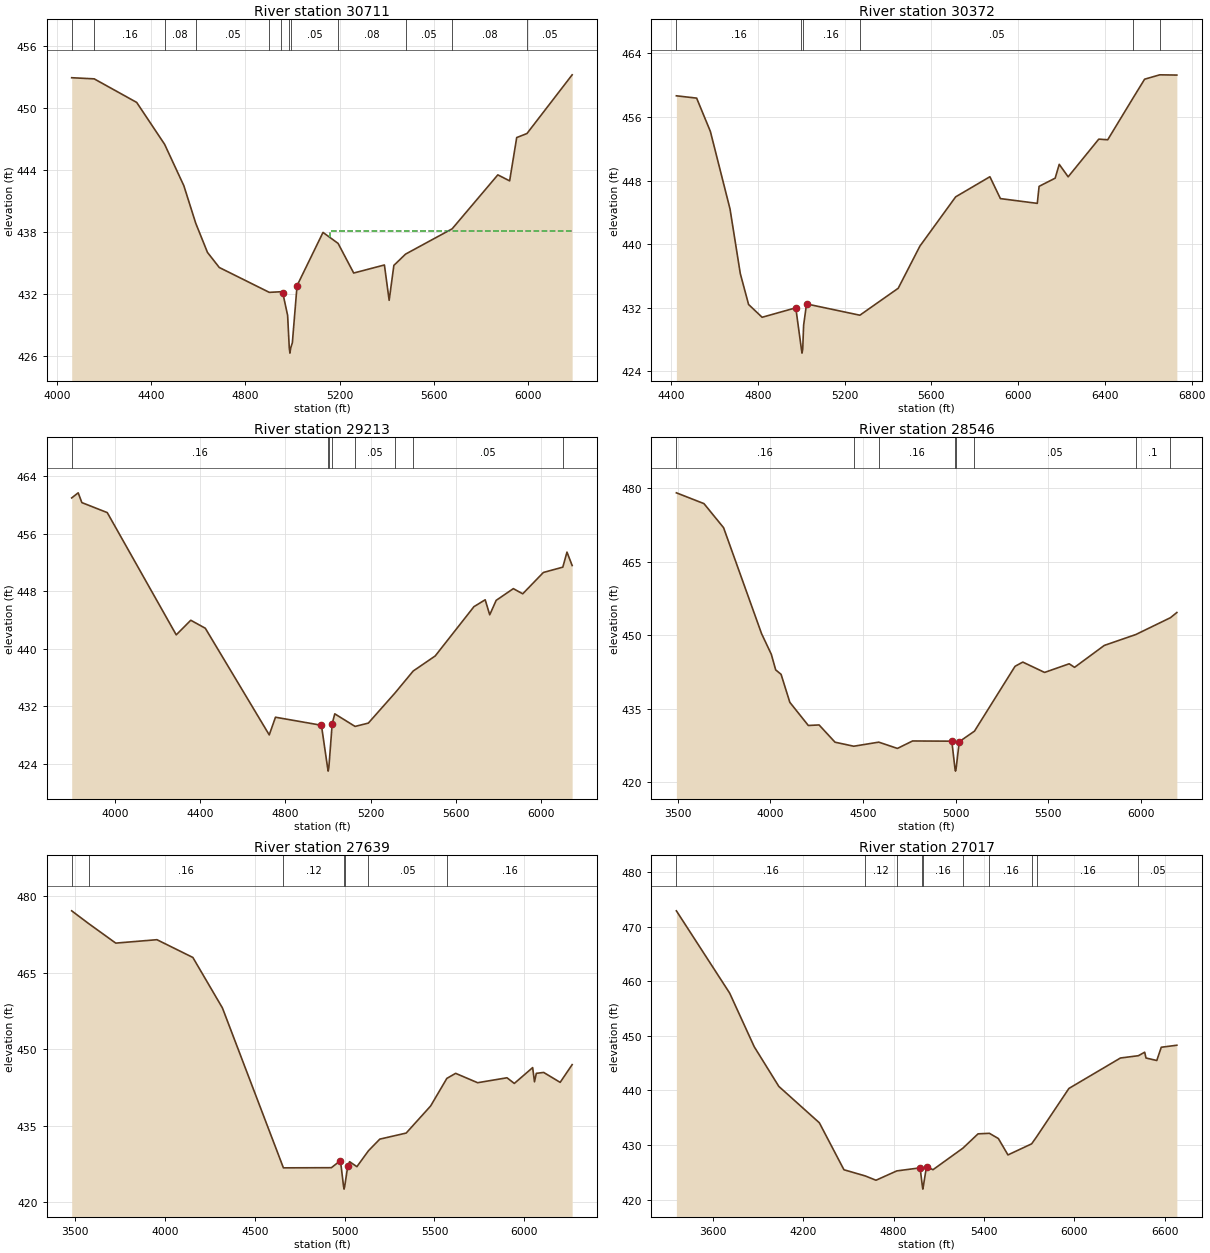
Type RM Length L Ch R = 1 ,30711   ,339,339,339
BEGIN DESCRIPTION:
HOLMAN CREEK 34.02
END DESCRIPTION:
XS GIS Cut Line= 3
      3543227.69     10578139.71       3542136.1     10578122.34
      3541107.42     10578061.58
#Sta/Elev= 30
  4063.1  452.92  4158.6  452.81  4338.7  450.53  4457.1  446.48  4538.7  442.47
  4589.1  438.84  4638.8  436.02  4688.8  434.56    4901  432.15  4950.5  432.21
  4958.8  432.04  4978.8  429.92  4985.8  426.77  4988.5  426.27  4991.8  426.77
  4998.8  427.27  5018.8   432.8  5128.8  437.95  5192.8  436.89    5259  434.02
  5389.2   434.8  5409.3  431.38  5429.3  434.76  5478.8  435.85  5676.5   438.3
  5870.1  443.52  5920.2  442.94  5950.2  447.13  5993.7  447.52  6185.3   453.2
#Mann= 12 ,-1 , 0
  4063.1     .08       0  4158.6     .16       0  4457.1     .08       0
  4589.1     .05       0    4901     .16       0  4950.5     .05       0
  4985.8     .04       0  4991.8     .05       0  5192.8     .08       0
  5478.8     .05       0  5676.5     .08       0  5993.7     .05       0
#XS Ineff= 2 , 0
                         5159.09           438.1
Permanent Ineff=
       F       F
Bank Sta=4958.8,5018.8
XS Rating Curve= 0 ,0
Exp/Cntr=0.3,0.1

Type RM Length L Ch R = 1 ,30372   ,1159,1159,1159
BEGIN DESCRIPTION:
HOLMAN CREEK 33.0
END DESCRIPTION:
XS GIS Cut Line= 3
      3542954.92     10577789.56      3542504.95     10577839.56
      3540706.06     10577389.83
#Sta/Elev= 30
  4424.8  458.67  4518.2  458.38  4581.5  454.19  4672.1  444.43  4719.4  436.31
  4757.6  432.42    4820  430.81  4975.2     432  5001.2   426.8  5003.9   426.3
  5007.2   426.8  5011.3   429.8  5024.8  432.49  5270.6  431.07  5447.4  434.46
  5547.3  439.76  5712.2  445.96    5870  448.49  5918.4  445.74  6088.5  445.14
  6096.8  447.28  6170.9  448.31  6189.6  450.05  6230.8  448.48  6371.9  453.22
  6413.1  453.14  6531.2  458.45  6583.2  460.76  6653.1  461.31  6731.8  461.28
#Mann= 6 ,-1 , 0
  4424.8     .16       0  5001.2     .07       0  5007.2     .16       0
  5270.6     .05       0  6531.2      .1       0  6653.1     .05       0
Bank Sta=4975.2,5024.8
XS Rating Curve= 0 ,0
Exp/Cntr=0.3,0.1

Type RM Length L Ch R = 1 ,29213   ,667,667,667
BEGIN DESCRIPTION:
HOLMAN CREEK 31.0
END DESCRIPTION:
XS GIS Cut Line= 3
      3543259.49     10577467.46      3541540.76      10576651.5
        3541098.     10576599.41
#Sta/Elev= 30
  3797.7  461.01  3828.2  461.72  3845.4  460.36  3964.6  458.97  4288.3  441.96
  4356.5  443.99  4424.7  442.88  4724.7  428.04    4754   430.5  4969.6  429.38
  4998.4   423.5  5001.2     423  5004.4   423.5  5020.1  429.58  5032.2  430.97
  5127.5  429.22  5189.6  429.68  5314.5  433.86  5400.3  436.93  5503.4  439.02
  5685.2  445.88    5738  446.84  5759.3  444.75  5789.6  446.76  5870.1  448.39
  5914.2  447.67  6011.1  450.64  6102.3  451.38  6121.8  453.47  6146.1  451.61
#Mann= 8 ,-1 , 0
  3797.7     .16       0  4998.4     .07       0  5004.4     .16       0
  5020.1     .12       0  5127.5     .05       0  5314.5     .16       0
  5400.3     .05       0  6102.3      .1       0
Bank Sta=4969.6,5020.1
XS Rating Curve= 0 ,0
Exp/Cntr=0.3,0.1

Type RM Length L Ch R = 1 ,28546   ,907,907,907
BEGIN DESCRIPTION:
HOLMAN CREEK 29.0
END DESCRIPTION:
XS GIS Cut Line= 3
      3543598.89     10576907.79      3542361.92     10576378.28
      3541012.11     10576269.78
#Sta/Elev= 30
  3493.3  479.06  3642.1  476.86  3747.9  471.95  3952.9  450.33  4005.5  446.12
    4029  442.95  4058.1  442.04  4105.2  436.34    4205  431.61  4263.1  431.72
  4349.1   428.2    4450  427.38  4585.1  428.21  4685.7  426.93  4767.3  428.45
  4979.1  428.41  4996.2   422.8  4998.9   422.3  5002.2   422.8  5019.2   428.3
  5101.2  430.45  5320.2  443.68  5361.9  444.54  5479.5  442.43  5612.1  444.19
  5641.2  443.47  5801.7  447.94  5971.7  450.16  6158.4  453.59    6193  454.65
#Mann= 8 ,-1 , 0
  3493.3     .16       0    4450     .12       0  4585.1     .16       0
  4996.2     .07       0  5002.2     .16       0  5101.2     .05       0
  5971.7      .1       0  6158.4     .05       0
Bank Sta=4979.1,5019.2
XS Rating Curve= 0 ,0
Exp/Cntr=0.3,0.1

Type RM Length L Ch R = 1 ,27639   ,622,622,622
BEGIN DESCRIPTION:
HOLMAN CREEK 27.0
END DESCRIPTION:
XS GIS Cut Line= 4
      3544054.66     10576842.71      3542934.84     10576000.68
        3542414.     10575909.53      3541576.75     10575740.35
#Sta/Elev= 30
  3481.8  477.18    3576  474.68  3726.9  470.84    3956  471.51  4155.9  468.02
  4320.4   458.1  4659.6   426.7  4926.3  426.73    4977  428.12  4994.3  423.02
  4997.1  422.52  5000.3  423.02  5017.4  426.98  5027.8  427.91  5068.4  426.93
  5132.7  430.06  5195.8  432.34  5342.5  433.53  5478.3  438.84  5568.8  444.27
  5617.6  445.26    5740  443.42  5903.3  444.39  5944.1  443.28  6046.1  446.39
  6056.3   443.6  6066.5  445.26  6107.3  445.44  6199.1  443.49  6265.8  446.97
#Mann= 7 ,-1 , 0
  3481.8     .12       0    3576     .16       0  4659.6     .12       0
  4994.3     .07       0  5000.3     .12       0  5132.7     .05       0
  5568.8     .16       0
Bank Sta=4977,5017.4
XS Rating Curve= 0 ,0
Exp/Cntr=0.3,0.1

Type RM Length L Ch R = 1 ,27017   ,738,738,738
BEGIN DESCRIPTION:
HOLMAN CREEK 25.0
END DESCRIPTION:
XS GIS Cut Line= 4
      3544306.34     10576456.39      3543225.64     10575514.57
      3542448.73     10575241.13      3541389.67     10575136.96
#Sta/Elev= 30
  3358.7  472.92  3712.1  457.85  3875.4  448.01  4038.7  440.74  4307.4  434.08
  4470.7  425.47  4611.8  424.34  4683.3  423.55  4821.6  425.26  4976.2  425.82
  4991.4  422.42  4994.2  421.92  4997.4  422.42  5018.6  426.05  5061.7  425.48
  5260.3  429.43  5360.7  432.05    5436  432.15  5495.6  431.19  5559.2  428.19
  5716.4  430.22  5749.6  431.52  5963.6  440.37  6305.8  445.95  6424.8  446.37
  6466.5  447.01  6475.3  445.95  6546.9  445.49  6576.6  447.92    6680  448.29
#Mann= 10 ,-1 , 0
  3358.7     .16       0  4611.8     .12       0  4821.6     .16       0
  4991.4     .07       0  4997.4     .16       0  5260.3     .05       0
    5436     .16       0  5716.4     .05       0  5749.6     .16       0
  6424.8     .05       0
Bank Sta=4976.2,5018.6
XS Rating Curve= 0 ,0
Exp/Cntr=0.3,0.1