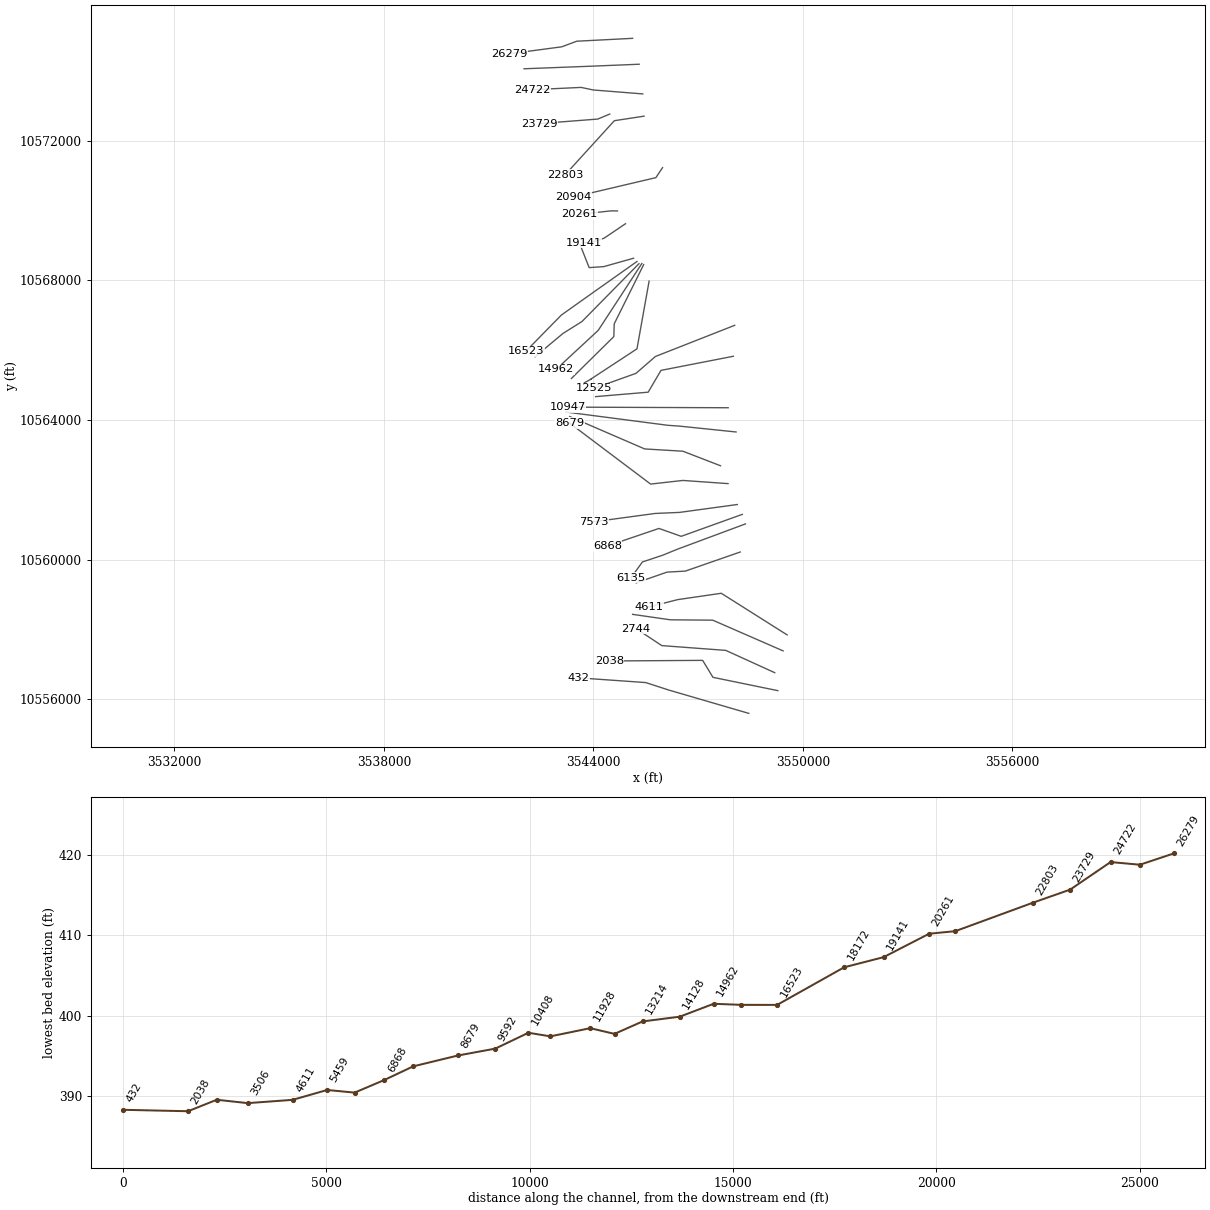
HEC-RAS study HOLMAN CREEK.prj: HOLMAN CREEK Base Level Engineering

--- HOLMAN CREEK.g01 (geometry) --- (continued)

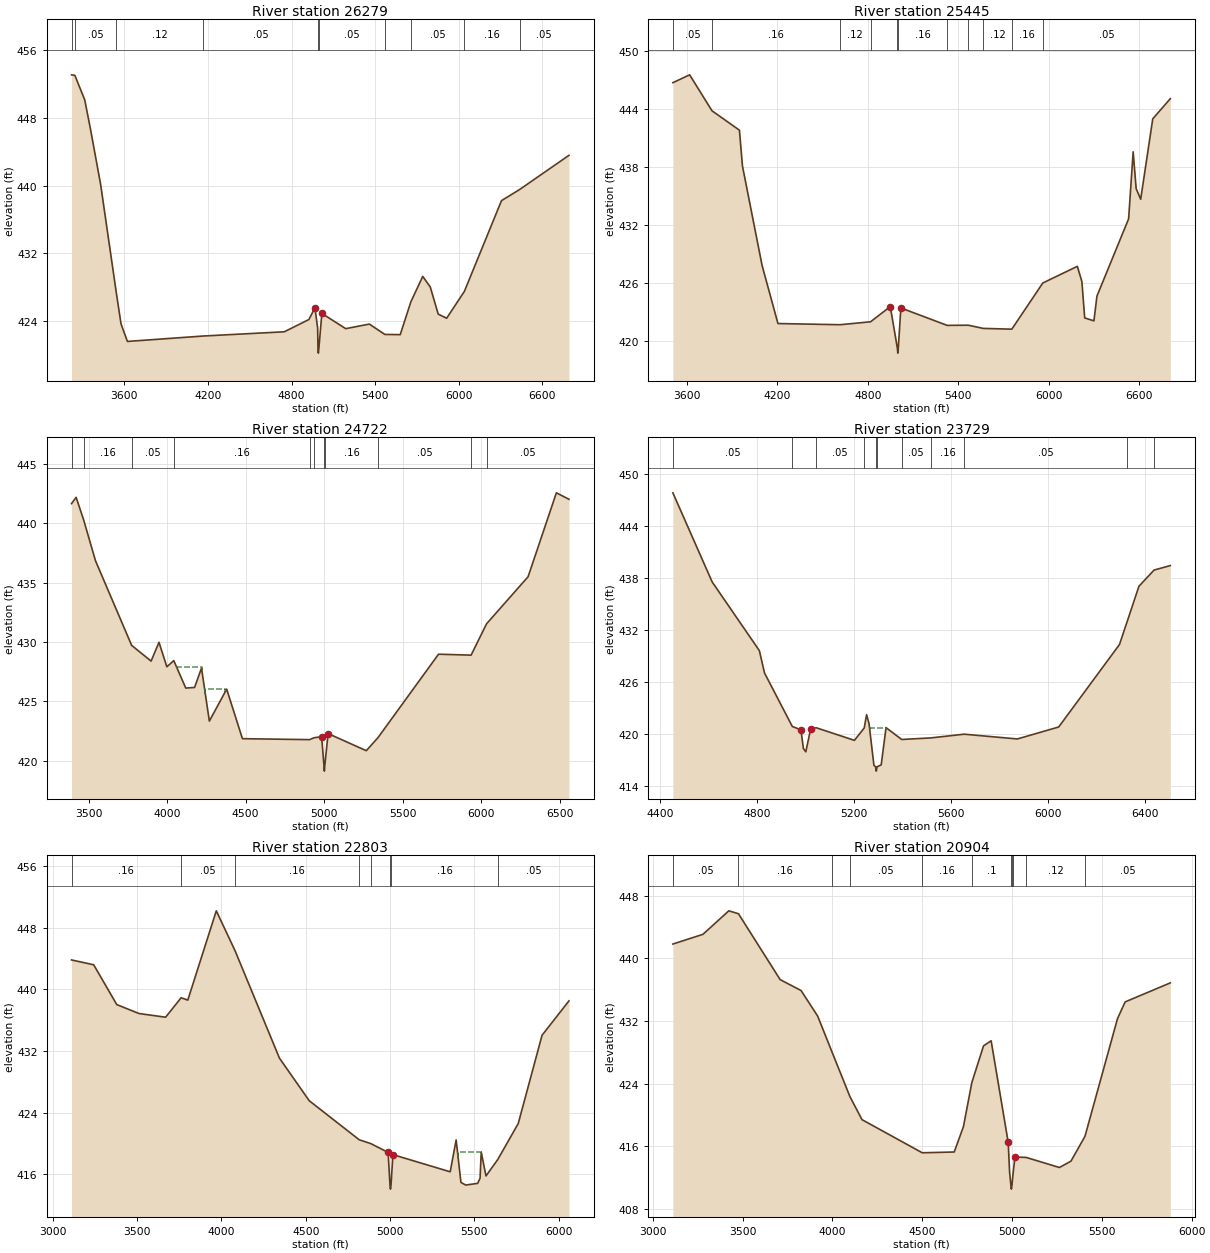
Type RM Length L Ch R = 1 ,26279   ,834,834,834
BEGIN DESCRIPTION:
HOLMAN CREEK 23.0
END DESCRIPTION:
XS GIS Cut Line= 4
      3545126.69     10574937.31      3543525.12     10574854.85
      3543095.43     10574694.26      3541602.33      10574494.6
#Sta/Elev= 30
  3221.7  453.08  3245.6  453.02  3316.4  450.12  3356.5  446.77  3430.4  440.14
  3542.1  427.44  3576.8  423.66  3622.7  421.59  4166.2  422.23  4748.3  422.73
  4924.7  424.18  4967.9  425.56  4987.5  423.18  4989.9  420.71  4992.6  420.21
  4995.9  420.71  5017.8   424.9  5188.9   423.1  5358.1  423.64  5469.6  422.42
    5580  422.39  5656.1  426.26  5741.5  429.27  5795.6  428.02  5852.4  424.82
    5913  424.33  6040.2   427.5  6306.5  438.22  6436.3  439.53  6790.5  443.57
#Mann= 10 ,-1 , 0
  3221.7     .08       0  3245.6     .05       0  3542.1     .12       0
  4166.2     .05       0  4989.9     .03       0  4995.9     .05       0
  5469.6      .1       0  5656.1     .05       0  6040.2     .16       0
  6436.3     .05       0
Bank Sta=4967.9,5017.8
XS Rating Curve= 0 ,0
Exp/Cntr=0.3,0.1

Type RM Length L Ch R = 1 ,25445   ,723,723,723
BEGIN DESCRIPTION:
HOLMAN CREEK 22.0
END DESCRIPTION:
XS GIS Cut Line= 3
      3545313.33     10574195.12       3543933.1      10574138.7
       3542015.9     10574064.96
#Sta/Elev= 30
  3507.1  446.69  3618.4   447.5  3766.7  443.79  3948.7  441.79  3968.7   438.1
  4098.8  427.85  4204.2  421.85  4616.4  421.73  4818.3  422.03  4949.5   423.6
  4996.6   419.3  4999.3   418.8  5002.6   419.3  5019.6  423.46    5327  421.66
  5467.1  421.68  5565.9  421.35  5755.7  421.27  5961.3  426.03  6190.4  427.75
  6220.5  426.19  6239.2  422.43  6300.5  422.13  6320.5  424.68  6530.7  432.65
  6560.7  439.56  6580.7  435.76  6610.8  434.67  6690.8  442.96  6807.1  445.04
#Mann= 11 ,-1 , 0
  3507.1     .05       0  3766.7     .16       0  4616.4     .12       0
  4818.3     .16       0  4996.6     .07       0  5002.6     .16       0
    5327     .12       0  5467.1     .16       0  5565.9     .12       0
  5755.7     .16       0  5961.3     .05       0
Bank Sta=4949.5,5019.6
XS Rating Curve= 0 ,0
Exp/Cntr=0.3,0.1

Type RM Length L Ch R = 1 ,24722   ,993,993,993
BEGIN DESCRIPTION:
HOLMAN CREEK 20.0
END DESCRIPTION:
XS GIS Cut Line= 4
      3545417.47     10573344.43      3543998.21     10573457.28
      3543650.98     10573531.06      3542262.12     10573465.96
#Sta/Elev= 30
  3390.9  441.64  3420.1  442.17  3467.4   440.3  3543.4  436.84    3774  429.71
  3897.9  428.39    3948  429.97  3998.2  427.91  4042.4  428.43  4118.6  426.12
  4174.8  426.17  4218.9   427.8    4269  423.34  4379.4  426.03  4479.7  421.86
  4907.7  421.78  4936.5  421.94  4984.4  422.03  4998.9  419.63  5001.7  419.13
  5004.9  419.63  5025.3  422.29  5268.8  420.85  5343.5  421.95  5729.1  428.97
  5936.5  428.89  6035.3  431.53  6299.7  435.49  6479.9  442.55    6560  442.01
#Mann= 11 ,-1 , 0
  3390.9     .05       0  3467.4     .16       0    3774     .05       0
  4042.4     .16       0  4907.7     .12       0  4936.5     .16       0
  4998.9     .07       0  5004.9     .16       0  5343.5     .05       0
  5936.5     .08       0  6035.3     .05       0
#XS Ineff= 2 ,-1
 4063.64 4220.45  427.88 4243.18 4368.18     426
Permanent Ineff=
       F       F
Bank Sta=4984.4,5025.3
XS Rating Curve= 0 ,0
Exp/Cntr=0.3,0.1

Type RM Length L Ch R = 1 ,23729   ,926,926,926
BEGIN DESCRIPTION:
HOLMAN CREEK 18.0
END DESCRIPTION:
XS GIS Cut Line= 3
       3544471.3     10572767.18      3544128.41     10572623.94
      3542453.07     10572493.73
#Sta/Elev= 30
  4453.1   447.8  4615.2  437.52  4809.9   429.6    4831  427.03  4945.8  420.85
  4981.5  420.46  4991.5  418.31  5001.5  417.93  5021.6  420.59  5044.7   420.7
  5202.1  419.25  5242.5  420.68  5252.3  422.21  5262.3  421.18  5282.4  416.38
  5289.4   416.2  5292.2   415.7  5295.4   416.2  5312.5  416.42  5332.5  420.72
    5397  419.35  5516.9  419.53  5654.6  419.96  5874.2  419.41  6044.7  420.79
  6295.4   430.3  6326.6   432.9  6375.7  437.02  6438.1  438.89  6505.1  439.41
#Mann= 11 ,-1 , 0
  4453.1     .05       0  4945.8     .16       0  5044.7     .05       0
  5242.5     .16       0  5289.4     .07       0  5295.4     .16       0
    5397     .05       0  5516.9     .16       0  5654.6     .05       0
  6326.6     .16       0  6438.1     .05       0
#XS Ineff= 1 ,-1
 5264.77 5331.25  420.65
Permanent Ineff=
       F
Bank Sta=4981.5,5021.6
XS Rating Curve= 0 ,0
Exp/Cntr=0.3,0.1

Type RM Length L Ch R = 1 ,22803   ,1899,1899,1899
BEGIN DESCRIPTION:
HOLMAN CREEK 17.0
END DESCRIPTION:
XS GIS Cut Line= 3
      3545453.53     10572707.05      3544602.83     10572576.84
      3543196.82     10571031.98
#Sta/Elev= 30
  3111.3  443.82  3242.7  443.19  3379.6  438.02  3511.5  436.86  3669.1  436.38
  3761.2  438.91  3800.7   438.6  3969.7   450.2  4081.3     445    4344  431.07
  4520.9  425.53  4817.2  420.46  4885.3  419.97  4988.5  418.82  4999.7  414.55
  5002.4  414.05  5005.7  414.55  5016.9  418.53  5356.7   416.3  5391.9  420.44
  5420.3  414.92  5448.6  414.58  5519.6   414.8  5533.8  415.47  5540.5  418.85
  5568.9  415.76  5639.1  417.91  5760.1  422.57  5901.4  434.04  6060.8   438.5
#Mann= 8 ,-1 , 0
  3111.3     .16       0  3761.2     .05       0  4081.3     .16       0
  4817.2     .12       0  4885.3     .16       0  4999.7     .07       0
  5005.7     .16       0  5639.1     .05       0
#XS Ineff= 1 ,-1
 5404.26 5543.47   418.9
Permanent Ineff=
       F
Bank Sta=4988.5,5016.9
XS Rating Curve= 0 ,0
Exp/Cntr=0.3,0.1

Type RM Length L Ch R = 1 ,20904   ,643,643,643
BEGIN DESCRIPTION:
HOLMAN CREEK 15.0
END DESCRIPTION:
XS GIS Cut Line= 3
      3545983.02     10571231.34      3545792.06      10570944.9
        3543431.     10570389.35
#Sta/Elev= 30
  3111.2  441.81  3278.6  443.05  3422.8  446.05  3476.4  445.68  3708.5  437.27
  3825.2  435.87  3917.7   432.6  3996.6  428.07  4097.2  422.33  4164.3  419.39
  4499.9  415.16  4677.9  415.26  4729.3  418.51    4776  424.13  4841.1  428.81
  4883.4  429.46  4978.5  416.49  4986.1  412.73  4993.4  411.02  4996.1  410.52
  4999.4  411.02  5003.2  411.98  5015.7  414.61  5078.2  414.57  5263.5  413.28
  5327.8  414.09  5405.9  417.26  5587.1  432.29  5629.5  434.42    5881  436.85
#Mann= 11 ,-1 , 0
  3111.2     .05       0  3476.4     .16       0  3996.6      .1       0
  4097.2     .05       0  4499.9     .16       0    4776      .1       0
  4993.4     .07       0  4999.4      .1       0  5003.2     .16       0
  5078.2     .12       0  5405.9     .05       0
Bank Sta=4978.5,5015.7
XS Rating Curve= 0 ,0
Exp/Cntr=0.3,0.1

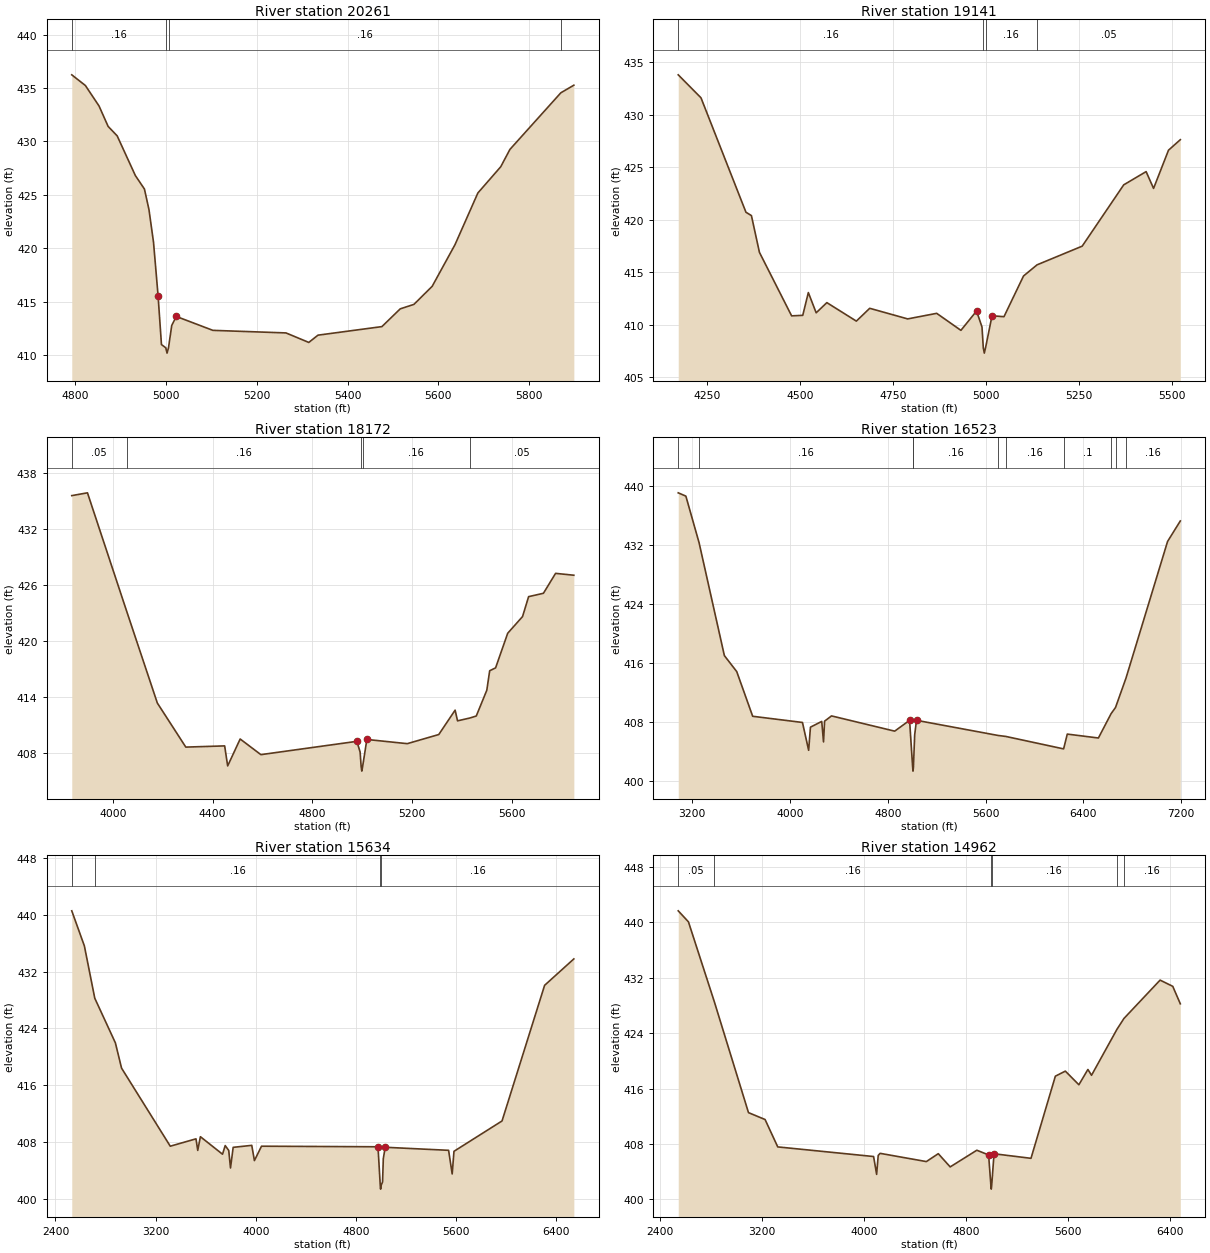
Type RM Length L Ch R = 1 ,20261   ,1120,1120,1120
BEGIN DESCRIPTION:
HOLMAN CREEK 13.0
END DESCRIPTION:
XS GIS Cut Line= 3
      3544692.09     10569991.64      3544492.11     10569991.64
      3543592.12     10569891.64
#Sta/Elev= 30
  4792.8  436.23  4822.8  435.23  4852.8  433.32  4872.8  431.41  4892.8  430.52
  4932.8  426.81  4952.8  425.55  4962.8  423.62  4972.8  420.57  4982.8  415.59
  4990.3     411  4999.8   410.7  5002.6   410.2  5005.8   410.7  5012.9  412.79
    5023  413.63  5103.5  412.33  5264.4  412.09  5314.7   411.2  5334.9  411.88
  5475.7  412.68    5516  414.34  5546.2  414.76  5586.4  416.45  5636.7  420.35
    5687  425.18  5737.3  427.63  5757.5  429.25  5869.7  434.55  5898.3  435.26
#Mann= 4 ,-1 , 0
  4792.8     .16       0  4999.8     .07       0  5005.8     .16       0
  5869.7     .05       0
Bank Sta=4982.8,5023
XS Rating Curve= 0 ,0
Exp/Cntr=0.3,0.1

Type RM Length L Ch R = 1 ,19141   ,969,969,969
BEGIN DESCRIPTION:
HOLMAN CREEK 12.0
END DESCRIPTION:
XS GIS Cut Line= 4
       3544922.7     10569624.82      3544306.37     10569208.14
       3543954.8      10569095.3      3543720.46     10569082.28
#Sta/Elev= 30
  4173.5  433.79  4234.6   431.6  4355.3   420.7    4370  420.38  4391.5  416.88
  4477.9  410.83  4507.8  410.88  4522.8  413.05  4543.8  411.12  4572.5  412.09
  4651.7  410.33  4687.6  411.55  4789.5  410.54  4867.4  411.07  4932.4  409.45
  4974.4  411.29    4989  409.77  4992.5  407.78  4995.2  407.28  4998.5  407.78
  5015.9  410.84    5048  410.75  5100.5  414.63  5136.8  415.69    5258  417.47
  5369.5  423.31  5429.6  424.57  5449.6  422.97  5489.7  426.61  5521.4  427.61
#Mann= 4 ,-1 , 0
  4173.5     .16       0  4992.5     .07       0  4998.5     .16       0
  5136.8     .05       0
Bank Sta=4974.4,5015.9
XS Rating Curve= 0 ,0
Exp/Cntr=0.3,0.1

Type RM Length L Ch R = 1 ,18172   ,1649,1649,1649
BEGIN DESCRIPTION:
HOLMAN CREEK 11.0
END DESCRIPTION:
XS GIS Cut Line= 4
      3545152.71     10568635.23      3544301.27     10568395.55
      3543881.02     10568366.13      3543620.59     10569025.88
#Sta/Elev= 30
  3834.8  435.61  3897.8  435.91  4054.6  423.24  4178.3  413.33  4292.5   408.6
  4448.4  408.73  4460.5  406.58  4510.7  409.47  4593.8  407.79  4979.1  409.22
  4992.1  408.07  4996.2  406.52  4998.9  406.02  5002.2  406.52  5019.2  409.42
  5181.3  408.97  5307.8  409.95  5373.4  412.57  5383.1  411.42  5433.3  411.73
  5458.3  411.94  5500.6  414.71  5512.1   416.8  5535.8  417.11  5584.5  420.83
    5644  422.62  5668.4  424.76  5727.8  425.12  5776.6  427.26  5849.9  427.06
#Mann= 5 ,-1 , 0
  3834.8     .05       0  4054.6     .16       0  4996.2     .07       0
  5002.2     .16       0  5433.3     .05       0
Bank Sta=4979.1,5019.2
XS Rating Curve= 0 ,0
Exp/Cntr=0.3,0.1

Type RM Length L Ch R = 1 ,16523   ,889,889,889
BEGIN DESCRIPTION:
HOLMAN CREEK 10.0
END DESCRIPTION:
XS GIS Cut Line= 4
      3545249.75     10568541.58      3543770.62     10567494.72
      3543083.12     10567005.14      3542067.51      10565968.7
#Sta/Elev= 30
  3085.2  439.13  3147.7  438.68  3255.8  432.35  3462.7  417.02  3563.7  414.85
  3694.2  408.78  4101.5  407.94    4152  404.16  4166.8   407.3    4259  408.08
  4273.8   405.3  4282.5  408.12  4339.1  408.83    4856  406.76  4977.7  408.23
    5003  401.83  5005.7  401.33    5009  401.83  5019.5  406.27  5034.3  408.23
  5699.7  406.18  5765.1  406.04  6237.8  404.35  6267.8  406.36  6522.4  405.83
  6625.8  409.12  6662.5  409.98    6748  413.96  7088.1  432.52  7192.4  435.31
#Mann= 10 ,-1 , 0
  3085.2     .05       0  3255.8     .16       0    5003     .07       0
    5009     .16       0  5699.7      .1       0  5765.1     .16       0
  6237.8      .1       0  6625.8     .16       0  6662.5      .1       0
    6748     .16       0
Bank Sta=4977.7,5034.3
XS Rating Curve= 0 ,0
Exp/Cntr=0.3,0.1

Type RM Length L Ch R = 1 ,15634   ,672,672,672
BEGIN DESCRIPTION:
HOLMAN CREEK 9.1
END DESCRIPTION:
XS GIS Cut Line= 4
      3545307.09     10568479.11      3543676.87     10566822.85
      3543129.99      10566479.1       3542333.1     10565812.42
#Sta/Elev= 30
  2530.1  440.57  2630.8  435.62  2713.8  428.25  2878.3  421.96  2927.8  418.39
  3316.7  407.39  3521.9  408.43    3536   406.8  3557.2  408.73  3733.9  406.26
  3755.2  407.48  3783.5  406.79  3797.6  404.32  3818.8  407.23  3967.3  407.51
  3988.5  405.36  4045.1  407.39  4975.2  407.31  4993.4  401.84  4996.1  401.34
  4999.4  401.84  5011.7  402.35  5017.6  405.64  5032.9  407.24  5538.9  406.81
  5567.6  403.48  5581.9  406.67  5965.7  410.95  6305.6  430.07    6539  433.79
#Mann= 4 ,-1 , 0
  2530.1     .05       0  2713.8     .16       0  4993.4     .07       0
  4999.4     .16       0
Bank Sta=4975.2,5032.9
XS Rating Curve= 0 ,0
Exp/Cntr=0.3,0.1

Type RM Length L Ch R = 1 ,14962   ,834,834,834
BEGIN DESCRIPTION:
HOLMAN CREEK 7.2
END DESCRIPTION:
XS GIS Cut Line= 3
      3545390.42     10568484.33      3544140.41     10566567.64
      3542932.08     10565447.85
#Sta/Elev= 30
    2545  441.68    2625  440.09  2827.2  428.59  3095.8  412.52  3225.6  411.53
  3325.1  407.57  4076.4  406.18  4100.2   403.6  4112.6  406.34  4127.7  406.64
  4489.9  405.45  4583.4  406.59  4676.9  404.68  4885.6  407.09    4978  406.41
    4996  401.97  4998.7  401.47    5002  401.97  5020.5  406.58  5310.2  405.92
  5501.3  417.79  5579.5  418.52  5685.6  416.55  5756.4  418.76  5784.8  417.92
  5984.4  424.57    6039  426.13  6322.3  431.67  6421.5  430.77  6480.7  428.25
#Mann= 6 ,-1 , 0
    2545     .05       0  2827.2     .16       0    4996     .07       0
    5002     .16       0  5984.4     .05       0    6039     .16       0
Bank Sta=4978,5020.5
XS Rating Curve= 0 ,0
Exp/Cntr=0.3,0.1

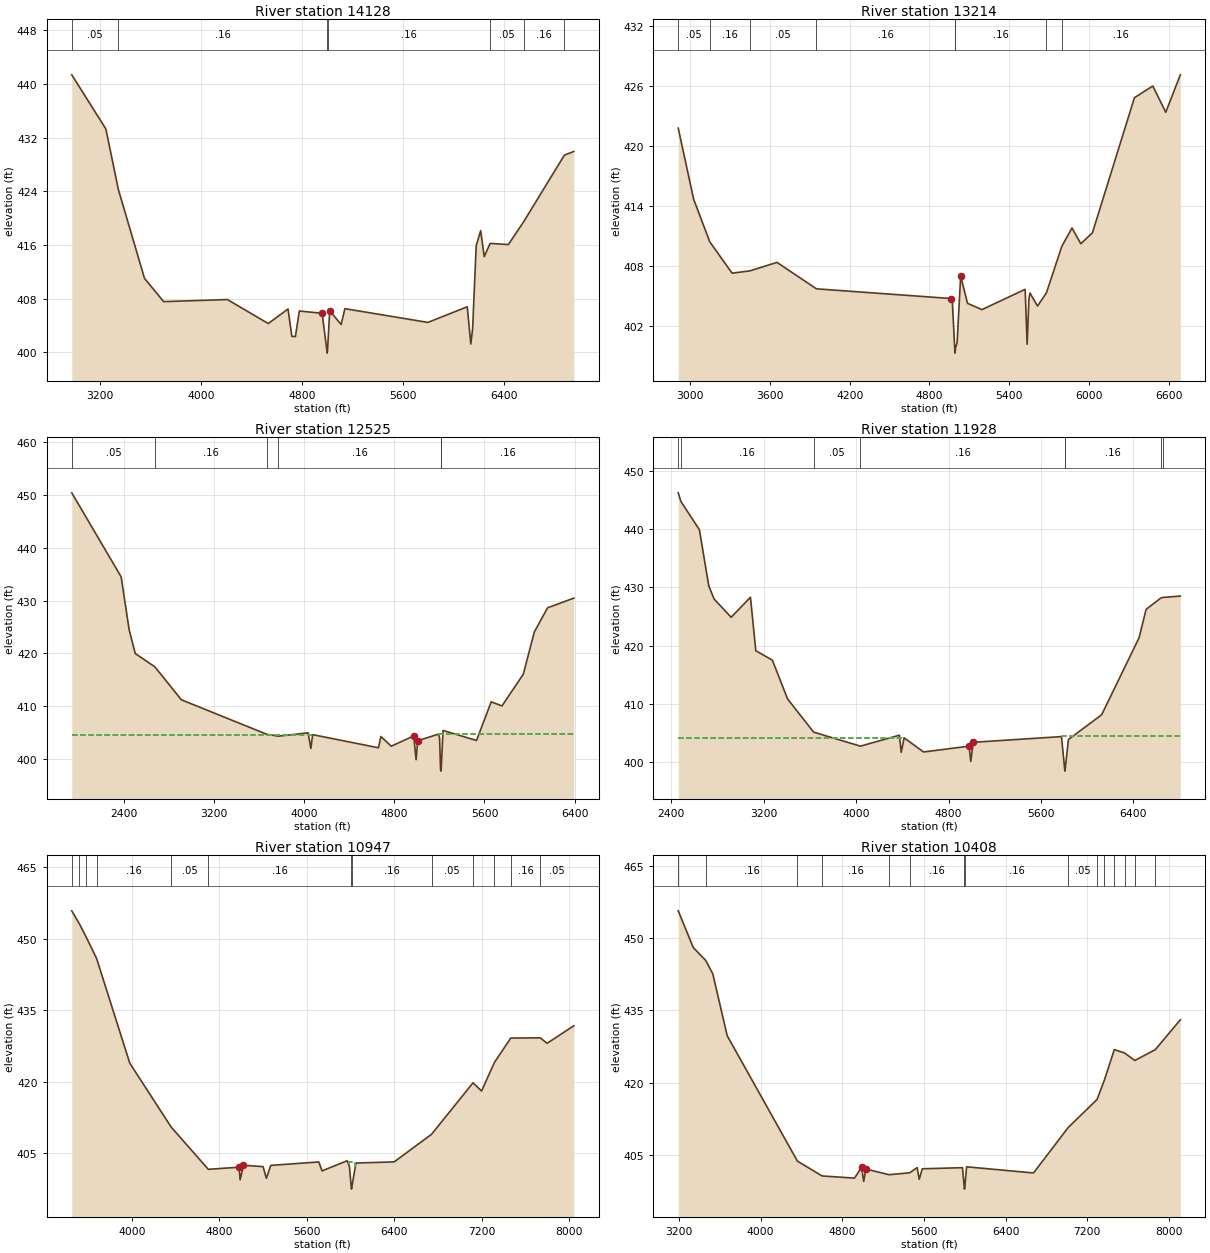
Type RM Length L Ch R = 1 ,14128   ,914,914,914
BEGIN DESCRIPTION:
HOLMAN CREEK 9.0
END DESCRIPTION:
XS GIS Cut Line= 4
      3545442.47     10568453.02      3544598.74     10566755.14
      3544588.32     10566390.56      3543372.35     10565189.54
#Sta/Elev= 30
  2980.4  441.36  3249.9  433.29  3348.9  424.26  3555.6  411.01  3706.9  407.54
  4210.9  407.85  4534.1  404.27  4690.4  406.44  4720.5  402.36  4748.5  402.33
  4779.8  406.14  4959.9   405.8  4996.9  400.36  4999.7  399.86  5002.9  400.36
  5019.9  406.18    5110  404.13    5140  406.49  5796.3  404.44  6107.4  406.77
  6135.7  401.22  6149.8  403.49  6178.1  415.89  6213.5  418.12  6241.8  414.25
  6288.3  416.22  6432.7  416.05  6553.3  419.45  6875.8  429.39  6950.2  429.93
#Mann= 7 ,-1 , 0
  2980.4     .05       0  3348.9     .16       0  4996.9     .07       0
  5002.9     .16       0  6288.3     .05       0  6553.3     .16       0
  6875.8     .05       0
Bank Sta=4959.9,5019.9
XS Rating Curve= 0 ,0
Exp/Cntr=0.3,0.1

Type RM Length L Ch R = 1 ,13214   ,689,689,689
BEGIN DESCRIPTION:
HOLMAN CREEK 7.0
END DESCRIPTION:
XS GIS Cut Line= 5
      3545597.87      10567979.1      3545250.65     10566038.99
      3543935.55     10565175.28      3543944.23     10565175.28
      3543745.83     10565067.45
#Sta/Elev= 30
  2909.9  421.81    3026  414.68  3147.4  410.42  3315.2  407.28  3448.5  407.51
  3653.1  408.36  3950.3  405.71  4963.4  404.74  4972.5  404.54  4990.6  399.77
  4993.3  399.27  4996.6  399.77  5008.7  400.32  5035.7  406.99    5087  404.26
  5195.5  403.63  5520.9  405.66    5536  400.16  5549.1  404.64  5557.1  405.29
  5614.3  403.99  5681.4  405.32  5796.8  409.97  5873.4   411.8  5939.8  410.23
  6027.2  411.32  6343.5  424.86  6481.7  426.03  6579.1   423.4  6688.7  427.15
#Mann= 8 ,-1 , 0
  2909.9     .05       0  3147.4     .16       0  3448.5     .05       0
  3950.3     .16       0  4990.6     .07       0  4996.6     .16       0
  5681.4     .05       0  5796.8     .16       0
Bank Sta=4963.4,5035.7
XS Rating Curve= 0 ,0
Exp/Cntr=0.3,0.1

Type RM Length L Ch R = 1 ,12525   ,597,597,597
BEGIN DESCRIPTION:
HOLMAN CREEK 8.0
END DESCRIPTION:
XS GIS Cut Line= 4
      3548049.59     10566713.18      3545778.72     10565819.53
      3545223.16     10565336.89      3544022.16     10564906.48
#Sta/Elev= 30
  1940.5  450.37  2378.4  434.48  2449.1   424.5  2503.3  419.97  2677.4  417.45
  2912.2  411.22  3668.5   404.7  3773.2  404.33  4036.2  404.97  4060.6  402.02
  4076.3  404.62  4660.5  402.14  4681.3  404.27  4773.8  402.44  4972.5  404.38
  4993.8   399.9    5008  403.47  5192.3  404.72    5202  404.03  5210.5  398.22
  5213.3  397.72  5216.5  398.22  5232.8  405.42  5529.7  403.51  5659.7  410.83
  5755.3  410.05  5944.3  416.05  6042.1  424.04  6159.6  428.62  6392.6  430.45
#Mann= 6 ,-1 , 0
  1940.5     .05       0  2677.4     .16       0  3668.5     .05       0
  3773.2     .16       0  5210.5     .07       0  5216.5     .16       0
#XS Ineff= 2 , 0
         4076.47  404.64 5191.96          404.75
Permanent Ineff=
       F       F
Bank Sta=4972.5,5008
XS Rating Curve= 0 ,0
Exp/Cntr=0.3,0.1

Type RM Length L Ch R = 1 ,11928   ,981,981,981
BEGIN DESCRIPTION:
HOLMAN CREEK 6.0
END DESCRIPTION:
XS GIS Cut Line= 4
       3548011.9     10565826.07      3545938.67     10565421.91
      3545571.49     10564796.91      3544066.72     10564669.34
#Sta/Elev= 30
  2458.9  446.22  2481.4  444.76  2642.1  439.89  2723.6  430.23  2769.5  427.99
  2917.2  424.85  3084.2  428.29  3130.7   419.1  3273.8  417.49  3406.2  410.81
  3631.7  405.12  4036.4  402.72  4374.1   404.6  4389.5  401.66  4414.8  404.15
  4583.1  401.72  4977.4  402.72  4991.8   400.1  5013.3  403.38  5777.4  404.36
  5804.2  398.93    5807  398.43  5810.2  398.93  5837.4  403.85  6125.6  408.12
  6449.5  421.35  6509.8   426.2  6636.5  428.14  6652.1  428.25  6806.2  428.49
#Mann= 8 ,-1 , 0
  2458.9     .05       0  2481.4     .16       0  3631.7     .05       0
  4036.4     .16       0  5804.2     .07       0  5810.2     .16       0
  6636.5     .05       0  6652.1     .16       0
#XS Ineff= 2 , 0
         4414.84  404.18 5777.45          404.38
Permanent Ineff=
       F       F
Bank Sta=4977.4,5013.3
XS Rating Curve= 0 ,0
Exp/Cntr=0.3,0.1

Type RM Length L Ch R = 1 ,10947   ,539,539,539
BEGIN DESCRIPTION:
HOLMAN CREEK 8.1
END DESCRIPTION:
XS GIS Cut Line= 2
      3547863.46     10564350.63      3543267.19     10564367.99
#Sta/Elev= 30
  3448.9  455.85  3518.7  453.12  3583.2  450.25  3675.8  445.87  3980.3  423.85
  4359.9  410.41    4699  401.57  4980.3  402.01  4990.3  399.36  5020.3  402.43
  5200.3  402.13  5230.3  399.69  5270.3  402.39  5710.3  403.12  5740.3  401.24
  5970.3  403.38  5990.3  402.22  6007.3  397.91    6010  397.41  6013.3  397.91
  6050.3  402.89  6400.3  403.13  6742.8  408.93  7122.4  419.74  7200.3  418.01
  7317.7  423.99  7467.3  429.13  7738.2  429.18  7800.3  428.03  8045.2  431.72
#Mann= 13 ,-1 , 0
  3448.9     .05       0  3518.7      .1       0  3583.2     .05       0
  3675.8     .16       0  4359.9     .05       0    4699     .16       0
  6007.3     .07       0  6013.3     .16       0  6742.8     .05       0
  7122.4     .16       0  7317.7     .05       0  7467.3     .16       0
  7738.2     .05       0
#XS Ineff= 1 ,-1
 5982.95 6044.32  403.05
Permanent Ineff=
       F
Bank Sta=4980.3,5020.3
XS Rating Curve= 0 ,0
Exp/Cntr=0.3,0.1

Type RM Length L Ch R = 1 ,10408   ,816,816,816
BEGIN DESCRIPTION:
HOLMAN CREEK 7.1
END DESCRIPTION:
XS GIS Cut Line= 4
      3548089.15     10563656.19      3546452.91     10563825.45
      3546136.07     10563847.15      3543206.72     10564229.05
#Sta/Elev= 30
  3193.8  455.72  3341.6  448.07  3462.8  445.41  3532.6   442.6  3673.4  429.74
    4361  403.68    4603   400.6  4919.8  400.15  4989.9  402.39    5010  399.45
    5030  402.05  5258.5  400.86    5459  401.25  5533.5  402.33  5553.7   399.9
  5583.9  402.09  5977.2  402.32  5994.4  398.36  5997.1  397.86  6000.4  398.36
  6017.5   402.5    6673  401.22  7013.3  410.69  7294.6  416.48  7363.8  420.33
  7464.1  426.86  7564.3  426.17  7664.6  424.61  7865.1  426.85  8110.5  433.06
#Mann= 15 ,-1 , 0
  3193.8     .05       0  3462.8     .16       0    4361     .05       0
    4603     .16       0  5258.5     .05       0    5459     .16       0
  5994.4     .07       0  6000.4     .16       0  7013.3     .05       0
  7294.6     .16       0  7363.8     .05       0  7464.1     .16       0
  7564.3     .05       0  7664.6     .16       0  7865.1     .05       0
Bank Sta=4989.9,5030
XS Rating Curve= 0 ,0
Exp/Cntr=0.3,0.1

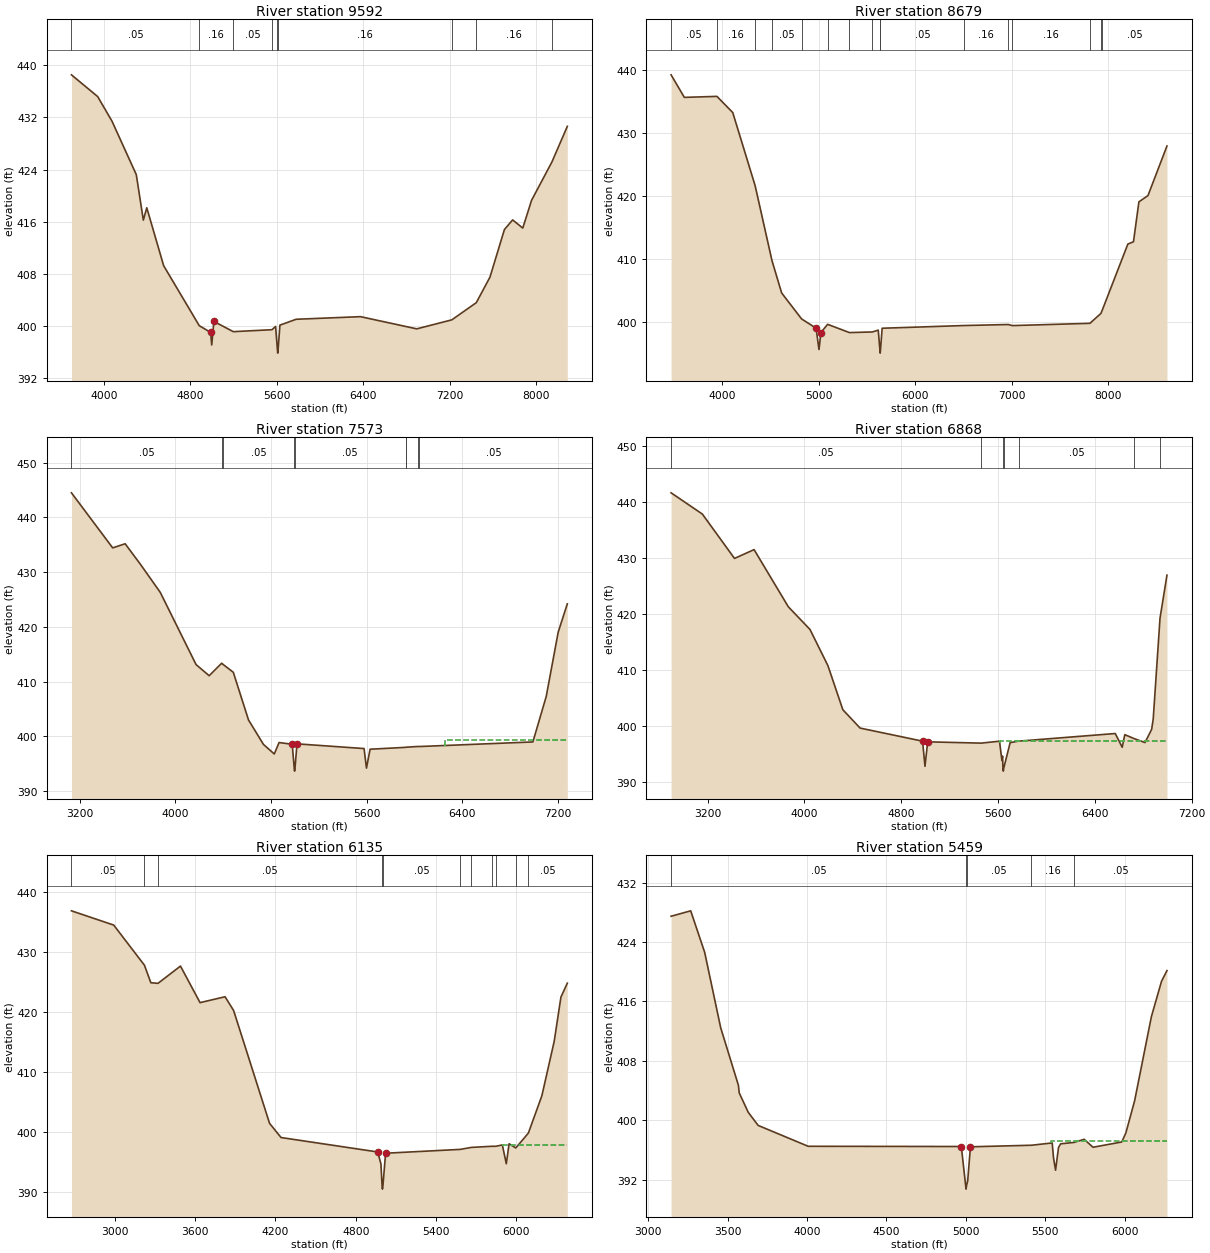
Type RM Length L Ch R = 1 ,9592    ,913,913,913
BEGIN DESCRIPTION:
HOLMAN CREEK 4.1
END DESCRIPTION:
XS GIS Cut Line= 4
      3547642.11     10562688.31      3546565.76     10563104.97
      3545472.01     10563170.07      3543325.34     10564098.74
#Sta/Elev= 30
  3698.5  438.54  3941.5   435.2  4073.8  431.43  4298.5  423.24  4363.7  416.27
  4395.5  418.16  4551.8  409.28  4881.1  400.09  4986.6  399.05  4996.6  397.13
  5016.6  400.74  5196.1  399.17  5554.5  399.47  5587.6  399.97  5604.7  396.38
  5607.4  395.88  5610.7  396.38  5627.7  400.17    5778  401.07  6373.3  401.47
  6893.8   399.6  7218.3  400.98  7444.7  403.61  7571.5  407.53  7705.3  414.83
  7781.2   416.3  7875.2  415.05  7956.5  419.31  8144.7  425.18  8287.3  430.64
#Mann= 9 ,-1 , 0
  3698.5     .05       0  4881.1     .16       0  5196.1     .05       0
  5554.5     .16       0  5604.7     .07       0  5610.7     .16       0
  7218.3     .05       0  7444.7     .16       0  8144.7     .05       0
Bank Sta=4986.6,5016.6
XS Rating Curve= 0 ,0
Exp/Cntr=0.3,0.1

Type RM Length L Ch R = 1 ,8679    ,1106,1106,1106
BEGIN DESCRIPTION:
HOLMAN CREEK 3.3
END DESCRIPTION:
XS GIS Cut Line= 4
      3547859.19     10562176.14      3546565.76     10562267.29
      3545641.28     10562163.13      3543318.37     10563913.96
#Sta/Elev= 30
  3469.9   439.2  3607.3  435.62  3944.6  435.78  4108.6  433.21  4340.8  421.58
  4514.2  409.75  4614.9  404.58  4821.4  400.46  4971.5  398.99  5001.7   395.6
  5021.8  398.29  5090.8   399.6  5317.3  398.29  5553.6  398.39  5615.5  398.68
  5632.7  395.53  5635.4  395.03  5638.7  395.53  5655.8  398.98  6506.6  399.41
  6962.1  399.57  7004.9   399.4  7807.6  399.76  7921.7  401.33  7937.7  401.93
  8200.7  412.34    8259  412.71  8315.2  419.04  8408.9  420.03  8605.7   427.9
#Mann= 16 ,-1 , 0
  3469.9     .05       0  3944.6     .16       0  4340.8      .1       0
  4514.2     .05       0  4821.4     .16       0  5090.8     .05       0
  5317.3     .16       0  5553.6     .05       0  5632.7     .07       0
  5638.7     .05       0  6506.6     .16       0  6962.1      .1       0
  7004.9     .16       0  7807.6     .05       0  7921.7     .16       0
  7937.7     .05       0
Bank Sta=4971.5,5021.8
XS Rating Curve= 0 ,0
Exp/Cntr=0.3,0.1

Type RM Length L Ch R = 1 ,7573    ,705,705,705
BEGIN DESCRIPTION:
HOLMAN CREEK 3.1
END DESCRIPTION:
XS GIS Cut Line= 4
      3548123.96     10561577.19      3546470.27     10561351.49
      3545771.48     10561321.11      3544006.51     10561082.45
#Sta/Elev= 30
  3130.3  444.48  3475.3  434.43  3579.7  435.18  3707.5  431.43  3873.9  426.29
  4173.2  413.12  4282.7  411.09  4387.2  413.37  4397.3  413.18  4484.6  411.72
    4612  403.01  4736.9  398.55  4827.5   396.8  4867.5  398.89  4977.6  398.57
  4994.7  394.17  4997.4  393.67  5000.7  394.17  5017.7  398.65  5578.9  397.79
    5599  394.22  5629.3  397.67  5926.4  398.01    5928  398.03  6027.3  398.17
  6041.6  398.16  6991.6     399  7103.5  407.32  7203.5  419.05  7279.8  424.21
#Mann= 9 ,-1 , 0
  3130.3     .05       0  4387.2     .16       0  4397.3     .05       0
  4994.7     .03       0  5000.7     .05       0  5926.4      .1       0
    5928     .16       0  6027.3      .1       0  6041.6     .05       0
#XS Ineff= 2 , 0
                         6254.92          399.43
Permanent Ineff=
       F       F
Bank Sta=4977.6,5017.7
XS Rating Curve= 0 ,0
Exp/Cntr=0.3,0.1

Type RM Length L Ch R = 1 ,6868    ,733,733,733
BEGIN DESCRIPTION:
HOLMAN CREEK 3.2
END DESCRIPTION:
XS GIS Cut Line= 4
       3548267.1     10561295.05      3546518.01     10560665.73
      3545879.99     10560891.42      3544402.43     10560389.22
#Sta/Elev= 30
  2899.2  441.57  3157.3  437.79  3423.1  429.88  3584.7  431.45  3867.8  421.26
  4046.7  417.22    4195  410.76    4318  402.92  4460.7  399.65  4976.5  397.32
  4996.5  392.84  5018.9   397.2  5460.5  396.97  5612.1  397.31  5632.1  393.87
  5637.3  394.66  5640.8  392.48  5643.6  391.98  5646.8  392.48  5700.1  397.06
  5769.8  397.32  6568.2  398.68  6625.7  396.23  6647.2  398.48  6723.6  397.78
  6813.9  397.07    6869  399.43    6882  401.29    6938  419.22  6995.4   426.9
#Mann= 7 ,-1 , 0
  2899.2     .05       0  5460.5     .16       0  5640.8     .03       0
  5646.8     .16       0  5769.8     .05       0  6723.6     .16       0
    6938     .05       0
#XS Ineff= 2 , 0
                         5613.64          397.36
Permanent Ineff=
       F       F
Bank Sta=4976.5,5018.9
XS Rating Curve= 0 ,0
Exp/Cntr=0.3,0.1

Type RM Length L Ch R = 1 ,6135    ,676,676,676
BEGIN DESCRIPTION:
HOLMAN CREEK 2.1
END DESCRIPTION:
XS GIS Cut Line= 5
      3548358.25     10561021.62      3546409.51     10560296.81
      3545984.16     10560123.19       3545406.9     10559931.33
       3545078.8     10559478.24
#Sta/Elev= 30
  2675.3  436.84  2991.3  434.46  3220.9  427.76  3268.7  424.84  3322.3  424.74
  3490.1  427.62  3636.5  421.52  3823.5   422.5  3887.5   420.2    4156  401.38
  4241.8  399.01  4964.4   396.6  4988.5  394.61  4997.1   390.9  4999.8   390.4
  5003.1   390.9  5023.3  396.39  5580.9  397.03  5663.9  397.36  5818.3  397.55
  5846.7  397.55    5896  397.77  5925.4  394.64  5946.3  397.97  5996.4  397.27
  6090.4  399.75  6191.5  405.99  6283.5  415.06  6333.8  422.44  6381.6  424.77
#Mann= 11 ,-1 , 0
  2675.3     .05       0  3220.9     .07       0  3322.3     .05       0
  4997.1     .03       0  5003.1     .05       0  5580.9      .1       0
  5663.9     .05       0  5818.3     .16       0  5846.7     .05       0
  5996.4     .16       0  6090.4     .05       0
#XS Ineff= 2 , 0
                         5893.18          397.82
Permanent Ineff=
       F       F
Bank Sta=4964.4,5023.3
XS Rating Curve= 0 ,0
Exp/Cntr=0.3,0.1

Type RM Length L Ch R = 1 ,5459    ,848,848,848
BEGIN DESCRIPTION:
HOLMAN CREEK 5.2
END DESCRIPTION:
XS GIS Cut Line= 4
      3548207.21     10560216.04      3546636.07     10559669.17
      3546110.03     10559639.66      3545229.79     10559332.36
#Sta/Elev= 30
  3143.8  427.48  3267.3  428.21  3355.3  422.62  3456.3  412.45  3567.6  404.73
  3572.9  403.69  3629.8  401.07    3692  399.31  4006.9   396.5  4971.6  396.47
  4998.7  391.23  5001.4  390.73  5004.7  391.23  5011.7  391.84  5028.9  396.43
  5413.3  396.64  5543.9  396.95  5552.5  394.89  5565.1  393.28  5583.6  396.33
  5596.9  396.83  5681.5  397.02  5745.1  397.44    5801  396.37    5982  397.08
  6007.8   398.3  6062.9  402.62  6168.8  413.98  6232.4  418.72  6266.6  420.16
#Mann= 5 ,-1 , 0
  3143.8     .05       0  4998.7     .03       0  5004.7     .05       0
  5413.3     .16       0  5681.5     .05       0
#XS Ineff= 2 , 0
                         5533.52          397.16
Permanent Ineff=
       F       F
Bank Sta=4971.6,5028.9
XS Rating Curve= 0 ,0
Exp/Cntr=0.3,0.1

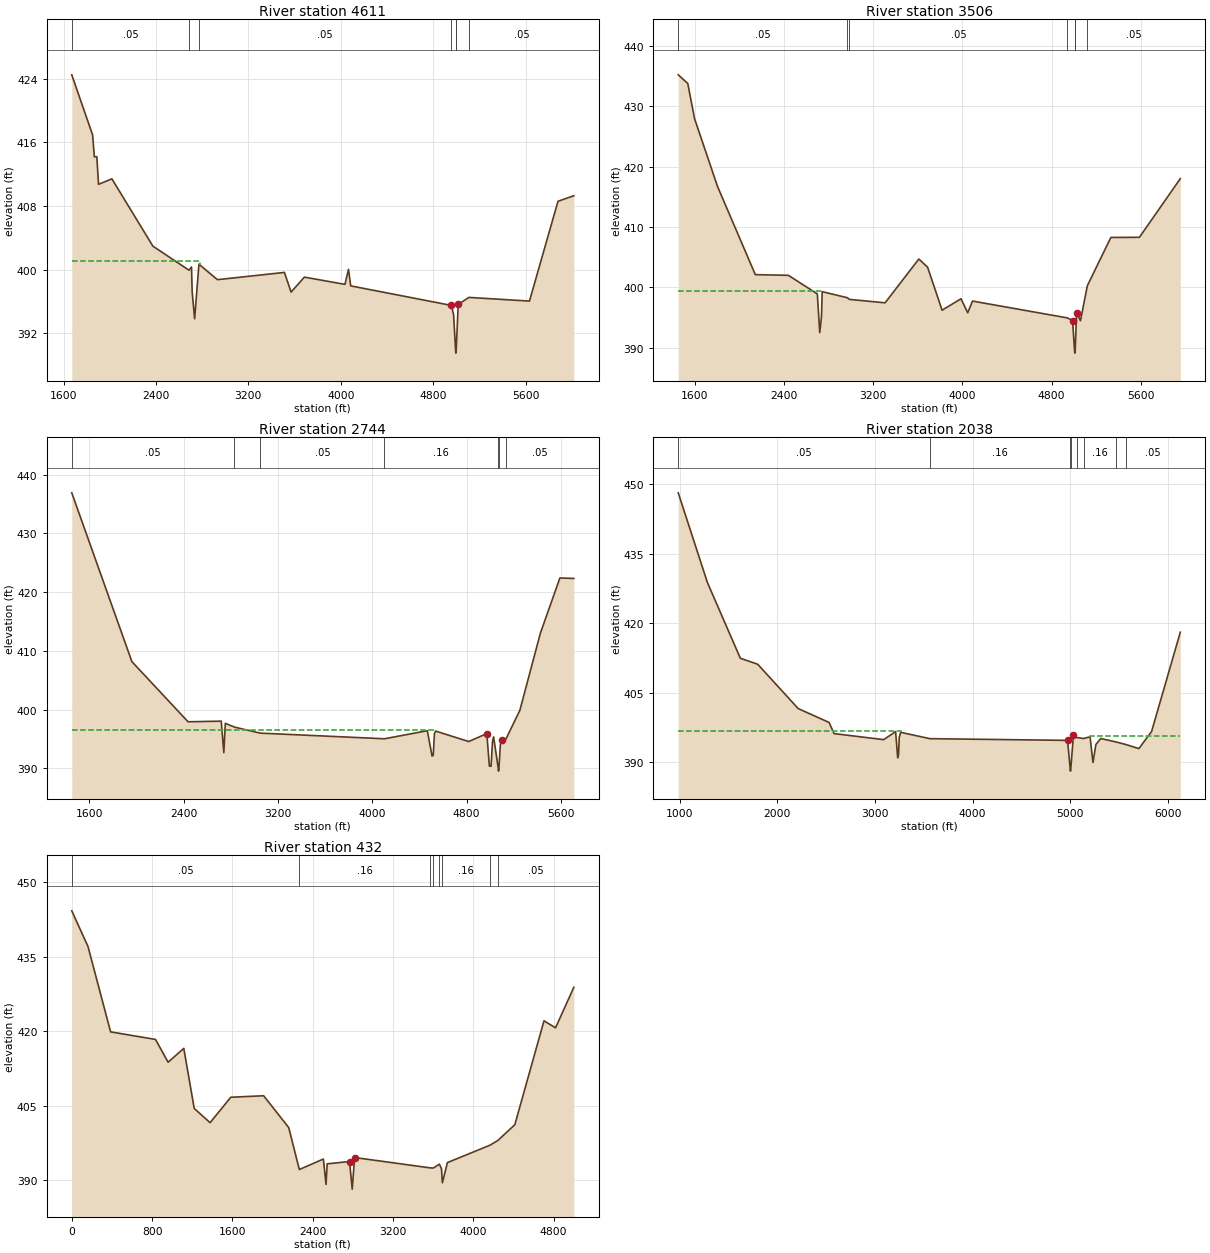
Type RM Length L Ch R = 1 ,4611    ,1105,1105,1105
BEGIN DESCRIPTION:
HOLMAN CREEK 4.2
END DESCRIPTION:
XS GIS Cut Line= 4
      3549550.64     10557840.99      3547664.69      10559033.7
      3546414.69     10558851.41      3545589.18     10558640.48
#Sta/Elev= 30
  1671.6  424.47  1851.9  416.92  1867.2  414.16  1888.4  414.19  1903.6  410.71
  2018.9   411.4  2374.1  402.94  2686.7  399.92  2708.2  400.32  2714.1  397.18
  2735.3  393.82  2772.6  400.67  2932.8  398.73  3512.7  399.64  3570.3  397.17
  3685.6  399.05    4037  398.14  4067.4  400.03  4086.5  397.95  4956.7   395.5
  4958.6  395.44  4976.9  394.37  4994.1     390  4996.8   389.5  5000.1     390
  5017.3  395.62  5109.4   396.5  5634.2  396.04  5881.1  408.58  6018.3  409.28
#Mann= 7 ,-1 , 0
  1671.6     .05       0  2686.7     .16       0  2772.6     .05       0
  4958.6     .16       0  4994.1     .07       0  5000.1     .16       0
  5109.4     .05       0
#XS Ineff= 2 , 0
         2782.95  401.02
Permanent Ineff=
       F       F
Bank Sta=4956.7,5017.3
XS Rating Curve= 0 ,0
Exp/Cntr=0.3,0.1

Type RM Length L Ch R = 1 ,3506    ,762,762,762
BEGIN DESCRIPTION:
HOLMAN CREEK 3.0
END DESCRIPTION:
XS GIS Cut Line= 4
      3549436.08     10557382.64      3547420.41     10558262.87
      3546206.87     10558273.29      3545125.33     10558429.28
#Sta/Elev= 30
  1449.7  435.23  1535.3   433.8  1595.9  427.98  1803.2  416.68  2141.5   402.1
  2437.9  401.99    2698  398.91  2719.8   392.5  2735.1   395.1  2741.6  399.28
  2968.5  398.27  2985.1     398  3306.2  397.43  3608.9  404.69  3687.5  403.34
  3817.5  396.21  3987.5   398.1  4047.5  395.78  4090.6  397.72  4942.2  394.93
  4988.8  394.48    5006  389.59  5008.8  389.09    5012  389.59  5025.3  395.77
  5059.5  394.46  5121.2  400.26  5332.3  408.27  5588.4  408.29  5955.5  418.02
#Mann= 7 ,-1 , 0
  1449.7     .05       0  2968.5     .16       0  2985.1     .05       0
  4942.2     .16       0    5006     .07       0    5012     .16       0
  5121.2     .05       0
#XS Ineff= 2 , 0
         2744.32  399.37
Permanent Ineff=
       F       F
Bank Sta=4988.8,5025.3
XS Rating Curve= 0 ,0
Exp/Cntr=0.3,0.1

Type RM Length L Ch R = 1 ,2744    ,706,706,706
BEGIN DESCRIPTION:
HOLMAN CREEK 2.0
END DESCRIPTION:
XS GIS Cut Line= 4
       3549196.2     10556758.14      3547793.41     10557397.04
      3545960.83     10557534.08      3545226.79     10558020.85
#Sta/Elev= 30
  1449.6   436.9  1959.6  408.16  2436.4  397.91  2717.8  398.02  2739.7  392.66
  2752.5  397.65  2829.8  397.01  3048.3  395.98  4102.6  395.02  4466.4  396.39
  4506.6  392.08  4516.6  392.19  4526.6  395.88  4536.6  396.33  4817.4  394.55
  4971.2   395.9  4992.7  390.38  5007.2  390.34  5019.7  394.64  5028.8  395.34
  5067.9  390.01  5070.6  389.51  5073.9  390.01  5085.9  393.99    5101  394.86
  5132.9  394.96  5251.3  399.85  5425.8  413.01  5591.2   422.4  5709.5  422.32
#Mann= 7 ,-1 , 0
  1449.6     .05       0  2829.8     .16       0  3048.3     .05       0
  4102.6     .16       0  5067.9     .07       0  5073.9     .16       0
  5132.9     .05       0
#XS Ineff= 2 , 0
         4536.93  396.52
Permanent Ineff=
       F       F
Bank Sta=4971.2,5101
XS Rating Curve= 0 ,0
Exp/Cntr=0.3,0.1

Type RM Length L Ch R = 1 ,2038    ,1603,1603,1603
BEGIN DESCRIPTION:
HOLMAN CREEK 1.0
END DESCRIPTION:
XS GIS Cut Line= 4
      3549284.61     10556242.94      3547426.92     10556624.89
      3547131.78     10557111.01      3544458.18     10557093.64
#Sta/Elev= 30
   986.6  448.18  1285.2  428.81  1622.1  412.46  1800.1  411.16  2214.3  401.59
  2530.7  398.59  2581.8  396.18  3089.4  394.88  3211.6  396.61  3232.9  390.97
    3242  391.73  3248.4  395.37  3263.9  396.46  3562.6  395.09  4971.5  394.72
  4998.5  388.58  5001.3  388.08  5004.5  388.58  5031.5  395.81  5068.7  395.32
    5136  395.12  5201.6   395.5  5231.6  389.95  5261.6  393.83  5311.6  395.12
  5468.6  394.38  5567.5  393.83  5701.6  392.95  5831.6  396.64  6125.5  418.08
#Mann= 8 ,-1 , 0
   986.6     .05       0  3562.6     .16       0  4998.5     .07       0
  5004.5     .16       0  5068.7     .05       0    5136     .16       0
  5468.6      .1       0  5567.5     .05       0
#XS Ineff= 2 , 0
         3263.73  396.69  5198.3          395.59
Permanent Ineff=
       F       F
Bank Sta=4971.5,5031.5
XS Rating Curve= 0 ,0
Exp/Cntr=0.3,0.1

Type RM Length L Ch R = 1 ,432     ,0,0,0
XS GIS Cut Line= 4
      3548453.52     10555591.77      3546159.27     10556260.93
      3545501.36     10556474.61      3543583.86     10556609.57
#Sta/Elev= 30
       0  444.18   161.6  437.02   386.9  419.86   834.2  418.34   959.8  413.76
  1116.1  416.54  1220.2  404.47  1378.1  401.61  1584.2  406.72  1911.6  407.02
  2161.6  400.63  2267.2   392.2  2506.6  394.31  2533.3  389.22  2544.6  393.34
  2767.5  393.81  2794.2  388.26  2817.9  394.61    3572  392.53  3602.1   392.5
  3662.3  393.28  3683.8  392.33  3692.3  389.54  3742.5  393.59  4163.5  397.06
  4243.7  398.01  4414.1   401.2  4704.8  422.08  4819.9  420.67  5002.2  428.82
#Mann= 8 ,-1 , 0
       0     .05       0  2267.2     .16       0    3572     .07       0
  3602.1     .16       0  3662.3     .05       0  3683.8     .16       0
  4163.5      .1       0  4243.7     .05       0
Bank Sta=2767.5,2817.9
XS Rating Curve= 0 ,0
Exp/Cntr=0.3,0.1

Chan Stop Cuts=-1
Use User Specified Reach Order=0
Composite Channel Slope=5