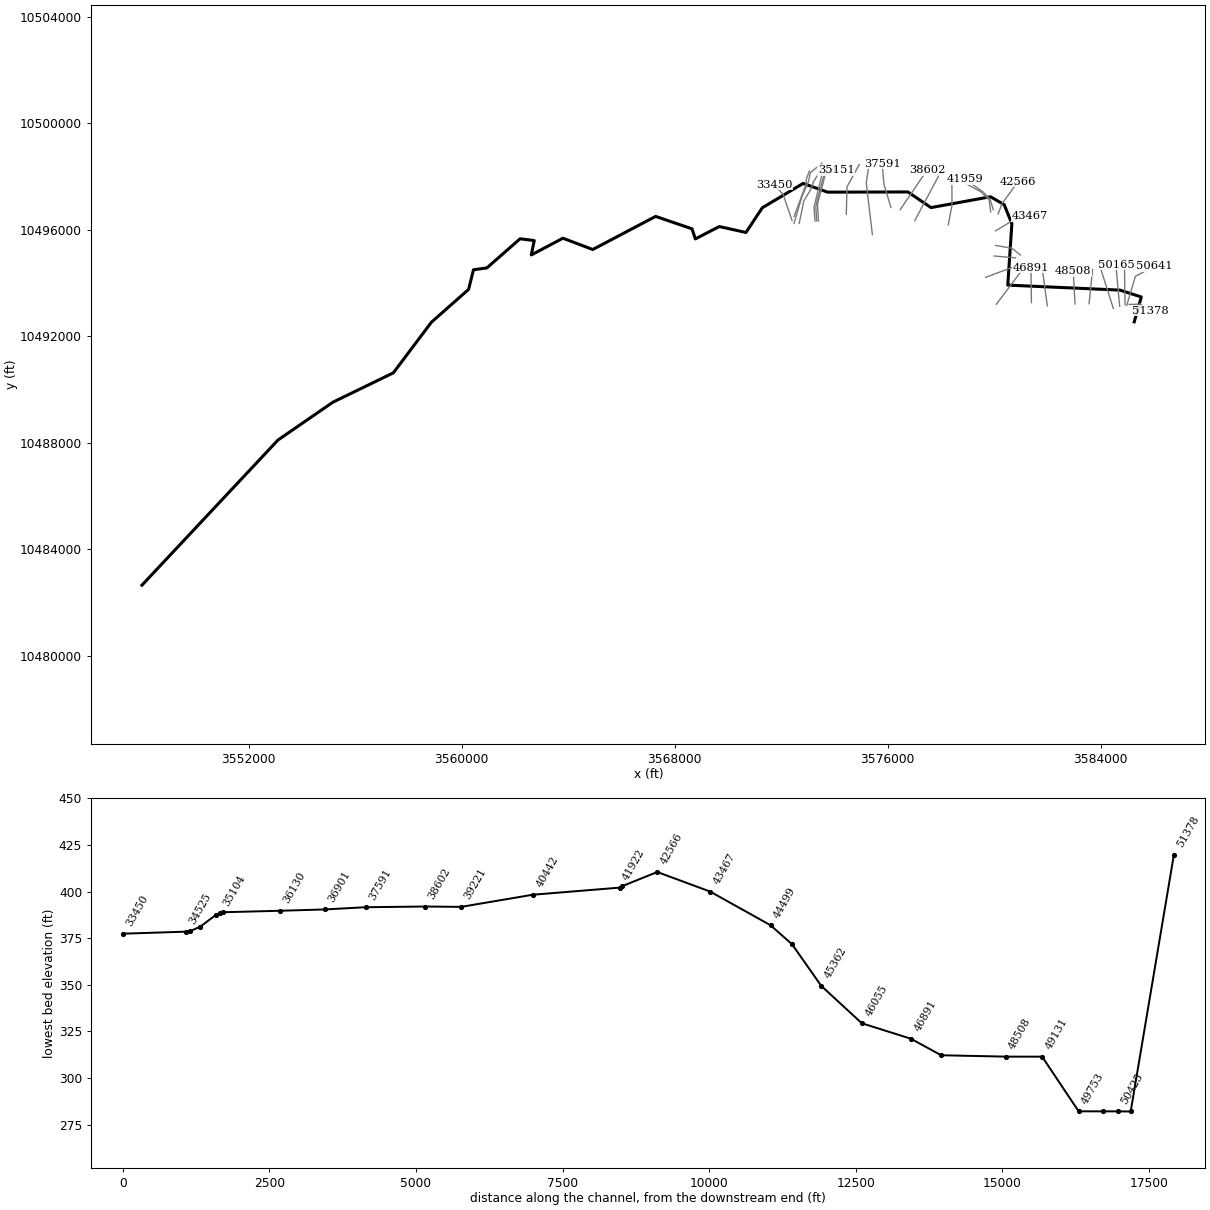
--- LAMBS CREEK.prj (project) ---

Proj Title=LAMBS CREEK Base Level Engineering
Current Plan=p01
Default Exp/Contr=0.3,0.1
English Units
Geom File=g01
Flow File=f01
Plan File=p01
Y Axis Title=Elevation
X Axis Title(PF)=Main Channel Distance
X Axis Title(XS)=Station
BEGIN DESCRIPTION:
LAMBS CREEK
END DESCRIPTION:
DSS Export Rating Curves= 0
DSS Export Rating Curve Sorted= 0
DSS Export Volume Flow Curves= 0
DXF OffsetX= 0
DXF OffsetY= 0
DXF ScaleX= 1
DXF ScaleY= 10

--- LAMBS CREEK.p01 (plan) ---

Plan Title=Multiple Run
Short Identifier=Multiple
Geom File=g01
Flow File=f01
Subcritical Flow
K Sum by GR= 0
Std Step Tol= 0.01
Critical Tol= 0.01
Num of Std Step Trials= 20
Max Error Tol= 0.3
Flow Tol Ratio= 0.001
Split Flow NTrial= 30
Split Flow Tol= 0.02
Split Flow Ratio= 0.02
Log Output Level= 0
Friction Slope Method= 1
Unsteady Friction Slope Method= 2
Unsteady Bridges Friction Slope Method= 1
Parabolic Critical Depth
Global Vel Dist=  1 , 1 , 1
Global Log Level= 0
CheckData=True
Encroach Param= -1, 0, 0, 0
BEGIN DESCRIPTION:
Multiple Run
END DESCRIPTION:

--- LAMBS CREEK.f01 (steady flow) ---

Flow Title=Multiple
Program Version=4.10
Number of Profiles= 7
Profile Names=10-year,25-year,50-year,1pct_min,100-year,1pct_plu,500-year
River Rch & RM=LAMBS CREEK,Reach-1         ,51378
    2004    2894    3664    3382    4574    6186    7110
River Rch & RM=LAMBS CREEK,Reach-1         ,47409
    1939    2737    3411    3091    4181    5654    6270
River Rch & RM=LAMBS CREEK,Reach-1         ,41959
    4847    7165    9213    8600   11630   15729   18503
River Rch & RM=LAMBS CREEK,Reach-1         ,37591
    5378    7954   10230    9546   12911   17460   20529
River Rch & RM=LAMBS CREEK,Reach-1         ,35151
    6408    9537   12317   11538   15604   21103   25000
River Rch & RM=LAMBS CREEK,Reach-1         ,27474
    7757   11624   15084   14192   19193   25956   31014
River Rch & RM=LAMBS CREEK,Reach-1         ,26403
    7823   11689   15137   14210   19218   25990   30916
River Rch & RM=LAMBS CREEK,Reach-1         ,21692
    8559   12799   16584   15573   21060   28481   33895
River Rch & RM=LAMBS CREEK,Reach-1         ,15873
    8605   12852   16640   15611   21112   28551   33916
River Rch & RM=LAMBS CREEK,Reach-1         ,13402
    8551   12742   16471   15426   20862   28213   33399
River Rch & RM=LAMBS CREEK,Reach-1         ,9959
    9179   13674   17672   16543   22373   30257   35781
Boundary for River Rch & Prof#=LAMBS CREEK,Reach-1         , 1
Up Type= 0
Dn Type= 3
Dn Slope=0.001
Boundary for River Rch & Prof#=LAMBS CREEK,Reach-1         , 2
Up Type= 0
Dn Type= 3
Dn Slope=0.001
Boundary for River Rch & Prof#=LAMBS CREEK,Reach-1         , 3
Up Type= 0
Dn Type= 3
Dn Slope=0.001
Boundary for River Rch & Prof#=LAMBS CREEK,Reach-1         , 4
Up Type= 0
Dn Type= 3
Dn Slope=0.001
Boundary for River Rch & Prof#=LAMBS CREEK,Reach-1         , 5
Up Type= 0
Dn Type= 3
Dn Slope=0.001
Boundary for River Rch & Prof#=LAMBS CREEK,Reach-1         , 6
Up Type= 0
Dn Type= 3
Dn Slope=0.001
Boundary for River Rch & Prof#=LAMBS CREEK,Reach-1         , 7
Up Type= 0
Dn Type= 3
Dn Slope=0.001
DSS Import GetInterval= 0
DSS Import GetPeak= 0
DSS Import FillOption= 0

--- LAMBS CREEK.g01 (geometry) ---

Geom Title=Existing Conditions
Program Version=4.10

River Reach=LAMBS CREEK     ,Reach-1
Reach XY= 30
      3585253.25     10492538.31       3585518.7     10493473.23
      3584716.68      10493731.9      3580504.86     10493918.77
       3580658.9     10496224.17      3580372.11     10496941.64
      3579856.05     10497239.93      3577622.21      10496831.9
      3576756.41     10497419.97      3573737.56     10497412.32
      3572820.43     10497740.22      3571285.69     10496823.83
      3570674.75       10495897.      3569672.68     10496120.29
      3568773.37     10495654.89      3568648.87     10496033.58
      3567282.03     10496501.84      3564921.83     10495256.67
       3563800.5     10495681.99      3562612.75     10495052.72
      3562723.84     10495592.91      3562192.55      10495660.6
      3560945.17     10494565.31      3560442.25     10494495.63
      3560258.15     10493758.21      3558861.59     10492523.91
       3557432.4     10490621.94       3555161.5     10489518.27
      3553099.87     10488096.83      3547992.11     10482641.64

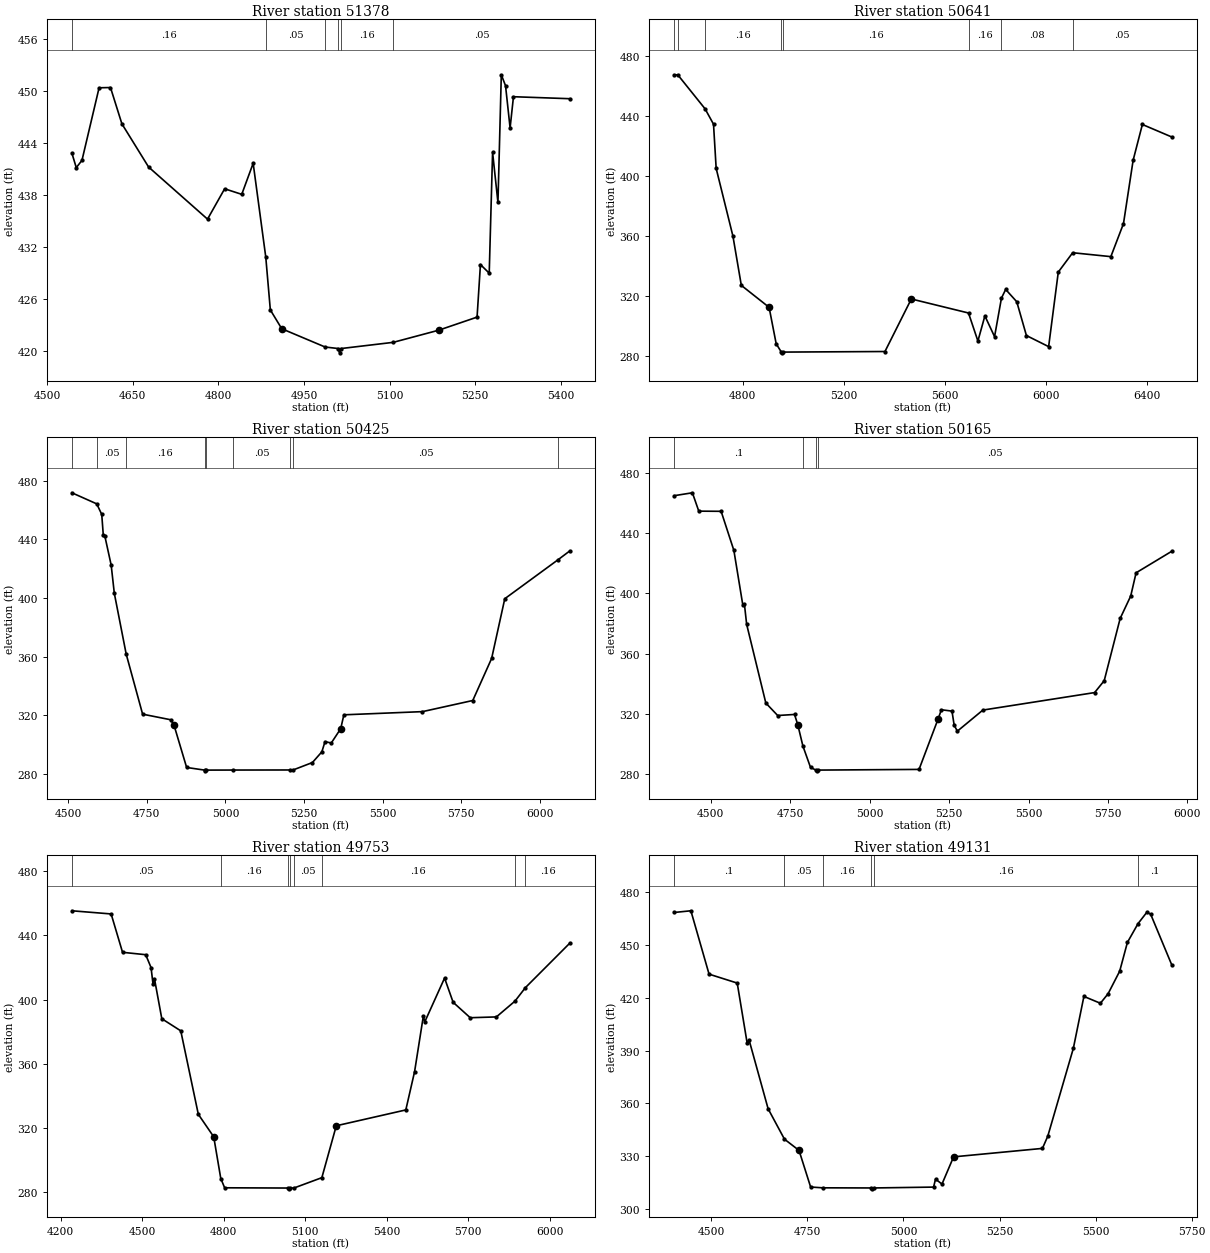
Type RM Length L Ch R = 1 ,51378   ,737,737,737
BEGIN DESCRIPTION:
UNT0170 IN SAND CR 20.0
END DESCRIPTION:
XS GIS Cut Line= 3
      3585064.42     10493192.48       3585477.7     10493205.11
      3585867.69     10492962.45
#Sta/Elev= 30
  4543.2  442.79  4550.9  441.11  4560.9  441.95  4590.9  450.32  4610.9  450.35
  4630.9  446.16  4677.7  441.18    4781  435.17    4811  438.67    4841  438.03
    4861  441.61  4883.1  430.79  4891.1   424.7  4911.1  422.53  4987.2  420.42
  5009.7  420.25  5012.5  419.75  5015.7  420.25  5106.5  420.96  5186.2  422.36
  5253.5  423.87  5259.4  429.93  5274.8  428.94  5280.7  442.87  5290.1  437.09
    5296  451.82  5303.4  450.56  5311.4  445.69  5317.3  449.29    5416  449.06
#Mann= 6 ,-1 , 0
  4543.2     .16       0  4883.1     .05       0  4987.2     .16       0
  5009.7     .07       0  5015.7     .16       0  5106.5     .05       0
Bank Sta=4911.1,5186.2
XS Rating Curve= 0 ,0
Exp/Cntr=0.3,0.1

Type RM Length L Ch R = 1 ,50641   ,216,216,216
BEGIN DESCRIPTION:
UNT0170 IN SAND CR 19.0
END DESCRIPTION:
XS GIS Cut Line= 3
      3584971.14     10493151.99      3585297.52     10494249.18
      3586025.37     10494637.37
#Sta/Elev= 30
  4527.9  467.08  4542.5  467.32  4650.6  444.63    4684   434.4  4694.5  404.92
  4760.8  359.81    4794  326.99  4903.9  312.36  4931.9  288.09  4952.3  282.53
    4955  282.03  4958.3  282.53  5362.2  282.91  5466.5  317.92  5692.7  308.58
  5729.9   289.9  5757.5  306.64  5795.8  292.81    5823  318.46  5839.7  324.28
  5883.6  316.09  5921.8  293.56  6009.7  286.17  6047.9  335.85  6104.8  348.74
  6255.8  346.14  6305.8  368.15    6344  410.39  6380.5   434.2  6497.5  425.82
#Mann= 8 ,-1 , 0
  4527.9      .1       0  4542.5     .05       0  4650.6     .16       0
  4952.3     .03       0  4958.3     .16       0  5692.7     .16       0
    5823     .08       0  6104.8     .05       0
Bank Sta=4903.9,5466.5
XS Rating Curve= 0 ,0
Exp/Cntr=0.3,0.1

Type RM Length L Ch R = 1 ,50425   ,260,260,260
BEGIN DESCRIPTION:
UNT0170 IN SAND CR 18.0
END DESCRIPTION:
XS GIS Cut Line= 4
      3584908.63     10493186.66       3584887.8     10494554.74
      3584871.04     10494684.41      3584854.41     10494767.37
#Sta/Elev= 30
  4511.7   471.7  4590.8  464.14  4606.7  456.95  4611.7   442.6  4616.7  442.04
  4636.7  422.39  4646.7  403.15  4684.5  361.66  4736.7  320.74  4826.7   316.9
  4836.7  313.14  4876.7   284.4  4933.7   282.6  4936.5   282.1  4939.7   282.6
  5023.2  282.64  5206.6  282.69  5215.1  282.68  5276.8  287.77  5306.8  295.07
  5316.8     302  5336.8  301.09  5366.8  310.86  5376.8   320.3  5626.8  322.47
  5786.8  330.06  5846.8  358.75  5888.6  399.46  6058.7  426.15  6095.3  432.04
#Mann= 9 ,-1 , 0
  4511.7      .1       0  4590.8     .05       0  4684.5     .16       0
  4933.7     .07       0  4939.7     .16       0  5023.2     .05       0
  5206.6     .16       0  5215.1     .05       0  6058.7     .08       0
Bank Sta=4836.7,5366.8
XS Rating Curve= 0 ,0
Exp/Cntr=0.3,0.1

Type RM Length L Ch R = 1 ,50165   ,412,412,412
BEGIN DESCRIPTION:
UNT0170 IN SAND CR 17.0
END DESCRIPTION:
XS GIS Cut Line= 3
      3584707.24      10493124.2       3584575.3     10494554.74
      3584572.43      10494684.4
#Sta/Elev= 30
  4384.9  464.99  4442.6  466.94  4462.7  454.73    4533  454.62  4573.1  428.62
  4601.2  392.34  4606.2  392.98  4613.3  379.48  4673.6  327.18  4710.9  318.88
  4763.9  319.58    4774  312.86  4790.2  298.62  4814.2  284.39  4831.2   282.6
    4834   282.1  4837.2   282.6  5155.6  283.05  5215.9  316.78  5225.9   322.7
  5259.2  321.81  5266.1  312.46  5276.1  308.46  5356.4  322.49  5707.9  334.12
  5738.1  342.02  5788.3  383.41  5821.5  398.31  5838.4  413.75  5951.2  428.13
#Mann= 4 ,-1 , 0
  4384.9      .1       0  4790.2     .05       0  4831.2     .04       0
  4837.2     .05       0
Bank Sta=4774,5215.9
XS Rating Curve= 0 ,0
Exp/Cntr=0.3,0.1

Type RM Length L Ch R = 1 ,49753   ,622,622,622
BEGIN DESCRIPTION:
UNT0170 IN SAND CR 16.0
END DESCRIPTION:
XS GIS Cut Line= 2
      3584467.95     10493043.89      3583914.54     10494790.93
#Sta/Elev= 30
  4241.8  455.27  4386.3   453.3  4428.3  429.41  4513.5  427.92  4533.2  419.92
  4540.5   409.6  4545.8  412.95  4572.8  388.06  4642.6  380.51  4707.2  328.54
  4763.9  314.54  4789.9  288.56  4804.1  282.78  5037.6  282.63  5040.4  282.13
  5043.6  282.63  5059.3  282.65  5161.9  289.09    5215   321.4  5470.9  331.26
  5503.2  355.08  5535.5  389.73  5540.7  386.09  5613.6  413.37  5645.1  398.28
    5708  388.68  5804.3  389.18  5872.6  398.99  5911.2  407.43  6074.4  435.09
#Mann= 8 ,-1 , 0
  4241.8     .05       0  4789.9     .16       0  5037.6     .07       0
  5043.6     .16       0  5059.3     .05       0  5161.9     .16       0
  5872.6     .05       0  5911.2     .16       0
Bank Sta=4763.9,5215
XS Rating Curve= 0 ,0
Exp/Cntr=0.3,0.1

Type RM Length L Ch R = 1 ,49131   ,623,623,623
BEGIN DESCRIPTION:
UNT0170 IN SAND CR 15.0
END DESCRIPTION:
XS GIS Cut Line= 2
      3583557.56     10493218.11      3583690.34     10494506.89
#Sta/Elev= 30
  4403.1  468.43  4446.9   469.4  4494.2   433.4  4567.5  428.33  4593.2  394.38
  4598.3  396.02  4647.9   356.9  4690.4  339.65  4728.3  333.28  4758.5  312.47
  4789.5  312.02  4916.3  311.94  4919.1  311.44  4922.3  311.94  5078.4  312.43
  5083.5  316.96  5100.3  314.15  5130.5  329.61  5361.7  334.41  5375.6  341.35
  5442.1  391.23  5469.6  420.75  5512.5  416.86  5532.6  422.29  5562.7  435.08
  5582.8  451.43  5610.4  462.09  5633.1  468.47  5643.2  467.51  5698.7   438.4
#Mann= 6 ,-1 , 0
  4403.1      .1       0  4690.4     .05       0  4789.5     .16       0
  4916.3     .07       0  4922.3     .16       0  5610.4      .1       0
Bank Sta=4728.3,5130.5
XS Rating Curve= 0 ,0
Exp/Cntr=0.3,0.1

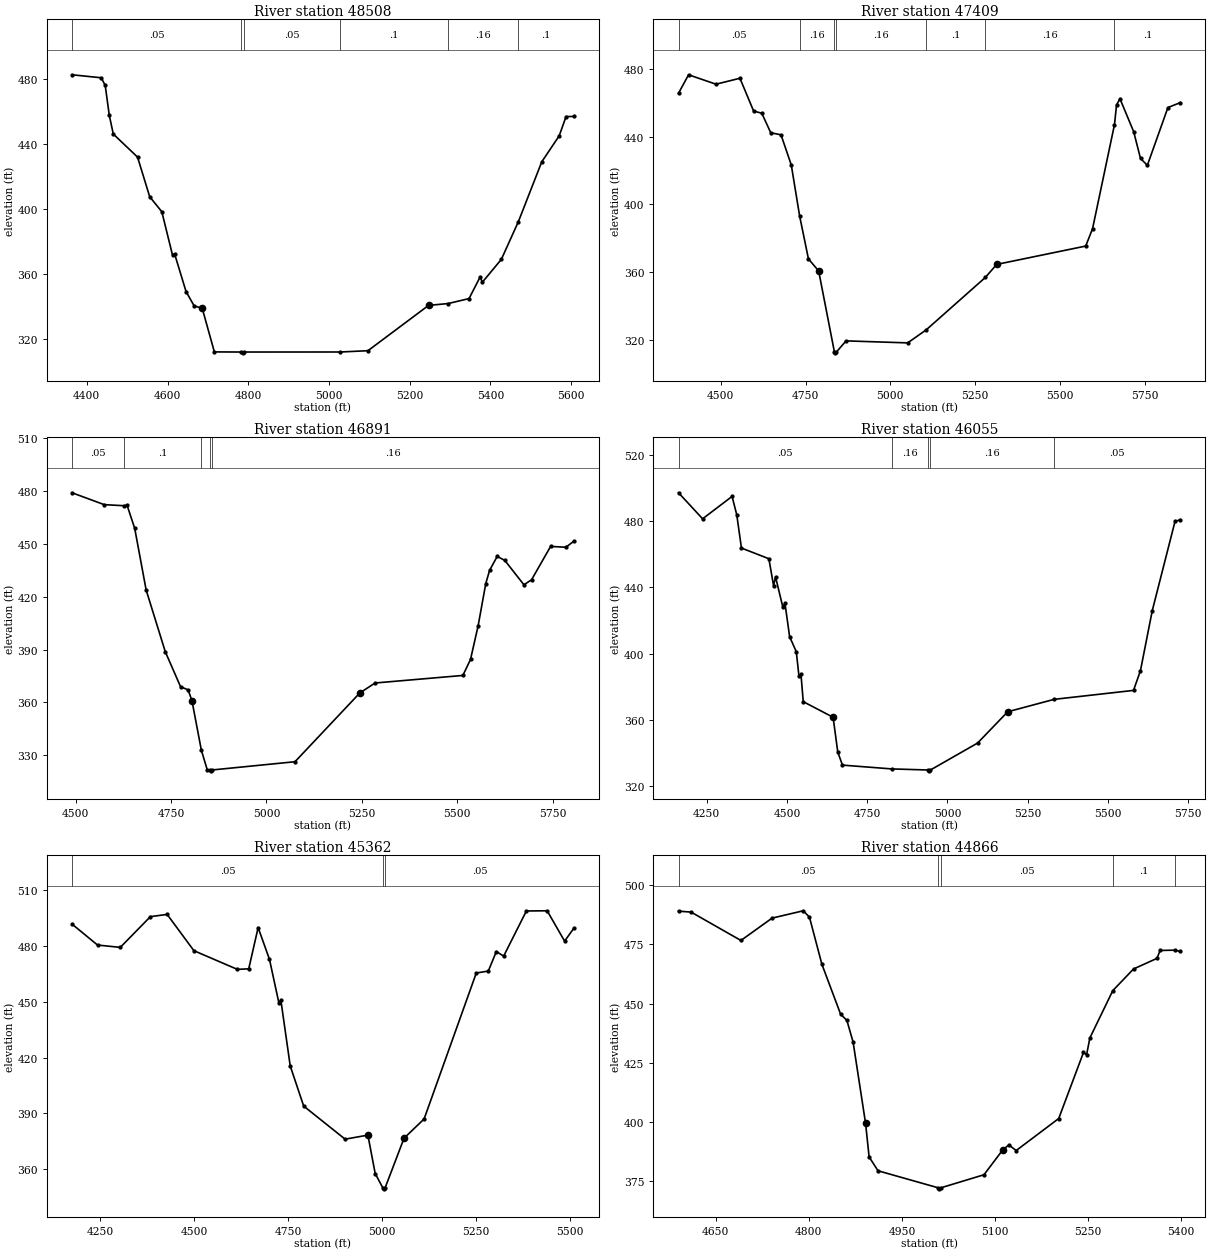
Type RM Length L Ch R = 1 ,48508   ,1099,1099,1099
BEGIN DESCRIPTION:
UNT0170 IN SAND CR 14.0
END DESCRIPTION:
XS GIS Cut Line= 2
      3583030.22     10493209.64      3582965.11     10494451.03
#Sta/Elev= 30
  4363.5  482.67  4435.6  480.83  4445.6  476.16  4455.6  457.85  4465.6  446.19
  4525.7  431.98  4555.8  407.58  4585.8  398.38  4612.4  371.59  4617.4  372.48
  4645.9  349.17  4665.9  340.36  4685.9  338.92    4716  312.03  4783.1  311.96
  4785.8  311.46  4789.1  311.96    5028  311.98  5096.5  312.77  5246.7  340.68
  5294.9   341.8  5346.9  344.86  5374.7  358.33  5379.7  354.86    5427  369.03
  5469.2  392.27  5527.1  429.09  5570.3  445.08  5587.2  456.93  5606.6     457
#Mann= 6 ,-1 , 0
  4363.5     .05       0  4783.1     .04       0  4789.1     .05       0
    5028      .1       0  5294.9     .16       0  5469.2      .1       0
Bank Sta=4685.9,5246.7
XS Rating Curve= 0 ,0
Exp/Cntr=0.3,0.1

Type RM Length L Ch R = 1 ,47409   ,518,518,518
BEGIN DESCRIPTION:
UNT0170 IN SAND CR 12.0
END DESCRIPTION:
XS GIS Cut Line= 2
        3581990.     10493142.27      3581790.52     10494607.96
#Sta/Elev= 30
  4375.7  465.84  4405.3  476.75  4486.1  471.17  4556.7  474.69  4597.1  455.25
    4621  454.01  4647.6  442.44  4677.8  441.21  4708.1  423.35  4732.6  393.24
  4758.6  367.82  4788.8  360.63  4835.2   312.7  4837.9   312.2  4841.2   312.7
  4869.6  319.28  5051.2  318.09  5105.7  325.78    5280   356.8  5313.6  364.53
    5576  375.39  5596.2  385.69  5660.8  447.25  5666.9  458.93    5677  462.55
  5717.3  443.12  5737.5  427.24  5757.7  423.17  5818.3  457.35  5854.9  460.29
#Mann= 7 ,-1 , 0
  4375.7     .05       0  4732.6     .16       0  4835.2     .07       0
  4841.2     .16       0  5105.7      .1       0    5280     .16       0
  5660.8      .1       0
Bank Sta=4788.8,5313.6
XS Rating Curve= 0 ,0
Exp/Cntr=0.3,0.1

Type RM Length L Ch R = 1 ,46891   ,836,836,836
BEGIN DESCRIPTION:
UNT0170 IN SAND CR 10.0
END DESCRIPTION:
XS GIS Cut Line= 2
      3581393.93     10493257.41      3581376.57      10494572.5
#Sta/Elev= 30
  4490.4  479.06  4574.6  472.32  4626.5  471.71  4634.6  471.94  4654.6  458.82
  4684.6  423.78  4734.7  388.76  4774.7   368.9  4794.7  367.05  4804.7  360.82
  4829.2  332.89  4844.7  321.64  4851.7  321.58  4854.4  321.08  4857.7  321.58
  5074.7  326.26  5244.7  365.35  5284.7  370.99  5514.7  375.28  5534.7  384.35
  5554.7  403.47  5574.7  427.46  5584.7  434.97  5604.7  442.92  5624.7  440.62
  5674.7  426.79  5694.7  429.63  5744.7  448.59  5784.7  448.12  5805.6  451.55
#Mann= 5 ,-1 , 0
  4490.4     .05       0  4626.5      .1       0  4829.2     .16       0
  4851.7     .07       0  4857.7     .16       0
Bank Sta=4804.7,5244.7
XS Rating Curve= 0 ,0
Exp/Cntr=0.3,0.1

Type RM Length L Ch R = 1 ,46055   ,693,693,693
BEGIN DESCRIPTION:
UNT0170 IN SAND CR 9.0
END DESCRIPTION:
XS GIS Cut Line= 2
      3580078.82     10493200.98      3581016.32     10494450.98
#Sta/Elev= 30
  4162.5  496.97  4237.5  481.28  4329.2  494.78  4343.8  483.71  4358.4  463.65
  4443.8  457.22  4458.4  440.99  4464.6  446.21  4487.5  427.89  4493.8   430.5
  4508.4  410.22  4529.2  401.17  4537.5  386.41  4543.8  387.49  4550.8  371.06
  4643.8  361.65  4658.4  340.62  4672.9  332.81  4826.3  330.52  4940.8  329.86
  4943.5  329.36  4946.8  329.86  5093.8  346.12  5187.5  364.97  5332.3  372.46
  5579.2  377.85  5600.8  389.69  5637.5  425.82  5708.4  479.66    5725  480.71
#Mann= 5 ,-1 , 0
  4162.5     .05       0  4826.3     .16       0  4940.8     .07       0
  4946.8     .16       0  5332.3     .05       0
Bank Sta=4643.8,5187.5
XS Rating Curve= 0 ,0
Exp/Cntr=0.3,0.1

Type RM Length L Ch R = 1 ,45362   ,496,496,496
BEGIN DESCRIPTION:
UNT0170 IN SAND CR 7.0
END DESCRIPTION:
XS GIS Cut Line= 2
      3579675.18     10494212.27      3580925.18     10494681.02
#Sta/Elev= 30
  4175.7  491.82  4243.5  480.57    4304  479.32  4384.1  495.85  4428.7  497.04
  4499.8  477.54  4615.5  467.49  4645.7  467.79  4670.7  489.96  4700.9  472.88
  4725.8  449.57  4731.2  450.92  4756.1  415.56  4791.9  393.97  4902.1  376.18
  4962.7  378.35  4982.2  357.67  5002.5  349.97  5005.2  349.47  5008.5  349.97
  5058.9   376.7  5112.3  387.05  5251.1  465.53  5283.1  466.59  5304.5   477.1
  5323.9  474.61  5384.4   498.9  5439.6     499  5486.1  482.69  5510.7  489.63
#Mann= 3 ,-1 , 0
  4175.7     .05       0  5002.5     .03       0  5008.5     .05       0
Bank Sta=4962.7,5058.9
XS Rating Curve= 0 ,0
Exp/Cntr=0.3,0.1

Type RM Length L Ch R = 1 ,44866   ,367,367,367
BEGIN DESCRIPTION:
UNT0170 IN SAND CR 6.0
END DESCRIPTION:
XS GIS Cut Line= 2
      3579991.96     10495013.07      3580797.27     10494943.65
#Sta/Elev= 30
  4590.2  489.02  4610.4  488.63  4690.7  476.64  4740.9  486.08  4791.1  489.18
  4801.1  486.48  4821.2  466.51  4851.3   445.5  4861.4  442.87  4871.4  433.72
  4891.5  399.36  4897.2   385.2  4911.5  379.35  5007.6  372.22  5010.4  371.72
  5013.6  372.22  5082.2  377.67  5112.3  388.12  5122.3  390.26  5134.1   387.9
  5202.6  401.42  5242.5  429.32  5247.5  428.35  5252.8  435.46  5289.7  455.44
  5323.1  464.59  5360.9  469.08  5365.9  472.42  5389.3  472.54  5398.5  472.01
#Mann= 5 ,-1 , 0
  4590.2     .05       0  5007.6     .03       0  5013.6     .05       0
  5289.7      .1       0  5389.3     .05       0
Bank Sta=4891.5,5112.3
XS Rating Curve= 0 ,0
Exp/Cntr=0.3,0.1

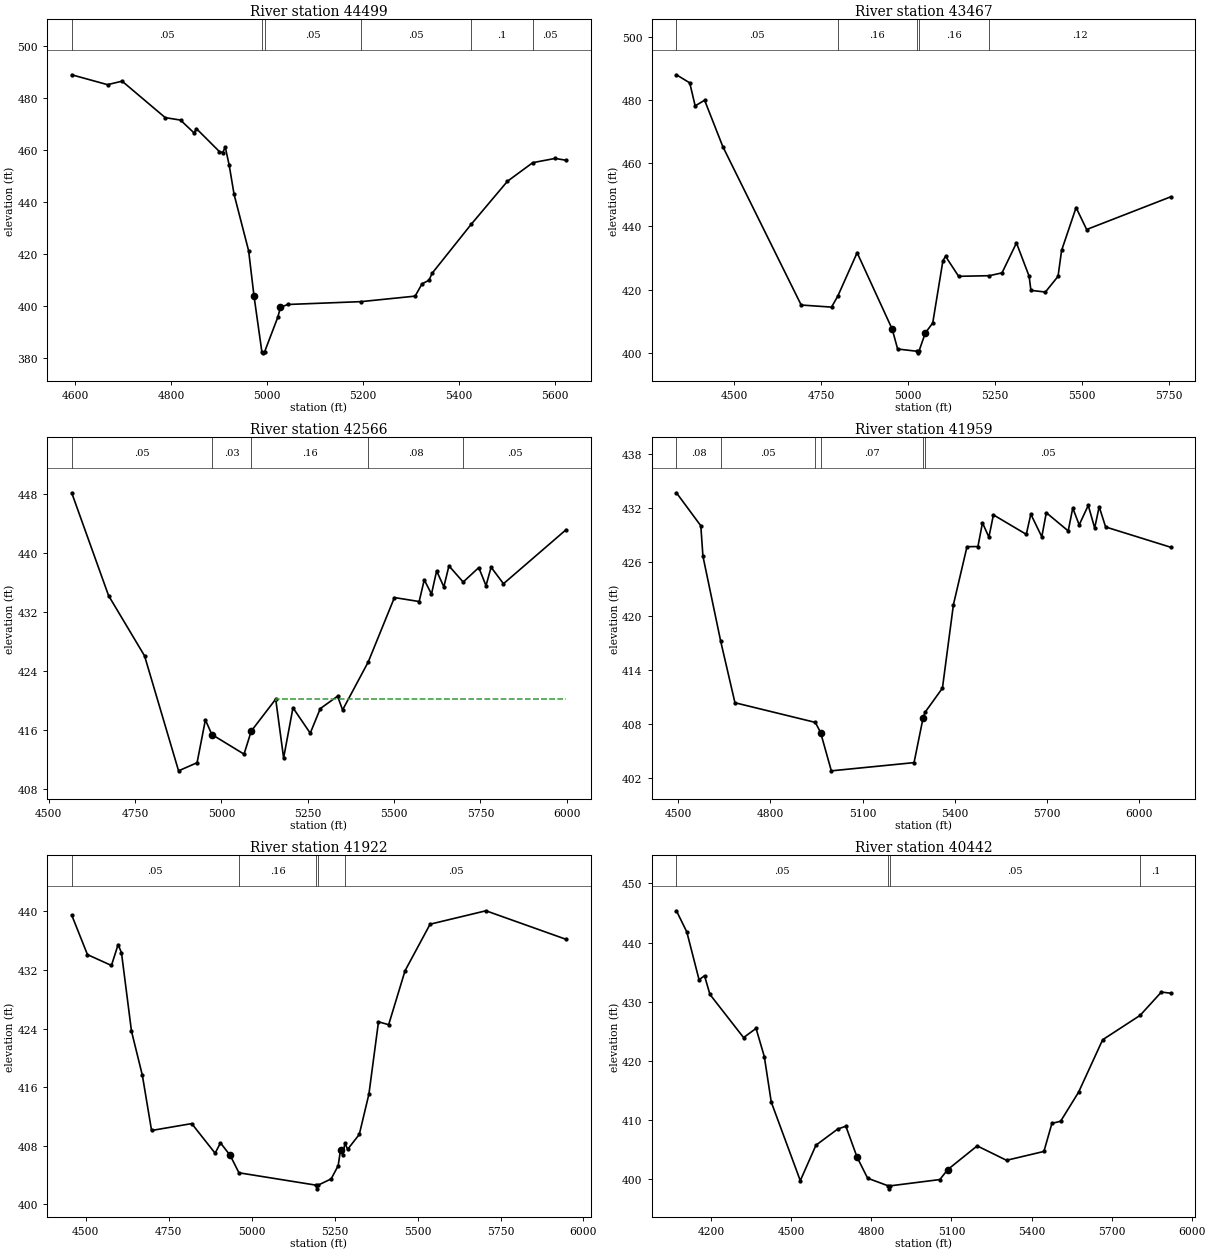
Type RM Length L Ch R = 1 ,44499   ,1032,1032,1032
BEGIN DESCRIPTION:
UNT0170 IN SAND CR 5.0
END DESCRIPTION:
XS GIS Cut Line= 3
      3580048.48     10495410.18      3580656.08     10495306.02
      3580981.57     10495049.97
#Sta/Elev= 30
  4592.6  489.07  4667.3  485.26  4697.7  486.61  4787.6  472.56  4819.5  471.61
  4847.6  466.68  4852.7  468.31  4900.7  459.45  4907.6  459.11  4912.7  461.25
    4921  454.21  4931.1  443.04  4961.5  421.24  4972.7  403.82    4989  382.43
  4991.7  381.93    4995  382.43  5022.4   395.7  5027.7  399.41  5042.7  400.56
  5195.9  401.66  5308.6  403.78  5323.1  408.53  5337.5  409.89    5344  412.57
  5425.3  431.41  5501.1  448.04  5553.9  455.21  5600.5  456.84  5623.2  456.14
#Mann= 6 ,-1 , 0
  4592.6     .05       0    4989     .07       0    4995     .05       0
  5195.9     .05       0  5425.3      .1       0  5553.9     .05       0
Bank Sta=4972.7,5027.7
XS Rating Curve= 0 ,0
Exp/Cntr=0.3,0.1

Type RM Length L Ch R = 1 ,43467   ,901,901,901
BEGIN DESCRIPTION:
UNT0170 IN SAND CR 3.0
END DESCRIPTION:
XS GIS Cut Line= 3
      3580044.07     10495957.05      3580716.85     10496360.71
      3581337.35     10496512.58
#Sta/Elev= 30
  4332.9  487.91  4371.2  485.35  4386.8  478.08    4414  479.87  4466.4  465.22
  4692.1  415.15  4779.4  414.49  4797.3  417.91  4853.2  431.68  4954.3   407.5
  4969.8  401.25  5025.2  400.54  5027.9  400.04  5031.2  400.54  5049.5  406.31
  5070.9  409.48  5100.3  429.19  5107.8  430.54  5145.5  424.22  5234.1  424.42
  5270.4  425.31    5312  434.77  5348.5  424.23  5353.6  419.79  5395.3  419.25
  5431.7  424.21    5442  432.41  5483.7  445.95  5514.1  439.01  5756.3  449.35
#Mann= 5 ,-1 , 0
  4332.9     .05       0  4797.3     .16       0  5025.2     .07       0
  5031.2     .16       0  5234.1     .12       0
Bank Sta=4954.3,5049.5
XS Rating Curve= 0 ,0
Exp/Cntr=0.3,0.1

Type RM Length L Ch R = 1 ,42566   ,607,607,607
BEGIN DESCRIPTION:
UNT0170 IN SAND CR 1.0
END DESCRIPTION:
XS GIS Cut Line= 4
       3580142.1     10496591.61      3580292.11     10496991.64
      3580592.11     10497391.64      3580880.83     10497805.08
#Sta/Elev= 30
  4566.4  448.17  4673.2  434.24  4777.4  426.08  4875.9  410.51  4929.5  411.61
  4953.6  417.41  4972.3  415.43  5065.5  412.77  5086.3  415.89  5157.2  420.22
  5180.1  412.26  5207.2  419.05  5257.2  415.61  5286.3  418.94  5336.3  420.62
  5350.9  418.76  5425.1  425.25    5501  433.98  5572.6  433.44  5587.4  436.38
  5608.3  434.45  5623.2  437.59  5644.1  435.43  5658.9  438.27  5700.1  436.08
  5745.3  438.04  5766.2  435.59    5781  438.09  5816.8  435.85  5997.9  443.16
#Mann= 5 ,-1 , 0
  4566.4     .05       0  4972.3     .03       0  5086.3     .16       0
  5425.1     .08       0  5700.1     .05       0
#XS Ineff= 2 , 0
       0  4957.5  412.76 5157.97       0  420.24
Permanent Ineff=
       T       F
Bank Sta=4972.3,5086.3
XS Rating Curve= 0 ,0
Exp/Cntr=0.3,0.1

Type RM Length L Ch R = 1 ,41959   ,37,37,37
BEGIN DESCRIPTION:
LAMBS CREEK 57.0
END DESCRIPTION:
XS GIS Cut Line= 4
      3579962.45     10496745.69      3579847.87     10497125.92
      3579587.45     10497412.37       3578916.3     10497891.02
#Sta/Elev= 30
  4494.2  433.65  4573.5  429.99  4580.4  426.62  4638.2  417.19  4684.6  410.37
  4946.2  408.19  4963.3  407.07  4998.2  402.82  5267.4  403.73  5297.1  408.73
  5303.2  409.31  5359.8  411.99  5395.6  421.25  5439.7  427.67  5475.3  427.69
  5490.1  430.32    5511  428.73  5525.7   431.2  5632.7  429.04  5647.4  431.28
  5683.1  428.77  5697.8  431.44  5769.1  429.42  5783.9  431.96  5804.8  430.09
  5834.3  432.25  5855.2  429.75  5869.9   432.1  5890.8  429.86  6102.8  427.61
#Mann= 6 ,-1 , 0
  4494.2     .08       0  4638.2     .05       0  4946.2     .16       0
  4963.3     .07       0  5297.1     .16       0  5303.2     .05       0
Bank Sta=4963.3,5297.1
XS Rating Curve= 0 ,0
Exp/Cntr=0.3,0.1

Type RM Length L Ch R = 1 ,41922   ,1480,1480,1480
BEGIN DESCRIPTION:
LAMBS CREEK 56.0
END DESCRIPTION:
XS GIS Cut Line= 4
      3579863.49     10496672.83       3579806.2     10497125.92
      3579504.12     10497417.58      3578967.68     10497714.44
#Sta/Elev= 30
  4457.7  439.48  4505.2  434.08  4577.5   432.6  4597.6  435.45  4607.7  434.34
  4637.9  423.63  4670.6  417.63  4698.4  410.09  4819.4  411.03  4889.9  406.99
  4906.1   408.4  4935.4  406.69  4961.7  404.32  5194.3  402.63    5197  402.13
  5200.3  402.63  5239.7  403.49  5260.8  405.29  5267.8  407.42    5275  406.75
  5281.1  408.39  5289.1  407.51  5324.4  409.55  5353.4  415.05  5382.3  424.92
  5412.9  424.52  5462.3  431.88  5537.8  438.23  5706.1  440.06  5947.4  436.17
#Mann= 5 ,-1 , 0
  4457.7     .05       0  4961.7     .16       0  5194.3     .07       0
  5200.3     .16       0  5281.1     .05       0
Bank Sta=4935.4,5267.8
XS Rating Curve= 0 ,0
Exp/Cntr=0.3,0.1

Type RM Length L Ch R = 1 ,40442   ,1221,1221,1221
BEGIN DESCRIPTION:
LAMBS CREEK 54.0
END DESCRIPTION:
XS GIS Cut Line= 3
      3578269.73     10496188.39      3578410.37     10496917.58
      3578405.16     10498026.84
#Sta/Elev= 30
  4069.8  445.38  4108.7  441.79  4154.6   433.7    4175  434.39  4195.3  431.22
  4321.3  423.92  4368.1  425.47    4399   420.7    4425  413.01  4533.8   399.7
  4592.5  405.71    4674  408.44  4704.5  408.92  4746.4  403.69    4786  400.12
  4863.5  398.82  4866.2  398.32  4869.5  398.82  5056.5  399.89  5086.5  401.59
  5196.5  405.59  5306.5  403.15  5446.5  404.65  5476.5   409.4  5509.1  409.76
  5576.5  414.69  5666.5  423.55  5806.9  427.68  5886.5  431.62  5921.7  431.43
#Mann= 4 ,-1 , 0
  4069.8     .05       0  4863.5     .03       0  4869.5     .05       0
  5806.9      .1       0
Bank Sta=4746.4,5086.5
XS Rating Curve= 0 ,0
Exp/Cntr=0.3,0.1

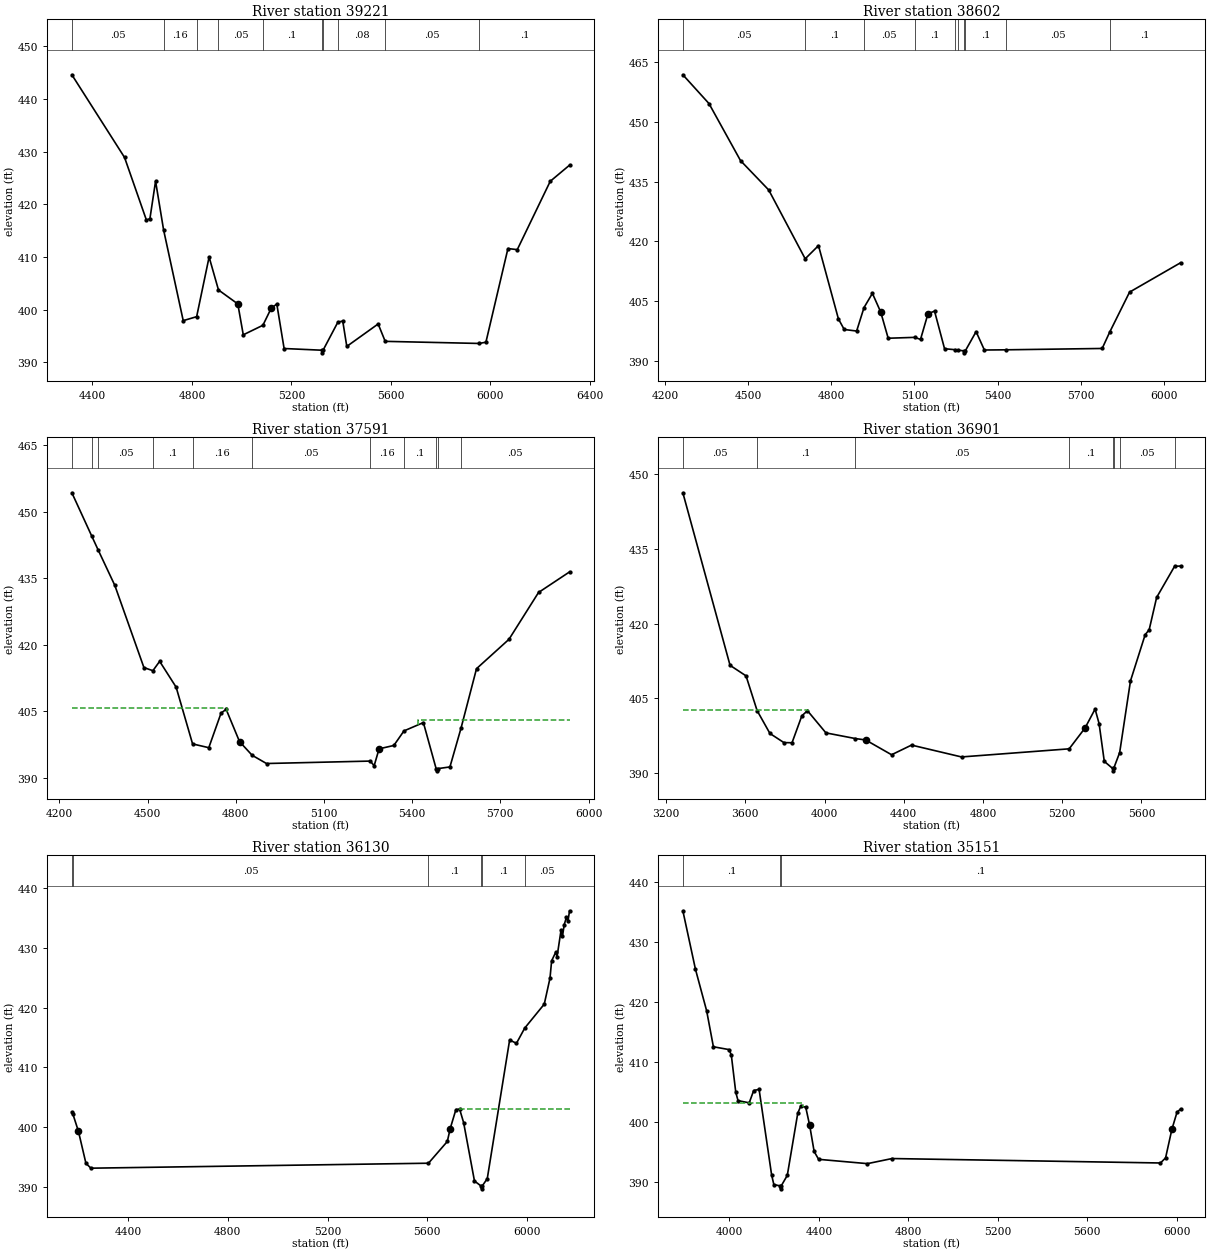
Type RM Length L Ch R = 1 ,39221   ,619,619,619
BEGIN DESCRIPTION:
LAMBS CREEK 53.0
END DESCRIPTION:
XS GIS Cut Line= 2
      3577014.55     10496344.71      3577957.15     10498110.13
#Sta/Elev= 30
  4317.3  444.57  4529.2  428.88  4617.1     417  4631.2  417.27  4653.9  424.38
  4686.2  415.13  4765.1  397.92  4819.1  398.67  4869.2  409.99  4906.9  403.74
  4984.6  401.09  5006.6  395.23  5085.5  397.04  5118.7  400.25  5141.4  401.08
  5170.8  392.63  5321.5  392.31  5324.3  391.81  5327.5  392.31  5387.2  397.65
  5406.6  397.83  5422.9  393.03    5549  397.29  5577.3  393.99  5955.2  393.59
  5982.3  393.83  6070.9   411.6  6108.4  411.39    6241  424.36  6318.6  427.42
#Mann= 10 ,-1 , 0
  4317.3     .05       0  4686.2     .16       0  4819.1      .1       0
  4906.9     .05       0  5085.5      .1       0  5321.5    .035       0
  5327.5      .1       0  5387.2     .08       0  5577.3     .05       0
  5955.2      .1       0
Bank Sta=4984.6,5118.7
XS Rating Curve= 0 ,0
Exp/Cntr=0.3,0.1

Type RM Length L Ch R = 1 ,38602   ,1011,1011,1011
BEGIN DESCRIPTION:
LAMBS CREEK 52.0
END DESCRIPTION:
XS GIS Cut Line= 2
      3576462.46     10496750.93      3577472.86     10498235.28
#Sta/Elev= 30
  4264.4   461.9  4358.7  454.66  4472.5  440.32  4574.2  432.94  4705.8  415.64
  4753.8  418.96  4825.7  400.52  4846.6  397.87  4891.4  397.48  4918.1  403.39
  4948.3  406.95  4978.2  402.27  5005.2  395.67  5100.6  395.89  5121.9  395.38
  5148.9  401.85  5172.5  402.48  5208.6  393.03  5246.8  392.79  5258.7  392.67
  5277.5   392.5  5280.2     392  5283.5   392.5  5322.4  397.33  5352.3  392.71
  5428.9  392.76  5777.3   393.1  5804.4   397.2  5876.1  407.26    6060  414.64
#Mann= 10 ,-1 , 0
  4264.4     .05       0  4705.8      .1       0  4918.1     .05       0
  5100.6      .1       0  5246.8     .08       0  5258.7      .1       0
  5277.5    .035       0  5283.5      .1       0  5428.9     .05       0
  5804.4      .1       0
Bank Sta=4978.2,5148.9
XS Rating Curve= 0 ,0
Exp/Cntr=0.3,0.1

Type RM Length L Ch R = 1 ,37591   ,690,690,690
BEGIN DESCRIPTION:
LAMBS CREEK 53.1
END DESCRIPTION:
XS GIS Cut Line= 3
      3576118.93      10496835.7      3575858.51     10497700.29
       3575785.6     10498486.66
#Sta/Elev= 30
  4242.6  454.31  4309.8  444.61  4331.8  441.45  4388.7  433.43  4487.7   414.9
  4518.2   414.2  4541.2  416.31  4597.2  410.49  4653.2  397.69  4708.3  396.84
  4750.1  404.65  4767.4  405.48  4812.8  398.22  4855.7  395.13  4904.6  393.27
  5257.3  393.82  5270.8  392.78  5287.5  396.58  5337.7  397.34  5372.1  400.62
  5438.2   402.5  5481.5  392.12  5484.3  391.62  5487.5  392.12  5528.5   392.5
  5566.3  401.26  5618.9  414.65  5729.4  421.28  5829.8  431.83  5935.3  436.47
#Mann= 11 ,-1 , 0
  4242.6     .05       0  4309.8      .1       0  4331.8     .05       0
  4518.2      .1       0  4653.2     .16       0  4855.7     .05       0
  5257.3     .16       0  5372.1      .1       0  5481.5    .033       0
  5487.5      .1       0  5566.3     .05       0
#XS Ineff= 2 , 0
         4771.62  405.72 5418.18           403.1
Permanent Ineff=
       F       F
Bank Sta=4812.8,5287.5
XS Rating Curve= 0 ,0
Exp/Cntr=0.3,0.1

Type RM Length L Ch R = 1 ,36901   ,771,771,771
BEGIN DESCRIPTION:
LAMBS CREEK 52.2
END DESCRIPTION:
XS GIS Cut Line= 3
      3575421.01     10495814.83      3575191.84     10497762.79
      3575274.95      10498308.2
#Sta/Elev= 30
  3284.4  446.27  3522.8  411.62  3603.4  409.51  3659.3  402.54  3724.2  397.94
  3794.7  396.11  3835.7  396.08  3885.3  401.49  3913.7  402.51  4006.9  398.06
  4155.8  396.92  4207.5  396.64  4338.4  393.67  4439.1  395.61  4691.5  393.23
  5235.2  394.86  5315.4  399.05    5366  402.84  5386.2  399.94  5412.5  392.34
  5454.1  390.94  5456.8  390.44  5460.1  390.94  5490.1   394.1  5544.7  408.49
  5618.9  417.78  5639.1  418.76  5676.8  425.25  5767.5  431.51  5797.5  431.56
#Mann= 8 ,-1 , 0
  3284.4     .05       0  3659.3      .1       0  4155.8     .05       0
  5235.2      .1       0  5454.1    .033       0  5460.1      .1       0
  5490.1     .05       0  5767.5      .1       0
#XS Ineff= 2 , 0
         3914.01  402.59 5366.17          402.78
Permanent Ineff=
       F       F
Bank Sta=4207.5,5315.4
XS Rating Curve= 0 ,0
Exp/Cntr=0.3,0.1

Type RM Length L Ch R = 1 ,36130   ,979,979,979
BEGIN DESCRIPTION:
LAMBS CREEK 52.1
END DESCRIPTION:
XS GIS Cut Line= 3
      3574441.84     10496575.28      3574467.88     10497611.75
       3574931.4     10498450.26
#Sta/Elev= 30
  4175.1  402.55  4178.6  402.29  4201.5  399.32  4231.5  393.98  4251.5  393.17
  5604.5     394  5680.1  397.63  5691.7  399.79  5714.5  402.96  5729.4  403.03
  5745.4  400.79  5788.9  391.03  5814.4  390.22  5817.1  389.72  5820.4  390.22
  5840.2  391.42  5929.8  414.57  5957.3  414.03  5990.4  416.57  6068.7  420.57
  6091.6   424.9  6098.2   427.8  6114.3  429.22    6120   428.5    6136  432.94
  6141.7   431.9  6148.7  433.85  6157.8   435.1  6163.5  434.38    6170  436.16
#Mann= 6 ,-1 , 0
  4175.1      .1       0  4178.6     .05       0  5604.5      .1       0
  5814.4    .033       0  5820.4      .1       0  5990.4     .05       0
#XS Ineff= 2 , 0
                         5725.85          403.05
Permanent Ineff=
       F       F
Bank Sta=4201.5,5691.7
XS Rating Curve= 0 ,0
Exp/Cntr=0.3,0.1

Type RM Length L Ch R = 1 ,35151   ,47,47,47
BEGIN DESCRIPTION:
LAMBS CREEK 51.2
END DESCRIPTION:
XS GIS Cut Line= 6
      3573396.44     10496325.29      3573365.19      10496873.9
      3573365.19     10496985.01      3573521.44     10497571.81
      3573642.97     10498044.04      3574068.56     10498244.72
#Sta/Elev= 30
  3791.4  435.27  3847.8  425.52  3897.9  418.58    3928   412.6  3998.1  412.13
  4008.1  411.23  4028.1  405.01  4038.2  403.62  4088.2  403.26  4108.3  405.31
  4132.4   405.5  4188.4  391.24  4198.4  389.63  4225.5  389.42  4228.2  388.92
  4231.5  389.42  4258.5  391.16  4305.4  401.54  4318.6  402.69  4340.9  402.55
  4358.6   399.5  4378.6  395.15  4398.6  393.84  4617.1  393.12  4727.1  393.97
  5927.7  393.23  5950.5  394.08  5978.8  398.85  6001.6  401.68  6017.4  402.23
#Mann= 3 ,-1 , 0
  3791.4      .1       0  4225.5     .07       0  4231.5      .1       0
#XS Ineff= 2 , 0
         4330.11   403.2
Permanent Ineff=
       F       F
Bank Sta=4358.6,5978.8
XS Rating Curve= 0 ,0
Exp/Cntr=0.3,0.1

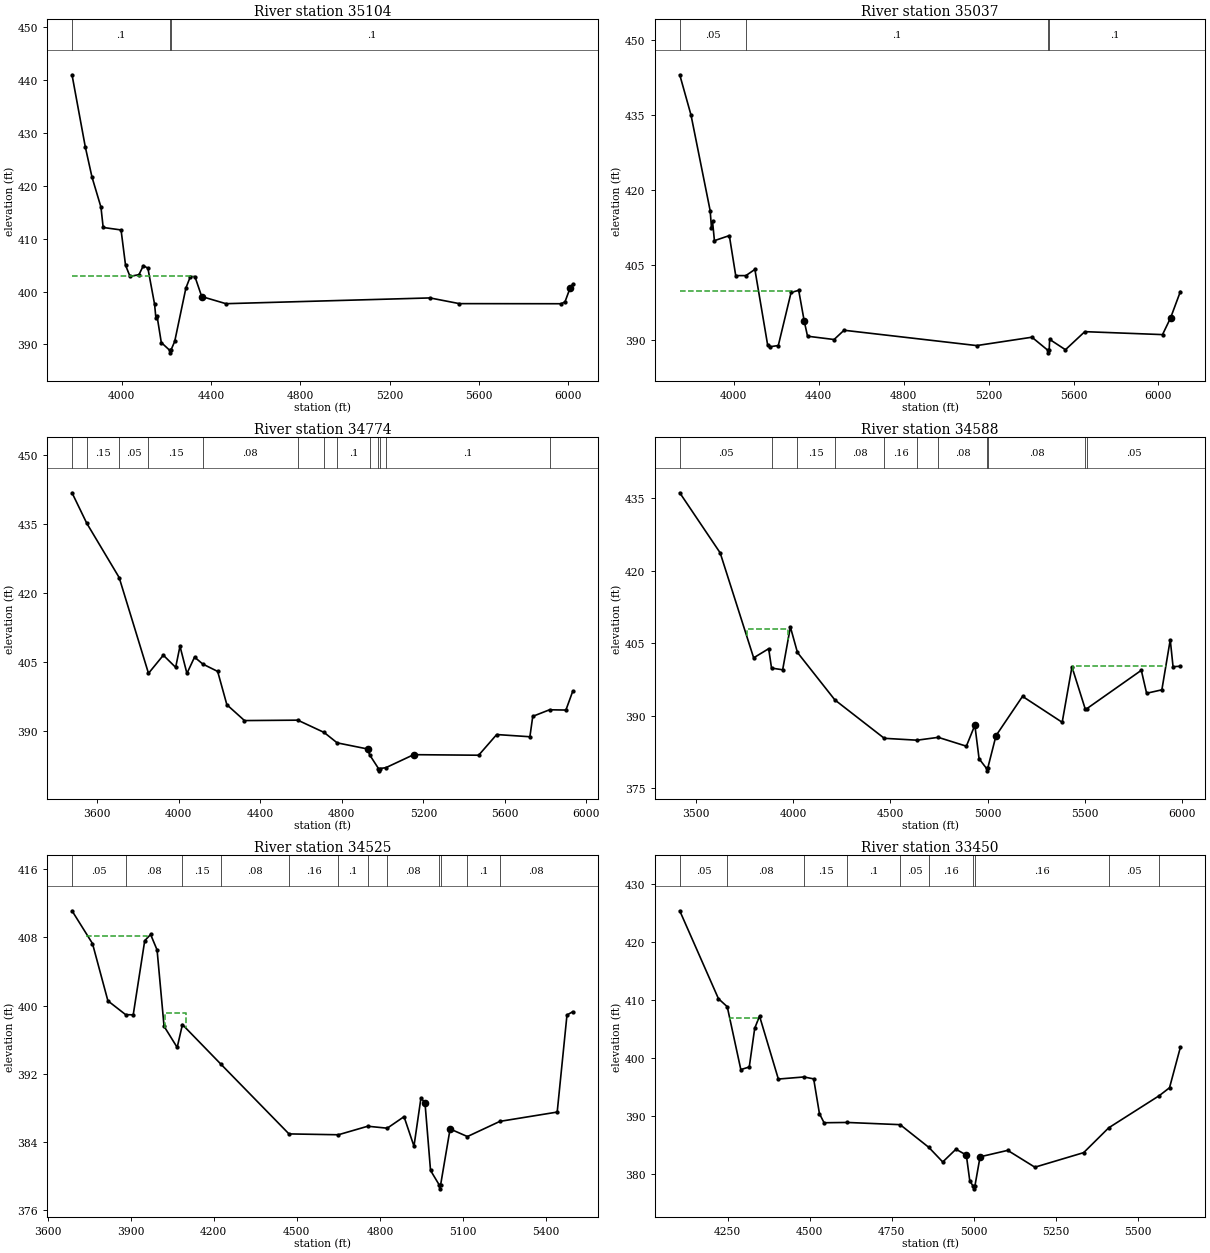
Type RM Length L Ch R = 1 ,35104   ,67,67,67
BEGIN DESCRIPTION:
LAMBS CREEK 51.0
END DESCRIPTION:
XS GIS Cut Line= 5
        3573327.     10496332.26      3573299.22     10496856.54
      3573330.47     10497040.56      3573608.25     10498071.81
      3574021.42     10498280.14
#Sta/Elev= 30
  3777.8  441.02  3837.3  427.37  3867.3  421.66  3907.4  415.98  3917.4  412.13
  3997.5  411.66  4017.5     405  4037.5  402.88  4077.6   403.2  4097.6  404.92
  4117.7  404.41  4147.7  397.59  4153.3  395.07  4158.3  395.47  4177.7  390.36
  4214.8  388.91  4217.5  388.41  4220.8  388.91  4237.8  390.57  4287.9  400.67
    4308  402.85  4328.3  402.84  4358.7  399.06  4467.3  397.71  5381.2   398.8
  5512.7  397.72  5969.3   397.7    5986  398.07  6008.3  400.63  6020.2  401.39
#Mann= 3 ,-1 , 0
  3777.8      .1       0  4214.8     .07       0  4220.8      .1       0
#XS Ineff= 2 , 0
         4319.89  403.04
Permanent Ineff=
       F       F
Bank Sta=4358.7,6008.3
XS Rating Curve= 0 ,0
Exp/Cntr=0.3,0.1

Type RM Length L Ch R = 1 ,35037   ,263,263,263
BEGIN DESCRIPTION:
LAMBS CREEK 51.1
END DESCRIPTION:
XS GIS Cut Line= 5
      3573267.97     10496328.75      3573229.78     10496856.54
      3573535.33     10498106.54      3573983.25     10498325.29
      3574018.73     10498301.44
#Sta/Elev= 30
    3746     443    3799  434.97  3889.3  415.85  3895.4  412.45  3900.4  413.73
  3909.3  409.88  3979.5  410.89  4009.6   402.9  4057.5   402.9  4099.8  404.14
    4160  389.02  4169.3  388.69  4210.1  388.94  4270.2  399.53  4306.1  399.96
  4331.9  393.86  4347.7   390.8  4472.7  390.14  4519.5  391.99  5144.2  388.93
  5404.3   390.6  5479.5  387.98  5482.2  387.48  5485.5  387.98  5487.6  390.17
    5562   388.1  5653.2  391.71  6019.1  391.12    6057  394.46  6103.2  399.72
#Mann= 4 ,-1 , 0
    3746     .05       0  4057.5      .1       0  5479.5     .07       0
  5485.5      .1       0
#XS Ineff= 2 , 0
         4278.98   399.8
Permanent Ineff=
       F       F
Bank Sta=4331.9,6057
XS Rating Curve= 0 ,0
Exp/Cntr=0.3,0.1

Type RM Length L Ch R = 1 ,34774   ,186,186,186
BEGIN DESCRIPTION:
LAMBS CREEK 50.01
END DESCRIPTION:
XS GIS Cut Line= 6
      3572673.34     10496242.93      3572846.95     10497083.21
      3573107.37     10497512.61      3573204.59     10497790.38
      3573433.76     10498168.86      3573682.47     10498427.93
#Sta/Elev= 30
  3476.3  441.78  3548.5  435.16  3707.6  423.33  3851.5  402.48  3924.3  406.43
  3984.8  403.78    4006  408.39  4040.1  402.46  4077.4  406.01    4118   404.5
  4190.8   402.9    4236  395.65  4322.5   392.2  4583.9  392.29  4712.9  389.62
  4777.1  387.35    4926  386.02  4936.5  384.74  4979.8  381.76  4982.6  381.26
  4985.8  381.76  5016.2  381.95  5152.4  384.78  5471.3  384.66  5559.7  389.16
  5722.6  388.68  5736.7  393.12    5819  394.55  5899.3  394.49  5932.4  398.53
#Mann= 13 ,-1 , 0
  3476.3     .05       0  3548.5     .15       0  3707.6     .05       0
  3851.5     .15       0    4118     .08       0  4583.9      .1       0
  4712.9     .08       0  4777.1      .1       0  4936.5     .08       0
  4979.8     .07       0  4985.8     .08       0  5016.2      .1       0
    5819     .15       0
Bank Sta=4926,5152.4
XS Rating Curve= 0 ,0
Exp/Cntr=0.3,0.1

Type RM Length L Ch R = 1 ,34588   ,63,63,63
BEGIN DESCRIPTION:
LAMBS CREEK 50.0
END DESCRIPTION:
XS GIS Cut Line= 5
      3572478.91     10496236.03      3572770.56     10497229.04
      3573027.51     10497826.26      3573090.01     10498145.71
      3573527.28     10498499.69
#Sta/Elev= 30
    3418  436.15  3625.8  423.72  3797.9     402  3875.1  403.89  3889.8  399.88
    3947  399.53  3986.7  408.38    4023  403.11  4215.4  393.29  4469.3  385.35
    4638  384.96  4746.7  385.55  4891.2  383.72  4934.8  388.07  4956.6  381.11
  4994.8  379.12  4997.5  378.62  5000.8  379.12  5043.6   385.9  5179.9  394.03
  5383.7  388.66  5433.9  400.13  5501.5   391.5  5508.8  391.44  5790.4  399.42
  5817.6  394.67    5896  395.38  5939.1  405.74  5953.5  400.17  5991.2  400.26
#Mann= 11 ,-1 , 0
    3418     .05       0  3889.8     .08       0    4023     .15       0
  4215.4     .08       0  4469.3     .16       0    4638      .1       0
  4746.7     .08       0  4994.8     .07       0  5000.8     .08       0
  5501.5      .1       0  5508.8     .05       0
#XS Ineff= 2 ,-1
 3761.93    3975  408.02 5440.91 5916.48  400.23
Permanent Ineff=
       F       F
Bank Sta=4934.8,5043.6
XS Rating Curve= 0 ,0
Exp/Cntr=0.3,0.1

Type RM Length L Ch R = 1 ,34525   ,1075,1075,1075
BEGIN DESCRIPTION:
LAMBS CREEK 50.02
END DESCRIPTION:
XS GIS Cut Line= 4
      3572482.36     10496495.22      3572919.87     10497686.22
      3572951.12     10497932.75      3573055.29     10498203.58
#Sta/Elev= 30
  3688.3  411.11  3762.2  407.27  3817.9  400.55    3882  398.93  3909.3  398.91
  3950.8   407.6  3972.1  408.33  3995.4  406.52  4020.6  397.57    4068  395.09
  4086.9  397.77  4225.7  393.13  4471.6  384.95  4649.9  384.85    4756  385.85
  4826.4  385.62    4887  386.97  4922.9  383.51    4948  389.14  4962.6  388.62
  4982.7  380.67  5013.3  379.01  5016.1  378.51  5019.3  379.01  5053.3  385.53
  5115.8  384.64  5233.1  386.42    5440  387.51  5475.3  398.89  5495.8  399.27
#Mann= 12 ,-1 , 0
  3688.3     .05       0    3882     .08       0  4086.9     .15       0
  4225.7     .08       0  4471.6     .16       0  4649.9      .1       0
    4756     .16       0  4826.4     .08       0  5013.3     .07       0
  5019.3     .08       0  5115.8      .1       0  5233.1     .08       0
#XS Ineff= 2 ,-1
 3739.77 3960.23  408.19 4023.86    4100  399.13
Permanent Ineff=
       F       F
Bank Sta=4962.6,5053.3
XS Rating Curve= 0 ,0
Exp/Cntr=0.3,0.1

Type RM Length L Ch R = 1 ,33450   ,95,95,95
BEGIN DESCRIPTION:
LAMBS CREEK 49.03
END DESCRIPTION:
XS GIS Cut Line= 4
      3572405.49     10496345.59      3572126.23     10497161.52
      3572079.35     10497312.56      3571741.25     10497687.07
#Sta/Elev= 30
    4104  425.34    4222  410.18  4248.7  408.81  4290.1  397.97  4315.8  398.42
  4332.4  405.09  4347.1  407.19  4404.4  396.34  4482.3   396.7    4512  396.37
  4529.6  390.37  4543.7  388.81  4614.5  388.86  4775.4  388.48  4862.7  384.57
  4905.2  382.05  4945.4  384.25    4977  383.24  4987.5  378.82  4997.2  377.92
  4999.9  377.42  5003.2  377.92  5018.9  382.94  5103.1  384.05  5185.8  381.15
  5334.5  383.66  5410.6  387.93  5564.8  393.48    5596  394.84  5629.1  401.82
#Mann= 10 ,-1 , 0
    4104     .05       0  4248.7     .08       0  4482.3     .15       0
  4614.5      .1       0  4775.4     .05       0  4862.7     .16       0
  4997.2     .07       0  5003.2     .16       0  5410.6     .05       0
  5564.8      .1       0
#XS Ineff= 1 ,-1
 4257.73 4341.59  406.87
Permanent Ineff=
       F
Bank Sta=4977,5018.9
XS Rating Curve= 0 ,0
Exp/Cntr=0.3,0.1