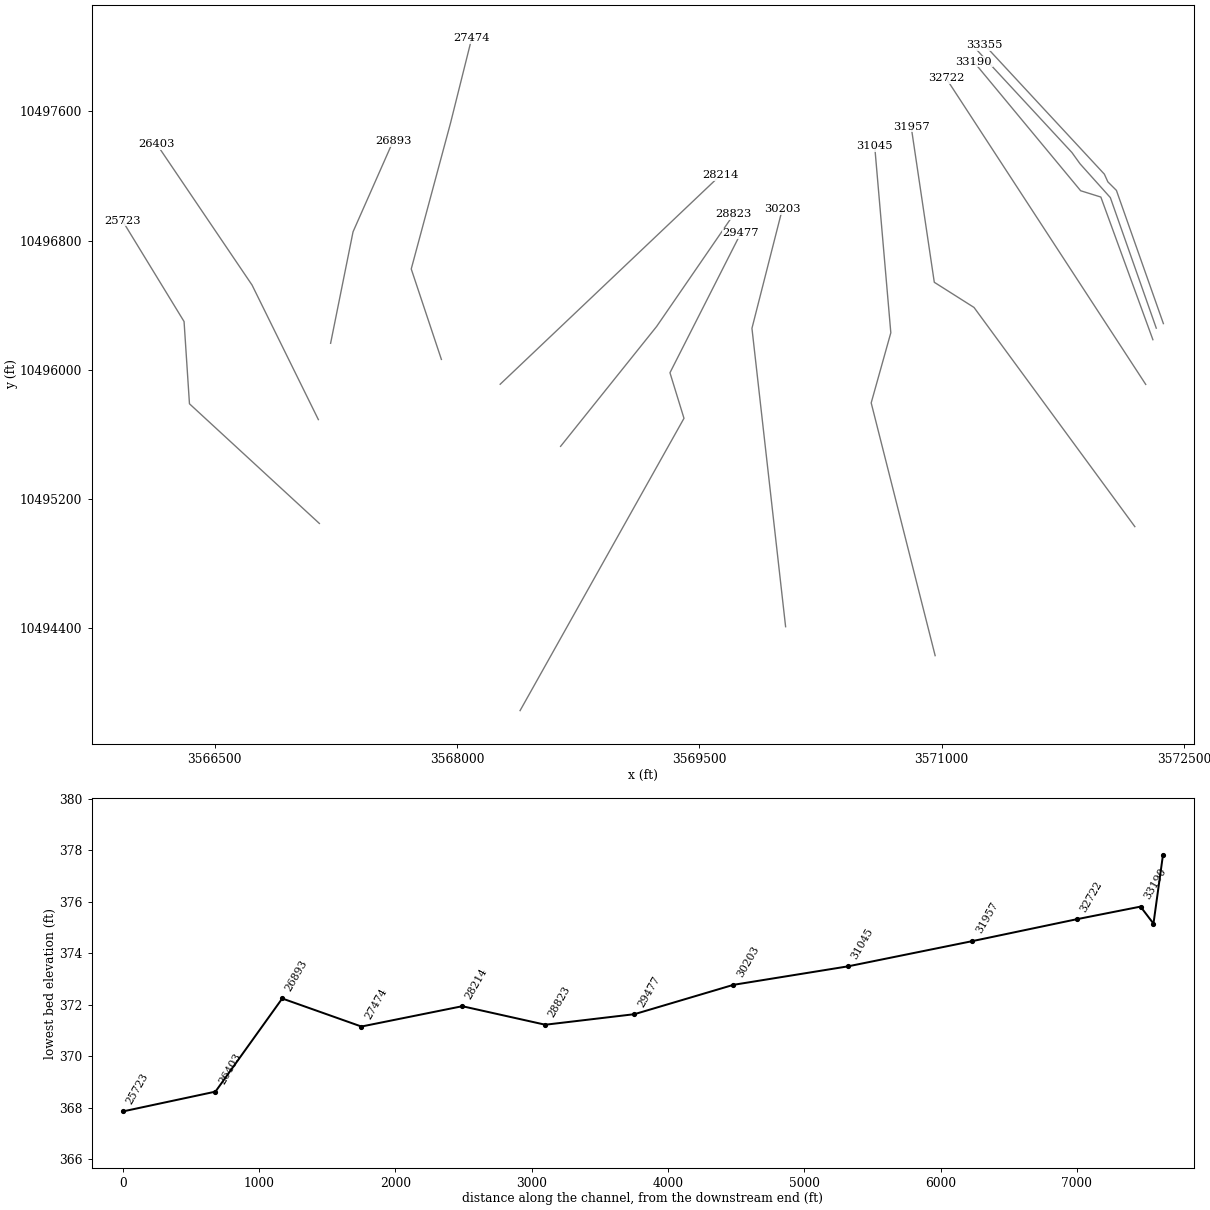
HEC-RAS study LAMBS CREEK.prj: LAMBS CREEK Base Level Engineering

--- LAMBS CREEK.g01 (geometry) --- (continued)

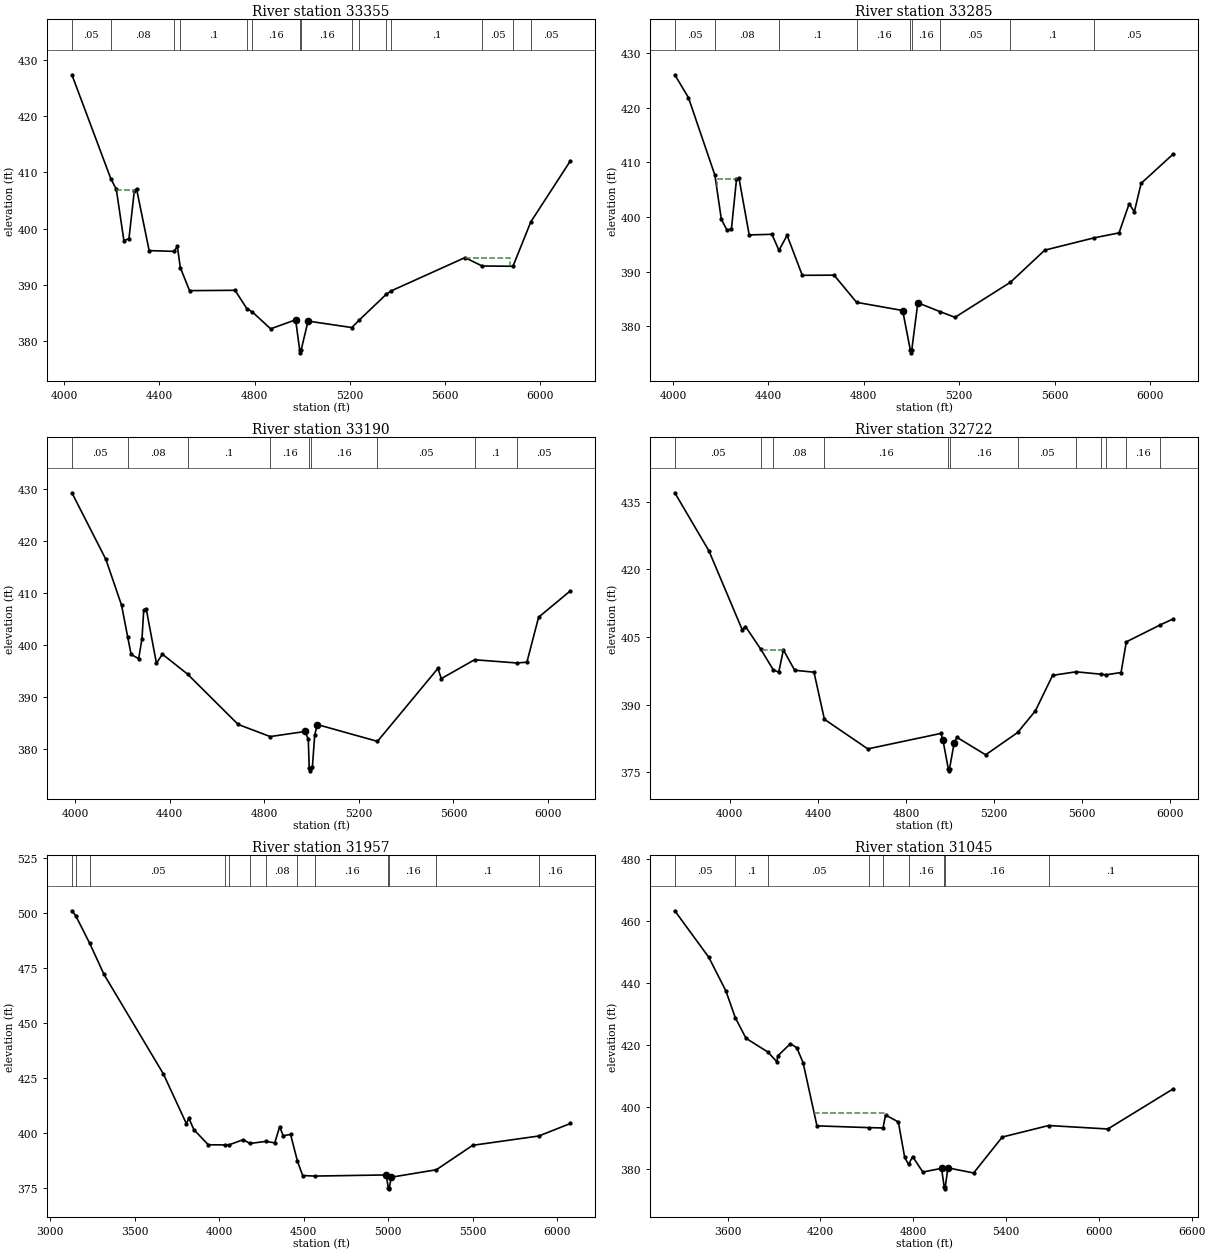
Type RM Length L Ch R = 1 ,33355   ,70,70,70
BEGIN DESCRIPTION:
LAMBS CREEK 49.02
END DESCRIPTION:
XS GIS Cut Line= 5
      3572373.04     10496285.91      3572082.24     10497110.56
      3572029.29     10497163.37      3572007.59     10497211.11
      3571265.82     10498010.94
#Sta/Elev= 30
  4033.5  427.41  4196.8  408.88  4219.8     407  4251.7  397.85  4272.9  398.19
  4295.6  406.74  4304.7   407.1  4357.7  396.06  4462.7  395.92    4476  396.82
  4488.6  393.01  4527.3  388.92  4718.2  388.98  4767.8  385.71  4791.2  385.11
  4867.6  382.11  4972.4  383.72  4989.6  378.33  4992.4  377.83  4995.6  378.33
  5024.7  383.49  5208.2  382.34  5239.2  383.66  5352.2  388.24  5372.8  388.86
  5683.3  394.81  5755.6  393.31  5884.8  393.27  5959.5  401.17    6126  412.08
#Mann= 15 ,-1 , 0
  4033.5     .05       0  4196.8     .08       0  4462.7     .15       0
  4488.6      .1       0  4767.8     .05       0  4791.2     .16       0
  4989.6     .07       0  4995.6     .16       0  5208.2     .05       0
  5239.2      .1       0  5352.2     .05       0  5372.8      .1       0
  5755.6     .05       0  5884.8     .16       0  5959.5     .05       0
#XS Ineff= 2 ,-1
 4220.17 4294.03  406.95 5681.82 5872.16  394.71
Permanent Ineff=
       F       F
Bank Sta=4972.4,5024.7
XS Rating Curve= 0 ,0
Exp/Cntr=0.3,0.1

Type RM Length L Ch R = 1 ,33285   ,95,95,95
BEGIN DESCRIPTION:
LAMBS CREEK 49.0
END DESCRIPTION:
XS GIS Cut Line= 5
      3572328.89     10496257.83      3572044.59     10497065.97
      3571856.87     10497275.38      3571806.96     10497344.83
      3571218.83     10497979.61
#Sta/Elev= 30
    4008  426.01    4065  421.85  4175.9  407.66  4202.9   399.6  4226.8  397.57
  4245.3  397.83  4266.5  406.87  4277.1  407.05  4319.7  396.72  4414.9  396.83
  4444.4   393.9  4478.5  396.64  4542.1  389.33  4675.4  389.36  4769.7  384.39
  4962.7  382.89  4994.8  375.65  4997.6  375.15  5000.8  375.65  5026.2  384.31
  5118.3   382.7  5182.1  381.65  5414.4  388.06    5558  393.93  5765.4  396.19
  5869.3  397.09  5911.8  402.44  5933.3  400.92  5961.7  406.14  6096.8  411.54
#Mann= 9 ,-1 , 0
    4008     .05       0  4175.9     .08       0  4444.4      .1       0
  4769.7     .16       0  4994.8     .07       0  5000.8     .16       0
  5118.3     .05       0  5414.4      .1       0  5765.4     .05       0
#XS Ineff= 1 ,-1
 4183.24 4268.47  406.95
Permanent Ineff=
       F
Bank Sta=4962.7,5026.2
XS Rating Curve= 0 ,0
Exp/Cntr=0.3,0.1

Type RM Length L Ch R = 1 ,33190   ,468,468,468
BEGIN DESCRIPTION:
LAMBS CREEK 49.01
END DESCRIPTION:
XS GIS Cut Line= 4
      3572308.04     10496186.27      3571985.89     10497069.33
      3571860.89     10497108.39      3571198.58     10497907.31
#Sta/Elev= 30
  3986.1   429.3  4129.8  416.48  4196.2  407.66  4221.9  401.59  4236.6   398.2
  4268.6  397.38  4282.6  401.26  4289.9  406.73  4300.5  406.95  4343.7   396.5
  4368.9  398.25  4475.1  394.42  4689.1  384.74  4824.8   382.4    4972  383.38
  4985.9  381.89  4989.9  376.31  4992.7  375.81  4995.9  376.31  5003.4  376.62
  5013.1  382.72  5024.3  384.71  5278.5  381.48  5534.2  395.51  5548.5  393.55
  5689.2  397.18  5867.8  396.56  5910.6  396.71  5960.1  405.36  6094.8  410.45
#Mann= 9 ,-1 , 0
  3986.1     .05       0  4221.9     .08       0  4475.1      .1       0
  4824.8     .16       0  4989.9     .07       0  4995.9     .16       0
  5278.5     .05       0  5689.2      .1       0  5867.8     .05       0
#XS Ineff= 1 ,-1
 4197.16 4292.61  406.72
Permanent Ineff=
       F
Bank Sta=4972,5024.3
XS Rating Curve= 0 ,0
Exp/Cntr=0.3,0.1

Type RM Length L Ch R = 1 ,32722   ,765,765,765
BEGIN DESCRIPTION:
LAMBS CREEK 47.1
END DESCRIPTION:
XS GIS Cut Line= 2
       3572263.6     10495909.63       3571027.5     10497805.45
#Sta/Elev= 30
  3750.7     437  3905.7  424.11  4056.5  406.64  4071.6  407.33  4141.3  402.28
  4197.7  397.73  4222.5  397.21  4243.6  402.15  4294.9  397.63  4382.5   397.2
  4429.9  386.75  4626.8  380.19  4958.8  383.62  4967.9  382.16    4992  375.82
  4994.7  375.32    4998  375.82  5018.5   381.4  5031.2  382.77  5161.8  378.87
  5307.2  383.83  5387.4  388.61  5465.8   396.5  5571.9  397.29  5686.2  396.75
  5707.8  396.62  5776.6  397.13  5800.4  403.93  5955.2  407.71  6013.9  409.04
#Mann= 12 ,-1 , 0
  3750.7     .05       0  4141.3      .1       0  4197.7     .08       0
  4429.9     .16       0    4992     .07       0    4998     .16       0
  5307.2     .05       0  5571.9     .15       0  5686.2      .1       0
  5707.8     .05       0  5800.4     .16       0  5955.2     .05       0
#XS Ineff= 1 ,-1
 4144.32 4241.48  402.07
Permanent Ineff=
       F
Bank Sta=4967.9,5018.5
XS Rating Curve= 0 ,0
Exp/Cntr=0.3,0.1

Type RM Length L Ch R = 1 ,31957   ,912,912,912
BEGIN DESCRIPTION:
LAMBS CREEK 46.3
END DESCRIPTION:
XS GIS Cut Line= 4
      3572196.28     10495029.16      3571200.69     10496386.06
      3570954.86     10496541.71      3570811.63      10497505.3
#Sta/Elev= 30
  3129.5  500.83    3152   498.6  3235.1  485.98  3319.4  471.89  3670.6  426.67
  3806.4  404.08  3821.1  406.55  3850.4   401.4    3936   394.5    4035  394.43
    4056  394.38  4142.9  396.83  4181.4  395.09  4277.3  396.03  4328.9  395.37
  4358.2   402.7    4379  398.59  4422.5  399.19  4463.3  387.05    4494  380.52
  4564.8  380.27  4988.3  380.79  5000.3  374.97    5003  374.47  5006.3  374.97
  5018.5  379.76  5284.5  383.14  5499.5  394.25  5890.5  398.48  6077.6  404.18
#Mann= 13 ,-1 , 0
  3129.5     .05       0    3152     .15       0  3235.1     .05       0
    4035      .1       0    4056     .05       0  4181.4      .1       0
  4277.3     .08       0  4463.3     .05       0  4564.8     .16       0
  5000.3     .07       0  5006.3     .16       0  5284.5      .1       0
  5890.5     .16       0
#XS Ineff= 1 ,-1
 3841.19 4360.23  402.25
Permanent Ineff=
       F
Bank Sta=4988.3,5018.5
XS Rating Curve= 0 ,0
Exp/Cntr=0.3,0.1

Type RM Length L Ch R = 1 ,31045   ,842,842,842
BEGIN DESCRIPTION:
LAMBS CREEK 46.2
END DESCRIPTION:
XS GIS Cut Line= 4
      3570960.18     10494230.55      3570564.24     10495795.18
      3570685.76     10496229.21      3570585.94     10497383.72
#Sta/Elev= 30
  3258.1   463.3  3477.7  448.29  3589.3  437.32  3648.7  428.82  3718.6  422.11
  3860.2  417.67  3918.5   414.5  3923.7  416.42  4005.7  420.38  4046.7  419.08
  4087.7  414.22  4177.3  393.83  4514.5  393.26  4604.3  393.16  4620.9  397.33
  4703.4   395.1  4744.6  383.62  4769.4   381.4  4796.2  383.91  4861.8  378.91
  4982.6  380.11  5000.4  373.99  5003.1  373.49  5006.4  373.99  5024.2  380.26
  5190.3  378.61  5375.4  390.22  5675.7  393.94  6057.9  392.82  6481.6  405.81
#Mann= 9 ,-1 , 0
  3258.1     .05       0  3648.7      .1       0  3860.2     .05       0
  4514.5      .1       0  4604.3     .08       0  4769.4     .16       0
  5000.4     .07       0  5006.4     .16       0  5675.7      .1       0
#XS Ineff= 1 ,-1
 4157.39 4624.72     398
Permanent Ineff=
       F
Bank Sta=4982.6,5024.2
XS Rating Curve= 0 ,0
Exp/Cntr=0.3,0.1

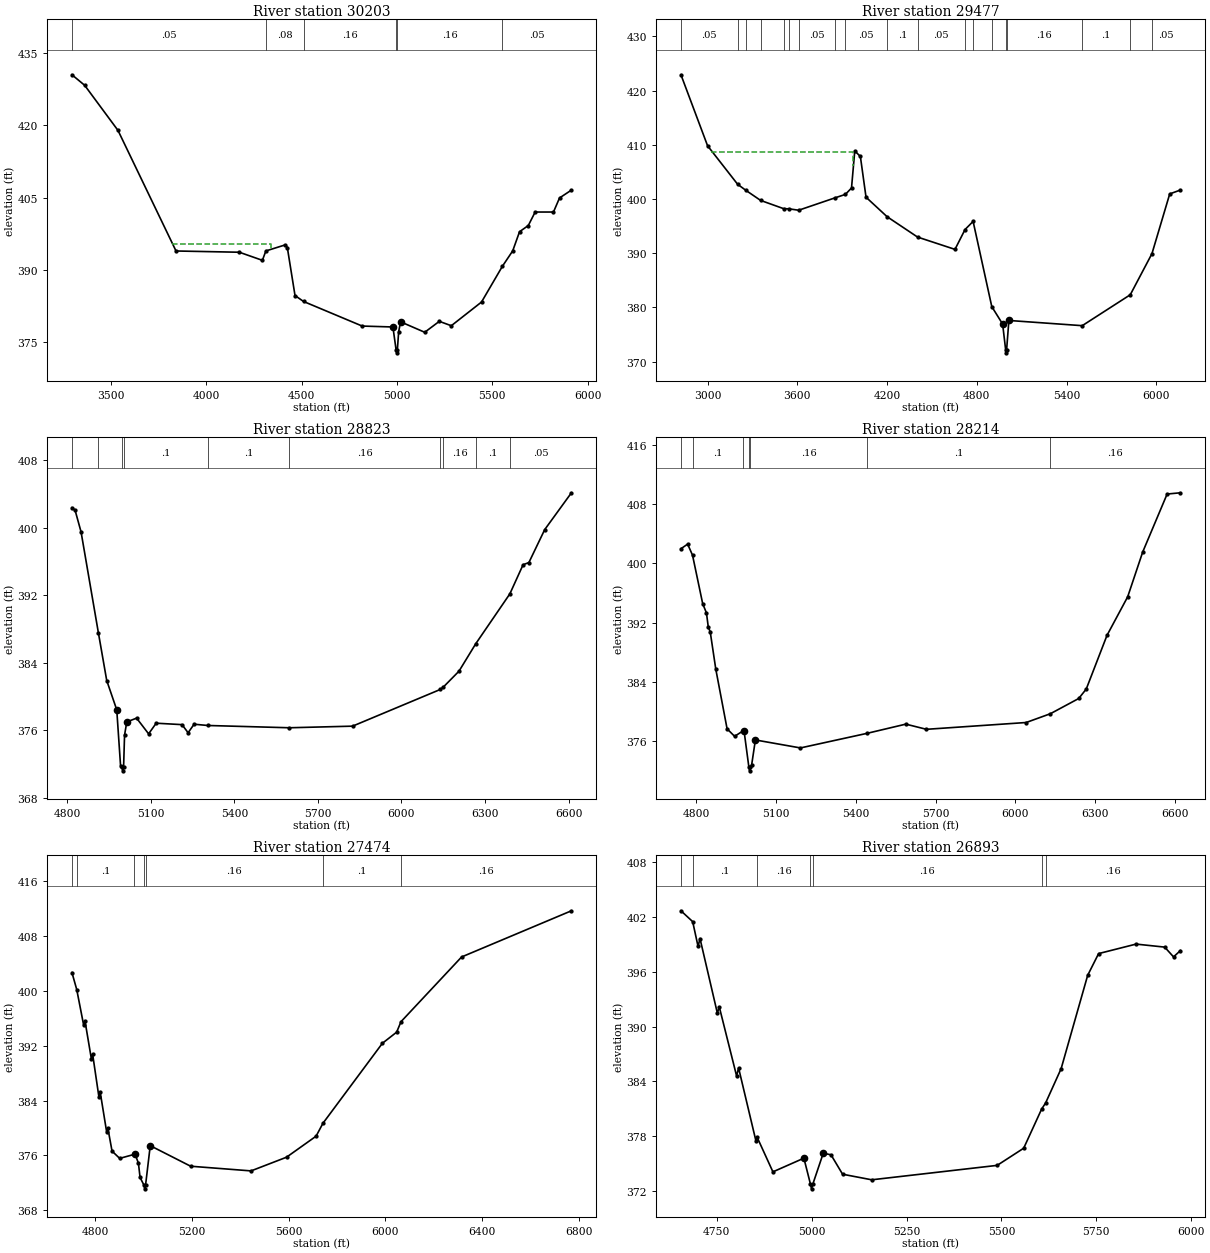
Type RM Length L Ch R = 1 ,30203   ,726,726,726
BEGIN DESCRIPTION:
LAMBS CREEK 48.0
END DESCRIPTION:
XS GIS Cut Line= 3
      3570034.45     10494409.63      3569826.12     10496256.82
      3570013.62     10496992.91
#Sta/Elev= 30
  3296.3  430.51  3362.8  428.33  3537.6  418.96  3841.8  393.92  4173.8  393.66
  4294.6  391.98  4312.9  393.93  4415.4   395.2  4425.4  394.63  4465.7  384.67
  4510.2  383.44  4817.9  378.33  4978.9  378.14    4996  373.27  4998.8  372.77
    5002  373.27  5009.1  377.19  5019.2  379.21  5145.7  377.04  5222.1  379.31
    5285   378.4  5443.4  383.32  5552.9  390.75    5607  393.95  5642.7  397.92
  5688.7  399.21  5724.5  402.01  5820.6  402.01  5852.3  404.93  5914.8  406.57
#Mann= 6 ,-1 , 0
  3296.3     .05       0  4312.9     .08       0  4510.2     .16       0
    4996     .07       0    5002     .16       0  5552.9     .05       0
#XS Ineff= 1 ,-1
 3818.18 4339.77  395.32
Permanent Ineff=
       F
Bank Sta=4978.9,5019.2
XS Rating Curve= 0 ,0
Exp/Cntr=0.3,0.1

Type RM Length L Ch R = 1 ,29477   ,654,654,654
BEGIN DESCRIPTION:
LAMBS CREEK 47.0
END DESCRIPTION:
XS GIS Cut Line= 4
      3568390.75     10493890.27      3569405.38     10495699.69
      3569318.58     10495981.81      3569756.92     10496845.49
#Sta/Elev= 30
  2822.5  422.91  3000.4  409.82  3201.2  402.72  3256.2   401.6  3354.9  399.74
  3509.8  398.21  3543.8  398.19  3609.2  397.93  3854.9  400.24  3921.5  400.85
  3962.4  402.03  3984.1  408.87  4021.7  407.84  4059.4  400.33    4200  396.74
  4403.8  392.98  4653.9  390.71  4721.1  394.37  4775.1  395.87  4899.9  380.15
  4972.3  376.94  4992.8  372.13  4995.5  371.63  4998.8  372.13  5014.1   377.6
  5504.4  376.64  5825.4  382.34  5970.3  389.92  6089.1  400.94  6160.7  401.66
#Mann= 19 ,-1 , 0
  2822.5     .05       0  3201.2      .1       0  3256.2     .05       0
  3354.9      .1       0  3509.8     .05       0  3543.8      .1       0
  3609.2     .05       0  3854.9      .1       0  3921.5     .05       0
    4200      .1       0  4403.8     .05       0  4721.1      .1       0
  4775.1     .05       0  4899.9     .16       0  4992.8     .07       0
  4998.8     .16       0  5504.4      .1       0  5825.4     .16       0
  5970.3     .05       0
#XS Ineff= 1 ,-1
 3022.73    3975  408.75
Permanent Ineff=
       F
Bank Sta=4972.3,5014.1
XS Rating Curve= 0 ,0
Exp/Cntr=0.3,0.1

Type RM Length L Ch R = 1 ,28823   ,609,609,609
BEGIN DESCRIPTION:
LAMBS CREEK 46.0
END DESCRIPTION:
XS GIS Cut Line= 3
      3568641.51     10495526.11      3569236.11     10496268.27
      3569713.54     10496962.71
#Sta/Elev= 30
  4816.7  402.37  4827.9  402.08  4849.4  399.51  4911.8  387.53  4941.6  381.91
  4977.6  378.44  4991.2  371.85  4996.2  371.72  4998.9  371.22  5002.2  371.72
  5005.6  375.45  5013.6  377.01  5048.8  377.46    5092   375.6  5119.2  376.86
    5212  376.69  5233.8  375.73  5255.3  376.74  5304.1  376.59  5597.3  376.32
  5824.4  376.51  6139.8  380.86  6150.7  381.15  6206.6  383.02  6266.8  386.27
  6389.2  392.17  6436.7  395.62  6457.6  395.88  6514.4  399.78  6610.4  404.14
#Mann= 10 ,-1 , 0
  4816.7     .05       0  4911.8      .1       0  4996.2     .07       0
  5002.2      .1       0  5304.1      .1       0  5597.3     .16       0
  6139.8      .1       0  6150.7     .16       0  6266.8      .1       0
  6389.2     .05       0
Bank Sta=4977.6,5013.6
XS Rating Curve= 0 ,0
Exp/Cntr=0.3,0.1

Type RM Length L Ch R = 1 ,28214   ,740,740,740
BEGIN DESCRIPTION:
LAMBS CREEK 46.1
END DESCRIPTION:
XS GIS Cut Line= 2
      3568267.57     10495910.57      3569630.42     10497203.97
#Sta/Elev= 30
  4741.7     402  4766.8  402.62  4785.2  401.13  4823.5  394.56  4837.6  393.31
  4844.5   391.4  4851.8  390.75  4872.8  385.69  4915.3  377.62  4943.6  376.61
  4976.3  377.37  4979.2  377.31  4997.2  372.44    5000  371.94  5003.2  372.44
  5007.5  372.71  5021.7  376.12  5191.2  375.04  5442.4  377.02  5587.6  378.26
  5665.2  377.56  6040.2  378.48  6131.4  379.67    6238  381.73  6266.3  383.01
  6344.4  390.28  6422.1  395.49  6478.7  401.56  6570.5   409.4  6620.6  409.57
#Mann= 7 ,-1 , 0
  4741.7     .05       0  4785.2      .1       0  4976.3     .16       0
  4997.2     .07       0  5003.2     .16       0  5442.4      .1       0
  6131.4     .16       0
Bank Sta=4979.2,5021.7
XS Rating Curve= 0 ,0
Exp/Cntr=0.3,0.1

Type RM Length L Ch R = 1 ,27474   ,581,581,581
BEGIN DESCRIPTION:
LAMBS CREEK 45.0
END DESCRIPTION:
XS GIS Cut Line= 4
      3567903.66     10496064.25      3567717.01     10496624.17
      3567960.07     10497526.95      3568091.44     10498052.65
#Sta/Elev= 30
  4703.3  402.61  4723.1  400.14  4751.8  394.95  4757.1   395.6  4783.4  390.11
  4788.7  390.78  4815.1  384.46  4820.3   385.2  4846.7  379.47  4851.9  379.98
  4869.2  376.64  4900.8  375.58  4960.8  376.16  4964.1  376.24  4978.4  374.87
  4985.2   372.8  5001.8  371.65  5004.5  371.15  5007.8  371.65  5027.3  377.43
  5194.5  374.44  5444.4  373.76  5591.2  375.75  5713.6  378.81    5742  380.69
  5988.1  392.33  6046.9  393.94  6065.1  395.47  6315.7  404.88  6770.3   411.6
#Mann= 7 ,-1 , 0
  4703.3     .05       0  4723.1      .1       0  4960.8     .16       0
  5001.8     .07       0  5007.8     .16       0    5742      .1       0
  6065.1     .16       0
Bank Sta=4964.1,5027.3
XS Rating Curve= 0 ,0
Exp/Cntr=0.3,0.1

Type RM Length L Ch R = 1 ,26893   ,490,490,490
BEGIN DESCRIPTION:
LAMBS CREEK 45.1
END DESCRIPTION:
XS GIS Cut Line= 3
      3567217.88     10496164.11      3567356.77     10496854.21
      3567604.15     10497414.06
#Sta/Elev= 30
  4655.5   402.7  4686.4  401.51  4700.6  398.79  4705.7  399.66  4751.4  391.49
  4756.5  392.17  4802.2  384.59  4807.3  385.49  4853.1  377.48    4856  377.91
  4897.8   374.1  4979.4   375.6  4996.8  372.74  4999.5  372.24  5002.8  372.74
  5030.4  376.14  5050.8  375.97  5081.4  373.84  5158.1  373.23  5488.6  374.81
  5558.5  376.69  5605.7  380.97  5616.3  381.65  5657.2  385.41  5727.1  395.63
  5755.9  398.01  5854.6  399.05    5930  398.72  5953.3  397.65  5971.5  398.34
#Mann= 7 ,-1 , 0
  4655.5     .05       0  4686.4      .1       0    4856     .16       0
  4996.8     .07       0  5002.8     .16       0  5605.7      .1       0
  5616.3     .16       0
Bank Sta=4979.4,5030.4
XS Rating Curve= 0 ,0
Exp/Cntr=0.3,0.1

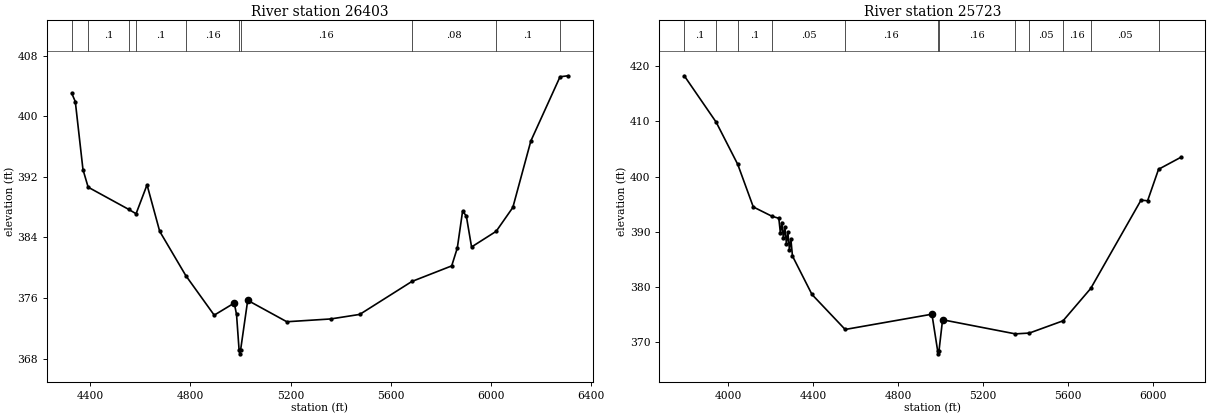
Type RM Length L Ch R = 1 ,26403   ,680,680,680
BEGIN DESCRIPTION:
LAMBS CREEK 44.0
END DESCRIPTION:
XS GIS Cut Line= 3
       3567142.1     10495691.65      3566731.77     10496524.35
      3566141.52     10497396.71
#Sta/Elev= 30
  4326.1  403.03  4340.1  401.95  4370.7  392.97  4391.4  390.64  4553.1  387.71
  4582.7  387.13  4626.5  390.95    4677  384.81  4781.2  378.96  4894.7  373.73
  4974.6  375.33  4983.8  373.83    4994  369.12  4996.8  368.62    5000  369.12
  5028.4  375.69  5184.5  372.86  5359.8  373.23  5475.7  373.83  5683.7  378.18
  5842.8  380.24  5865.2   382.6  5886.2  387.45  5901.1  386.86  5922.1  382.74
  6020.4  384.81  6086.9  387.96  6158.9  396.75  6275.4  405.23  6307.7  405.36
#Mann= 10 ,-1 , 0
  4326.1     .05       0  4391.4      .1       0  4553.1     .05       0
  4582.7      .1       0  4781.2     .16       0    4994     .07       0
    5000     .16       0  5683.7     .08       0  6020.4      .1       0
  6275.4     .16       0
Bank Sta=4974.6,5028.4
XS Rating Curve= 0 ,0
Exp/Cntr=0.3,0.1

Type RM Length L Ch R = 1 ,25723   ,1036,1036,1036
BEGIN DESCRIPTION:
LAMBS CREEK 43.0
END DESCRIPTION:
XS GIS Cut Line= 4
      3567148.42     10495048.67       3566344.2     10495789.55
      3566310.76     10496298.65      3565928.84     10496923.63
#Sta/Elev= 30
  3793.2  418.28  3943.3  409.87    4045  402.21  4118.1  394.49    4205  392.82
  4238.3  392.43  4245.7  389.75  4252.5  391.67  4259.9  388.84  4266.7  390.89
  4274.1  387.83  4280.9  389.87  4288.2  386.77    4295  388.66  4302.4   385.6
  4394.3  378.62  4550.5  372.27  4958.9  375.04    4986  368.35  4988.7  367.85
    4992  368.35    5009  374.03  5351.5  371.47  5417.5  371.62    5576  373.84
  5706.3  379.71  5943.1  395.73    5974  395.61  6025.5  401.32  6129.3  403.47
#Mann= 12 ,-1 , 0
  3793.2      .1       0  3943.3     .05       0    4045      .1       0
    4205     .05       0  4550.5     .16       0    4986     .07       0
    4992     .16       0  5351.5     .12       0  5417.5     .05       0
    5576     .16       0  5706.3     .05       0  6025.5      .1       0
Bank Sta=4958.9,5009
XS Rating Curve= 0 ,0
Exp/Cntr=0.3,0.1