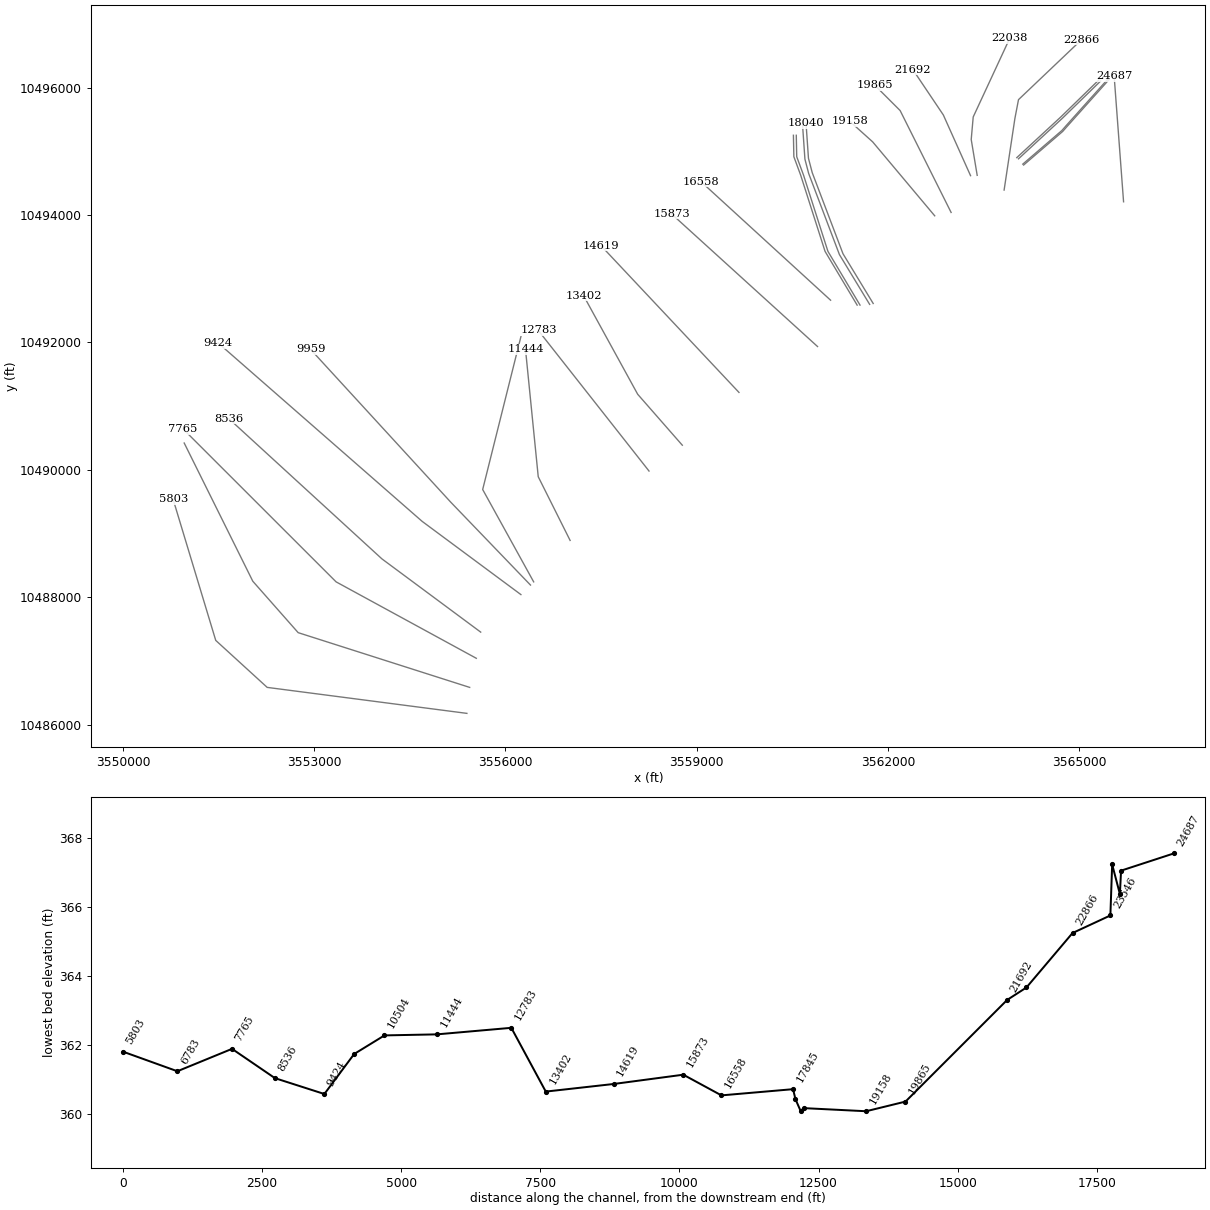
HEC-RAS study LAMBS CREEK.prj: LAMBS CREEK Base Level Engineering

--- LAMBS CREEK.g01 (geometry) --- (continued)

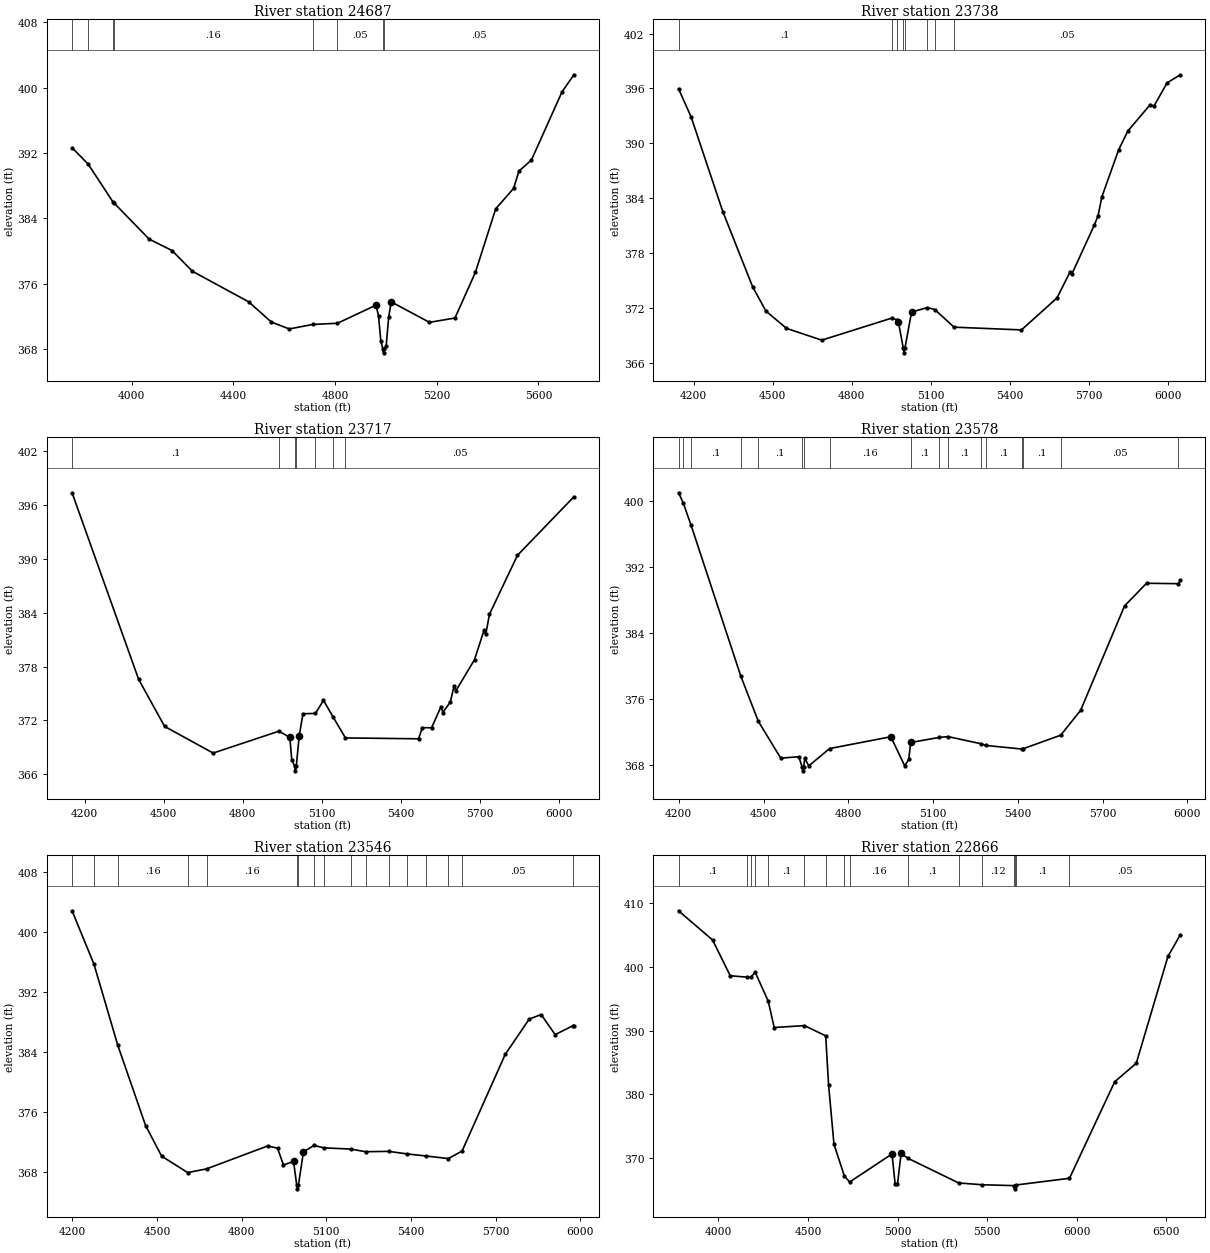
Type RM Length L Ch R = 1 ,24687   ,949,949,949
BEGIN DESCRIPTION:
LAMBS CREEK 42.0
END DESCRIPTION:
XS GIS Cut Line= 2
      3565698.14      10494209.2      3565550.68     10496178.19
#Sta/Elev= 30
  3765.1  392.64  3828.3  390.65  3926.4     386  3929.1  385.92  4068.4  381.47
  4158.6  380.07  4238.9  377.53  4459.5  373.81  4549.7  371.32  4619.9  370.48
  4711.3  371.03  4809.4  371.18  4960.9  373.39  4970.9   372.1    4980     369
    4988  368.06  4990.7  367.56    4994  368.06    5001  368.36    5011  371.95
    5021  373.79  5171.5  371.29  5271.7  371.82    5352  377.39  5432.2  385.18
  5502.4  387.67  5523.6  389.79  5572.6  391.14  5692.9  399.47  5739.6  401.57
#Mann= 8 ,-1 , 0
  3765.1     .05       0  3828.3     .16       0  3926.4     .05       0
  3929.1     .16       0  4711.3      .1       0  4809.4     .05       0
    4988    .035       0    4994     .05       0
Bank Sta=4960.9,5021
XS Rating Curve= 0 ,0
Exp/Cntr=0.3,0.1

Type RM Length L Ch R = 1 ,23738   ,21,21,21
BEGIN DESCRIPTION:
LAMBS CREEK 40.01
END DESCRIPTION:
XS GIS Cut Line= 4
      3564130.17     10494786.33      3564742.99     10495313.65
      3564818.51     10495399.58      3565473.44     10496131.33
#Sta/Elev= 30
  4142.3  395.97  4189.9   392.9  4310.6   382.5  4423.6  374.29  4474.1  371.63
    4552  369.74  4685.9  368.45  4951.5  370.86  4972.1  370.66  4976.8  370.46
  4995.6  367.56  4998.3  367.06  5001.6  367.56    5027  371.53  5086.9  372.01
    5115   371.8  5188.2  369.87  5444.2  369.57  5578.7  373.06  5628.9  375.92
  5635.6   375.7  5720.8  381.05    5735  382.07  5749.2  384.12  5812.8  389.27
  5847.9  391.34  5933.1  394.24  5947.4  394.08  5996.7  396.61  6047.2   397.5
#Mann= 8 ,-1 , 0
  4142.3      .1       0  4951.5     .05       0  4972.1      .1       0
  4995.6     .07       0  5001.6      .1       0  5086.9     .05       0
    5115      .1       0  5188.2     .05       0
Bank Sta=4976.8,5027
XS Rating Curve= 0 ,0
Exp/Cntr=0.3,0.1

Type RM Length L Ch R = 1 ,23717   ,139,139,139
BEGIN DESCRIPTION:
LAMBS CREEK 40.0
END DESCRIPTION:
XS GIS Cut Line= 4
      3564117.15     10494800.65      3564729.97     10495327.97
      3564805.49     10495413.91      3565460.42     10496145.66
#Sta/Elev= 30
  4152.6  397.37  4405.1  376.59  4503.9  371.33  4688.2  368.36    4938   370.8
  4979.3  370.11  4986.5  367.64  4997.7  366.88  5000.5  366.38  5003.7  366.88
  5014.9  370.28  5029.2  372.74  5076.6  372.78  5106.9  374.24  5143.1   372.4
  5190.4  370.05    5468  369.95  5482.2  371.19  5517.4  371.18  5553.3  373.54
    5560  372.88  5588.4  374.04  5602.6  375.84  5609.3  375.29  5680.4  378.77
  5716.3  382.03    5723  381.58  5737.2  383.84  5843.4   390.4  6057.5  396.92
#Mann= 7 ,-1 , 0
  4152.6      .1       0    4938     .05       0  4997.7     .03       0
  5003.7     .05       0  5076.6     .05       0  5143.1      .1       0
  5190.4     .05       0
Bank Sta=4979.3,5014.9
XS Rating Curve= 0 ,0
Exp/Cntr=0.3,0.1

Type RM Length L Ch R = 1 ,23578   ,32,32,32
BEGIN DESCRIPTION:
LAMBS CREEK 40.02
END DESCRIPTION:
XS GIS Cut Line= 3
      3564049.01     10494883.38      3564739.95     10495522.24
      3565338.04     10496104.73
#Sta/Elev= 30
  4199.3  400.95  4216.2   399.7  4243.5  397.03  4419.7  378.72  4481.6  373.25
    4561  368.78  4625.1  368.95  4636.3  367.74    4639  367.24  4642.3  367.74
  4646.1  368.77  4660.2  367.84  4733.8  369.94  4950.6  371.37  4999.9  367.84
  5014.1  368.64  5020.9  370.68  5022.9  370.69  5121.9  371.29  5153.1  371.39
    5269  370.53    5286  370.32  5415.6  369.88  5418.9  369.92  5551.8  371.56
  5622.3  374.57  5777.9  387.24  5855.6  389.98  5968.6  389.93  5975.2  390.36
#Mann= 17 ,-1 , 0
  4199.3      .1       0  4216.2     .05       0  4243.5      .1       0
  4419.7     .16       0  4481.6      .1       0  4636.3     .07       0
  4642.3      .1       0  4733.8     .16       0  5022.9      .1       0
  5121.9     .16       0  5153.1      .1       0    5269     .16       0
    5286      .1       0  5415.6     .05       0  5418.9      .1       0
  5551.8     .05       0  5968.6     .16       0
Bank Sta=4950.6,5020.9
XS Rating Curve= 0 ,0
Exp/Cntr=0.3,0.1

Type RM Length L Ch R = 1 ,23546   ,680,680,680
BEGIN DESCRIPTION:
LAMBS CREEK 40.03
END DESCRIPTION:
XS GIS Cut Line= 3
      3564022.97     10494902.48      3564713.91     10495541.34
      3565312.86     10496124.66
#Sta/Elev= 30
  4199.6  402.85    4277  395.74  4361.7  384.89  4460.1  374.19  4516.8  370.12
  4609.1  367.93  4675.8  368.42  4892.1  371.48  4927.3  371.18  4948.3  368.94
    4984  369.42  4995.2  366.26  4997.9  365.76  5001.2  366.26  5019.1   370.7
  5056.5  371.55  5091.3  371.23  5187.4  371.06  5239.3  370.71  5320.3  370.76
  5385.8  370.42  5453.2  370.14  5532.4   369.8  5580.8   370.8  5733.6  383.69
  5818.5   388.4  5860.9  389.01  5910.4  386.33  5974.1  387.53  5976.7  387.53
#Mann= 17 ,-1 , 0
  4199.6     .05       0    4277      .1       0  4361.7     .16       0
  4609.1      .1       0  4675.8     .16       0  4995.2     .07       0
  5001.2     .16       0  5056.5      .1       0  5091.3     .16       0
  5187.4      .1       0  5239.3     .16       0  5320.3      .1       0
  5385.8     .05       0  5453.2      .1       0  5532.4     .16       0
  5580.8     .05       0  5974.1     .16       0
Bank Sta=4984,5019.1
XS Rating Curve= 0 ,0
Exp/Cntr=0.3,0.1

Type RM Length L Ch R = 1 ,22866   ,828,828,828
BEGIN DESCRIPTION:
LAMBS CREEK 39.0
END DESCRIPTION:
XS GIS Cut Line= 4
      3563823.79     10494393.29      3563993.06      10495517.4
      3564049.48     10495812.54      3565038.11     10496753.48
#Sta/Elev= 30
  3777.2  408.72  3967.7  404.14  4065.9  398.56  4161.4  398.34  4180.9  398.34
  4205.2  399.11  4277.9   394.6  4311.5  390.47  4480.2  390.77    4599  389.17
  4614.9  381.56  4645.2  372.22  4703.7  367.23  4732.9  366.32  4969.2   370.7
  4986.6  366.05  4999.8  365.94  5020.1   370.8  5056.6  370.05  5341.4  366.17
  5472.9  365.89  5651.3  365.75    5654  365.25  5657.3  365.75    5662  365.85
  5960.4   366.9  6212.9  381.99  6333.4  384.89  6510.1  401.58  6579.3  404.97
#Mann= 16 ,-1 , 0
  3777.2      .1       0  4161.4     .05       0  4180.9      .1       0
  4205.2     .05       0  4277.9      .1       0  4480.2     .05       0
    4599     .16       0  4703.7     .05       0  4732.9     .16       0
  5056.6      .1       0  5341.4     .16       0  5472.9     .12       0
  5651.3     .07       0  5657.3     .12       0    5662      .1       0
  5960.4     .05       0
Bank Sta=4969.2,5020.1
XS Rating Curve= 0 ,0
Exp/Cntr=0.3,0.1

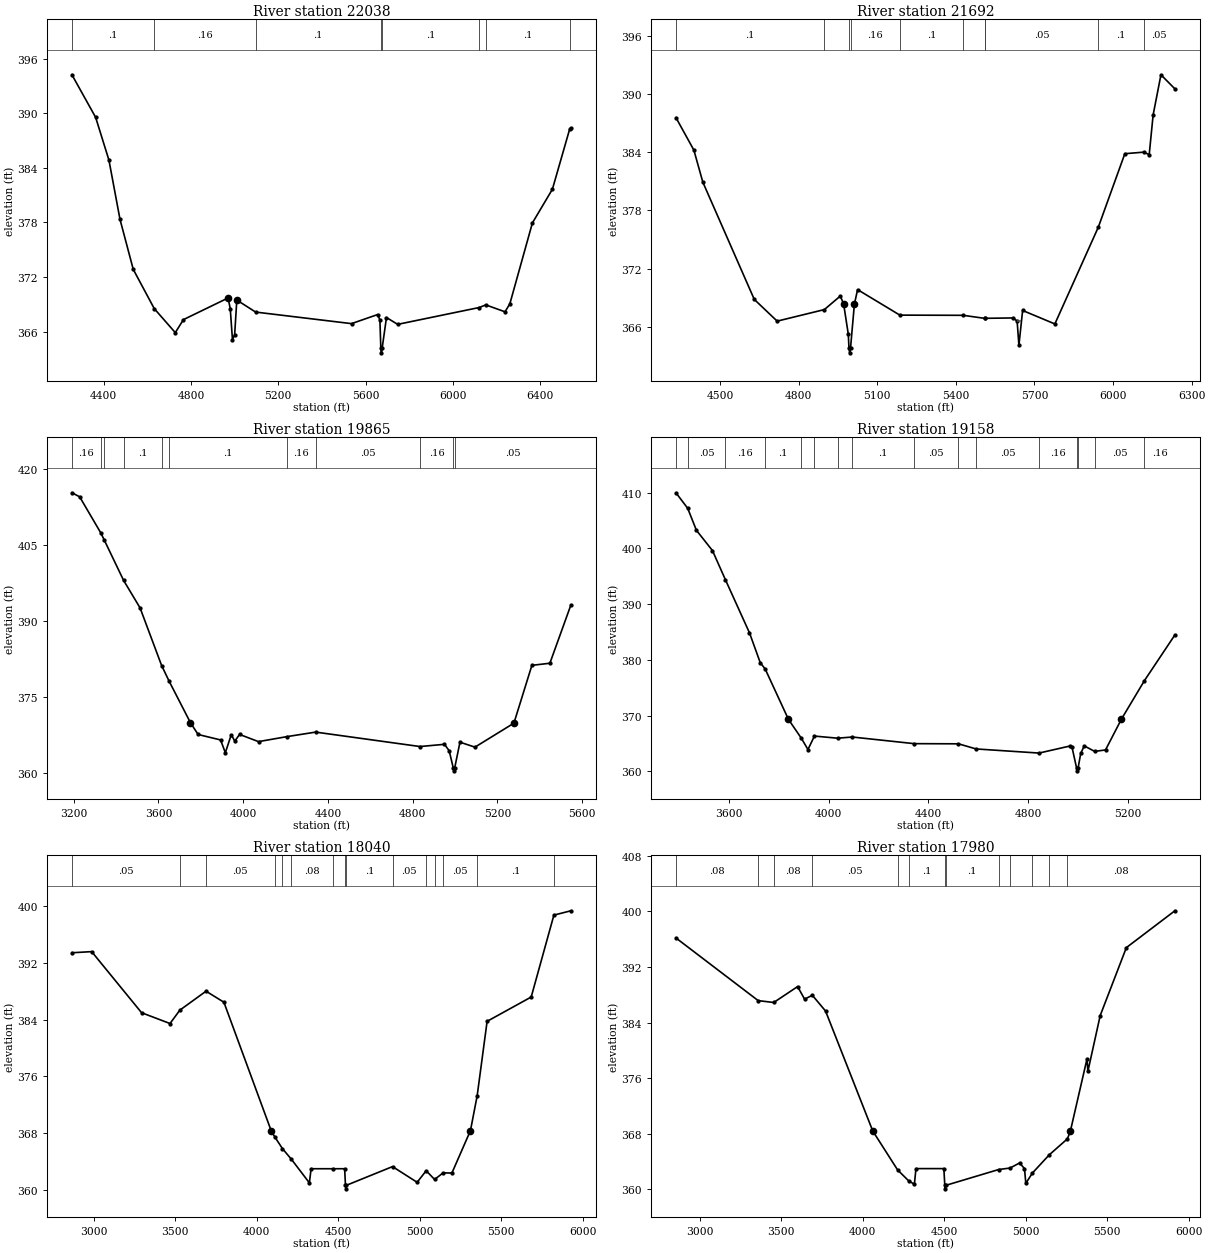
Type RM Length L Ch R = 1 ,22038   ,346,346,346
BEGIN DESCRIPTION:
LAMBS CREEK 38.0
END DESCRIPTION:
XS GIS Cut Line= 4
      3563401.42     10494624.38      3563307.67     10495186.84
      3563338.92     10495541.01      3563911.83     10496775.37
#Sta/Elev= 30
  4254.3  394.23    4363  389.55  4423.9  384.85  4474.6  378.34  4535.4  372.84
  4631.6  368.53    4728  365.89  4765.3  367.32  4969.9   369.7  4979.9  368.53
    4990  365.13    5000  365.64    5010  369.47  5096.2  368.15  5535.6  366.88
  5655.6  367.88  5665.8  367.27    5670  364.17  5672.7  363.67    5676  364.17
  5695.9  367.55  5747.2   366.8  6120.7  368.65    6151  368.94  6239.1  368.18
  6261.2  369.05  6364.7  377.95  6456.3  381.65  6535.1  388.23  6540.9  388.33
#Mann= 8 ,-1 , 0
  4254.3      .1       0  4631.6     .16       0  5096.2      .1       0
    5670     .07       0    5676      .1       0  6120.7     .05       0
    6151      .1       0  6535.1     .05       0
Bank Sta=4969.9,5010
XS Rating Curve= 0 ,0
Exp/Cntr=0.3,0.1

Type RM Length L Ch R = 1 ,21692   ,1827,1827,1827
BEGIN DESCRIPTION:
LAMBS CREEK 37.0
END DESCRIPTION:
XS GIS Cut Line= 3
      3563297.25     10494619.15      3562870.17     10495572.26
      3562391.02     10496285.78
#Sta/Elev= 30
  4332.2  387.57  4400.6  384.22  4434.7  380.92  4631.1  368.82  4718.4  366.58
  4898.4  367.77  4959.5  369.17  4972.2  368.33  4989.9  365.22  4992.4  363.81
  4995.1  363.31  4998.4  363.81  5013.1  368.33  5025.3  369.83  5186.6   367.2
  5428.2  367.18  5509.8  366.87  5510.2  366.87  5619.1  366.91  5634.1  366.58
  5640.9   364.1  5655.1  367.68  5778.1  366.29  5943.9  376.27  6045.1  383.85
  6117.3  384.01  6138.1  383.75  6153.1  387.85  6182.9  391.99  6236.1  390.54
#Mann= 10 ,-1 , 0
  4332.2      .1       0  4898.4     .16       0  4992.4     .07       0
  4998.4     .16       0  5186.6      .1       0  5428.2     .05       0
  5509.8      .1       0  5510.2     .05       0  5943.9      .1       0
  6117.3     .05       0
#XS Ineff= 1 ,-1
 5634.03 5650.71  366.59
Permanent Ineff=
       F
Bank Sta=4972.2,5013.1
XS Rating Curve= 0 ,0
Exp/Cntr=0.3,0.1

Type RM Length L Ch R = 1 ,19865   ,707,707,707
BEGIN DESCRIPTION:
LAMBS CREEK 36.0
END DESCRIPTION:
XS GIS Cut Line= 3
      3562992.13      10494041.6      3562192.11     10495641.64
      3561792.09     10496041.65
#Sta/Elev= 30
  3191.7  415.28  3228.1  414.49    3328  407.35  3343.9  405.98  3435.5  397.98
  3513.2  392.55    3615  381.16  3650.7  378.04  3750.8  369.89  3787.1  367.54
  3893.3  366.46  3915.7  363.93  3943.6  367.48  3960.4  366.23  3982.8  367.55
  4072.2  366.13  4206.9  367.12    4342  368.01  4834.2  365.16  4949.9   365.6
  4972.2  364.32  4991.7  360.86  4994.5  360.36  4997.7  360.86    5023  366.02
  5093.7  365.04  5277.6  369.78  5362.4   381.2  5447.3  381.61  5546.3   393.1
#Mann= 11 ,-1 , 0
  3191.7     .16       0    3328      .1       0  3343.9     .05       0
  3435.5      .1       0    3615     .05       0  3650.7      .1       0
  4206.9     .16       0    4342     .05       0  4834.2     .16       0
  4991.7     .03       0  4997.7     .05       0
Bank Sta=3750.8,5277.6
XS Rating Curve= 0 ,0
Exp/Cntr=0.3,0.1

Type RM Length L Ch R = 1 ,19158   ,1118,1118,1118
BEGIN DESCRIPTION:
LAMBS CREEK 35.0
END DESCRIPTION:
XS GIS Cut Line= 3
      3562734.77     10493988.91       3561760.8     10495150.38
      3561401.45     10495473.28
#Sta/Elev= 30
  3388.7  409.99  3435.8   407.2  3470.6  403.26    3535  399.61  3586.5  394.42
  3683.3  384.85  3726.2  379.52  3746.4  378.34  3839.4  369.32  3890.9  365.94
  3917.5  363.91  3943.6  366.32  4036.1  365.94  4095.3  366.15  4343.2  364.96
  4520.5  364.93  4591.2  364.01  4843.4  363.27  4968.5  364.55  4975.2  364.38
  4993.8  360.58  4996.6  360.08  4999.8  360.58  5010.3   363.2  5024.5  364.56
  5066.2  363.57  5109.7  363.83  5173.3  369.35  5265.7  376.28  5387.6  384.47
#Mann= 16 ,-1 , 0
  3388.7      .1       0  3435.8     .05       0  3586.5     .16       0
  3746.4      .1       0  3890.9     .05       0  3943.6      .1       0
  4036.1     .05       0  4095.3      .1       0  4343.2     .05       0
  4520.5      .1       0  4591.2     .05       0  4843.4     .16       0
  4993.8     .07       0  4999.8     .16       0  5066.2     .05       0
  5265.7     .16       0
Bank Sta=3839.4,5173.3
XS Rating Curve= 0 ,0
Exp/Cntr=0.3,0.1

Type RM Length L Ch R = 1 ,18040   ,60,60,60
BEGIN DESCRIPTION:
LAMBS CREEK 34.03
END DESCRIPTION:
XS GIS Cut Line= 5
      3561769.47      10492612.2      3561295.52     10493393.44
      3560812.88      10494666.7      3560753.85      10494892.4
      3560715.66     10495444.46
#Sta/Elev= 30
  2865.2   393.4  2986.4  393.56  3292.7  384.96  3467.2  383.44  3527.5  385.32
  3688.3  387.99  3797.9  386.44  4088.7  368.31  4108.9  367.53  4157.1  365.83
  4212.3  364.33  4322.5  361.01  4333.1     363  4468.4     363    4539     363
    4544  360.67  4546.8  360.17    4550  360.67  4832.7   363.3  4983.9  361.09
  5039.4  362.72    5091  361.49  5142.8  362.41  5197.4   362.4  5311.1  368.37
  5352.3  373.27  5413.3  383.75  5683.9  387.17  5823.2   398.7  5927.3  399.31
#Mann= 15 ,-1 , 0
  2865.2     .05       0  3527.5     .08       0  3688.3     .05       0
  4108.9     .16       0  4157.1     .05       0  4212.3     .08       0
  4468.4      .1       0    4544    .035       0    4550      .1       0
  4832.7     .05       0  5039.4     .16       0    5091     .08       0
  5142.8     .05       0  5352.3      .1       0  5823.2     .05       0
Bank Sta=4088.7,5311.1
XS Rating Curve= 0 ,0
Exp/Cntr=0.3,0.1

Type RM Length L Ch R = 1 ,17980   ,92,92,92
BEGIN DESCRIPTION:
LAMBS CREEK 34.0
END DESCRIPTION:
XS GIS Cut Line= 5
      3561713.93     10492598.28      3561239.96     10493379.55
      3560757.32     10494652.81       3560698.3     10494878.51
      3560660.24     10495428.64
#Sta/Elev= 30
  2854.8  396.17  3359.2  387.16  3454.5  386.89    3601  389.18  3643.7  387.37
  3691.3  387.93  3772.4  385.66  4061.9  368.41  4214.3  362.81  4281.3  361.26
  4317.2  360.74  4326.9     363    4498     363  4503.8  360.59  4506.5  360.09
  4509.8  360.59  4834.6  362.87  4903.9  363.08  4962.4  363.81  4992.6     363
  5000.7  360.88  5041.4  362.37  5144.4  364.98  5255.8  367.28  5273.8  368.37
  5376.3  378.81  5381.3  376.98  5456.9  385.01  5617.3  394.78    5915  400.08
#Mann= 13 ,-1 , 0
  2854.8     .08       0  3359.2     .05       0  3454.5     .08       0
  3691.3     .05       0  4214.3     .08       0  4281.3      .1       0
  4503.8     .07       0  4509.8      .1       0  4834.6     .05       0
  4903.9      .1       0  5041.4     .08       0  5144.4     .05       0
  5255.8     .08       0
Bank Sta=4061.9,5273.8
XS Rating Curve= 0 ,0
Exp/Cntr=0.3,0.1

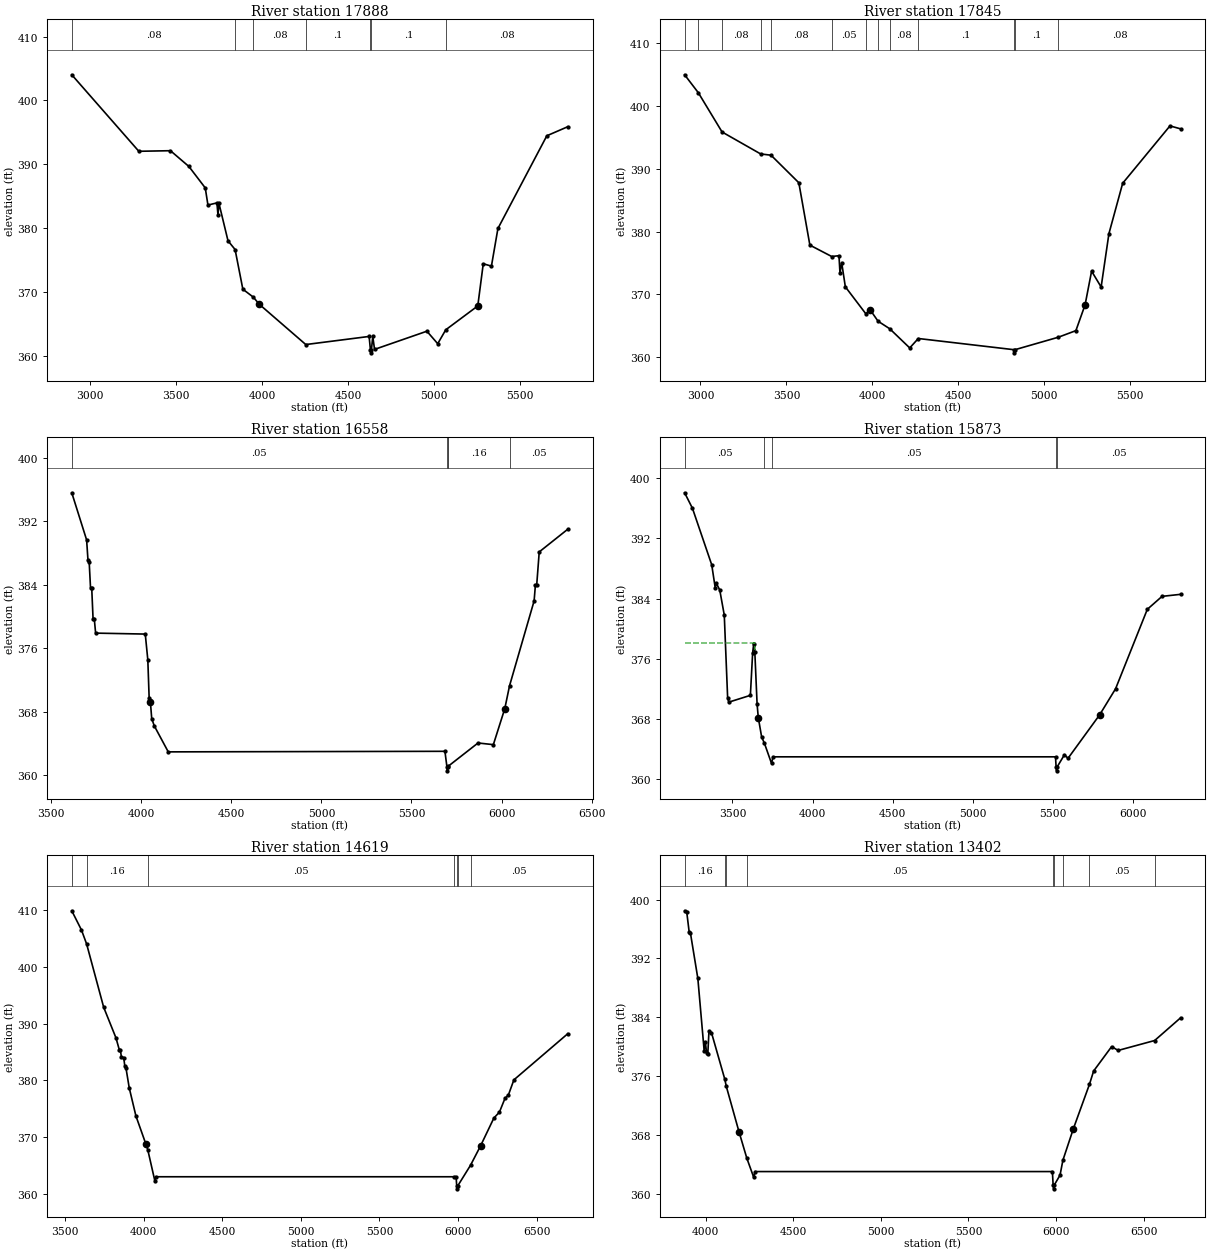
Type RM Length L Ch R = 1 ,17888   ,43,43,43
BEGIN DESCRIPTION:
LAMBS CREEK 34.01
END DESCRIPTION:
XS GIS Cut Line= 5
      3561562.88     10492586.84      3561059.41     10493430.59
      3560677.46     10494625.04      3560569.82      10494916.7
      3560562.88     10495253.46
#Sta/Elev= 30
    2892  404.01  3281.9  392.02  3465.8  392.11    3573  389.64  3668.2  386.28
  3683.8  383.59    3736  383.93  3742.1  382.05    3748  383.84  3800.5  377.99
  3841.7  376.62  3886.8   370.4  3947.6  369.16  3983.3  368.02  4252.8  361.73
  4621.1     363  4628.6  360.93  4631.3  360.43  4634.6  360.93  4642.3     363
  4652.6  360.97    4957  363.82    5020  361.86  5066.7  364.04  5252.9  367.78
  5284.8  374.39  5332.3  374.02  5370.1  379.92  5654.5  394.45  5776.3  395.87
#Mann= 7 ,-1 , 0
    2892     .08       0  3841.7     .05       0  3947.6     .08       0
  4252.8      .1       0  4628.6     .07       0  4634.6      .1       0
  5066.7     .08       0
Bank Sta=3983.3,5252.9
XS Rating Curve= 0 ,0
Exp/Cntr=0.3,0.1

Type RM Length L Ch R = 1 ,17845   ,1287,1287,1287
BEGIN DESCRIPTION:
LAMBS CREEK 34.02
END DESCRIPTION:
XS GIS Cut Line= 5
      3561517.75     10492586.83      3561014.27     10493430.59
      3560632.32     10494625.04      3560524.69      10494916.7
      3560517.74     10495253.55
#Sta/Elev= 30
  2908.1  404.94  2987.7  402.09    3126  395.84  3350.3  392.35  3410.6  392.15
  3572.3  387.77  3636.5  377.85  3763.5  376.04  3805.8  376.17  3811.6  373.39
  3821.4  375.07  3842.8  371.22  3961.9  366.93  3986.3  367.59    4033  365.75
  4100.9  364.55  4217.2   361.5  4267.1     363  4823.2  361.22  4825.9  360.72
  4829.2  361.22    5081   363.2  5183.5  364.25    5237  368.36  5274.8  373.71
  5330.3  371.19  5375.6  379.68  5455.6  387.69  5730.6  396.81  5792.5  396.34
#Mann= 13 ,-1 , 0
  2908.1     .08       0  2987.7     .05       0    3126     .08       0
  3350.3      .1       0  3410.6     .08       0  3763.5     .05       0
  3961.9     .08       0    4033     .05       0  4100.9     .08       0
  4267.1      .1       0  4823.2     .07       0  4829.2      .1       0
    5081     .08       0
Bank Sta=3986.3,5237
XS Rating Curve= 0 ,0
Exp/Cntr=0.3,0.1

Type RM Length L Ch R = 1 ,16558   ,685,685,685
BEGIN DESCRIPTION:
LAMBS CREEK 30.0
END DESCRIPTION:
XS GIS Cut Line= 2
      3561101.07     10492663.93       3559069.8     10494523.32
#Sta/Elev= 30
  3614.1  395.57  3696.5  389.63  3703.9  387.13  3710.7  386.86  3718.1  383.62
  3724.9  383.55  3732.3  379.67    3739   379.7  3746.5  377.89  4022.1  377.77
  4036.3  374.51  4043.7  369.69  4050.5  369.25  4057.9  367.13    4072  366.21
  4149.7  362.93  5685.8     363    5697  361.04  5699.8  360.54    5703  361.04
  5705.3  361.14  5869.6  364.05  5954.7  363.84  6018.2  368.38  6044.6  371.26
    6181  381.95  6188.4     384  6195.2   383.9  6209.4  388.12  6367.9  390.98
#Mann= 5 ,-1 , 0
  3614.1     .05       0    5697    .033       0    5703     .05       0
  5705.3     .16       0  6044.6     .05       0
Bank Sta=4050.5,6018.2
XS Rating Curve= 0 ,0
Exp/Cntr=0.3,0.1

Type RM Length L Ch R = 1 ,15873   ,1254,1254,1254
BEGIN DESCRIPTION:
LAMBS CREEK 28.0
END DESCRIPTION:
XS GIS Cut Line= 2
      3560896.24     10491936.47      3558605.83     10494018.66
#Sta/Elev= 30
  3201.7  398.05  3250.6  395.99  3370.9  388.49  3392.5  385.46  3399.2  386.05
  3420.9  385.15  3449.2  381.82  3470.2  370.83  3477.6  370.26  3612.1  371.16
  3626.2   376.8    3633  378.01  3639.8  376.94    3654  370.01  3661.4  368.22
  3682.4  365.63  3699.9  364.79  3744.1  362.12  3753.3     363  5516.3     363
  5520.1  361.64  5522.8  361.14  5526.1  361.64  5572.4  363.29    5594  362.79
    5792  368.58  5891.3  372.04  6089.3  382.58  6181.2   384.3  6297.1  384.57
#Mann= 5 ,-1 , 0
  3201.7     .05       0  3699.9     .08       0  3744.1     .05       0
  5520.1    .033       0  5526.1     .05       0
#XS Ineff= 2 , 0
         3638.51  378.07
Permanent Ineff=
       F       F
Bank Sta=3661.4,5792
XS Rating Curve= 0 ,0
Exp/Cntr=0.3,0.1

Type RM Length L Ch R = 1 ,14619   ,1217,1217,1217
BEGIN DESCRIPTION:
LAMBS CREEK 26.0
END DESCRIPTION:
XS GIS Cut Line= 2
      3559663.57     10491216.02      3557502.11     10493516.36
#Sta/Elev= 30
  3542.1  409.91  3603.9  406.51  3636.5  404.06  3745.1  392.89  3823.2   387.5
  3844.2  385.43  3851.5  385.28  3858.4  384.05  3872.5  384.03  3879.4  382.56
  3886.7  382.23  3907.7  378.68  3950.2  373.73  4014.2  368.72    4026  367.73
  4070.8  362.27  4077.7     363  5973.6     363  5987.9     363  5991.8  361.37
  5994.5  360.87  5997.8  361.37  6079.7  365.03  6143.2  368.43  6228.2  373.35
  6263.8  374.41    6299  376.83  6320.5  377.41  6355.7  380.09  6698.6  388.23
#Mann= 7 ,-1 , 0
  3542.1     .05       0  3636.5     .16       0    4026     .05       0
  5973.6      .1       0  5991.8    .033       0  5997.8      .1       0
  6079.7     .05       0
Bank Sta=4014.2,6143.2
XS Rating Curve= 0 ,0
Exp/Cntr=0.3,0.1

Type RM Length L Ch R = 1 ,13402   ,619,619,619
BEGIN DESCRIPTION:
LAMBS CREEK 24.0
END DESCRIPTION:
XS GIS Cut Line= 3
      3558774.41     10490387.12       3558074.4     10491187.13
      3557224.54     10492736.87
#Sta/Elev= 30
  3880.4  398.48  3892.3  398.35  3906.5  395.57  3913.2  395.51  3955.9  389.27
  3991.9  379.45  3998.6  380.65    4006  379.11  4012.8  379.04  4019.5  382.15
  4033.7   381.9  4109.5  375.58  4118.4  374.58  4190.3  368.45  4235.5  364.81
  4274.8  362.21  4282.4     363  5979.2     363  5983.4  361.15  5986.2  360.65
  5989.4  361.15  6022.8  362.51  6039.1  364.54  6098.6  368.81  6190.4  374.85
  6214.5  376.68  6317.2     380  6354.5  379.48  6562.8  380.83  6710.9  383.92
#Mann= 9 ,-1 , 0
  3880.4     .16       0  4109.5      .1       0  4118.4     .16       0
  4235.5     .05       0  5983.4    .033       0  5989.4     .05       0
  6039.1     .16       0  6190.4     .05       0  6562.8     .08       0
Bank Sta=4190.3,6098.6
XS Rating Curve= 0 ,0
Exp/Cntr=0.3,0.1

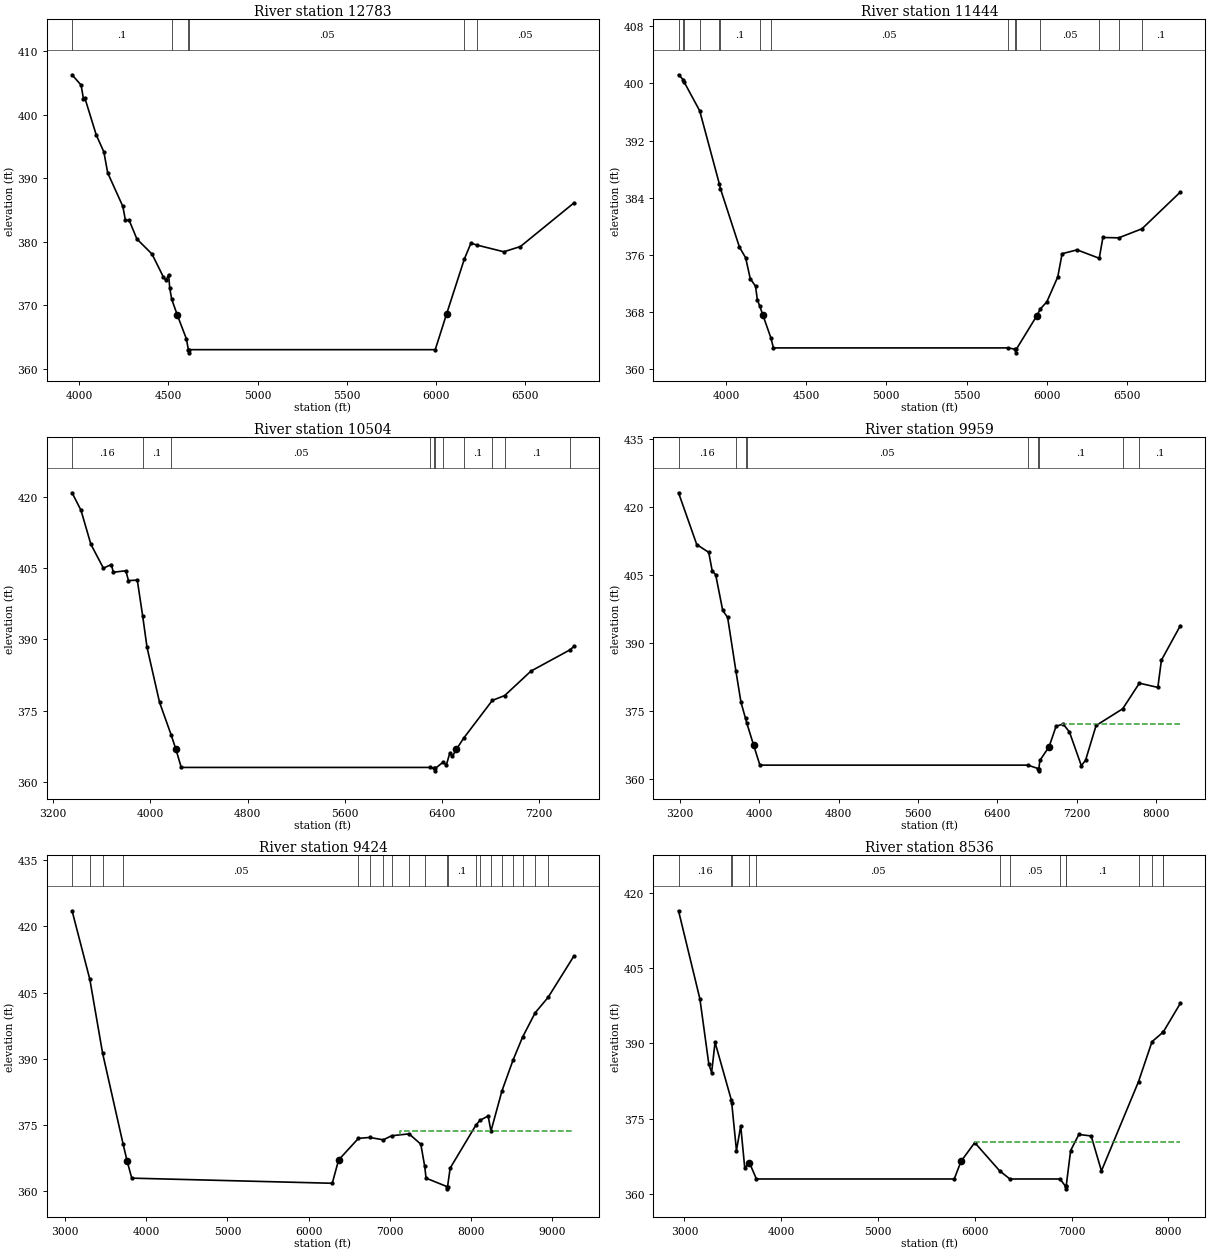
Type RM Length L Ch R = 1 ,12783   ,1339,1339,1339
BEGIN DESCRIPTION:
LAMBS CREEK 22.0
END DESCRIPTION:
XS GIS Cut Line= 3
      3558252.12     10489981.63      3556520.35     10492182.15
      3556520.35     10492195.22
#Sta/Elev= 30
  3960.3  406.33  4010.9   404.7  4023.9  402.57  4031.7   402.7  4095.8  396.85
  4138.5  394.18    4160  390.87    4245  385.58  4259.4   383.4  4280.2  383.41
  4323.6  380.45  4408.5  378.07  4472.7  374.43  4487.1  373.93  4501.6  374.83
  4507.9   372.7  4519.2  370.92  4551.3  368.39    4601  364.72  4612.4     363
  4615.2   362.5  4618.4     363  5996.4     363  6060.3  368.65  6159.8   377.3
  6196.7  379.79  6229.9  379.49  6381.1  378.43  6474.1  379.26  6773.6  386.12
#Mann= 6 ,-1 , 0
  3960.3      .1       0  4519.2     .05       0  4612.4    .033       0
  4618.4     .05       0  6159.8      .1       0  6229.9     .05       0
Bank Sta=4551.3,6060.3
XS Rating Curve= 0 ,0
Exp/Cntr=0.3,0.1

Type RM Length L Ch R = 1 ,11444   ,940,940,940
BEGIN DESCRIPTION:
LAMBS CREEK 21.0
END DESCRIPTION:
XS GIS Cut Line= 3
      3557013.98       10488892.      3556513.98     10489891.99
      3556313.98     10491891.99
#Sta/Elev= 30
  3704.9  401.19  3733.8  400.51  3739.7  400.18  3836.7  396.16    3959  385.96
  3966.1  385.26  4084.6  377.09  4123.3   375.6  4151.7   372.7  4184.8  371.63
  4196.4  369.71  4211.4  368.84  4229.5  367.66  4280.2  364.43  4296.6     363
  5758.2     363  5804.5  362.81  5807.2  362.31  5810.5  362.81  5938.1  367.49
  5960.3  368.45  6000.5  369.43  6068.8  372.92  6095.9  376.17  6189.4  376.71
  6327.5  375.53  6350.2  378.44  6448.7  378.39  6594.1  379.66  6832.9  384.79
#Mann= 15 ,-1 , 0
  3704.9     .05       0  3733.8      .1       0  3739.7     .16       0
  3836.7      .1       0    3959     .16       0  3966.1      .1       0
  4211.4     .16       0  4280.2     .05       0  5758.2      .1       0
  5804.5    .033       0  5810.5      .1       0  5960.3     .05       0
  6327.5      .1       0  6448.7     .05       0  6594.1      .1       0
Bank Sta=4229.5,5938.1
XS Rating Curve= 0 ,0
Exp/Cntr=0.3,0.1

Type RM Length L Ch R = 1 ,10504   ,545,545,545
BEGIN DESCRIPTION:
LAMBS CREEK 19.0
END DESCRIPTION:
XS GIS Cut Line= 3
      3556442.11     10488241.63      3555642.11     10489691.64
       3556242.1     10492091.62
#Sta/Elev= 30
    3355  420.96  3428.4  417.27  3509.7   410.1  3612.9  405.05  3678.2  405.82
  3694.3  404.19  3797.4   404.5  3819.2  402.43  3891.8  402.53  3936.4  394.91
  3971.7  388.37  4074.7  376.76  4169.7  369.92    4210  366.79  4253.5     363
    6303     363  6337.8  362.78  6340.5  362.28  6343.8  362.78  6405.2  364.04
  6436.1  363.56  6464.5  366.09  6485.1  365.33  6518.6  366.83  6576.7  369.13
  6813.8  377.14  6915.9  378.17  7131.9  383.33  7451.4  387.79  7484.9  388.52
#Mann= 11 ,-1 , 0
    3355     .16       0  3936.4      .1       0  4169.7     .05       0
    6303      .1       0  6337.8    .033       0  6343.8      .1       0
  6405.2     .05       0  6576.7      .1       0  6813.8     .05       0
  6915.9      .1       0  7451.4     .08       0
Bank Sta=4210,6518.6
XS Rating Curve= 0 ,0
Exp/Cntr=0.3,0.1

Type RM Length L Ch R = 1 ,9959    ,535,535,535
BEGIN DESCRIPTION:
LAMBS CREEK 18.0
END DESCRIPTION:
XS GIS Cut Line= 3
      3556392.09     10488191.66      3555142.11     10489491.64
      3552942.11     10491891.63
#Sta/Elev= 30
    3187  423.19  3370.8  411.74  3491.2  410.03  3526.4  405.94  3561.7  405.06
  3632.4   397.2  3682.1  395.63  3766.1  383.71  3816.4  376.91  3862.3  373.33
  3873.6  372.41  3943.7  367.44  4007.3     363  6708.5     363  6813.6  362.24
  6816.3  361.74  6819.6  362.24  6830.8  364.06  6922.6  367.05  6993.5  371.59
  7064.5  372.08    7128  370.34  7248.2  362.88  7290.8  364.08  7396.8  371.76
  7665.1  375.45  7833.4  381.11  8019.6  380.18  8055.4  386.19  8246.2  393.82
#Mann= 9 ,-1 , 0
    3187     .16       0  3766.1      .1       0  3862.3     .16       0
  3873.6     .05       0  6708.5      .1       0  6813.6    .033       0
  6819.6      .1       0  7665.1     .08       0  7833.4      .1       0
#XS Ineff= 2 , 0
                         7048.28          372.15
Permanent Ineff=
       F       F
Bank Sta=3943.7,6922.6
XS Rating Curve= 0 ,0
Exp/Cntr=0.3,0.1

Type RM Length L Ch R = 1 ,9424    ,888,888,888
BEGIN DESCRIPTION:
LAMBS CREEK 17.0
END DESCRIPTION:
XS GIS Cut Line= 3
      3556242.08     10488041.66      3554692.11     10489191.64
      3551492.07     10491991.67
#Sta/Elev= 30
  3086.3   423.5  3305.2  407.97  3462.1   391.3  3715.7  370.66  3765.4   366.8
  3821.7     363  6291.9  361.84  6370.2  367.12  6614.2     372  6752.3  372.21
  6921.5  371.67  7022.4  372.59  7238.5  373.02  7382.9  370.68  7430.6   365.7
  7447.5     363  7706.4  361.08  7709.2  360.58  7712.4  361.08  7744.5  365.27
  8062.2  375.02  8110.9  376.07  8212.5  377.07  8246.9  373.64    8383  382.77
  8519.1  389.71  8635.8  394.88  8791.2  400.41  8951.6  403.92  9268.4  413.24
#Mann= 20 ,-1 , 0
  3086.3      .1       0  3305.2     .16       0  3462.1      .1       0
  3715.7     .05       0  6614.2     .08       0  6752.3     .05       0
  6921.5     .08       0  7022.4     .05       0  7238.5      .1       0
  7430.6     .07       0  7706.4    .033       0  7712.4      .1       0
  8062.2     .16       0  8110.9      .1       0  8246.9      .1       0
    8383     .08       0  8519.1     .08       0  8635.8      .1       0
  8791.2      .1       0  8951.6     .16       0
#XS Ineff= 2 , 0
                         7121.42          373.68
Permanent Ineff=
       F       F
Bank Sta=3765.4,6370.2
XS Rating Curve= 0 ,0
Exp/Cntr=0.3,0.1

Type RM Length L Ch R = 1 ,8536    ,771,771,771
BEGIN DESCRIPTION:
LAMBS CREEK 15.0
END DESCRIPTION:
XS GIS Cut Line= 3
      3555611.21      10487452.4       3554061.2     10488602.41
      3551661.21      10490802.4
#Sta/Elev= 30
  2938.6  416.39  3159.6  398.83  3251.4  385.89  3280.6  384.19  3316.1  390.21
  3483.1   378.8    3488  378.18  3537.3  368.66  3581.1  373.56  3622.8  365.21
  3670.5  366.28  3743.4     363  5787.8     363  5858.1  366.52  5999.9  370.24
  6257.8  364.61  6363.2     363  6880.7     363  6938.5  361.54  6941.2  361.04
  6944.5  361.54  6990.8  368.67  7075.9  371.86  7202.9  371.57  7309.2  364.61
  7692.3  382.38  7831.6  390.33  7947.4  392.24  7947.5  392.24  8124.4  397.96
#Mann= 14 ,-1 , 0
  2938.6     .16       0  3483.1      .1       0    3488     .16       0
  3670.5     .07       0  3743.4     .05       0  6257.8     .07       0
  6363.2     .05       0  6880.7      .1       0  6938.5    .033       0
  6944.5      .1       0  7692.3     .05       0  7831.6      .1       0
  7947.4     .16       0  7947.5     .05       0
#XS Ineff= 2 , 0
                         5999.16          370.28
Permanent Ineff=
       F       F
Bank Sta=3670.5,5858.1
XS Rating Curve= 0 ,0
Exp/Cntr=0.3,0.1

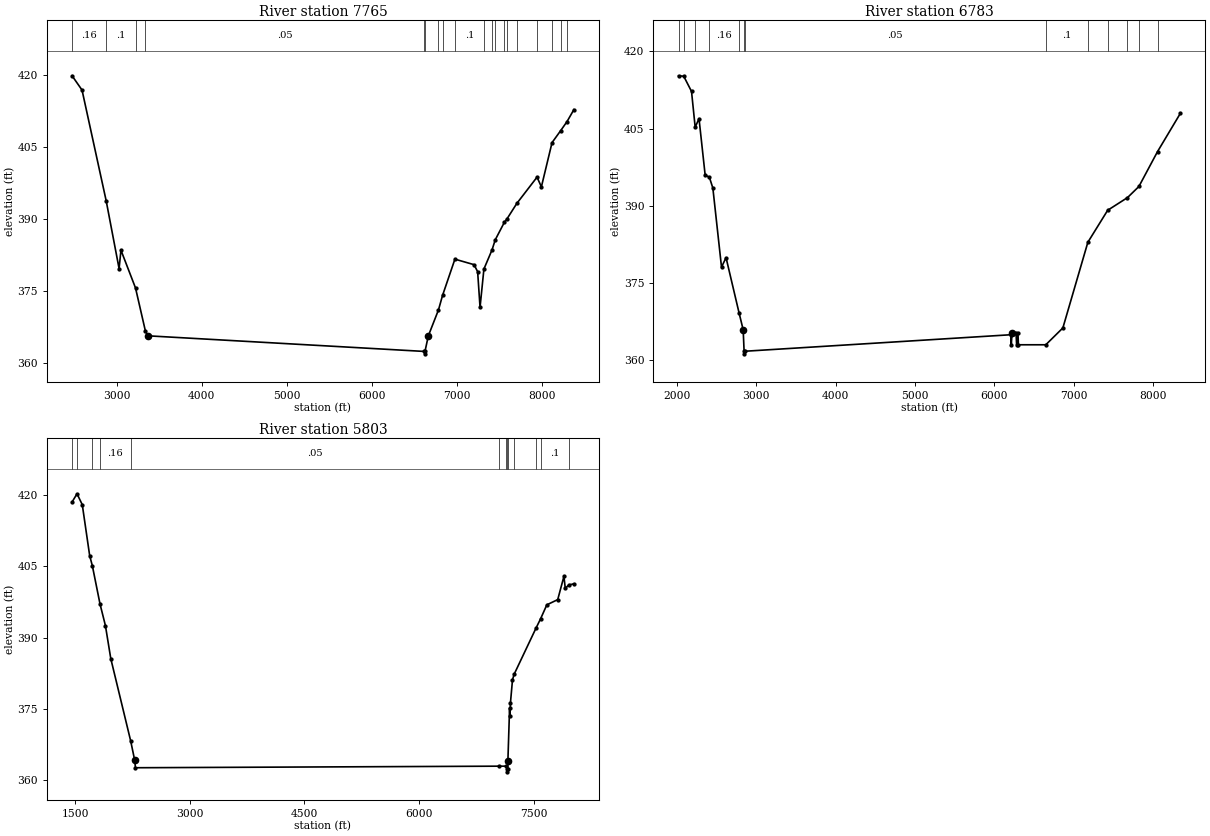
Type RM Length L Ch R = 1 ,7765    ,982,982,982
BEGIN DESCRIPTION:
LAMBS CREEK 14.0
END DESCRIPTION:
XS GIS Cut Line= 3
      3555542.11     10487041.64      3553342.11     10488241.64
      3550942.11     10490641.64
#Sta/Elev= 30
  2475.8  419.89    2593  416.91  2876.7  393.83  3028.7  379.67  3050.6  383.51
    3222  375.62  3337.1  366.72  3366.7  365.65  6619.3  362.39    6622  361.89
  6625.3  362.39  6664.7  365.64  6784.2  371.06  6831.7  374.06  6977.2  381.64
  7202.1  380.49  7244.5  379.03  7272.8  371.59  7318.3  379.58  7413.9  383.58
  7451.8  385.68  7559.4  389.35  7585.3  389.92    7705  393.26    7943  398.75
  7994.1  396.72  8119.3  405.95  8221.7  408.47  8295.3  410.33  8375.9  412.82
#Mann= 19 ,-1 , 0
  2475.8     .16       0  2876.7      .1       0    3222     .07       0
  3337.1     .05       0  6619.3    .033       0  6625.3     .05       0
  6784.2      .1       0  6831.7     .05       0  6977.2      .1       0
  7318.3     .05       0  7413.9     .08       0  7451.8     .05       0
  7559.4      .1       0  7585.3     .05       0    7705     .16       0
    7943      .1       0  8119.3     .08       0  8221.7      .1       0
  8295.3     .08       0
Bank Sta=3366.7,6664.7
XS Rating Curve= 0 ,0
Exp/Cntr=0.3,0.1

Type RM Length L Ch R = 1 ,6783    ,980,980,980
BEGIN DESCRIPTION:
LAMBS CREEK 2.0
END DESCRIPTION:
XS GIS Cut Line= 4
      3555438.05     10486584.74      3552747.03     10487444.12
      3552035.23     10488251.42      3550958.85     10490421.54
#Sta/Elev= 30
  2021.4  415.24    2087  415.15  2185.1   412.2  2231.1  405.26  2279.6  406.91
  2357.3  395.89    2409  395.58  2453.9  393.44    2563  378.08  2620.1  379.92
  2783.3  369.25    2836  365.91  2847.6  361.74  2850.3  361.24  2853.6  361.74
  6209.2  364.95  6214.8     363  6224.2  365.27  6274.5  365.37    6282     363
  6298.9  365.26  6304.5     363  6649.5     363  6864.8  366.27  7179.8  382.91
  7429.4  389.12    7679  391.58    7823  393.74  8057.9  400.52    8345  407.93
#Mann= 13 ,-1 , 0
  2021.4     .05       0    2087     .16       0  2231.1      .1       0
    2409     .16       0  2783.3     .05       0  2847.6    .033       0
  2853.6     .05       0  6649.5      .1       0  7179.8     .16       0
  7429.4      .1       0    7679     .08       0    7823      .1       0
  8057.9     .16       0
Bank Sta=2836,6224.2
XS Rating Curve= 0 ,0
Exp/Cntr=0.3,0.1

Type RM Length L Ch R = 1 ,5803    ,0,0,0
BEGIN DESCRIPTION:
LAMBS CREEK 1.0
END DESCRIPTION:
XS GIS Cut Line= 4
      3555394.63     10486176.76      3552260.92     10486584.75
      3551453.63      10487322.6      3550785.23     10489536.15
#Sta/Elev= 30
  1461.1  418.45  1525.9  420.18  1594.7  417.89  1691.6  407.18  1726.3  405.08
  1826.5  397.07  1897.3  392.52  1967.9  385.56  2227.4  368.34  2280.5  364.25
  2290.6  362.67  7042.7     363    7144     363  7155.3  362.31    7158  361.81
  7161.3  362.31 7163.94  364.09    7186  375.15  7191.2  373.53  7197.3  376.26
  7224.2  381.12  7245.3  382.28  7531.6  391.97  7590.7   393.9  7673.7  396.87
    7816  397.96  7897.1  402.83  7914.9  400.34  7961.5  401.05  8027.2  401.27
#Mann= 13 ,-1 , 0
  1461.1      .1       0  1525.9     .16       0  1726.3     .05       0
  1826.5     .16       0  2227.4     .05       0  7042.7     .07       0
    7144     .16       0  7155.3    .033       0  7161.3     .16       0
  7245.3      .1       0  7531.6     .16       0  7590.7      .1       0
  7961.5     .05       0
Bank Sta=2280.5,7163.94
XS Rating Curve= 0 ,0
Exp/Cntr=0.3,0.1

Chan Stop Cuts=-1
Use User Specified Reach Order=0
Composite Channel Slope=5