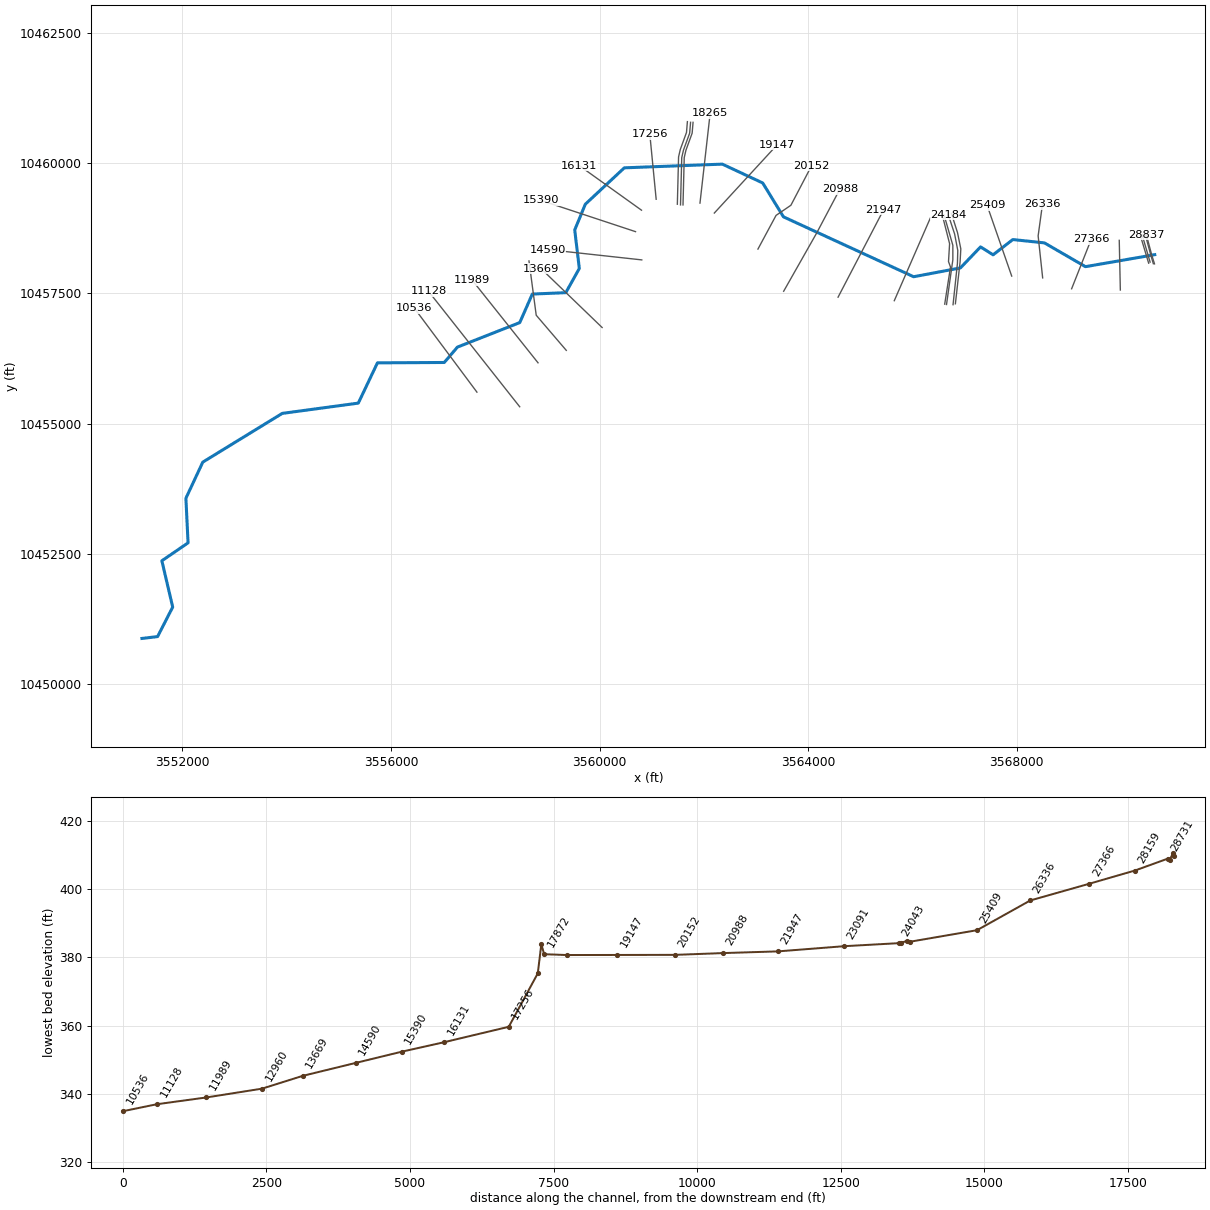
--- LONG HOLLOW CREEK.prj (project) ---

Proj Title=LONG HOLLOW CREEK Base Level Engineering
Current Plan=p01
Default Exp/Contr=0.3,0.1
English Units
Geom File=g01
Flow File=f01
Plan File=p01
BEGIN DESCRIPTION:
LONG HOLLOW CREEK
END DESCRIPTION:

--- LONG HOLLOW CREEK.p01 (plan) ---

Plan Title=Multiple Run
Short Identifier=Multiple
Geom File=g01
Flow File=f01
Subcritical Flow
K Sum by GR= 0
Std Step Tol= 0.01
Critical Tol= 0.01
Num of Std Step Trials= 20
Max Error Tol= 0.3
Flow Tol Ratio= 0.001
Split Flow NTrial= 30
Split Flow Tol= 0.02
Split Flow Ratio= 0.02
Log Output Level= 0
Friction Slope Method= 1
Unsteady Friction Slope Method= 2
Unsteady Bridges Friction Slope Method= 1
Parabolic Critical Depth
Global Vel Dist=  1 , 1 , 1
Global Log Level= 0
CheckData=True
Encroach Param= -1, 0, 0, 0
BEGIN DESCRIPTION:
Multiple Run
END DESCRIPTION:

--- LONG HOLLOW CREEK.f01 (steady flow) ---

Flow Title=Multiple
Number of Profiles=7
Profile Names=10-year,25-year,50-year,1pct_min,100-year,1pct_plu,500-year
River Rch & RM= LONG HOLLOW CREE,Reach-1,28837
     902    1223    1482    1310    1772    2396    2525
River Rch & RM= LONG HOLLOW CREE,Reach-1,28765
    1406    1953    2407    2160    2921    3950    4292
River Rch & RM= LONG HOLLOW CREE,Reach-1,23091
    1689    2359    2917    2625    3550    4800    5246
River Rch & RM= LONG HOLLOW CREE,Reach-1,19147
    2171    3078    3847    3496    4728    6394    7127
River Rch & RM= LONG HOLLOW CREE,Reach-1,13669
    2467    3511    4399    4005    5416    7325    8197
River Rch & RM= LONG HOLLOW CREE,Reach-1,7627
    2704    3863    4852    4428    5988    8098    9104
River Rch & RM= LONG HOLLOW CREE,Reach-1,6145
    3073    4420    5575    5108    6908    9342   10589
Boundary for River Rch & Prof#=LONG HOLLOW CREE,Reach-1,1
Up Type=0
Dn Type=3
Dn Slope=0.005
Boundary for River Rch & Prof#=LONG HOLLOW CREE,Reach-1,2
Up Type=0
Dn Type=3
Dn Slope=0.005
Boundary for River Rch & Prof#=LONG HOLLOW CREE,Reach-1,3
Up Type=0
Dn Type=3
Dn Slope=0.005
Boundary for River Rch & Prof#=LONG HOLLOW CREE,Reach-1,4
Up Type=0
Dn Type=3
Dn Slope=0.005
Boundary for River Rch & Prof#=LONG HOLLOW CREE,Reach-1,5
Up Type=0
Dn Type=3
Dn Slope=0.005
Boundary for River Rch & Prof#=LONG HOLLOW CREE,Reach-1,6
Up Type=0
Dn Type=3
Dn Slope=0.005
Boundary for River Rch & Prof#=LONG HOLLOW CREE,Reach-1,7
Up Type=0
Dn Type=3
Dn Slope=0.005

--- LONG HOLLOW CREEK.g01 (geometry) ---

Geom Title=Existing Conditions

River Reach=LONG HOLLOW CREE,Reach-1
Reach XY= 30
      3570647.24     10458242.04      3569317.42     10458012.31
      3568530.73     10458468.22      3567924.48     10458531.96
      3567546.25     10458239.37      3567306.24     10458391.28
      3566919.31     10457987.83      3566022.99     10457819.04
      3563526.02     10458967.70      3563127.70     10459617.56
      3562353.83     10459978.57      3560473.74     10459907.70
      3559725.95     10459210.05      3559522.62     10458716.28
      3559610.67     10457977.46      3559351.25     10457513.53
      3558709.37     10457486.67      3558468.17     10456939.53
      3557272.86     10456469.43      3557020.41     10456174.57
      3555738.99     10456167.49      3555371.96     10455395.20
      3553913.57     10455198.10      3552389.37     10454263.44
      3552065.27     10453570.20      3552106.85     10452715.17
      3551604.42     10452371.42      3551812.15     10451483.52
      3551522.56     10450917.41      3551222.11     10450881.64

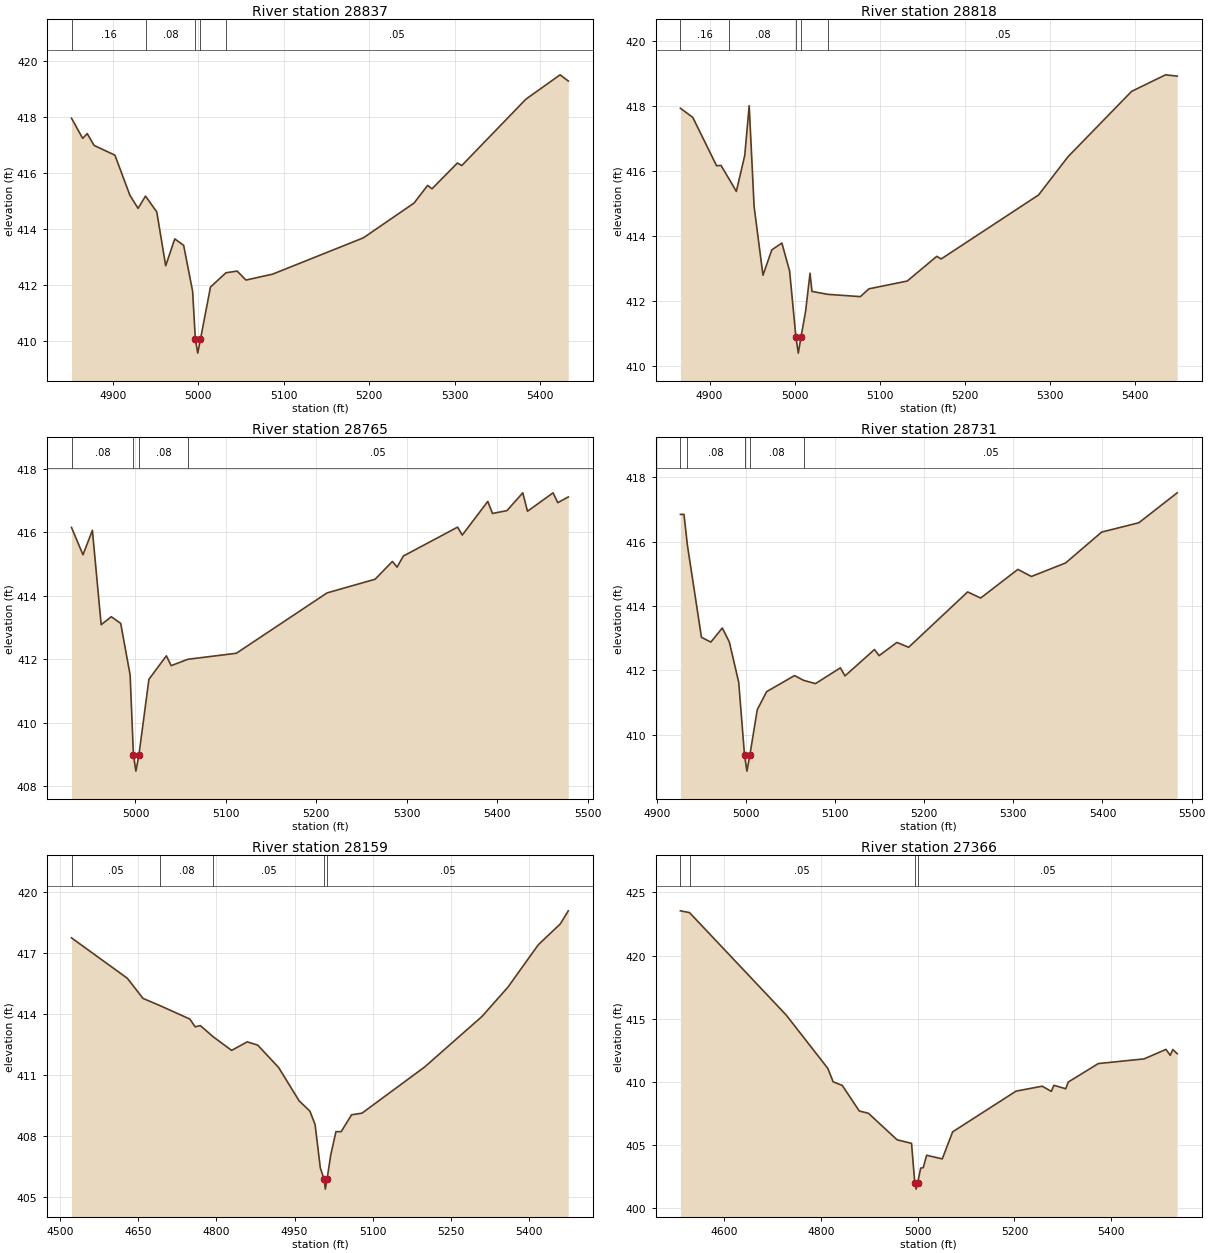
Type RM Length L Ch R = 1,28837,19,19,19
BEGIN DESCRIPTION:
LONG HOLLOW CREEK 57.02
END DESCRIPTION:
XS GIS Cut Line= 3
      3570641.79     10458066.48      3570591.42     10458226.60
      3570484.65     10458625.91
#Sta/Elev= 30
  4851.7  417.96  4864.8  417.24  4870.1  417.41  4878.1  416.99  4902.5  416.64
  4920.0  415.21  4929.6  414.74  4938.3  415.18  4951.5  414.61  4961.9  412.69
  4972.5  413.65  4982.9  413.42  4993.4  411.78  4996.6  410.07  4999.4  409.57
  5002.6  410.07  5014.3  411.93  5032.4  412.44  5045.5  412.50  5055.8  412.18
  5086.9  412.39  5193.3  413.69  5252.5  414.93  5268.3  415.56  5273.5  415.44
  5303.2  416.36  5308.3  416.27  5383.3  418.64  5423.3  419.51  5432.9  419.29
#Mann=5,-1,0
  4851.7    0.16       0  4938.3    0.08       0  4996.6    0.07       0
  5002.6    0.08       0  5032.4    0.05       0
Bank Sta=4996.6,5002.6
Exp/Cntr=0.3,0.1

Type RM Length L Ch R = 1,28818,53,53,53
BEGIN DESCRIPTION:
LONG HOLLOW CREEK 57.01
END DESCRIPTION:
XS GIS Cut Line= 3
      3570620.07     10458068.70      3570575.80     10458217.05
      3570463.83     10458631.06
#Sta/Elev= 30
  4865.8  417.94  4880.3  417.66  4908.3  416.17  4913.5  416.18  4922.6  415.78
  4931.5  415.38  4941.4  416.49  4946.6  418.02  4952.4  414.91  4962.8  412.80
  4973.2  413.58  4985.0  413.79  4994.1  412.93  5001.5  410.90  5004.3  410.40
  5007.5  410.90  5012.9  411.69  5018.1  412.86  5020.4  412.30  5039.1  412.21
  5077.2  412.14  5087.3  412.38  5132.3  412.62  5167.0  413.38  5172.2  413.30
  5286.6  415.27  5321.3  416.45  5395.9  418.46  5435.8  418.97  5449.5  418.93
#Mann=5,-1,0
  4865.8    0.16       0  4922.6    0.08       0  5001.5    0.07       0
  5007.5    0.08       0  5039.1    0.05       0
Bank Sta=5001.5,5007.5
Exp/Cntr=0.3,0.1

Type RM Length L Ch R = 1,28765,34,34,34
BEGIN DESCRIPTION:
LONG HOLLOW CREEK 57.0
END DESCRIPTION:
XS GIS Cut Line= 2
      3570557.57     10458099.43      3570403.51     10458626.69
#Sta/Elev= 30
  4929.3  416.15  4942.0  415.29  4952.4  416.06  4962.1  413.09  4973.3  413.34
  4983.7  413.13  4994.1  411.51  4997.8  408.98  5000.5  408.48  5003.8  408.98
  5014.9  411.37  5034.2  412.11  5039.5  411.80  5057.9  412.00  5111.6  412.19
  5211.9  414.09  5265.0  414.52  5284.1  415.08  5289.3  414.90  5296.2  415.25
  5356.2  416.16  5361.4  415.91  5389.6  416.97  5394.8  416.59  5410.8  416.68
  5428.3  417.24  5433.5  416.66  5461.8  417.24  5467.0  416.93  5478.6  417.11
#Mann=4,-1,0
  4929.3    0.08       0  4997.8    0.07       0  5003.8    0.08       0
  5057.9    0.05       0
Bank Sta=4997.8,5003.8
Exp/Cntr=0.3,0.1

Type RM Length L Ch R = 1,28731,572,572,572
BEGIN DESCRIPTION:
LONG HOLLOW CREEK 57.03
END DESCRIPTION:
XS GIS Cut Line= 2
      3570529.80     10458079.01      3570370.08     10458612.83
#Sta/Elev= 30
  4926.6  416.85  4930.6  416.85  4934.4  415.90  4950.2  413.03  4960.7  412.88
  4973.6  413.32  4981.5  412.88  4992.0  411.63  4998.5  409.37  5001.2  408.87
  5004.5  409.37  5012.8  410.78  5023.3  411.34  5054.6  411.84  5064.9  411.69
  5078.1  411.59  5106.0  412.08  5111.2  411.83  5144.3  412.65  5149.5  412.46
  5169.4  412.87  5182.6  412.72  5248.8  414.44  5263.4  414.25  5305.1  415.14
  5320.3  414.92  5358.6  415.34  5399.1  416.30  5440.8  416.59  5483.8  417.52
#Mann=5,-1,0
  4926.6    0.16       0  4934.4    0.08       0  4998.5    0.07       0
  5004.5    0.08       0  5064.9    0.05       0
Bank Sta=4998.5,5004.5
Exp/Cntr=0.3,0.1

Type RM Length L Ch R = 1,28159,793,793,793
BEGIN DESCRIPTION:
LONG HOLLOW CREEK 56.0
END DESCRIPTION:
XS GIS Cut Line= 2
      3569986.74     10457564.58      3569965.92     10458517.15
#Sta/Elev= 30
  4522.2  417.76  4629.3  415.77  4659.3  414.78  4692.2  414.42  4749.3  413.76
  4759.3  413.38  4769.3  413.44  4794.0  412.89  4829.3  412.22  4859.3  412.64
  4879.3  412.48  4919.4  411.38  4958.7  409.74  4979.4  409.23  4989.4  408.57
  4999.4  406.44  5006.4  405.89  5009.1  405.39  5012.4  405.89  5019.4  407.07
  5029.4  408.22  5039.4  408.22  5059.4  409.05  5079.4  409.13  5199.4  411.40
  5309.5  413.89  5359.5  415.34  5417.5  417.42  5459.5  418.44  5475.0  419.09
#Mann=5,-1,0
  4522.2    0.05       0  4692.2    0.08       0  4794.0    0.05       0
  5006.4    0.03       0  5012.4    0.05       0
Bank Sta=5006.4,5012.4
Exp/Cntr=0.3,0.1

Type RM Length L Ch R = 1,27366,1030,1030,1030
BEGIN DESCRIPTION:
LONG HOLLOW CREEK 54.0
END DESCRIPTION:
XS GIS Cut Line= 2
      3569052.65     10457588.33      3569431.15     10458543.25
#Sta/Elev= 30
  4509.4  423.54  4528.2  423.40  4728.1  415.30  4814.2  411.08  4825.2  410.02
  4844.1  409.73  4879.2  407.71  4898.1  407.53  4957.5  405.43  4987.3  405.15
  4994.0  402.03  4996.8  401.53  5000.0  402.03  5006.2  403.19  5011.6  403.23
  5018.5  404.21  5050.8  403.92  5072.3  406.06  5203.4  409.28  5257.4  409.67
  5276.4  409.26  5281.7  409.74  5306.1  409.47  5311.4  410.00  5373.5  411.46
  5468.2  411.83  5513.4  412.58  5522.2  412.11  5527.6  412.57  5536.6  412.24
#Mann=4,-1,0
  4509.4    0.08       0  4528.2    0.05       0  4994.0    0.03       0
  5000.0    0.05       0
Bank Sta=4994,5000
Exp/Cntr=0.3,0.1

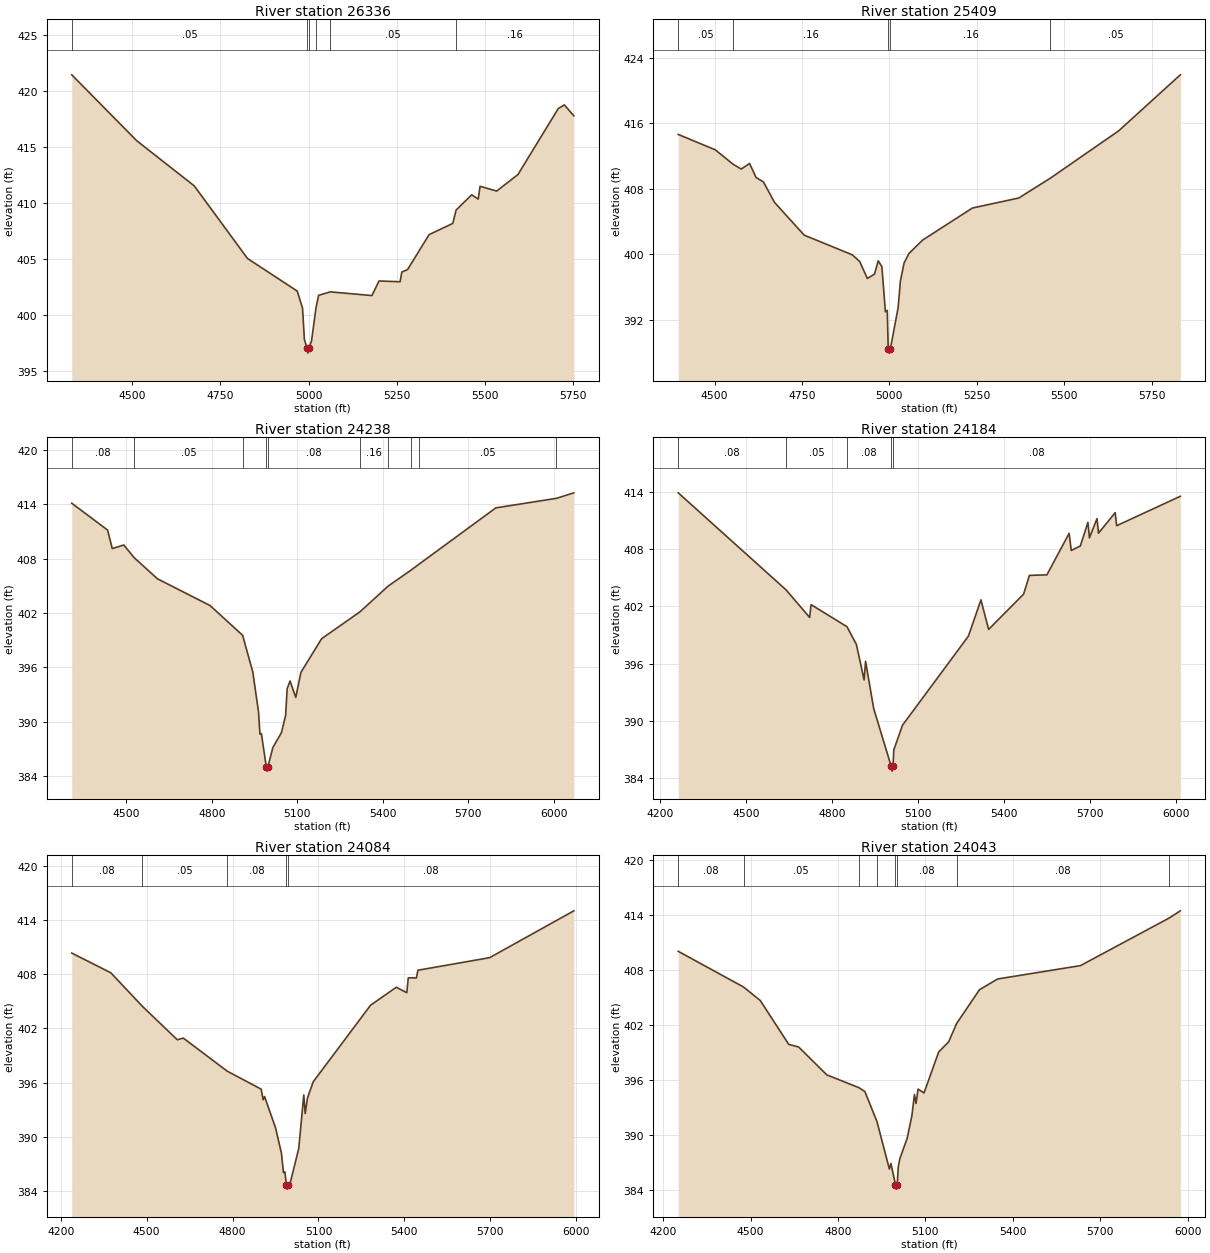
Type RM Length L Ch R = 1,26336,927,927,927
BEGIN DESCRIPTION:
LONG HOLLOW CREEK 52.0
END DESCRIPTION:
XS GIS Cut Line= 3
      3568497.11     10457796.68      3568410.30     10458602.26
      3568493.41     10459208.25
#Sta/Elev= 30
  4329.5  421.42  4513.4  415.55  4676.5  411.52  4827.3  405.05  4968.1  402.15
  4983.1  400.61  4988.3  397.84  4995.3  397.12  4998.1  396.62  5001.3  397.12
  5008.4  397.69  5021.2  400.66  5028.5  401.77  5061.6  402.08  5179.5  401.75
  5199.7  403.05  5259.3  402.98  5264.3  403.85  5280.4  404.06  5341.5  407.18
  5408.6  408.18  5418.0  409.37  5462.1  410.73  5480.7  410.35  5485.8  411.49
  5532.8  411.06  5593.3  412.54  5707.2  418.41  5724.5  418.74  5751.4  417.77
#Mann=6,-1,0
  4329.5    0.05       0  4995.3    0.03       0  5001.3    0.05       0
  5021.2    0.16       0  5061.6    0.05       0  5418.0    0.16       0
Bank Sta=4995.3,5001.3
Exp/Cntr=0.3,0.1

Type RM Length L Ch R = 1,25409,1171,1171,1171
BEGIN DESCRIPTION:
LONG HOLLOW CREEK 50.0
END DESCRIPTION:
XS GIS Cut Line= 2
      3567903.36     10457831.41      3567431.54     10459187.90
#Sta/Elev= 30
  4396.0  414.66  4501.6  412.79  4552.9  411.02  4576.2  410.43  4600.2  411.11
  4618.6  409.40  4639.8  408.85  4671.5  406.35  4756.2  402.35  4893.9  399.94
  4915.0  399.13  4937.0  397.05  4957.4  397.58  4968.1  399.21  4978.6  398.48
  4988.6  392.97  4993.9  393.14  4996.7  388.42  4999.5  387.92  5002.7  388.42
  5025.0  393.47  5031.5  396.73  5042.1  398.95  5056.1  400.11  5095.0  401.74
  5237.4  405.66  5370.3  406.89  5460.7  409.32  5656.2  415.11  5832.2  421.95
#Mann=5,-1,0
  4396.0    0.05       0  4552.9    0.16       0  4996.7    0.07       0
  5002.7    0.16       0  5460.7    0.05       0
Bank Sta=4996.7,5002.7
Exp/Cntr=0.3,0.1

Type RM Length L Ch R = 1,24238,54,54,54
BEGIN DESCRIPTION:
LONG HOLLOW CREEK 48.03
END DESCRIPTION:
XS GIS Cut Line= 5
      3566823.20     10457300.37      3566913.49     10458102.49
      3566927.38     10458352.49      3566864.88     10458661.52
      3566746.97     10459032.58
#Sta/Elev= 30
  4308.2  414.11  4433.9  411.15  4450.4  409.10  4490.6  409.50  4527.9  408.08
  4608.8  405.77  4793.8  402.81  4907.8  399.53  4943.5  395.49  4963.6  391.09
  4968.8  388.61  4973.8  388.67  4990.8  385.03  4993.5  384.53  4996.8  385.03
  5013.9  387.13  5044.1  388.78  5058.8  390.69  5064.2  393.64  5074.3  394.48
  5094.4  392.67  5112.4  395.43  5185.1  399.15  5320.1  402.13  5419.0  404.97
  5499.1  406.73  5527.5  407.39  5796.6  413.60  6009.2  414.65  6070.4  415.26
#Mann=10,-1,0
  4308.2    0.08       0  4527.9    0.05       0  4907.8    0.08       0
  4990.8    0.07       0  4996.8    0.08       0  5320.1    0.16       0
  5419.0     0.1       0  5499.1    0.08       0  5527.5    0.05       0
  6009.2    0.08       0
Bank Sta=4990.8,4996.8
Exp/Cntr=0.3,0.1

Type RM Length L Ch R = 1,24184,100,100,100
BEGIN DESCRIPTION:
LONG HOLLOW CREEK 48.0
END DESCRIPTION:
XS GIS Cut Line= 5
      3566778.36     10457282.81      3566862.27     10458072.98
      3566869.22     10458322.98      3566808.45     10458638.95
      3566687.07     10459006.56
#Sta/Elev= 30
  4262.4  413.87  4639.2  403.71  4721.4  400.83  4726.4  402.17  4851.9  399.86
  4884.7  398.00  4911.6  394.29  4916.7  396.24  4945.1  391.30  5006.3  385.25
  5009.0  384.75  5012.3  385.25  5015.4  386.97  5045.6  389.55  5275.8  398.87
  5319.7  402.67  5346.5  399.58  5468.7  403.27  5489.0  405.23  5550.1  405.29
  5627.7  409.63  5635.1  407.84  5666.8  408.31  5693.3  410.78  5698.6  409.16
  5725.0  411.17  5730.3  409.65  5788.5  411.79  5793.8  410.43  6016.0  413.51
#Mann=5,-1,0
  4262.4    0.08       0  4639.2    0.05       0  4851.9    0.08       0
  5006.3    0.07       0  5012.3    0.08       0
Bank Sta=5006.3,5012.3
Exp/Cntr=0.3,0.1

Type RM Length L Ch R = 1,24084,41,41,41
BEGIN DESCRIPTION:
LONG HOLLOW CREEK 48.01
END DESCRIPTION:
XS GIS Cut Line= 4
      3566653.07     10457286.50      3566774.60     10458144.16
      3566774.60     10458421.93      3566604.76     10459007.71
#Sta/Elev= 30
  4238.3  410.32  4374.8  408.14  4484.4  404.45  4607.1  400.73  4627.9  400.92
  4781.1  397.27  4900.0  395.27  4906.8  394.10  4911.8  394.46  4950.5  390.96
  4970.7  388.20  4977.8  386.03  4982.8  386.13  4987.9  384.72  4990.6  384.22
  4993.9  384.72  5001.0  384.85  5031.3  388.73  5048.8  394.64  5053.8  392.58
  5061.6  394.28  5081.8  396.09  5282.0  404.55  5372.0  406.54  5408.6  405.94
  5413.8  407.58  5442.2  407.57  5447.4  408.42  5698.0  409.81  5992.2  414.99
#Mann=5,-1,0
  4238.3    0.08       0  4484.4    0.05       0  4781.1    0.08       0
  4987.9    0.07       0  4993.9    0.08       0
Bank Sta=4987.9,4993.9
Exp/Cntr=0.3,0.1

Type RM Length L Ch R = 1,24043,952,952,952
BEGIN DESCRIPTION:
LONG HOLLOW CREEK 48.02
END DESCRIPTION:
XS GIS Cut Line= 5
      3566618.35     10457293.47      3566729.46     10458005.27
      3566691.26     10458109.43      3566712.10     10458453.18
      3566576.90     10458983.58
#Sta/Elev= 30
  4251.9  410.08  4476.2  406.18  4533.4  404.71  4631.2  399.92  4665.0  399.64
  4761.9  396.59  4871.9  395.20  4892.5  394.77  4934.1  391.48  4976.5  386.31
  4981.8  386.92  4997.4  384.62  5000.2  384.12  5003.4  384.62  5007.0  386.53
  5012.3  387.43  5037.5  389.66  5053.7  392.11  5062.6  394.45  5068.0  393.47
  5075.0  395.04  5095.5  394.62  5145.6  399.08  5180.2  400.21  5207.3  402.20
  5285.8  405.89  5348.0  407.06  5632.4  408.52  5937.7  413.73  5975.0  414.50
#Mann=8,-1,0
  4251.9    0.08       0  4476.2    0.05       0  4871.9     0.1       0
  4934.1    0.08       0  4997.4    0.07       0  5003.4    0.08       0
  5207.3    0.08       0  5937.7    0.05       0
Bank Sta=4997.4,5003.4
Exp/Cntr=0.3,0.1

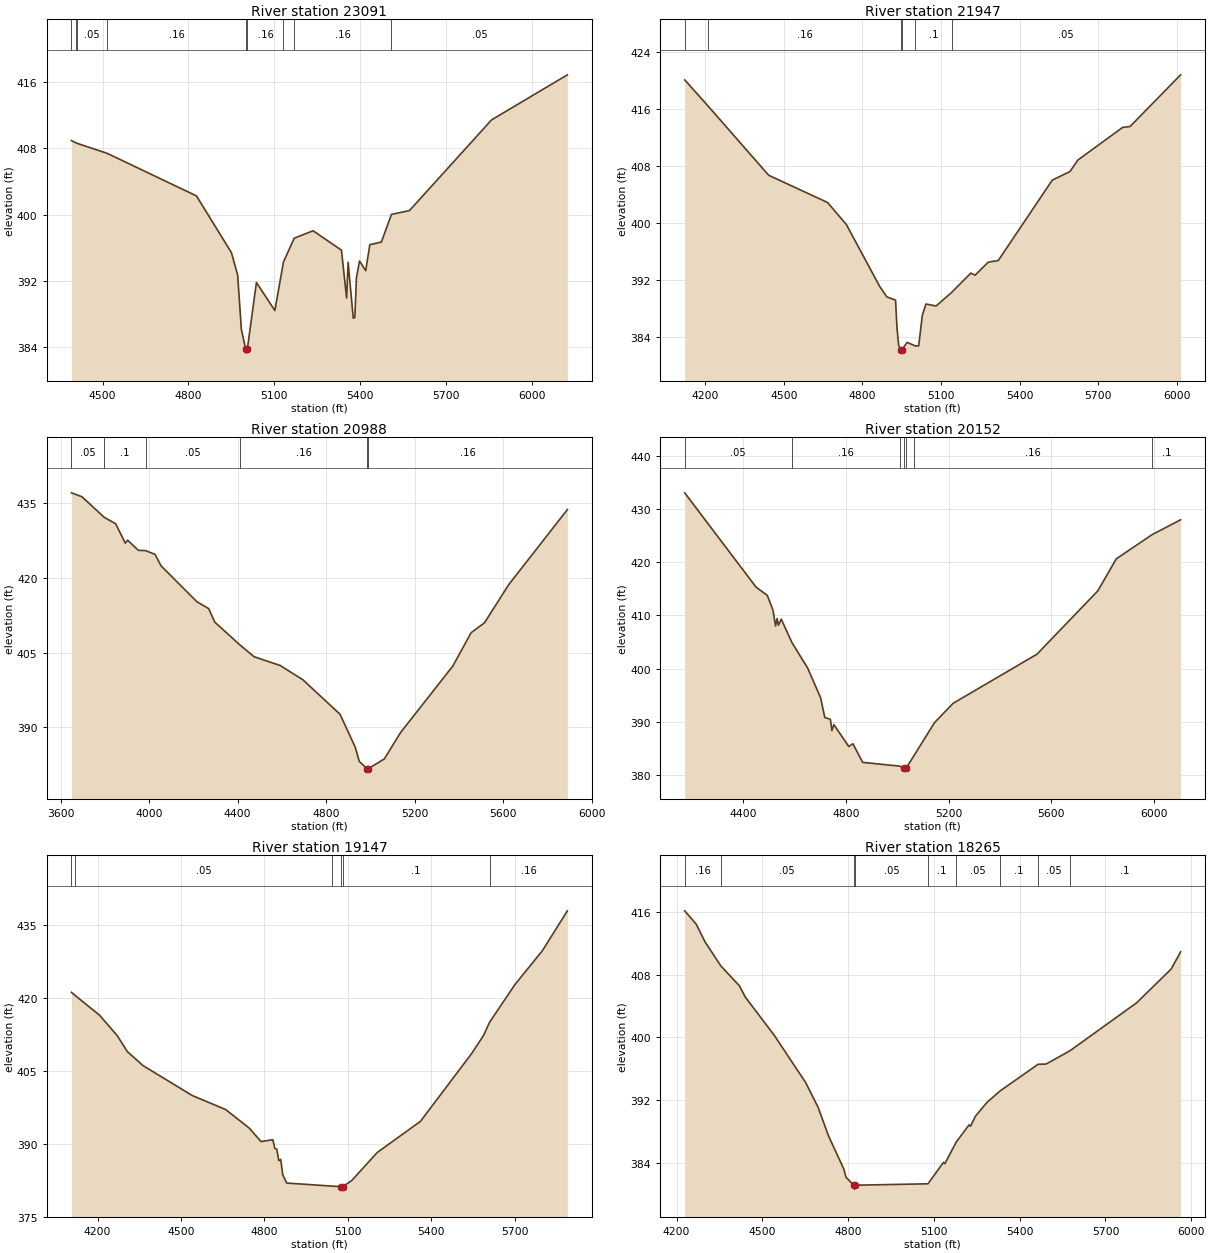
Type RM Length L Ch R = 1,23091,1144,1144,1144
BEGIN DESCRIPTION:
LONG HOLLOW CREEK 46.0
END DESCRIPTION:
XS GIS Cut Line= 2
      3565651.33     10457359.41      3566343.75     10458947.31
#Sta/Elev= 30
  4391.3  408.96  4406.9  408.69  4411.8  408.61  4515.9  407.41  4827.9  402.26
  4950.1  395.39  4971.9  392.67  4984.7  386.12  4999.7  383.73  5002.4  383.23
  5005.7  383.73  5037.4  391.78  5101.8  388.38  5131.8  394.26  5169.5  397.14
  5235.3  398.04  5334.4  395.69  5352.4  389.90  5357.8  394.22  5375.6  387.45
  5381.2  387.55  5386.7  392.33  5397.4  394.38  5419.2  393.21  5433.5  396.35
  5473.8  396.67  5509.2  400.02  5571.9  400.48  5858.9  411.46  6123.6  416.91
#Mann=9,-1,0
  4391.3    0.05       0  4406.9    0.16       0  4411.8    0.05       0
  4515.9    0.16       0  4999.7    0.07       0  5005.7    0.16       0
  5131.8     0.1       0  5169.5    0.16       0  5509.2    0.05       0
Bank Sta=4999.7,5005.7
Exp/Cntr=0.3,0.1

Type RM Length L Ch R = 1,21947,959,959,959
BEGIN DESCRIPTION:
LONG HOLLOW CREEK 42.0
END DESCRIPTION:
XS GIS Cut Line= 2
      3564573.21     10457427.15      3565447.38     10459106.11
#Sta/Elev= 30
  4121.5  420.10  4212.1  416.37  4442.2  406.70  4666.7  402.88  4738.6  399.78
  4865.6  391.10  4893.3  389.61  4926.3  389.17  4931.9  385.21  4938.3  382.82
  4945.4  382.22  4948.1  381.72  4951.4  382.22  4970.5  383.23  5002.1  382.73
  5014.7  382.75  5028.5  387.03  5042.4  388.62  5081.0  388.34  5140.5  390.25
  5213.6  392.96  5230.0  392.67  5279.9  394.49  5318.4  394.73  5524.6  406.02
  5592.2  407.23  5622.2  408.84  5793.4  413.43  5821.1  413.54  6014.4  420.81
#Mann=6,-1,0
  4121.5    0.05       0  4212.1    0.16       0  4945.4    0.07       0
  4951.4    0.16       0  5002.1     0.1       0  5140.5    0.05       0
Bank Sta=4945.4,4951.4
Exp/Cntr=0.3,0.1

Type RM Length L Ch R = 1,20988,836,836,836
BEGIN DESCRIPTION:
LONG HOLLOW CREEK 40.0
END DESCRIPTION:
XS GIS Cut Line= 3
      3563529.71     10457540.62      3564161.63     10458655.17
      3564609.57     10459502.42
#Sta/Elev= 30
  3649.4  437.08  3696.6  436.30  3798.1  432.14  3849.3  430.86  3892.6  426.97
  3902.7  427.58  3951.7  425.54  3984.2  425.48  4026.8  424.73  4054.1  422.42
  4215.7  415.23  4269.1  413.84  4296.5  411.13  4412.3  406.47  4473.9  404.19
  4592.2  402.42  4694.7  399.55  4862.0  392.65  4930.6  386.07  4949.3  383.16
  4984.0  381.72  4986.7  381.22  4990.0  381.72  5062.4  383.67  5135.4  388.95
  5371.8  402.32  5454.2  409.00  5514.6  410.99  5624.6  418.68  5889.0  433.72
#Mann=6,-1,0
  3649.4    0.05       0  3798.1     0.1       0  3984.2    0.05       0
  4412.3    0.16       0  4984.0    0.07       0  4990.0    0.16       0
Bank Sta=4984,4990
Exp/Cntr=0.3,0.1

Type RM Length L Ch R = 1,20152,1005,1005,1005
BEGIN DESCRIPTION:
LONG HOLLOW CREEK 38.0
END DESCRIPTION:
XS GIS Cut Line= 4
      3563036.64     10458349.63      3563383.85     10458995.44
      3563668.58     10459189.89      3564064.36     10459946.74
#Sta/Elev= 30
  4171.8  433.04  4449.8  415.31  4493.6  413.75  4515.5  411.01  4526.0  407.99
  4531.8  409.40  4537.4  408.15  4548.0  409.29  4589.5  404.89  4650.9  400.08
  4701.4  394.50  4717.6  390.79  4739.5  390.45  4745.2  388.32  4753.1  389.44
  4810.9  385.33  4827.2  385.85  4865.3  382.35  5009.0  381.64  5027.7  381.20
  5030.4  380.70  5033.7  381.20  5065.6  383.65  5145.1  389.82  5217.8  393.46
  5544.2  402.69  5781.3  414.60  5853.2  420.62  5992.6  425.17  6103.9  427.97
#Mann=7,-1,0
  4171.8    0.05       0  4589.5    0.16       0  5009.0     0.1       0
  5027.7    0.07       0  5033.7     0.1       0  5065.6    0.16       0
  5992.6     0.1       0
Bank Sta=5027.7,5033.7
Exp/Cntr=0.3,0.1

Type RM Length L Ch R = 1,19147,882,882,882
BEGIN DESCRIPTION:
LONG HOLLOW CREEK 36.0
END DESCRIPTION:
XS GIS Cut Line= 2
      3562199.84     10459040.60      3563407.62     10460352.50
#Sta/Elev= 30
  4106.1  421.13  4120.0  420.46  4207.4  416.42  4270.9  412.21  4306.7  408.97
  4363.4  406.07  4540.3  399.92  4660.6  397.03  4745.6  393.21  4787.6  390.45
  4830.1  390.83  4837.5  389.03  4844.3  388.89  4851.7  386.51  4858.5  386.79
  4865.9  383.62  4880.0  381.92  5042.5  381.29  5074.9  381.17  5077.7  380.67
  5080.9  381.17  5113.4  382.41  5205.5  388.20  5360.9  394.60  5545.2  408.56
  5587.8  412.26  5609.4  414.97  5700.6  422.72  5799.9  429.73  5889.3  437.89
#Mann=6,-1,0
  4106.1     0.1       0  4120.0    0.05       0  5042.5     0.1       0
  5074.9   0.033       0  5080.9     0.1       0  5609.4    0.16       0
Bank Sta=5074.9,5080.9
Exp/Cntr=0.3,0.1

Type RM Length L Ch R = 1,18265,393,393,393
BEGIN DESCRIPTION:
LONG HOLLOW CREEK 34.0
END DESCRIPTION:
XS GIS Cut Line= 2
      3561924.77     10459231.38      3562120.08     10460954.45
#Sta/Elev= 30
  4228.6  416.14  4269.1  414.43  4299.3  412.21  4354.7  409.13  4420.1  406.57
  4440.2  405.16  4540.8  400.32  4651.6  394.24  4695.1  391.08  4732.1  387.39
  4784.7  383.24  4792.5  382.17  4819.6  381.15  4822.4  380.65  4825.6  381.15
  5079.2  381.33  5133.4  384.06  5138.4  383.90  5178.4  386.67  5223.1  388.85
  5228.1  388.67  5245.3  389.95  5285.6  391.71  5331.8  393.18  5464.2  396.57
  5492.1  396.60  5575.2  398.28  5808.9  404.41  5929.7  408.72  5962.7  410.91
#Mann=9,-1,0
  4228.6    0.16       0  4354.7    0.05       0  4819.6   0.033       0
  4825.6    0.05       0  5079.2     0.1       0  5178.4    0.05       0
  5331.8     0.1       0  5464.2    0.05       0  5575.2     0.1       0
Bank Sta=4819.6,4825.6
Exp/Cntr=0.3,0.1

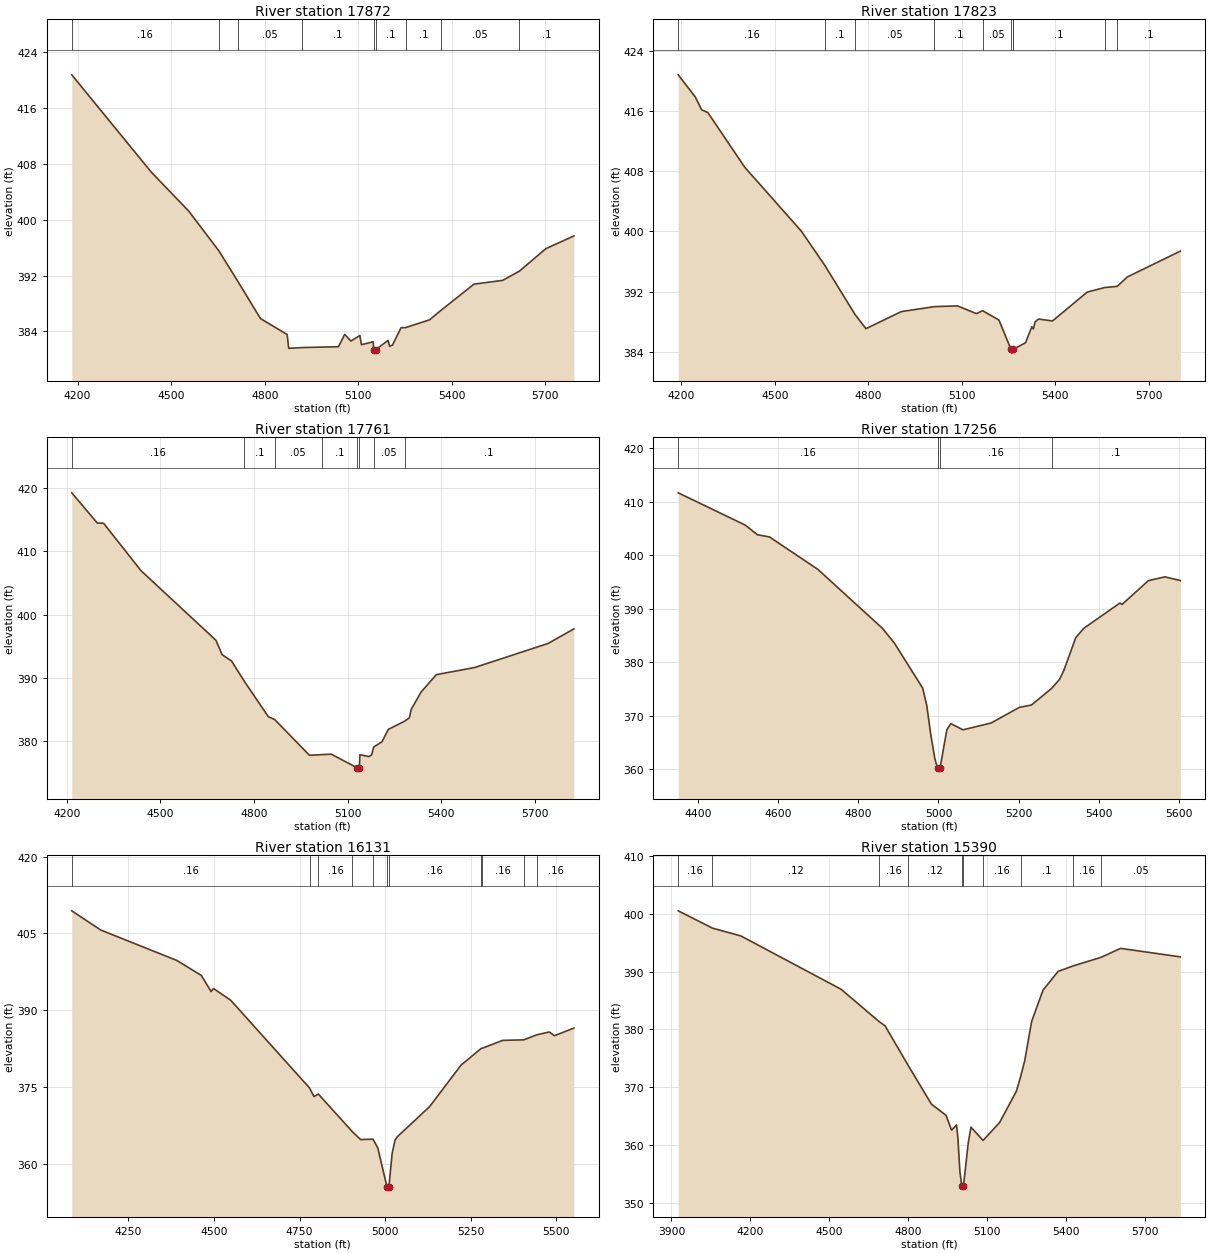
Type RM Length L Ch R = 1,17872,49,49,49
BEGIN DESCRIPTION:
LONG HOLLOW CREEK 33.01
END DESCRIPTION:
XS GIS Cut Line= 5
      3561599.25     10459196.69      3561622.69     10460103.79
      3561655.67     10460246.15      3561774.60     10460572.54
      3561791.96     10460780.91
#Sta/Elev= 30
  4181.3  420.79  4436.3  406.84  4556.4  401.25  4652.6  395.58  4714.4  391.14
  4786.5  385.84  4872.0  383.56  4877.0  381.58  4921.0  381.69  5036.5  381.81
  5056.5  383.58  5076.5  382.62  5105.1  383.42  5110.2  382.10  5147.8  382.52
  5149.9  381.39  5152.6  380.89  5155.9  381.39  5195.6  382.71  5200.7  381.87
  5209.7  382.04  5237.2  384.53  5252.1  384.55  5328.9  385.67  5365.7  387.04
  5471.1  390.78  5562.8  391.32  5616.6  392.64  5701.7  395.87  5791.3  397.69
#Mann=9,-1,0
  4181.3    0.16       0  4652.6     0.1       0  4714.4    0.05       0
  4921.0     0.1       0  5149.9    0.07       0  5155.9     0.1       0
  5252.1     0.1       0  5365.7    0.05       0  5616.6     0.1       0
Bank Sta=5149.9,5155.9
Exp/Cntr=0.3,0.1

Type RM Length L Ch R = 1,17823,62,62,62
BEGIN DESCRIPTION:
LONG HOLLOW CREEK 33.0
END DESCRIPTION:
XS GIS Cut Line= 5
      3561551.51     10459196.67      3561574.95     10460103.79
      3561607.93     10460246.15      3561726.85     10460572.54
      3561744.22     10460780.89
#Sta/Elev= 30
  4190.6  420.82  4245.6  417.86  4265.6  416.17  4285.6  415.80  4404.0  408.53
  4585.7  400.02  4660.1  395.52  4758.3  388.91  4792.6  387.07  4905.8  389.34
  5011.8  390.00  5085.9  390.10  5146.9  389.07  5166.6  389.46  5219.0  388.22
  5257.6  384.32  5260.4  383.82  5263.6  384.32  5265.6  384.34  5304.3  385.20
  5324.3  387.32  5329.6  387.03  5335.1  387.98  5345.8  388.35  5390.7  388.10
  5502.4  391.94  5558.3  392.54  5598.2  392.70  5630.8  393.95  5800.6  397.38
#Mann=10,-1,0
  4190.6    0.16       0  4660.1     0.1       0  4758.3    0.05       0
  5011.8     0.1       0  5166.6    0.05       0  5257.6    0.03       0
  5263.6    0.05       0  5265.6     0.1       0  5558.3    0.05       0
  5598.2     0.1       0
Bank Sta=5257.6,5263.6
Exp/Cntr=0.3,0.1

Type RM Length L Ch R = 1,17761,505,505,505
BEGIN DESCRIPTION:
LONG HOLLOW CREEK 33.02
END DESCRIPTION:
XS GIS Cut Line= 5
      3561490.74     10459209.64      3561514.18     10460116.81
      3561547.17     10460259.17      3561666.09     10460585.56
      3561683.45     10460793.86
#Sta/Elev= 30
  4215.5  419.26  4297.5  414.48  4317.5  414.45  4437.6  406.95  4677.7  395.96
  4697.7  393.67  4727.7  392.69  4767.9  389.54  4845.9  383.87  4866.1  383.43
  4977.8  377.77  5017.4  377.88  5047.8  377.95  5131.5  375.77  5134.2  375.27
  5137.5  375.77  5139.6  377.87  5169.0  377.57  5177.2  377.85  5183.7  379.09
  5210.0  379.89  5230.6  381.87  5282.5  383.15  5298.2  383.70  5303.7  385.00
  5335.6  387.77  5384.6  390.52  5506.9  391.64  5743.0  395.45  5825.5  397.75
#Mann=8,-1,0
  4215.5    0.16       0  4767.9     0.1       0  4866.1    0.05       0
  5017.4     0.1       0  5131.5    0.03       0  5137.5     0.1       0
  5183.7    0.05       0  5282.5     0.1       0
Bank Sta=5131.5,5137.5
Exp/Cntr=0.3,0.1

Type RM Length L Ch R = 1,17256,1125,1125,1125
BEGIN DESCRIPTION:
LONG HOLLOW CREEK 32.0
END DESCRIPTION:
XS GIS Cut Line= 2
      3561084.49     10459305.19      3560962.96     10460550.88
#Sta/Elev= 30
  4351.3  411.67  4518.5  405.63  4548.7  403.83  4578.8  403.42  4699.4  397.36
  4860.2  386.35  4890.3  383.56  4960.6  375.18  4970.7  371.98  4980.7  366.53
  4990.8  362.04  4997.8  360.14  5000.6  359.64  5003.8  360.14  5020.9  367.38
  5031.0  368.52  5061.1  367.36  5131.4  368.64  5201.8  371.57  5231.9  372.00
  5282.9  375.16  5302.2  376.83  5312.3  378.42  5342.4  384.61  5362.5  386.35
  5452.6  391.08  5457.6  390.80  5523.3  395.25  5564.4  395.96  5602.9  395.27
#Mann=4,-1,0
  4351.3    0.16       0  4997.8    0.07       0  5003.8    0.16       0
  5282.9     0.1       0
Bank Sta=4997.8,5003.8
Exp/Cntr=0.3,0.1

Type RM Length L Ch R = 1,16131,741,741,741
BEGIN DESCRIPTION:
LONG HOLLOW CREEK 29.0
END DESCRIPTION:
XS GIS Cut Line= 2
      3560803.27     10459095.27      3559610.50     10459949.48
#Sta/Elev= 30
  4084.3  409.42  4169.1  405.67  4391.4  399.74  4462.7  396.82  4491.6  393.67
  4498.3  394.27  4548.7  391.98  4779.3  374.85  4791.9  373.18  4804.9  373.67
  4904.4  366.32  4928.3  364.80  4964.6  364.87  4978.6  363.17  5005.1  355.63
  5007.8  355.13  5011.1  355.63  5020.5  362.13  5029.0  364.71  5035.1  365.32
  5129.7  371.21  5221.8  379.32  5281.0  382.59  5284.2  382.62  5343.4  384.15
  5404.8  384.25  5443.9  385.25  5479.8  385.79  5494.5  385.05  5551.4  386.55
#Mann=11,-1,0
  4084.3    0.16       0  4779.3    0.12       0  4804.9    0.16       0
  4904.4    0.12       0  4964.6    0.16       0  5005.1    0.07       0
  5011.1    0.16       0  5281.0    0.12       0  5284.2    0.16       0
  5404.8    0.12       0  5443.9    0.16       0
Bank Sta=5005.1,5011.1
Exp/Cntr=0.3,0.1

Type RM Length L Ch R = 1,15390,800,800,800
BEGIN DESCRIPTION:
LONG HOLLOW CREEK 27.0
END DESCRIPTION:
XS GIS Cut Line= 2
      3560688.62     10458683.84      3558876.60     10459282.64
#Sta/Elev= 30
  3925.8  400.52  4055.6  397.53  4164.4  396.16  4544.5  386.95  4688.5  381.38
  4712.0  380.61  4800.4  373.71  4888.3  367.05  4943.7  365.12  4964.8  362.55
  4983.5  363.46  4988.8  361.19  4996.4  355.34  5003.9  352.84  5006.7  352.34
  5009.9  352.84  5028.0  360.31  5038.5  363.07  5084.5  360.77  5147.5  363.88
  5210.9  369.26  5227.1  371.80  5242.7  374.55  5269.1  381.37  5312.3  386.78
  5369.6  390.03  5426.8  390.98  5532.3  392.46  5607.2  394.02  5834.2  392.55
#Mann=10,-1,0
  3925.8    0.16       0  4055.6    0.12       0  4688.5    0.16       0
  4800.4    0.12       0  5003.9    0.07       0  5009.9    0.12       0
  5084.5    0.16       0  5227.1     0.1       0  5426.8    0.16       0
  5532.3    0.05       0
Bank Sta=5003.9,5009.9
Exp/Cntr=0.3,0.1

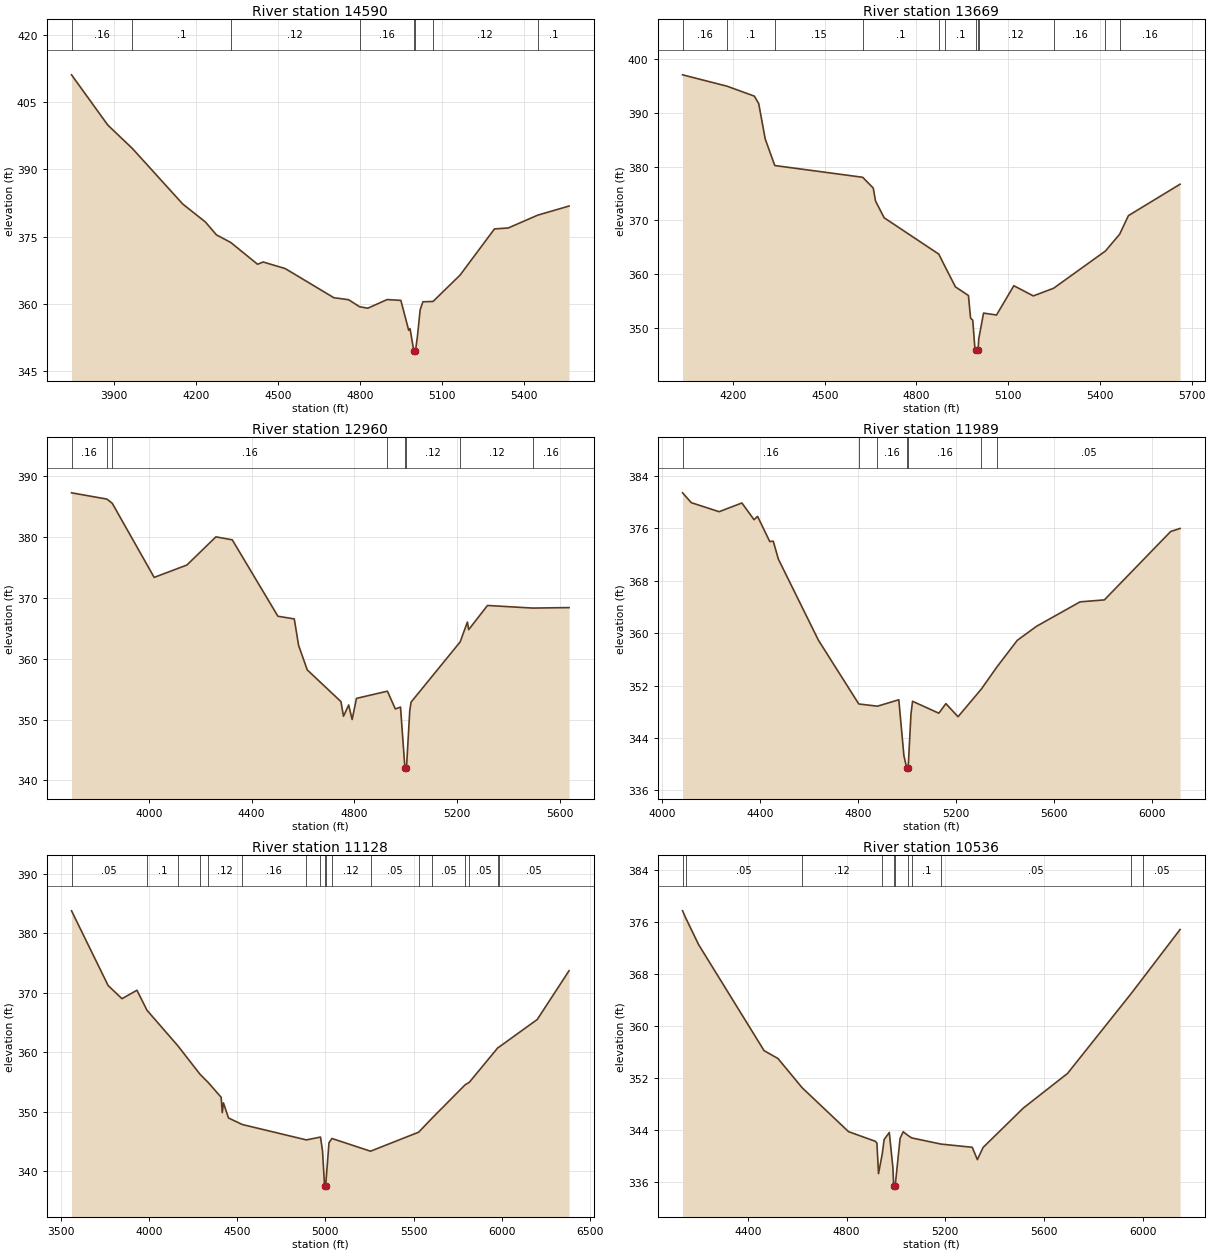
Type RM Length L Ch R = 1,14590,921,921,921
BEGIN DESCRIPTION:
LONG HOLLOW CREEK 25.0
END DESCRIPTION:
XS GIS Cut Line= 2
      3560808.49     10458142.16      3559001.19     10458340.07
#Sta/Elev= 30
  3746.5  411.06  3879.1  399.86  3969.0  394.64  4152.7  382.29  4235.8  378.27
  4276.0  375.41  4328.7  373.70  4426.3  368.86  4447.0  369.36  4527.6  367.89
  4705.0  361.41  4758.9  360.96  4799.1  359.39  4829.3  359.07  4899.7  360.99
  4950.0  360.81  4978.6  354.15  4983.6  354.52  4997.3  349.56  5000.1  349.06
  5003.3  349.56  5010.4  352.71  5020.5  358.70  5030.5  360.50  5067.5  360.57
  5166.0  366.42  5292.1  376.73  5342.4  376.94  5449.8  379.79  5564.6  381.83
#Mann=8,-1,0
  3746.5    0.16       0  3969.0     0.1       0  4328.7    0.12       0
  4799.1    0.16       0  4997.3    0.07       0  5003.3    0.16       0
  5067.5    0.12       0  5449.8     0.1       0
Bank Sta=4997.3,5003.3
Exp/Cntr=0.3,0.1

Type RM Length L Ch R = 1,13669,709,709,709
BEGIN DESCRIPTION:
LONG HOLLOW CREEK 24.0
END DESCRIPTION:
XS GIS Cut Line= 2
      3560048.02     10456845.30      3558876.64     10457975.03
#Sta/Elev= 30
  4034.8  397.13  4179.9  395.02  4269.7  393.16  4283.9  391.78  4305.2  385.18
  4336.5  380.23  4624.0  378.04  4658.7  376.03  4665.9  373.63  4694.2  370.50
  4873.1  363.72  4893.7  361.37  4927.5  357.62  4970.0  356.01  4976.9  351.82
  4984.1  351.40  4991.1  346.19  4995.3  345.78  4998.0  345.28  5001.3  345.78
  5003.7  347.95  5019.4  352.74  5061.8  352.38  5118.4  357.84  5182.2  355.94
  5248.6  357.37  5418.2  364.31  5464.7  367.45  5493.3  370.90  5662.2  376.75
#Mann=12,-1,0
  4034.8    0.16       0  4179.9     0.1       0  4336.5    0.15       0
  4624.0     0.1       0  4873.1    0.12       0  4893.7     0.1       0
  4995.3    0.07       0  5001.3     0.1       0  5003.7    0.12       0
  5248.6    0.16       0  5418.2    0.12       0  5464.7    0.16       0
Bank Sta=4995.3,5001.3
Exp/Cntr=0.3,0.1

Type RM Length L Ch R = 1,12960,971,971,971
BEGIN DESCRIPTION:
LONG HOLLOW CREEK 22.0
END DESCRIPTION:
XS GIS Cut Line= 3
      3559360.47     10456406.94      3558784.11     10457080.51
      3558645.22     10458122.19
#Sta/Elev= 30
  3698.9  387.24  3836.8  386.21  3857.5  385.52  4020.7  373.35  4148.1  375.38
  4261.1  380.01  4324.8  379.52  4502.6  366.97  4566.3  366.53  4583.1  362.19
  4616.8  358.16  4748.0  352.95  4758.0  350.55  4778.2  352.39  4791.6  350.01
  4808.5  353.48  4929.0  354.66  4959.8  351.74  4980.0  352.05  4997.2  342.03
  4999.9  341.53  5003.2  342.03  5016.0  351.43  5021.1  352.86  5212.2  362.75
  5240.5  366.02  5245.5  364.77  5318.7  368.74  5494.4  368.31  5636.3  368.39
#Mann=8,-1,0
  3698.9    0.16       0  3836.8    0.05       0  3857.5    0.16       0
  4929.0    0.12       0  4997.2    0.07       0  5003.2    0.12       0
  5212.2    0.12       0  5494.4    0.16       0
Bank Sta=4997.2,5003.2
Exp/Cntr=0.3,0.1

Type RM Length L Ch R = 1,11989,861,861,861
BEGIN DESCRIPTION:
LONG HOLLOW CREEK 19.0
END DESCRIPTION:
XS GIS Cut Line= 2
      3558818.85     10456168.23      3557553.27     10457756.71
#Sta/Elev= 30
  4084.6  381.42  4120.2  379.92  4233.9  378.54  4326.8  379.87  4376.5  377.32
  4390.9  377.83  4440.5  373.99  4454.9  374.04  4475.7  371.31  4639.1  358.94
  4804.0  349.20  4880.2  348.86  4967.4  349.84  4988.2  341.32  4999.6  339.45
  5002.4  338.95  5005.6  339.45  5017.1  347.66  5023.5  349.61  5130.8  347.79
  5159.6  349.25  5209.2  347.25  5304.7  351.49  5366.8  354.79  5451.1  358.91
  5529.5  361.05  5707.3  364.78  5806.6  365.08  6077.3  375.52  6115.6  375.98
#Mann=7,-1,0
  4084.6    0.16       0  4804.0    0.12       0  4880.2    0.16       0
  4999.6    0.07       0  5005.6    0.16       0  5304.7     0.1       0
  5366.8    0.05       0
Bank Sta=4999.6,5005.6
Exp/Cntr=0.3,0.1

Type RM Length L Ch R = 1,11128,592,592,592
BEGIN DESCRIPTION:
LONG HOLLOW CREEK 18.0
END DESCRIPTION:
XS GIS Cut Line= 2
      3558467.18     10455325.32      3556717.19     10457540.58
#Sta/Elev= 30
  3559.5  383.79  3767.2  371.22  3845.8  369.01  3930.7  370.43  3987.5  367.07
  4164.4  361.03  4287.9  356.32  4334.7  354.92  4408.5  352.42  4414.8  349.83
  4421.4  351.49  4450.1  348.94  4528.3  347.84  4892.1  345.25  4972.1  345.73
  4983.9  343.38  4995.3  337.47  4998.1  336.97  5001.3  337.47  5020.4  344.77
  5037.2  345.49  5256.0  343.35  5529.3  346.55  5603.6  348.86  5793.5  354.54
  5816.6  354.94  5979.2  360.78  5983.8  360.84  6202.2  365.51  6382.6  373.71
#Mann=18,-1,0
  3559.5    0.05       0  3987.5     0.1       0  4164.4    0.12       0
  4287.9    0.16       0  4334.7    0.12       0  4528.3    0.16       0
  4892.1    0.12       0  4972.1    0.16       0  4995.3    0.07       0
  5001.3    0.16       0  5037.2    0.12       0  5256.0    0.05       0
  5529.3     0.1       0  5603.6    0.05       0  5793.5     0.1       0
  5816.6    0.05       0  5979.2     0.1       0  5983.8    0.05       0
Bank Sta=4995.3,5001.3
Exp/Cntr=0.3,0.1

Type RM Length L Ch R = 1,10536,788,788,788
BEGIN DESCRIPTION:
LONG HOLLOW CREEK 17.0
END DESCRIPTION:
XS GIS Cut Line= 2
      3557646.98     10455605.72      3556443.89     10457220.26
#Sta/Elev= 30
  4136.4  377.69  4149.4  376.58  4201.5  372.49  4466.4  356.20  4522.6  354.99
  4620.7  350.49  4808.3  343.75  4916.8  342.27  4923.0  342.00  4929.5  337.30
  4945.0  340.43  4952.2  342.53  4973.1  343.63  4987.7  338.23  4990.9  335.42
  4993.6  334.92  4996.9  335.42  5016.8  342.72  5029.3  343.74  5050.1  343.13
  5063.9  342.79  5182.8  341.84  5308.8  341.35  5329.6  339.45  5352.6  341.32
  5515.6  347.38  5694.5  352.70  5950.2  364.89  6000.4  367.38  6149.9  374.82
#Mann=11,-1,0
  4136.4     0.1       0  4149.4    0.05       0  4620.7    0.12       0
  4945.0    0.16       0  4990.9    0.07       0  4996.9    0.16       0
  5050.1    0.05       0  5063.9     0.1       0  5182.8    0.05       0
  5950.2     0.1       0  6000.4    0.05       0
Bank Sta=4990.9,4996.9
Exp/Cntr=0.3,0.1