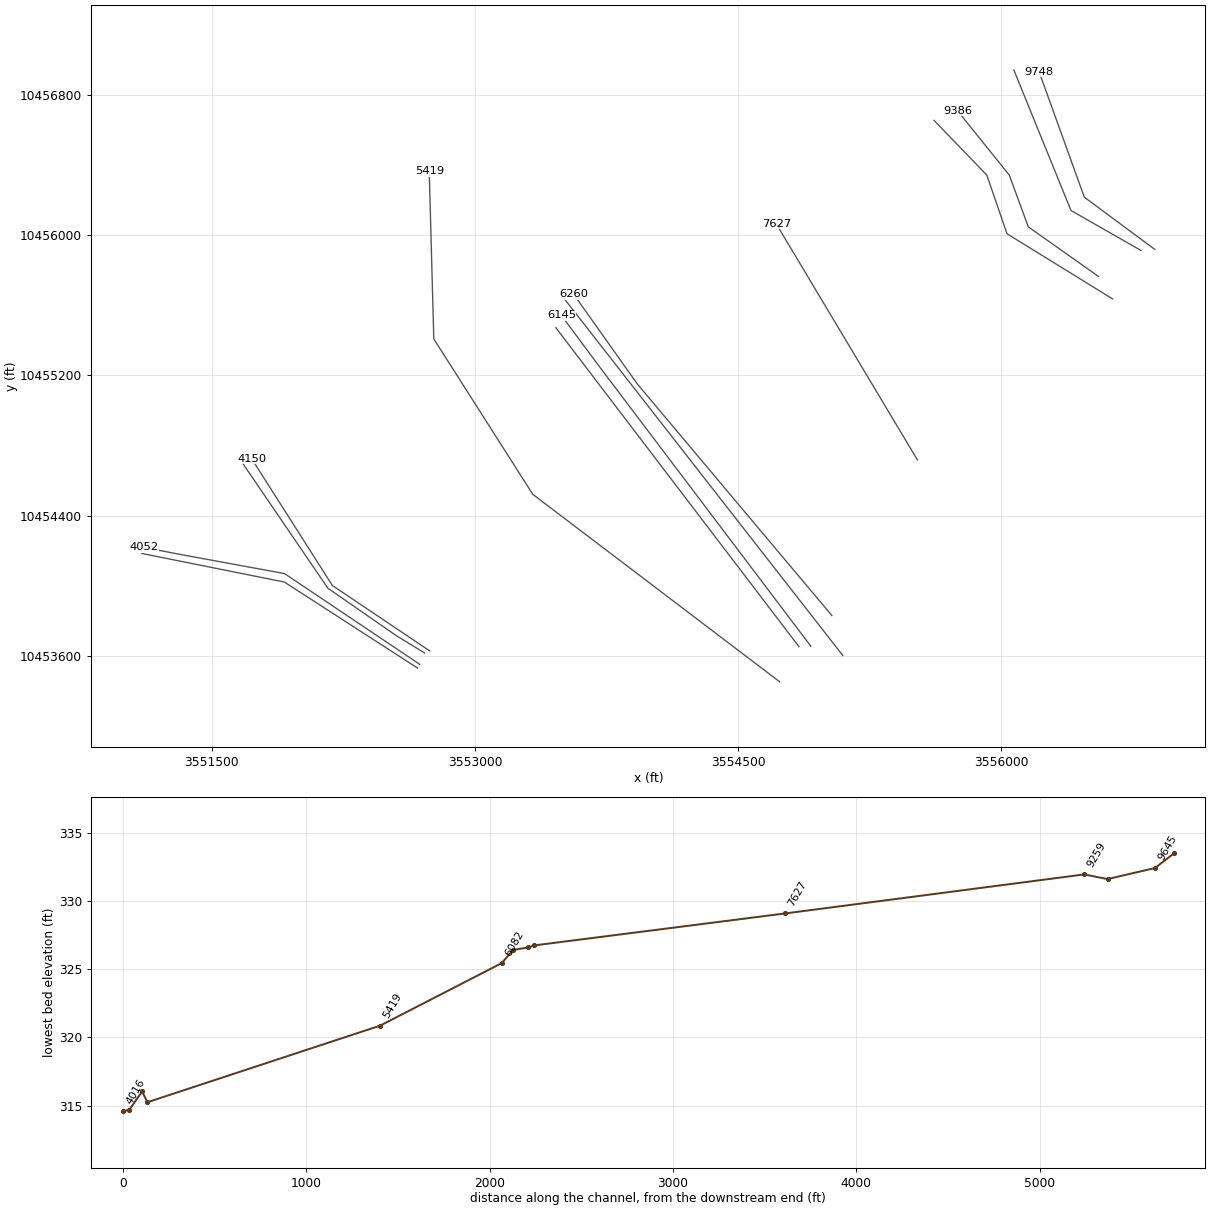
HEC-RAS study LONG HOLLOW CREEK.prj: LONG HOLLOW CREEK Base Level Engineering

--- LONG HOLLOW CREEK.g01 (geometry) --- (continued)

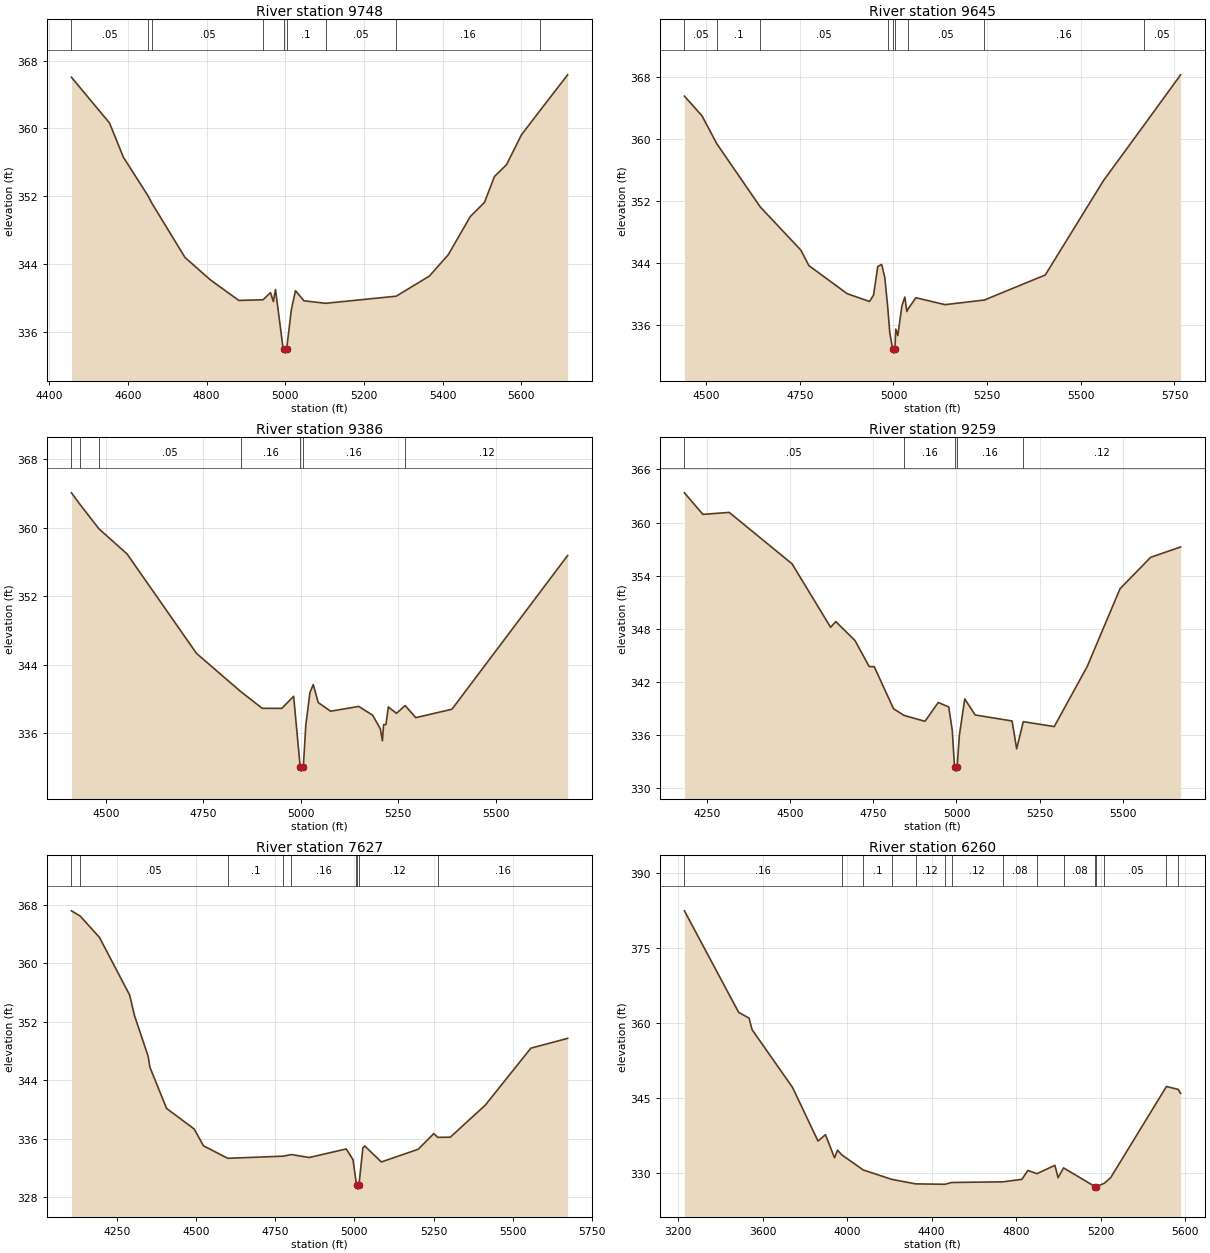
Type RM Length L Ch R = 1,9748,103,103,103
BEGIN DESCRIPTION:
LONG HOLLOW CREEK 16.0
END DESCRIPTION:
XS GIS Cut Line= 3
      3556873.91     10455918.60      3556472.40     10456215.93
      3556214.15     10456932.07
#Sta/Elev= 30
  4456.6  366.04  4553.2  360.65  4588.6  356.60  4651.0  352.06  4660.5  351.21
  4745.1  344.77  4809.8  342.12  4881.9  339.70  4943.5  339.78  4962.3  340.63
  4969.7  339.56  4975.0  341.00  4994.2  334.10  4997.4  333.98  5000.1  333.48
  5003.4  333.98  5015.4  338.62  5025.8  340.85  5047.3  339.66  5102.2  339.36
  5281.8  340.20  5366.2  342.58  5414.0  345.09  5470.1  349.60  5506.1  351.27
  5531.5  354.33  5562.1  355.72  5600.1  359.25  5648.3  362.18  5717.5  366.33
#Mann=9,-1,0
  4456.6    0.05       0  4651.0     0.1       0  4660.5    0.05       0
  4943.5     0.1       0  4997.4    0.07       0  5003.4     0.1       0
  5102.2    0.05       0  5281.8    0.16       0  5648.3    0.05       0
Bank Sta=4997.4,5003.4
Exp/Cntr=0.3,0.1

Type RM Length L Ch R = 1,9645,259,259,259
BEGIN DESCRIPTION:
LONG HOLLOW CREEK 15.0
END DESCRIPTION:
XS GIS Cut Line= 3
      3556795.73     10455912.12      3556396.44     10456139.98
      3556070.93     10456940.72
#Sta/Elev= 30
  4442.2  365.49  4489.2  362.95  4528.4  359.38  4644.9  351.21  4752.7  345.68
  4774.3  343.68  4876.6  340.06  4936.1  339.06  4946.9  339.88  4958.2  343.56
  4968.5  343.83  4976.9  342.16  4985.0  338.20  4990.1  335.09  4997.9  332.91
  5000.6  332.41  5003.9  332.91  5006.3  335.51  5011.7  334.67  5022.5  338.48
  5030.4  339.63  5035.8  337.76  5039.3  338.11  5059.9  339.54  5137.5  338.65
  5242.3  339.24  5405.2  342.47  5560.4  354.61  5667.4  361.67  5766.3  368.23
#Mann=9,-1,0
  4442.2    0.05       0  4528.4     0.1       0  4644.9    0.05       0
  4985.0     0.1       0  4997.9    0.07       0  5003.9     0.1       0
  5039.3    0.05       0  5242.3    0.16       0  5667.4    0.05       0
Bank Sta=4997.9,5003.9
Exp/Cntr=0.3,0.1

Type RM Length L Ch R = 1,9386,127,127,127
BEGIN DESCRIPTION:
LONG HOLLOW CREEK 14.0
END DESCRIPTION:
XS GIS Cut Line= 4
      3556553.28     10455764.29      3556153.39     10456046.66
      3556044.88     10456341.80      3555750.52     10456707.58
#Sta/Elev= 30
  4411.5  364.07  4434.0  362.68  4482.2  359.86  4554.0  356.95  4732.5  345.33
  4845.5  340.90  4901.0  338.93  4951.2  338.92  4981.7  340.33  4998.5  332.10
  5001.3  331.60  5004.5  332.10  5006.9  332.36  5012.9  336.95  5023.5  340.76
  5032.0  341.70  5044.8  339.60  5076.8  338.59  5148.6  339.15  5184.4  338.13
  5204.2  336.54  5209.5  335.14  5212.7  337.03  5218.6  337.03  5224.8  339.09
  5245.6  338.34  5267.9  339.25  5295.2  337.84  5388.0  338.82  5685.0  356.76
#Mann=7,-1,0
  4411.5    0.05       0  4434.0     0.1       0  4482.2    0.05       0
  4845.5    0.16       0  4998.5    0.07       0  5004.5    0.16       0
  5267.9    0.12       0
Bank Sta=4998.5,5004.5
Exp/Cntr=0.3,0.1

Type RM Length L Ch R = 1,9259,1632,1632,1632
BEGIN DESCRIPTION:
LONG HOLLOW CREEK 13.0
END DESCRIPTION:
XS GIS Cut Line= 4
      3556632.98     10455636.51      3556031.86     10456007.60
      3555916.84     10456341.80      3555616.18     10456653.28
#Sta/Elev= 30
  4181.6  363.35  4237.2  360.92  4316.4  361.14  4505.6  355.33  4621.5  348.17
  4636.9  348.82  4694.8  346.68  4737.4  343.75  4752.8  343.72  4810.7  338.98
  4842.5  338.23  4905.4  337.56  4945.2  339.69  4976.9  339.18  4987.5  336.52
  4993.8  332.64  4996.1  332.44  4998.8  331.94  5002.1  332.44  5008.7  335.95
  5025.0  340.09  5056.3  338.28  5167.3  337.60  5181.2  334.46  5201.1  337.52
  5294.3  336.97  5393.3  343.74  5492.1  352.52  5584.2  356.07  5674.4  357.24
#Mann=5,-1,0
  4181.6    0.05       0  4842.5    0.16       0  4996.1    0.07       0
  5002.1    0.16       0  5201.1    0.12       0
Bank Sta=4996.1,5002.1
Exp/Cntr=0.3,0.1

Type RM Length L Ch R = 1,7627,1367,1367,1367
BEGIN DESCRIPTION:
LONG HOLLOW CREEK 11.0
END DESCRIPTION:
XS GIS Cut Line= 2
      3555521.41     10454718.70      3554716.47     10456064.90
#Sta/Elev= 30
  4105.6  367.18  4133.1  366.47  4194.2  363.53  4289.5  355.65  4305.1  352.80
  4347.9  347.28  4353.7  345.75  4406.2  340.13  4493.5  337.31  4522.9  335.01
  4599.6  333.30  4774.2  333.59  4801.0  333.81  4857.5  333.41  4974.2  334.58
  4995.6  333.11  5006.3  329.72  5008.2  329.58  5010.9  329.08  5014.2  329.58
  5026.7  334.71  5032.6  334.99  5085.1  332.80  5201.8  334.54  5250.9  336.68
  5263.6  336.17  5303.0  336.19  5413.8  340.58  5557.8  348.38  5674.1  349.72
#Mann=9,-1,0
  4105.6    0.12       0  4133.1    0.05       0  4599.6     0.1       0
  4774.2    0.05       0  4801.0    0.16       0  5006.3    0.12       0
  5008.2    0.07       0  5014.2    0.12       0  5263.6    0.16       0
Bank Sta=5008.2,5014.2
Exp/Cntr=0.3,0.1

Type RM Length L Ch R = 1,6260,32,32,32
BEGIN DESCRIPTION:
LONG HOLLOW CREEK 10.0
END DESCRIPTION:
XS GIS Cut Line= 3
      3555033.89     10453831.92      3553925.06     10455151.94
      3553563.07     10455662.38
#Sta/Elev= 30
  3229.5  382.46  3486.3  362.13  3535.7  360.98  3550.0  358.66  3741.3  347.12
  3862.2  336.36  3897.4  337.65  3940.3  333.01  3954.6  334.54  3974.1  333.62
  4076.3  330.58  4210.8  328.70  4324.4  327.79  4463.7  327.71  4494.7  328.07
  4738.0  328.20  4827.4  328.70  4856.0  330.48  4898.5  329.83  4984.1  331.50
  4998.9  329.02  5024.9  330.99  5174.2  327.24  5177.0  326.74  5180.2  327.24
  5217.9  327.91  5248.6  329.07  5512.2  347.29  5567.7  346.71  5579.2  345.90
#Mann=15,-1,0
  3229.5    0.16       0  3974.1    0.08       0  4076.3     0.1       0
  4210.8    0.05       0  4324.4    0.12       0  4463.7    0.08       0
  4494.7    0.12       0  4738.0    0.08       0  4898.5    0.12       0
  5024.9    0.08       0  5174.2    0.07       0  5180.2    0.08       0
  5217.9    0.05       0  5512.2     0.1       0  5567.7    0.08       0
Bank Sta=5174.2,5180.2
Exp/Cntr=0.3,0.1

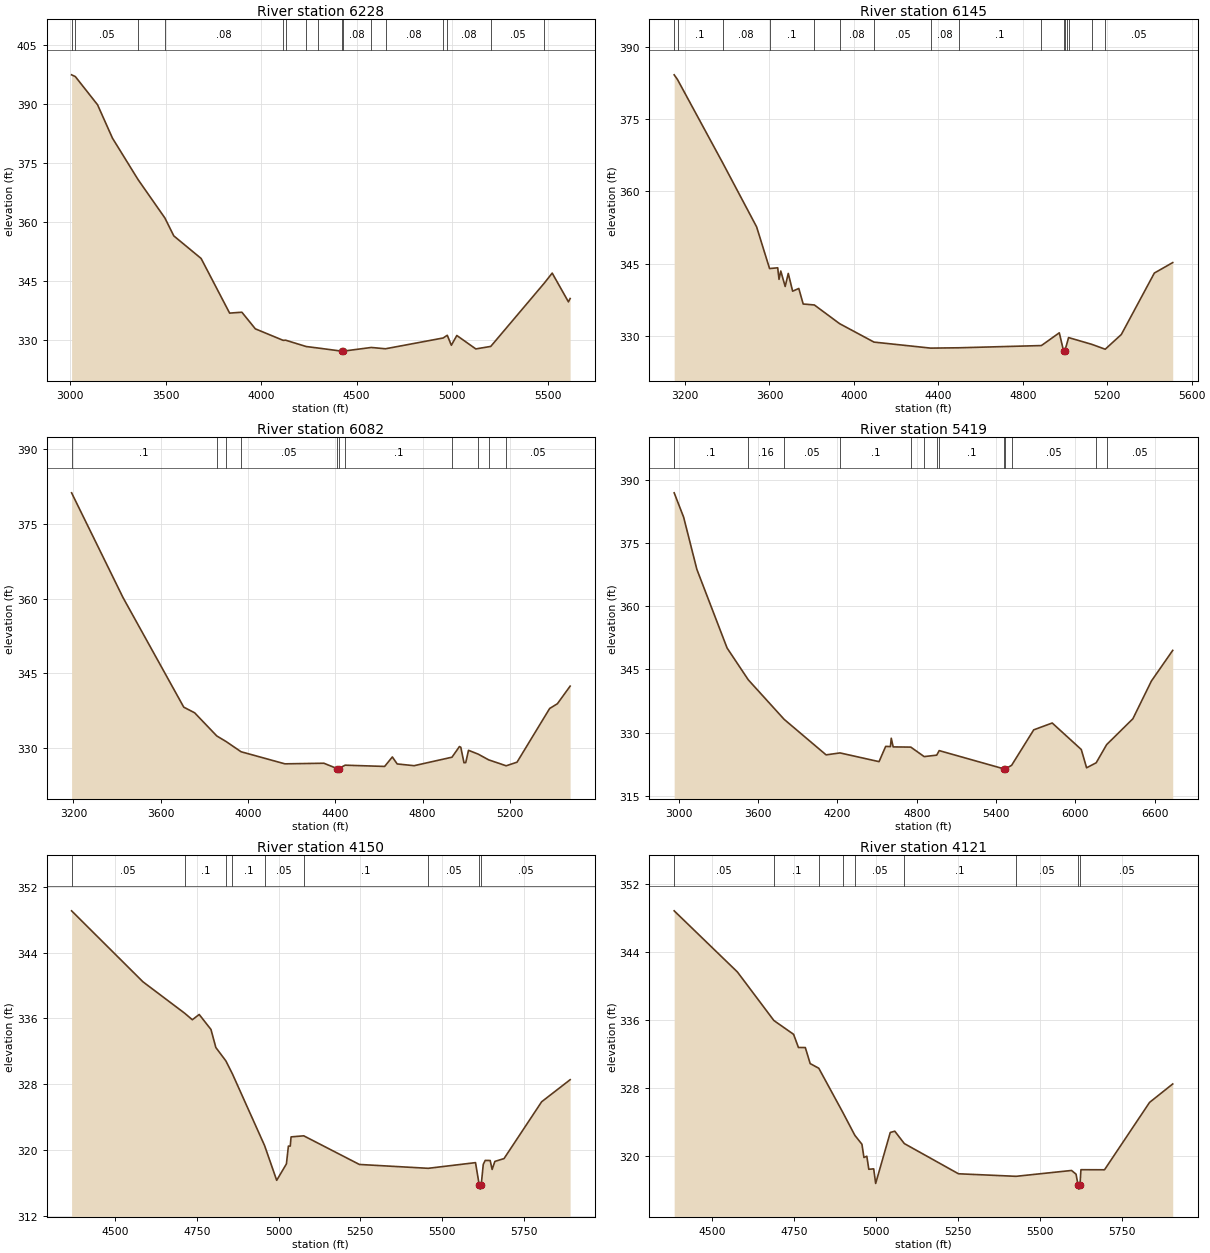
Type RM Length L Ch R = 1,6228,83,83,83
BEGIN DESCRIPTION:
LONG HOLLOW CREEK 9.0
END DESCRIPTION:
XS GIS Cut Line= 2
      3555096.07     10453604.53      3553490.20     10455661.77
#Sta/Elev= 30
  3007.6  397.43  3027.1  396.99  3143.5  389.81  3221.6  381.31  3355.4  370.78
  3496.4  360.96  3542.7  356.43  3685.6  350.69  3834.8  336.78  3899.0  337.00
  3969.6  332.77  4114.8  329.85  4128.3  329.88  4235.6  328.27  4297.5  327.89
  4422.5  327.09  4425.2  326.59  4428.5  327.09  4576.5  328.03  4650.9  327.70
  4952.4  330.44  4974.3  331.13  4995.6  328.59  5024.2  331.08  5123.7  327.66
  5201.9  328.30  5481.9  344.40  5523.5  346.96  5608.5  339.64  5617.4  340.49
#Mann=16,-1,0
  3007.6    0.16       0  3027.1    0.05       0  3355.4    0.16       0
  3496.4    0.08       0  4114.8     0.1       0  4128.3    0.08       0
  4235.6    0.05       0  4297.5    0.08       0  4422.5    0.07       0
  4428.5    0.08       0  4576.5    0.12       0  4650.9    0.08       0
  4952.4    0.12       0  4974.3    0.08       0  5201.9    0.05       0
  5481.9    0.08       0
Bank Sta=4422.5,4428.5
Exp/Cntr=0.3,0.1

Type RM Length L Ch R = 1,6145,63,63,63
BEGIN DESCRIPTION:
LONG HOLLOW CREEK 8.0
END DESCRIPTION:
XS GIS Cut Line= 3
      3554914.15     10453657.11      3553718.81     10455237.88
      3553492.26     10455542.55
#Sta/Elev= 30
  3148.8  384.20  3164.7  383.21  3377.9  365.98  3539.3  352.63  3600.7  343.97
  3639.2  344.13  3645.5  341.73  3653.8  343.46  3674.6  340.25  3689.2  342.96
  3710.0  339.27  3739.1  339.84  3759.9  336.61  3812.9  336.41  3932.4  332.53
  4095.3  328.70  4363.9  327.45  4498.2  327.52  4888.2  327.98  4973.1  330.63
  4993.0  326.91  4995.7  326.41  4999.0  326.91  5007.7  328.16  5017.0  329.64
  5127.2  328.23  5190.6  327.22  5266.9  330.28  5423.3  343.04  5510.3  345.21
#Mann=16,-1,0
  3148.8    0.05       0  3164.7     0.1       0  3377.9    0.08       0
  3600.7     0.1       0  3812.9    0.05       0  3932.4    0.08       0
  4095.3    0.05       0  4363.9    0.08       0  4498.2     0.1       0
  4888.2    0.12       0  4993.0    0.07       0  4999.0    0.12       0
  5007.7    0.08       0  5017.0    0.05       0  5127.2    0.08       0
  5190.6    0.05       0
Bank Sta=4993,4999
Exp/Cntr=0.3,0.1

Type RM Length L Ch R = 1,6082,663,663,663
BEGIN DESCRIPTION:
LONG HOLLOW CREEK 7.0
END DESCRIPTION:
XS GIS Cut Line= 2
      3554846.41     10453654.55      3553460.99     10455472.27
#Sta/Elev= 30
  3191.3  381.17  3427.0  360.20  3705.5  338.25  3755.4  337.12  3857.0  332.48
  3899.5  331.37  3968.3  329.32  4169.1  326.90  4347.8  327.02  4409.2  325.94
  4412.0  325.44  4415.2  325.94  4445.4  326.63  4626.3  326.38  4661.7  328.28
  4683.9  326.88  4761.5  326.53  4935.2  328.23  4969.3  330.36  4975.6  330.22
  4990.1  327.13  4998.2  327.14  5010.9  329.61  5055.0  328.85  5103.2  327.70
  5183.6  326.51  5233.3  327.23  5383.0  337.99  5418.3  338.93  5476.8  342.46
#Mann=11,-1,0
  3191.3     0.1       0  3857.0    0.05       0  3899.5     0.1       0
  3968.3    0.05       0  4409.2    0.07       0  4415.2    0.05       0
  4445.4     0.1       0  4935.2    0.12       0  5055.0    0.05       0
  5103.2     0.1       0  5183.6    0.05       0
Bank Sta=4409.2,4415.2
Exp/Cntr=0.3,0.1

Type RM Length L Ch R = 1,5419,1269,1269,1269
BEGIN DESCRIPTION:
LONG HOLLOW CREEK 6.0
END DESCRIPTION:
XS GIS Cut Line= 4
      3554736.20     10453454.87      3553329.92     10454522.60
      3552765.69     10455408.02      3552739.64     10456362.85
#Sta/Elev= 30
  2965.0  386.91  3036.6  381.13  3136.5  368.76  3365.2  350.08  3525.6  342.53
  3796.8  333.15  4114.0  324.72  4219.5  325.18  4514.5  323.11  4564.7  326.73
  4600.6  326.68  4606.9  328.67  4621.4  326.61  4754.7  326.56  4855.9  324.31
  4950.8  324.65  4969.4  325.73  5463.2  321.36  5465.9  320.86  5469.2  321.36
  5517.5  322.25  5684.5  330.66  5824.3  332.28  6044.3  325.99  6084.3  321.65
  6156.9  322.84  6236.0  327.15  6434.5  333.29  6574.5  342.24  6735.8  349.52
#Mann=13,-1,0
  2965.0     0.1       0  3525.6    0.16       0  3796.8    0.05       0
  4219.5     0.1       0  4754.7    0.05       0  4855.9     0.1       0
  4950.8    0.12       0  4969.4     0.1       0  5463.2    0.07       0
  5469.2     0.1       0  5517.5    0.05       0  6156.9     0.1       0
  6236.0    0.05       0
Bank Sta=5463.2,5469.2
Exp/Cntr=0.3,0.1

Type RM Length L Ch R = 1,4150,29,29,29
BEGIN DESCRIPTION:
LONG HOLLOW CREEK 1.02
END DESCRIPTION:
XS GIS Cut Line= 3
      3552743.18     10453630.03      3552187.63     10454003.28
      3551727.55     10454725.96
#Sta/Elev= 30
  4366.1  349.08  4584.3  340.46  4712.3  336.63  4735.7  335.84  4756.7  336.48
  4792.7  334.66  4807.7  332.46  4838.3  330.84  4858.5  329.25  4956.9  320.54
  4993.9  316.32  5023.7  318.32  5029.7  320.48  5035.4  320.48  5037.9  321.60
  5076.7  321.73  5247.0  318.25  5457.6  317.78  5602.5  318.47  5613.9  315.75
  5616.7  315.25  5619.9  315.75  5626.2  318.26  5632.2  318.74  5647.4  318.73
  5653.3  317.64  5661.7  318.62  5689.7  318.96  5804.9  325.87  5892.1  328.55
#Mann=9,-1,0
  4366.1    0.05       0  4712.3     0.1       0  4838.3    0.05       0
  4858.5     0.1       0  4956.9    0.05       0  5076.7     0.1       0
  5457.6    0.05       0  5613.9    0.03       0  5619.9    0.05       0
Bank Sta=5613.9,5619.9
Exp/Cntr=0.3,0.1

Type RM Length L Ch R = 1,4121,69,69,69
BEGIN DESCRIPTION:
LONG HOLLOW CREEK 1.01
END DESCRIPTION:
XS GIS Cut Line= 4
      3552713.46     10453618.52      3552550.70     10453718.35
      3552162.24     10453987.44      3551678.43     10454696.89
#Sta/Elev= 30
  4384.1  348.85  4577.2  341.64  4688.5  335.92  4748.7  334.29  4763.5  332.74
  4784.5  332.73  4799.4  330.84  4825.7  330.29  4898.7  325.11  4935.8  322.38
  4957.4  321.33  4963.5  319.77  4972.3  319.92  4978.4  318.38  4993.3  318.43
  4999.3  316.71  5043.9  322.72  5057.7  322.87  5086.8  321.41  5252.2  317.85
  5427.9  317.55  5597.4  318.24  5611.2  317.80  5617.1  316.54  5619.8  316.04
  5623.1  316.54  5626.1  318.33  5698.0  318.32  5835.5  326.26  5906.3  328.44
#Mann=9,-1,0
  4384.1    0.05       0  4688.5     0.1       0  4825.7    0.05       0
  4898.7     0.1       0  4935.8    0.05       0  5086.8     0.1       0
  5427.9    0.05       0  5617.1    0.03       0  5623.1    0.05       0
Bank Sta=5617.1,5623.1
Exp/Cntr=0.3,0.1

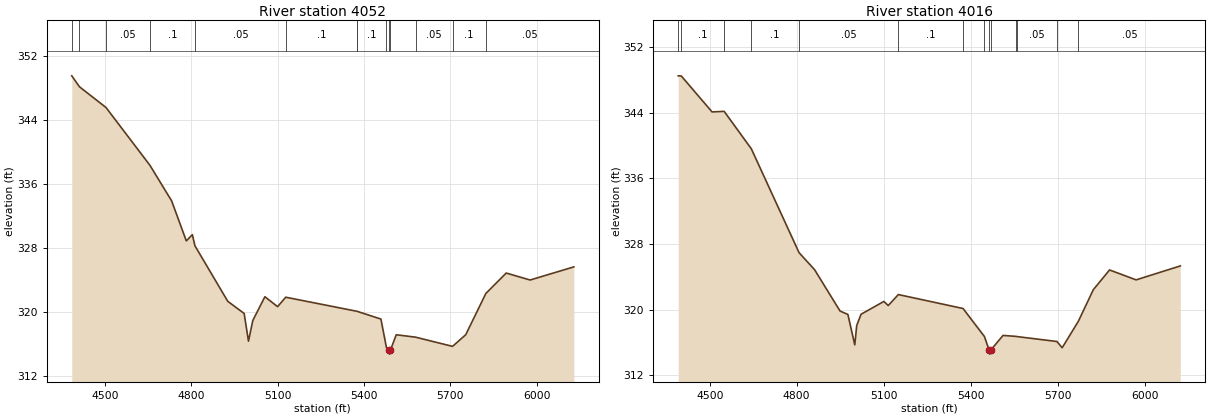
Type RM Length L Ch R = 1,4052,36,36,36
BEGIN DESCRIPTION:
LONG HOLLOW CREEK 1.0
END DESCRIPTION:
XS GIS Cut Line= 4
      3552685.84     10453553.84      3551914.99     10454071.21
      3551328.19     10454178.85      3551112.95     10454220.51
#Sta/Elev= 30
  4384.7  349.47  4411.5  348.10  4503.7  345.51  4656.1  338.30  4731.6  333.85
  4782.6  328.85  4803.6  329.62  4812.7  328.23  4926.6  321.30  4983.6  319.78
  4998.6  316.32  5013.6  318.90  5055.6  321.87  5099.8  320.63  5128.0  321.81
  5375.7  320.05  5376.6  320.04  5458.7  319.08  5477.8  315.54  5485.8  315.20
  5488.6  314.70  5491.8  315.20  5511.9  317.12  5579.0  316.82  5707.5  315.67
  5753.2  317.12  5823.3  322.28  5893.9  324.83  5977.0  323.96  6128.9  325.60
#Mann=14,-1,0
  4384.7    0.05       0  4411.5     0.1       0  4503.7    0.05       0
  4656.1     0.1       0  4812.7    0.05       0  5128.0     0.1       0
  5375.7    0.05       0  5376.6     0.1       0  5477.8    0.16       0
  5485.8    0.03       0  5491.8    0.16       0  5579.0    0.05       0
  5707.5     0.1       0  5823.3    0.05       0
Bank Sta=5485.8,5491.8
Exp/Cntr=0.3,0.1

Type RM Length L Ch R = 1,4016,0,0,0
BEGIN DESCRIPTION:
LONG HOLLOW CREEK 1.03
END DESCRIPTION:
XS GIS Cut Line= 3
      3552673.71     10453532.39      3551914.20     10454022.82
      3551102.54     10454185.58
#Sta/Elev= 30
  4391.5  348.51  4402.1  348.49  4508.2  344.11  4549.9  344.18  4643.6  339.62
  4808.4  326.95  4861.9  324.88  4949.7  319.84  4976.7  319.43  5000.5  315.72
  5007.1  318.07  5022.2  319.45  5100.8  321.01  5115.9  320.51  5150.8  321.85
  5374.0  320.15  5447.8  316.73  5463.8  315.09  5466.6  314.59  5469.8  315.09
  5511.9  316.87  5557.1  316.75  5559.8  316.73  5697.7  316.13  5715.9  315.37
  5771.7  318.59  5823.3  322.44  5879.3  324.85  5970.9  323.64  6123.4  325.34
#Mann=14,-1,0
  4391.5    0.05       0  4402.1     0.1       0  4549.9    0.05       0
  4643.6     0.1       0  4808.4    0.05       0  5150.8     0.1       0
  5374.0    0.05       0  5447.8     0.1       0  5463.8    0.03       0
  5469.8     0.1       0  5557.1    0.16       0  5559.8    0.05       0
  5697.7     0.1       0  5771.7    0.05       0
Bank Sta=5463.8,5469.8
Exp/Cntr=0.3,0.1

Chan Stop Cuts=-1