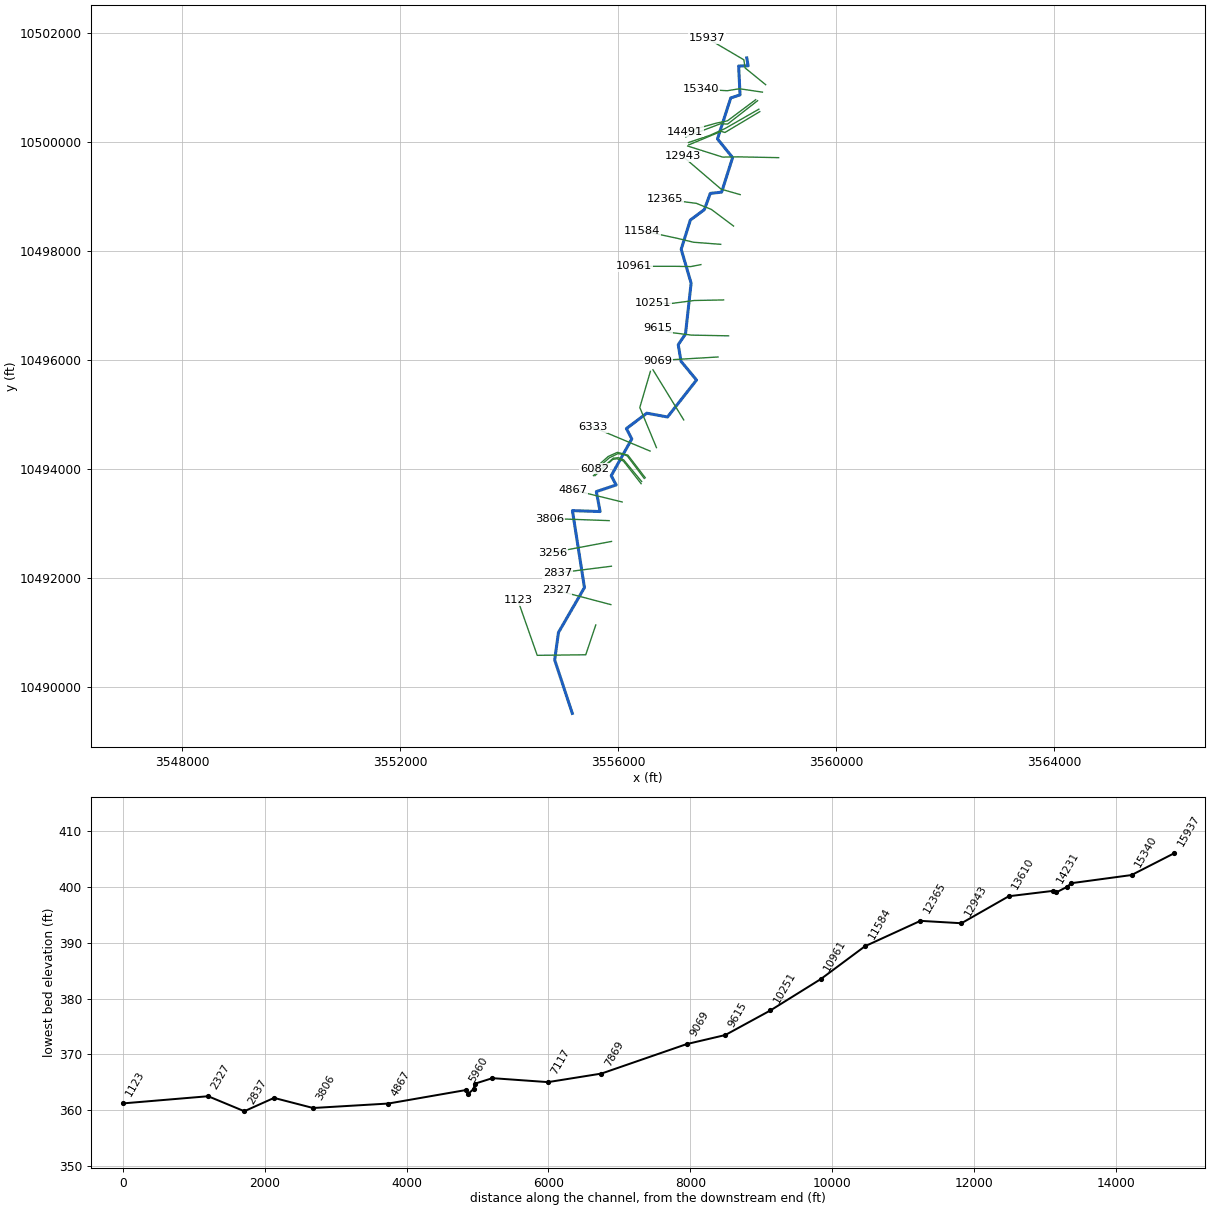
--- LIES BRANCH.prj (project) ---

Proj Title=LIES BRANCH Base Level Engineering
Current Plan=p01
Default Exp/Contr=0.3,0.1
English Units
Geom File=g01
Flow File=f01
Plan File=p01
BEGIN DESCRIPTION:
LIES BRANCH
END DESCRIPTION:

--- LIES BRANCH.p01 (plan) ---

Plan Title=Multiple Run
Short Identifier=Multiple
Geom File=g01
Flow File=f01
Subcritical Flow
K Sum by GR= 0
Std Step Tol= 0.01
Critical Tol= 0.01
Num of Std Step Trials= 20
Max Error Tol= 0.3
Flow Tol Ratio= 0.001
Split Flow NTrial= 30
Split Flow Tol= 0.02
Split Flow Ratio= 0.02
Log Output Level= 0
Friction Slope Method= 1
Unsteady Friction Slope Method= 2
Unsteady Bridges Friction Slope Method= 1
Parabolic Critical Depth
Global Vel Dist=  1 , 1 , 1
Global Log Level= 0
CheckData=True
Encroach Param= -1, 0, 0, 0
BEGIN DESCRIPTION:
Multiple Run
END DESCRIPTION:

--- LIES BRANCH.f01 (steady flow) ---

Flow Title=Multiple
Number of Profiles=7
Profile Names=10-year,25-year,50-year,1pct_min,100-year,1pct_plu,500-year
River Rch & RM= LIES BRANCH,Reach-1,15937
    1322    1840    2270    2042    2761    3734    4074
River Rch & RM= LIES BRANCH,Reach-1,6333
    1763    2475    3073    2775    3753    5076    5590
Boundary for River Rch & Prof#=LIES BRANCH,Reach-1,1
Up Type=0
Dn Type=3
Dn Slope=0.005
Boundary for River Rch & Prof#=LIES BRANCH,Reach-1,2
Up Type=0
Dn Type=3
Dn Slope=0.005
Boundary for River Rch & Prof#=LIES BRANCH,Reach-1,3
Up Type=0
Dn Type=3
Dn Slope=0.005
Boundary for River Rch & Prof#=LIES BRANCH,Reach-1,4
Up Type=0
Dn Type=3
Dn Slope=0.005
Boundary for River Rch & Prof#=LIES BRANCH,Reach-1,5
Up Type=0
Dn Type=3
Dn Slope=0.005
Boundary for River Rch & Prof#=LIES BRANCH,Reach-1,6
Up Type=0
Dn Type=3
Dn Slope=0.005
Boundary for River Rch & Prof#=LIES BRANCH,Reach-1,7
Up Type=0
Dn Type=3
Dn Slope=0.005

--- LIES BRANCH.g01 (geometry) ---

Geom Title=Existing Conditions

River Reach=LIES BRANCH,Reach-1
Reach XY= 30
      3558362.11     10501551.64      3558386.87     10501406.36
      3558212.95     10501402.45      3558238.95     10500873.20
      3558068.07     10500815.98      3557825.01     10500064.24
      3558102.30     10499721.53      3557900.75     10499086.99
      3557692.94     10499063.98      3557584.29     10498767.04
      3557327.02     10498574.58      3557159.05     10498038.06
      3557341.01     10497416.61      3557237.60     10496482.07
      3557104.95     10496287.57      3557155.25     10495982.92
      3557440.08     10495637.53      3556908.62     10494959.32
      3556527.96     10495029.25      3556153.74     10494746.20
      3556252.68     10494556.91      3555875.47     10493881.38
      3555966.09     10493711.59      3555602.03     10493589.72
      3555671.82     10493223.57      3555163.80     10493240.54
      3555384.35     10491827.58      3554907.57     10491003.12
      3554838.13     10490499.65      3555161.50     10489518.27

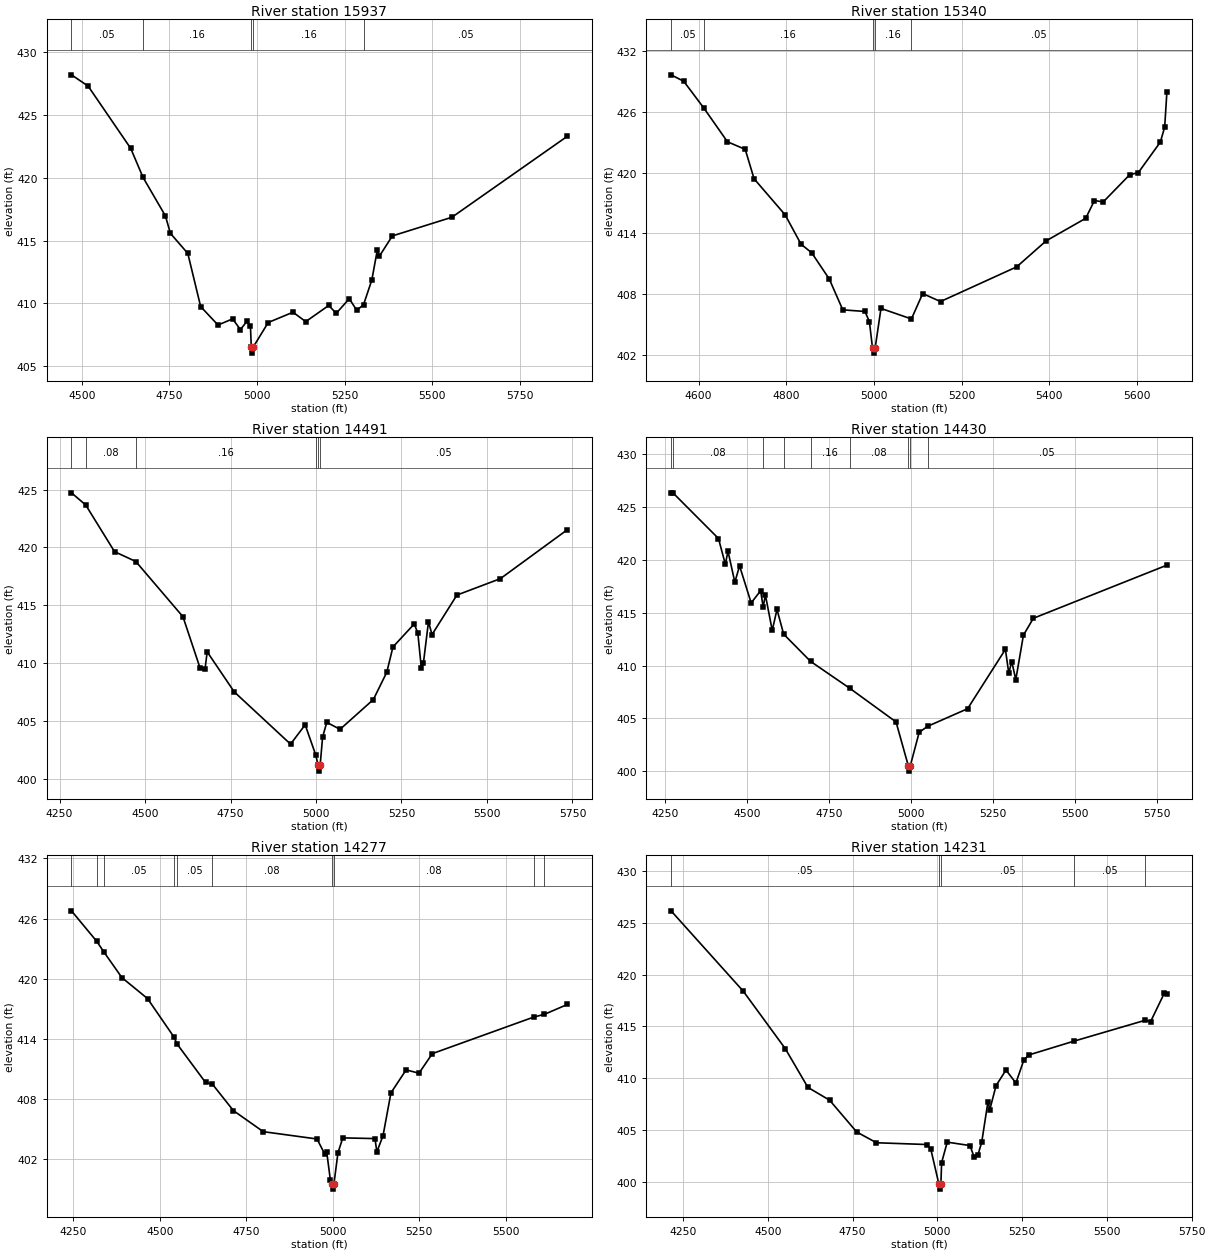
Type RM Length L Ch R = 1,15937,597,597,597
BEGIN DESCRIPTION:
LIES BRANCH 32.0
END DESCRIPTION:
XS GIS Cut Line= 4
      3558708.31     10501060.07      3558331.60     10501367.34
      3558309.03     10501516.65      3557638.86     10501910.76
#Sta/Elev= 30
  4470.6  428.21  4518.2  427.31  4639.6  422.35  4674.9  420.03  4738.6  416.97
  4753.0  415.57  4802.5  413.98  4839.2  409.74  4888.7  408.27  4930.4  408.76
  4952.6  407.91  4971.2  408.56  4981.3  408.16  4983.6  406.53  4986.3  406.03
  4989.6  406.53  5031.9  408.47  5102.7  409.29  5139.0  408.54  5204.6  409.83
  5226.0  409.20  5263.2  410.37  5284.6  409.44  5303.9  409.89  5327.6  411.86
  5343.2  414.25  5349.0  413.75  5386.1  415.37  5556.1  416.86  5885.2  423.31
#Mann=5,-1,0
  4470.6    0.05       0  4674.9    0.16       0  4983.6    0.07       0
  4989.6    0.16       0  5303.9    0.05       0
Bank Sta=4983.6,4989.6
Exp/Cntr=0.3,0.1

Type RM Length L Ch R = 1,15340,849,849,849
BEGIN DESCRIPTION:
LIES BRANCH 31.0
END DESCRIPTION:
XS GIS Cut Line= 4
      3558649.32     10500922.90      3558229.17     10500985.40
      3558003.47     10500948.94      3557527.28     10500976.65
#Sta/Elev= 30
  4537.4  429.67  4566.4  429.03  4612.4  426.37  4666.0  423.05  4706.5  422.30
  4726.7  419.39  4797.4  415.83  4833.8  412.92  4858.1  412.07  4898.1  409.48
  4928.9  406.43  4979.5  406.27  4989.6  405.26  4996.7  402.65  4999.5  402.15
  5002.7  402.65  5016.0  406.57  5085.4  405.53  5111.1  408.04  5151.7  407.25
  5325.4  410.68  5392.5  413.25  5482.7  415.48  5502.7  417.24  5522.7  417.10
  5582.8  419.78  5602.9  420.01  5652.9  423.02  5662.8  424.50  5667.8  427.95
#Mann=5,-1,0
  4537.4    0.05       0  4612.4    0.16       0  4996.7    0.07       0
  5002.7    0.16       0  5085.4    0.05       0
Bank Sta=4996.7,5002.7
Exp/Cntr=0.3,0.1

Type RM Length L Ch R = 1,14491,61,61,61
BEGIN DESCRIPTION:
LIES BRANCH 29.3
END DESCRIPTION:
XS GIS Cut Line= 4
      3558525.57     10500783.99      3558007.38     10500395.99
      3557804.80     10500354.39      3557231.37     10500192.88
#Sta/Elev= 30
  4284.9  424.72  4326.6  423.67  4410.9  419.64  4473.1  418.79  4611.0  414.02
  4661.0  409.59  4675.6  409.53  4681.8  410.99  4761.0  407.53  4925.6  403.02
  4968.3  404.69  4999.4  402.07  5006.1  401.19  5008.8  400.69  5012.1  401.19
  5019.3  403.63  5031.5  404.90  5070.3  404.30  5167.7  406.87  5207.0  409.23
  5225.0  411.41  5287.3  413.40  5297.7  412.62  5308.1  409.57  5314.2  410.05
  5328.9  413.59  5339.3  412.48  5412.0  415.89  5539.2  417.31  5734.8  421.53
#Mann=6,-1,0
  4284.9    0.05       0  4326.6    0.08       0  4473.1    0.16       0
  4999.4    0.05       0  5006.1    0.03       0  5012.1    0.05       0
Bank Sta=5006.1,5012.1
Exp/Cntr=0.3,0.1

Type RM Length L Ch R = 1,14430,153,153,153
BEGIN DESCRIPTION:
LIES BRANCH 29.2
END DESCRIPTION:
XS GIS Cut Line= 4
      3558560.76     10500765.78      3558011.29     10500337.40
      3557879.24     10500342.18      3557241.71     10500100.40
#Sta/Elev= 30
  4269.4  426.33  4276.4  426.29  4413.9  422.01  4434.8  419.58  4442.9  420.82
  4463.7  417.88  4478.2  419.42  4513.5  415.92  4542.4  417.08  4550.0  415.53
  4556.9  416.67  4577.7  413.32  4592.2  415.30  4612.5  412.97  4694.3  410.40
  4814.0  407.85  4954.9  404.67  4992.3  400.52  4995.1  400.02  4998.3  400.52
  5025.4  403.69  5051.3  404.26  5172.9  405.92  5288.1  411.53  5298.4  409.28
  5307.5  410.38  5319.8  408.66  5343.0  412.87  5373.3  414.47  5780.1  419.49
#Mann=9,-1,0
  4269.4    0.05       0  4276.4    0.08       0  4550.0    0.16       0
  4612.5    0.08       0  4694.3    0.16       0  4814.0    0.08       0
  4992.3    0.07       0  4998.3    0.08       0  5051.3    0.05       0
Bank Sta=4992.3,4998.3
Exp/Cntr=0.3,0.1

Type RM Length L Ch R = 1,14277,46,46,46
BEGIN DESCRIPTION:
LIES BRANCH 29.0
END DESCRIPTION:
XS GIS Cut Line= 4
      3558582.90     10500609.53      3557959.90     10500252.60
      3557681.86     10500129.06      3557292.52     10499997.55
#Sta/Elev= 30
  4244.8  426.78  4317.8  423.74  4338.1  422.70  4390.6  420.12  4464.7  418.03
  4540.6  414.22  4550.1  413.50  4632.3  409.67  4652.1  409.50  4712.9  406.86
  4799.2  404.76  4954.6  404.03  4977.1  402.52  4982.6  402.74  4993.2  399.94
  4997.4  399.53  5000.1  399.03  5003.4  399.53  5015.1  402.65  5029.1  404.14
  5122.1  404.07  5127.6  402.74  5145.4  404.36  5168.3  408.63  5212.1  410.92
  5249.4  410.59  5287.9  412.54  5581.3  416.19  5612.0  416.46  5678.0  417.44
#Mann=10,-1,0
  4244.8    0.05       0  4317.8    0.08       0  4338.1    0.05       0
  4540.6    0.08       0  4550.1    0.05       0  4652.1    0.08       0
  4997.4    0.07       0  5003.4    0.08       0  5581.3    0.05       0
  5612.0    0.08       0
Bank Sta=4997.4,5003.4
Exp/Cntr=0.3,0.1

Type RM Length L Ch R = 1,14231,621,621,621
BEGIN DESCRIPTION:
LIES BRANCH 29.1
END DESCRIPTION:
XS GIS Cut Line= 4
      3558601.12     10500565.26      3557961.81     10500182.45
      3557894.10     10500203.28      3557297.78     10499954.60
#Sta/Elev= 30
  4214.8  426.14  4427.8  418.39  4551.7  412.85  4618.3  409.12  4682.5  407.88
  4762.2  404.82  4820.6  403.78  4969.5  403.61  4980.6  403.19  5004.5  399.81
  5007.2  399.31  5010.5  399.81  5012.7  401.87  5029.2  403.84  5096.3  403.51
  5108.8  402.38  5119.6  402.60  5130.9  403.83  5149.3  407.74  5154.8  406.98
  5173.2  409.29  5202.4  410.79  5231.7  409.54  5255.5  411.79  5271.3  412.26
  5402.3  413.57  5613.1  415.59  5628.9  415.46  5669.2  418.19  5676.9  418.09
#Mann=5,-1,0
  4214.8    0.05       0  5004.5    0.03       0  5010.5    0.05       0
  5402.3    0.05       0  5613.1    0.08       0
Bank Sta=5004.5,5010.5
Exp/Cntr=0.3,0.1

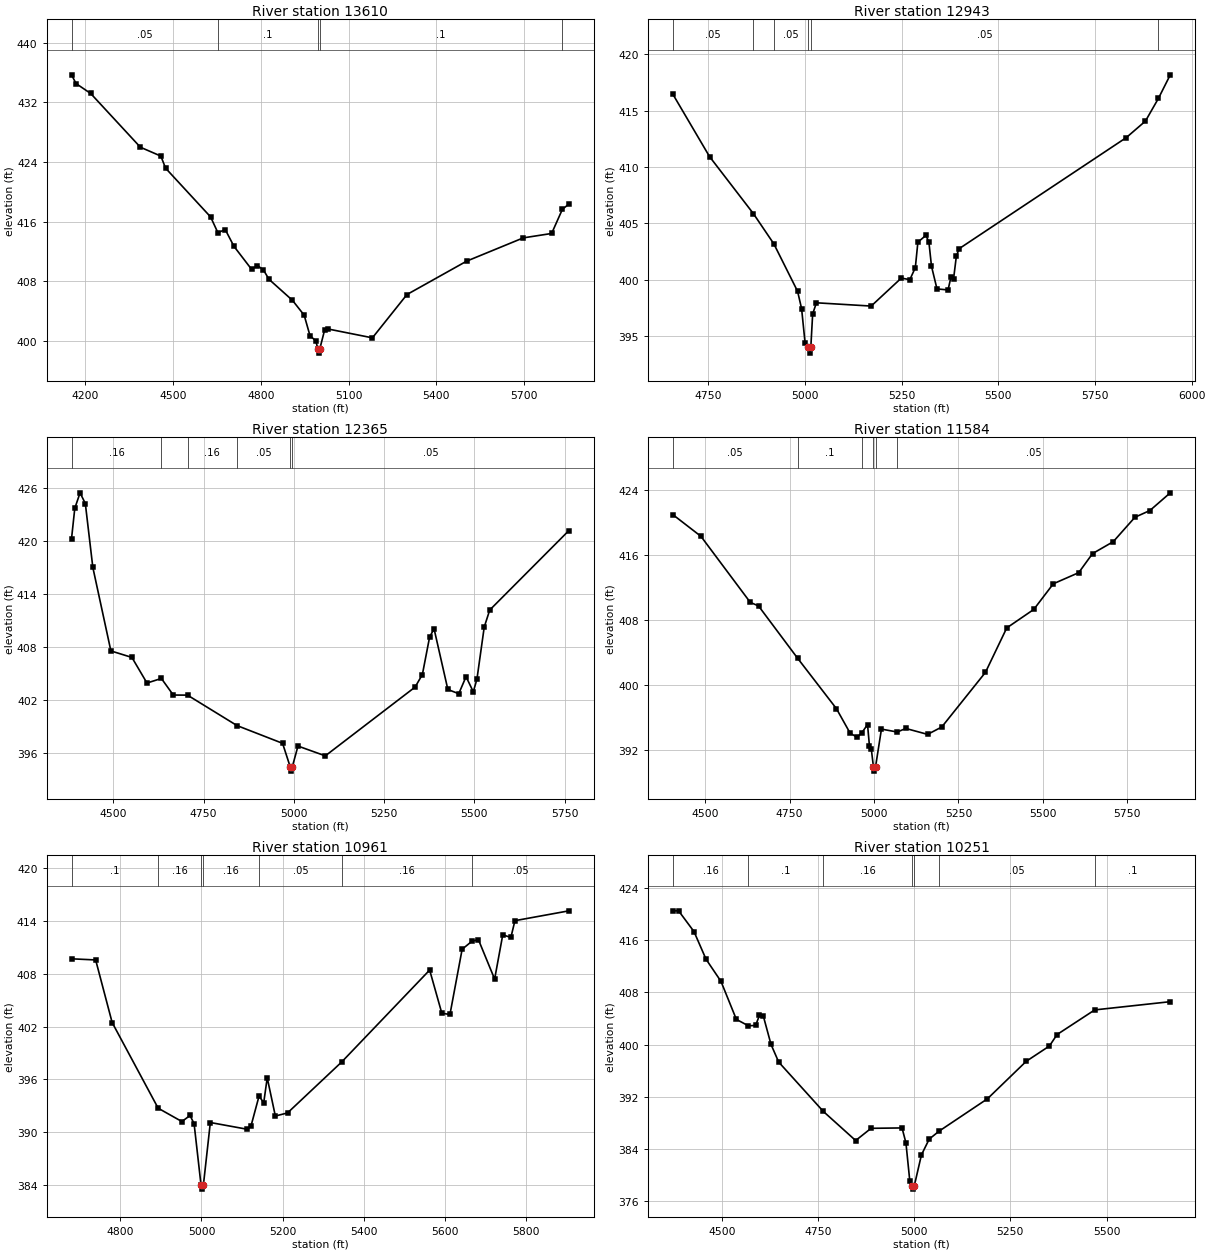
Type RM Length L Ch R = 1,13610,667,667,667
BEGIN DESCRIPTION:
LIES BRANCH 28.0
END DESCRIPTION:
XS GIS Cut Line= 4
      3558947.47     10499720.21      3558200.84     10499735.09
      3557918.84     10499730.63      3557278.19     10499933.76
#Sta/Elev= 30
  4152.7  435.68  4168.1  434.51  4218.1  433.18  4388.1  425.97  4458.1  424.78
  4474.3  423.16  4628.2  416.62  4653.2  414.50  4678.2  414.93  4708.2  412.67
  4768.2  409.60  4788.2  410.09  4808.2  409.55  4828.2  408.24  4908.2  405.43
  4948.2  403.44  4968.2  400.68  4988.2  399.99  4995.2  398.85  4998.0  398.35
  5001.2  398.85  5018.2  401.46  5028.2  401.60  5181.5  400.40  5299.7  406.21
  5503.9  410.69  5697.5  413.81  5794.4  414.40  5831.4  417.66  5853.6  418.34
#Mann=5,-1,0
  4152.7    0.05       0  4653.2     0.1       0  4995.2    0.03       0
  5001.2     0.1       0  5831.4    0.08       0
Bank Sta=4995.2,5001.2
Exp/Cntr=0.3,0.1

Type RM Length L Ch R = 1,12943,578,578,578
BEGIN DESCRIPTION:
LIES BRANCH 26.0
END DESCRIPTION:
XS GIS Cut Line= 3
      3558242.08     10499041.65      3557892.11     10499141.64
      3557192.13     10499741.62
#Sta/Elev= 30
  4658.8  416.45  4753.7  410.92  4867.2  405.86  4919.9  403.19  4981.2  398.99
  4991.6  397.45  5000.7  394.38  5009.4  394.01  5012.1  393.51  5015.4  394.01
  5020.2  396.98  5029.9  397.97  5171.5  397.68  5249.4  400.16  5271.4  400.02
  5285.6  401.08  5292.2  403.34  5313.1  403.95  5320.8  403.32  5327.4  401.21
  5341.6  399.20  5370.2  399.11  5377.8  400.26  5384.4  400.07  5391.6  402.08
  5398.7  402.76  5831.1  412.61  5880.5  414.07  5914.2  416.09  5944.7  418.17
#Mann=6,-1,0
  4658.8    0.05       0  4867.2     0.1       0  4919.9    0.05       0
  5009.4    0.03       0  5015.4    0.05       0  5914.2     0.1       0
Bank Sta=5009.4,5015.4
Exp/Cntr=0.3,0.1

Type RM Length L Ch R = 1,12365,781,781,781
BEGIN DESCRIPTION:
LIES BRANCH 24.0
END DESCRIPTION:
XS GIS Cut Line= 4
      3558119.34     10498465.01      3557713.11     10498769.69
      3557437.07     10498881.67      3556869.31     10498954.59
#Sta/Elev= 30
  4384.1  420.28  4393.1  423.71  4407.7  425.47  4422.3  424.26  4443.1  417.02
  4493.1  407.56  4551.4  406.82  4593.1  403.92  4633.0  404.44  4666.0  402.56
  4705.4  402.55  4842.6  399.10  4968.8  397.09  4989.8  394.44  4992.6  393.94
  4995.8  394.44  5011.5  396.78  5087.2  395.67  5335.9  403.46  5356.1  404.88
  5376.3  409.16  5388.6  410.05  5426.7  403.19  5456.9  402.71  5477.1  404.64
  5497.2  402.93  5507.3  404.36  5527.5  410.26  5542.7  412.19  5762.2  421.20
#Mann=6,-1,0
  4384.1    0.16       0  4633.0    0.05       0  4705.4    0.16       0
  4842.6    0.05       0  4989.8    0.03       0  4995.8    0.05       0
Bank Sta=4989.8,4995.8
Exp/Cntr=0.3,0.1

Type RM Length L Ch R = 1,11584,623,623,623
BEGIN DESCRIPTION:
LIES BRANCH 23.0
END DESCRIPTION:
XS GIS Cut Line= 4
      3557884.95     10498129.07      3557384.92     10498167.39
      3557103.73     10498235.83      3556437.04     10498379.07
#Sta/Elev= 30
  4404.5  421.00  4487.6  418.33  4633.7  410.19  4658.1  409.75  4774.1  403.29
  4888.8  397.09  4929.5  394.06  4950.2  393.57  4963.9  394.11  4980.9  395.13
  4986.7  392.43  4991.9  392.16  4998.5  389.89  5001.3  389.39  5004.5  389.89
  5022.1  394.57  5068.9  394.21  5094.1  394.65  5158.8  393.92  5200.7  394.83
  5330.0  401.56  5393.1  407.04  5473.2  409.32  5531.0  412.48  5606.2  413.85
  5647.1  416.20  5708.5  417.67  5772.7  420.68  5817.0  421.51  5877.3  423.69
#Mann=6,-1,0
  4404.5    0.05       0  4774.1     0.1       0  4963.9    0.16       0
  4998.5    0.07       0  5004.5    0.16       0  5068.9    0.05       0
Bank Sta=4998.5,5004.5
Exp/Cntr=0.3,0.1

Type RM Length L Ch R = 1,10961,710,710,710
BEGIN DESCRIPTION:
LIES BRANCH 21.0
END DESCRIPTION:
XS GIS Cut Line= 4
      3557520.41     10497756.67      3557332.90     10497720.21
      3557054.25     10497725.42      3556299.07     10497725.42
#Sta/Elev= 30
  4680.1  409.71  4739.5  409.58  4780.1  402.46  4893.4  392.71  4951.9  391.19
  4971.9  391.88  4981.9  390.95  4998.9  384.00  5001.7  383.50  5004.9  384.00
  5021.9  391.08  5112.0  390.32  5122.0  390.68  5141.8  394.08  5153.4  393.34
  5162.0  396.17  5182.0  391.82  5212.0  392.17  5345.6  397.98  5562.0  408.43
  5592.0  403.51  5612.0  403.38  5642.0  410.80  5665.9  411.70  5682.0  411.90
  5722.0  407.40  5742.0  412.44  5762.0  412.14  5772.0  414.05  5905.0  415.17
#Mann=7,-1,0
  4680.1     0.1       0  4893.4    0.16       0  4998.9    0.07       0
  5004.9    0.16       0  5141.8    0.05       0  5345.6    0.16       0
  5665.9    0.05       0
Bank Sta=4998.9,5004.9
Exp/Cntr=0.3,0.1

Type RM Length L Ch R = 1,10251,636,636,636
BEGIN DESCRIPTION:
LIES BRANCH 20.0
END DESCRIPTION:
XS GIS Cut Line= 4
      3557937.03     10497108.23      3557395.40     10497097.81
      3556996.96     10497045.73      3556648.03     10497043.13
#Sta/Elev= 30
  4373.0  420.49  4387.9  420.49  4427.9  417.31  4459.2  413.08  4498.0  409.69
  4538.0  403.87  4569.1  402.89  4588.0  402.94  4598.0  404.49  4608.0  404.39
  4628.0  400.04  4648.0  397.33  4764.1  389.77  4848.0  385.32  4888.0  387.19
  4968.5  387.25  4978.6  384.97  4988.7  379.10  4994.3  378.38  4997.1  377.88
  5000.3  378.38  5018.9  383.12  5039.1  385.54  5065.1  386.77  5190.4  391.71
  5291.2  397.45  5351.4  399.79  5371.4  401.55  5469.2  405.32  5665.5  406.58
#Mann=7,-1,0
  4373.0    0.16       0  4569.1     0.1       0  4764.1    0.16       0
  4994.3    0.07       0  5000.3    0.16       0  5065.1    0.05       0
  5469.2     0.1       0
Bank Sta=4994.3,5000.3
Exp/Cntr=0.3,0.1

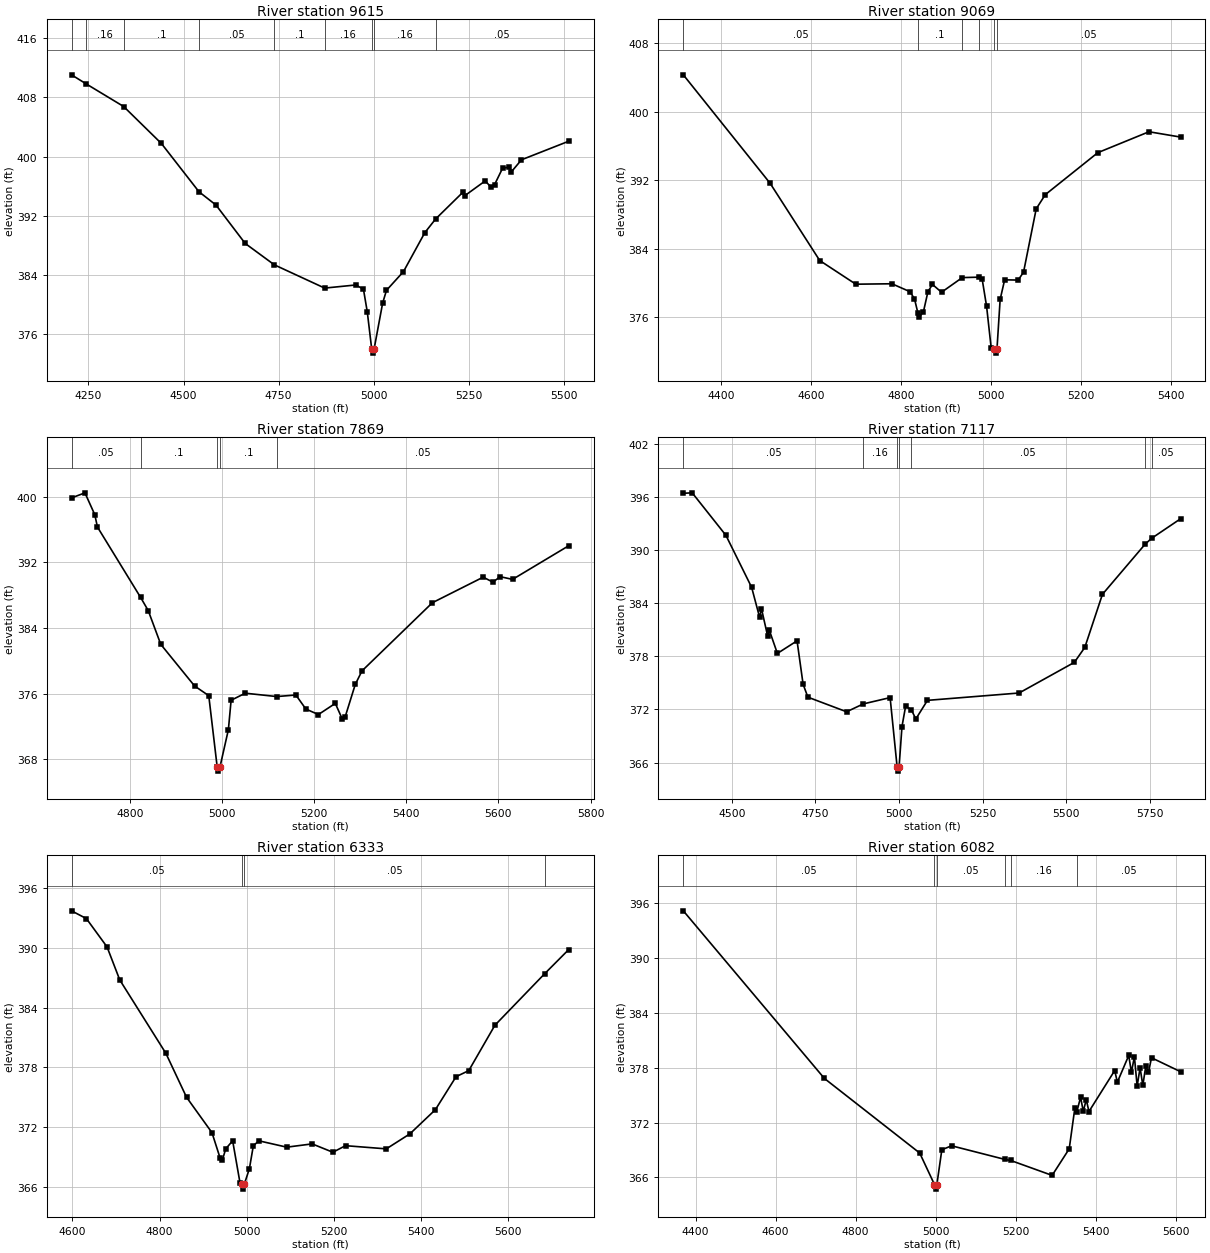
Type RM Length L Ch R = 1,9615,546,546,546
BEGIN DESCRIPTION:
LIES BRANCH 18.0
END DESCRIPTION:
XS GIS Cut Line= 4
      3558028.19     10496449.38      3557351.13     10496462.40
      3556957.90     10496511.88      3556736.80     10496584.71
#Sta/Elev= 30
  4205.8  411.04  4243.9  409.83  4342.8  406.76  4441.9  401.77  4540.7  395.25
  4585.3  393.46  4662.0  388.28  4738.6  385.39  4870.8  382.25  4952.6  382.67
  4972.7  382.10  4982.8  379.03  4994.5  373.97  4997.2  373.47  5000.5  373.97
  5023.1  380.22  5033.2  381.95  5077.9  384.48  5134.0  389.74  5162.3  391.58
  5233.6  395.17  5238.6  394.71  5292.6  396.72  5306.5  395.95  5317.0  396.20
  5338.1  398.42  5356.2  398.60  5361.4  397.95  5387.9  399.57  5512.1  402.08
#Mann=9,-1,0
  4205.8     0.1       0  4243.9    0.16       0  4342.8     0.1       0
  4540.7    0.05       0  4738.6     0.1       0  4870.8    0.16       0
  4994.5    0.07       0  5000.5    0.16       0  5162.3    0.05       0
Bank Sta=4994.5,5000.5
Exp/Cntr=0.3,0.1

Type RM Length L Ch R = 1,9069,1200,1200,1200
BEGIN DESCRIPTION:
LIES BRANCH 17.0
END DESCRIPTION:
XS GIS Cut Line= 2
      3557834.57     10496061.01      3556732.09     10495995.90
#Sta/Elev= 30
  4316.8  404.30  4509.6  391.65  4619.8  382.64  4699.9  379.88  4780.1  379.93
  4820.1  379.01  4830.2  378.18  4837.6  376.57  4840.2  376.00  4850.2  376.69
  4860.2  379.02  4870.2  379.85  4890.3  378.94  4936.4  380.65  4973.9  380.70
  4980.4  380.52  4990.4  377.30  5000.5  372.49  5007.5  372.34  5010.2  371.84
  5013.5  372.34  5020.5  378.10  5030.5  380.39  5060.6  380.36  5072.5  381.29
  5100.6  388.67  5120.7  390.32  5237.4  395.22  5351.1  397.66  5421.2  397.04
#Mann=6,-1,0
  4316.8    0.05       0  4837.6     0.1       0  4936.4    0.16       0
  4973.9    0.05       0  5007.5    0.03       0  5013.5    0.05       0
Bank Sta=5007.5,5013.5
Exp/Cntr=0.3,0.1

Type RM Length L Ch R = 1,7869,752,752,752
BEGIN DESCRIPTION:
LIES BRANCH 15.0
END DESCRIPTION:
XS GIS Cut Line= 2
      3557205.19     10494906.49      3556640.93     10495826.66
#Sta/Elev= 30
  4673.4  399.83  4702.5  400.45  4723.8  397.80  4729.7  396.28  4823.4  387.71
  4839.9  386.11  4867.1  382.00  4940.5  376.93  4971.3  375.75  4989.6  367.06
  4992.4  366.56  4995.6  367.06  5013.9  371.61  5019.8  375.19  5050.6  376.05
  5118.8  375.64  5160.4  375.83  5182.1  374.12  5209.3  373.45  5246.0  374.81
  5261.4  372.87  5267.3  373.15  5289.4  377.13  5304.0  378.77  5456.8  387.07
  5567.0  390.18  5588.3  389.57  5603.7  390.24  5630.8  389.91  5752.8  394.01
#Mann=5,-1,0
  4673.4    0.05       0  4823.4     0.1       0  4989.6    0.07       0
  4995.6     0.1       0  5118.8    0.05       0
Bank Sta=4989.6,4995.6
Exp/Cntr=0.3,0.1

Type RM Length L Ch R = 1,7117,784,784,784
BEGIN DESCRIPTION:
LIES BRANCH 13.0
END DESCRIPTION:
XS GIS Cut Line= 3
      3556705.30     10494397.28      3556399.74     10495133.40
      3556594.18     10495796.57
#Sta/Elev= 30
  4354.5  396.40  4381.1  396.45  4482.0  391.65  4559.0  385.78  4582.9  382.38
  4588.3  383.39  4606.7  380.31  4612.1  380.92  4636.0  378.32  4694.9  379.74
  4713.0  374.84  4727.3  373.38  4843.2  371.73  4893.2  372.62  4973.4  373.33
  4994.3  365.53  4997.0  365.03  5000.3  365.53  5008.9  370.06  5019.7  372.34
  5036.6  371.98  5050.4  370.92  5085.1  373.02  5359.4  373.85  5524.8  377.31
  5556.1  379.00  5608.8  384.99  5736.3  390.64  5755.8  391.31  5842.6  393.52
#Mann=7,-1,0
  4354.5    0.05       0  4893.2    0.16       0  4994.3    0.07       0
  5000.3    0.16       0  5036.6    0.05       0  5736.3    0.16       0
  5755.8    0.05       0
Bank Sta=4994.3,5000.3
Exp/Cntr=0.3,0.1

Type RM Length L Ch R = 1,6333,251,251,251
BEGIN DESCRIPTION:
LIES BRANCH 12.0
END DESCRIPTION:
XS GIS Cut Line= 2
      3556588.84     10494333.59      3555535.66     10494775.66
#Sta/Elev= 30
  4597.8  393.73  4631.9  392.95  4679.4  390.10  4708.6  386.78  4814.5  379.40
  4862.0  374.98  4920.4  371.42  4938.7  368.92  4944.1  368.64  4952.1  369.80
  4967.9  370.60  4984.7  366.40  4988.7  366.24  4991.4  365.74  4994.7  366.24
  5006.4  367.80  5015.4  370.10  5028.1  370.60  5092.2  369.96  5150.5  370.29
  5198.1  369.45  5227.2  370.11  5320.9  369.79  5375.1  371.30  5433.6  373.73
  5481.1  377.05  5510.3  377.66  5570.3  382.22  5684.3  387.39  5740.0  389.84
#Mann=4,-1,0
  4597.8    0.05       0  4988.7    0.03       0  4994.7    0.05       0
  5684.3     0.1       0
Bank Sta=4988.7,4994.7
Exp/Cntr=0.3,0.1

Type RM Length L Ch R = 1,6082,13,13,13
BEGIN DESCRIPTION:
LIES BRANCH 11.03
END DESCRIPTION:
XS GIS Cut Line= 5
      3556499.66     10493844.23      3556181.97     10494258.27
      3555989.26     10494310.36      3555819.99     10494234.83
      3555569.98     10494010.87
#Sta/Elev= 30
  4369.4  395.11  4722.0  376.81  4960.1  368.67  4997.0  365.23  4999.7  364.73
  5003.0  365.23  5015.4  369.03  5039.8  369.46  5173.3  367.97  5187.4  367.86
  5291.0  366.23  5333.7  369.13  5347.9  373.62  5352.4  373.13  5362.1  374.76
  5368.8  373.23  5376.3  374.50  5383.0  373.20  5447.3  377.67  5454.0  376.41
  5482.4  379.32  5489.1  377.49  5496.6  379.19  5503.4  375.98  5510.8  377.98
  5517.6  376.05  5525.1  378.18  5531.8  377.48  5539.3  379.07  5611.9  377.55
#Mann=6,-1,0
  4369.4    0.05       0  4997.0    0.03       0  5003.0    0.05       0
  5173.3    0.08       0  5187.4    0.16       0  5352.4    0.05       0
Bank Sta=4997,5003
Exp/Cntr=0.3,0.1

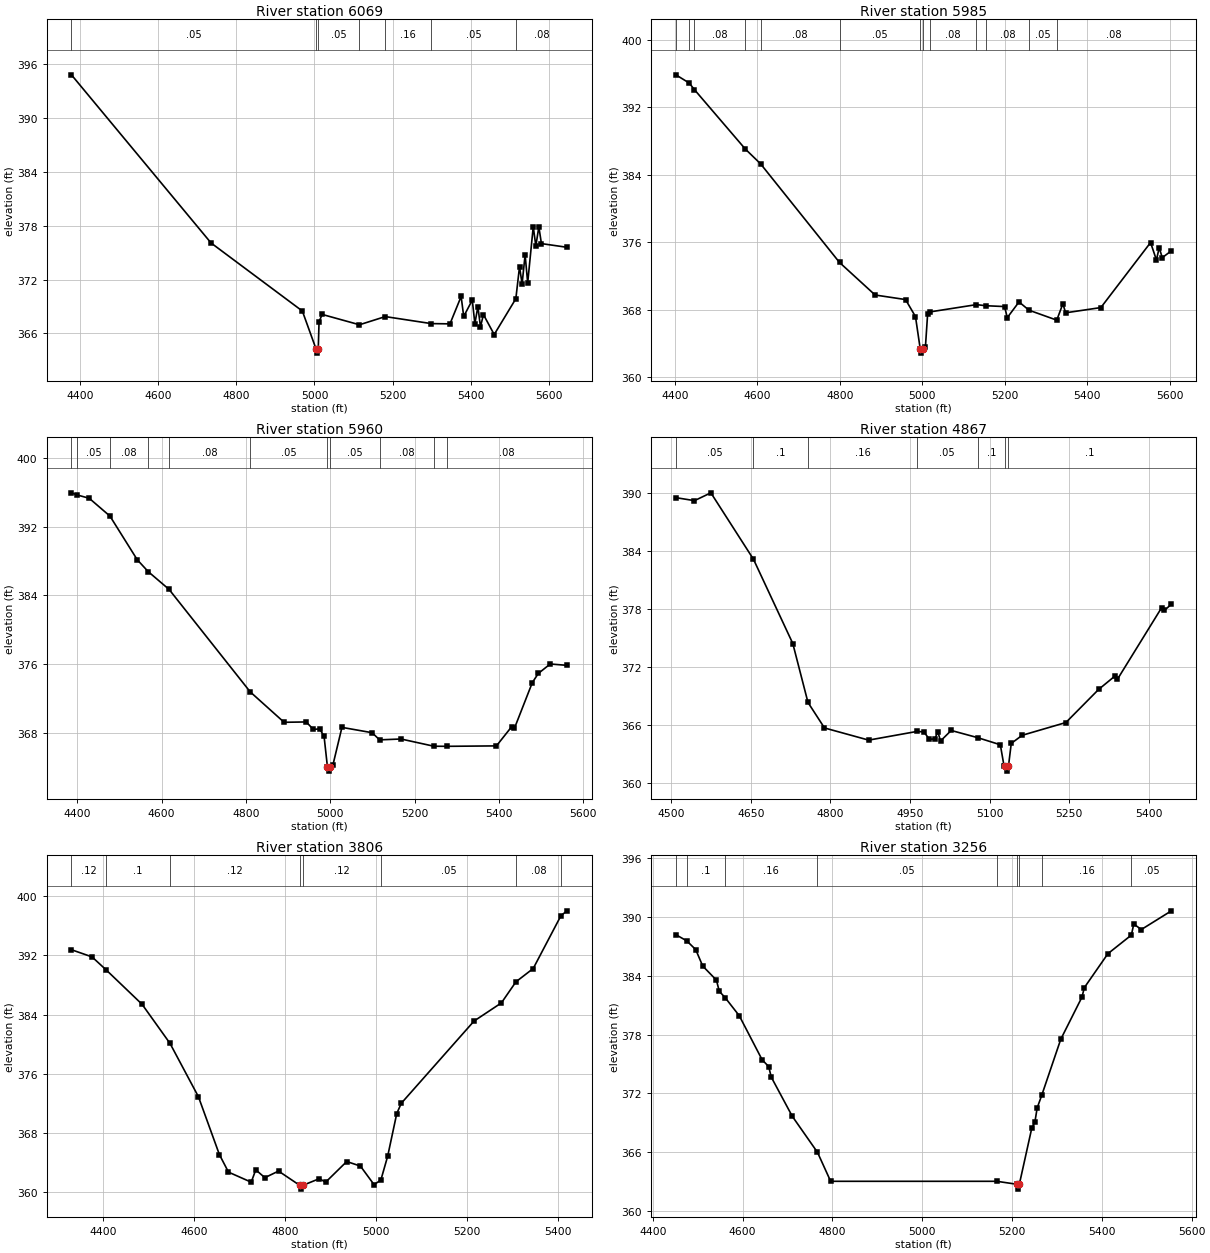
Type RM Length L Ch R = 1,6069,84,84,84
BEGIN DESCRIPTION:
LIES BRANCH 11.01
END DESCRIPTION:
XS GIS Cut Line= 6
      3556481.46     10493831.17      3556171.55     10494242.65
      3556111.65     10494268.69      3555999.68     10494286.92
      3555843.43     10494211.40      3555541.33     10493950.97
#Sta/Elev= 30
  4378.9  394.81  4735.7  376.08  4969.0  368.50  5003.7  364.31  5006.4  363.81
  5009.7  364.31  5011.7  367.32  5019.7  368.12  5115.0  366.97  5180.9  367.88
  5298.3  367.10  5346.3  367.07  5374.8  370.12  5381.4  367.90  5403.3  369.72
  5409.9  367.09  5417.6  369.00  5424.2  366.75  5431.9  368.10  5459.3  365.88
  5514.6  369.87  5524.0  373.43  5530.6  371.54  5538.3  374.76  5544.9  371.64
  5559.1  377.90  5565.7  375.74  5573.4  377.88  5580.0  376.01  5645.2  375.60
#Mann=7,-1,0
  4378.9    0.05       0  5003.7    0.03       0  5009.7    0.05       0
  5115.0    0.08       0  5180.9    0.16       0  5298.3    0.05       0
  5514.6    0.08       0
Bank Sta=5003.7,5009.7
Exp/Cntr=0.3,0.1

Type RM Length L Ch R = 1,5985,25,25,25
BEGIN DESCRIPTION:
LIES BRANCH 11.0
END DESCRIPTION:
XS GIS Cut Line= 5
      3556434.59     10493773.87      3556103.84     10494172.33
      3556007.49     10494211.40      3555913.74     10494203.58
      3555549.16     10493883.28
#Sta/Elev= 30
  4402.8  395.83  4435.0  394.86  4447.6  394.08  4571.1  387.03  4607.9  385.29
  4799.4  373.59  4885.7  369.73  4959.5  369.19  4983.6  367.17  4995.1  363.34
  4997.8  362.84  5001.1  363.34  5007.7  363.58  5013.1  367.53  5017.9  367.72
  5131.5  368.59  5153.8  368.46  5199.5  368.36  5206.2  367.05  5234.6  368.91
  5258.7  367.93  5326.1  366.75  5340.9  368.69  5347.6  367.62  5433.0  368.24
  5553.5  375.95  5567.7  373.88  5574.4  375.33  5581.9  374.16  5604.0  374.97
#Mann=13,-1,0
  4402.8    0.08       0  4435.0    0.05       0  4447.6    0.08       0
  4571.1    0.05       0  4607.9    0.08       0  4799.4    0.05       0
  4995.1    0.03       0  5001.1    0.05       0  5017.9    0.08       0
  5131.5    0.16       0  5153.8    0.08       0  5258.7    0.05       0
  5326.1    0.08       0
Bank Sta=4995.1,5001.1
Exp/Cntr=0.3,0.1

Type RM Length L Ch R = 1,5960,1093,1093,1093
BEGIN DESCRIPTION:
LIES BRANCH 11.02
END DESCRIPTION:
XS GIS Cut Line= 5
      3556424.13     10493734.87      3556098.63     10494151.50
      3555978.84     10494193.17      3555903.32     10494180.15
      3555576.17     10493881.55
#Sta/Elev= 30
  4386.4  395.92  4399.3  395.68  4428.5  395.29  4477.7  393.22  4542.5  388.15
  4568.5  386.77  4617.9  384.71  4810.4  372.81  4890.7  369.28  4943.2  369.32
  4960.1  368.45  4975.0  368.52  4985.5  367.66  4993.5  364.11  4996.3  363.61
  4999.5  364.11  5006.7  364.36  5027.9  368.69  5099.5  368.07  5117.2  367.24
  5167.9  367.34  5246.0  366.50  5276.6  366.49  5394.3  366.54  5430.1  368.75
  5436.8  368.56  5479.4  373.89  5493.6  374.95  5521.9  376.05  5561.5  375.89
#Mann=11,-1,0
  4386.4    0.08       0  4399.3    0.05       0  4477.7    0.08       0
  4568.5    0.05       0  4617.9    0.08       0  4810.4    0.05       0
  4993.5    0.03       0  4999.5    0.05       0  5117.2    0.08       0
  5246.0    0.05       0  5276.6    0.08       0
Bank Sta=4993.5,4999.5
Exp/Cntr=0.3,0.1

Type RM Length L Ch R = 1,4867,1061,1061,1061
BEGIN DESCRIPTION:
LIES BRANCH 9.0
END DESCRIPTION:
XS GIS Cut Line= 2
      3556076.09     10493399.54      3555168.91     10493620.91
#Sta/Elev= 30
  4508.7  389.50  4543.7  389.19  4574.6  390.00  4654.9  383.12  4729.0  374.40
  4757.6  368.30  4788.7  365.66  4872.0  364.40  4963.1  365.30  4976.0  365.25
  4986.3  364.50  4996.6  364.51  5002.2  365.28  5007.4  364.31  5027.5  365.40
  5077.1  364.66  5120.1  363.92  5127.2  361.69  5129.4  361.69  5132.1  361.19
  5135.4  361.69  5140.7  364.06  5161.3  364.90  5243.6  366.22  5305.4  369.65
  5335.6  371.01  5340.8  370.70  5424.1  378.11  5429.3  377.83  5442.5  378.47
#Mann=7,-1,0
  4508.7    0.05       0  4654.9     0.1       0  4757.6    0.16       0
  4963.1    0.05       0  5077.1     0.1       0  5129.4    0.03       0
  5135.4     0.1       0
Bank Sta=5129.4,5135.4
Exp/Cntr=0.3,0.1

Type RM Length L Ch R = 1,3806,550,550,550
BEGIN DESCRIPTION:
LIES BRANCH 7.0
END DESCRIPTION:
XS GIS Cut Line= 2
      3555837.37     10493056.67      3554747.97     10493095.73
#Sta/Elev= 30
  4330.1  392.76  4375.4  391.79  4406.0  390.06  4485.5  385.38  4546.9  380.10
  4609.5  372.88  4655.6  365.06  4675.6  362.69  4725.6  361.33  4735.6  363.00
  4755.6  361.94  4785.7  362.83  4832.7  360.89  4835.4  360.39  4838.7  360.89
  4875.7  361.81  4889.2  361.32  4935.7  364.12  4965.8  363.51  4995.8  361.00
  5010.8  361.61  5025.8  364.84  5045.8  370.61  5055.8  372.00  5215.9  383.12
  5276.0  385.57  5308.0  388.42  5346.0  390.22  5407.0  397.36  5420.2  398.02
#Mann=8,-1,0
  4330.1    0.12       0  4406.0     0.1       0  4546.9    0.12       0
  4832.7    0.07       0  4838.7    0.12       0  5010.8    0.05       0
  5308.0    0.08       0  5407.0    0.05       0
Bank Sta=4832.7,4838.7
Exp/Cntr=0.3,0.1

Type RM Length L Ch R = 1,3256,419,419,419
BEGIN DESCRIPTION:
LIES BRANCH 5.0
END DESCRIPTION:
XS GIS Cut Line= 2
      3555880.75     10492674.72      3554796.35     10492470.85
#Sta/Elev= 30
  4451.5  388.20  4475.7  387.57  4495.6  386.68  4511.2  385.00  4541.7  383.56
  4548.1  382.42  4561.3  381.76  4592.6  379.92  4643.5  375.42  4658.2  374.72
  4663.8  373.65  4710.7  369.64  4766.8  365.96  4796.1  363.00  5166.2  363.00
  5210.3  362.70  5213.0  362.20  5216.3  362.70  5243.8  368.40  5250.9  369.05
  5256.0  370.50  5266.0  371.77  5308.5  377.51  5355.7  381.82  5361.0  382.79
  5413.5  386.26  5465.7  388.16  5471.1  389.29  5488.0  388.73  5554.9  390.64
#Mann=9,-1,0
  4451.5    0.16       0  4475.7     0.1       0  4561.3    0.16       0
  4766.8    0.05       0  5166.2    0.12       0  5210.3   0.033       0
  5216.3    0.12       0  5266.0    0.16       0  5465.7    0.05       0
Bank Sta=5210.3,5216.3
Exp/Cntr=0.3,0.1

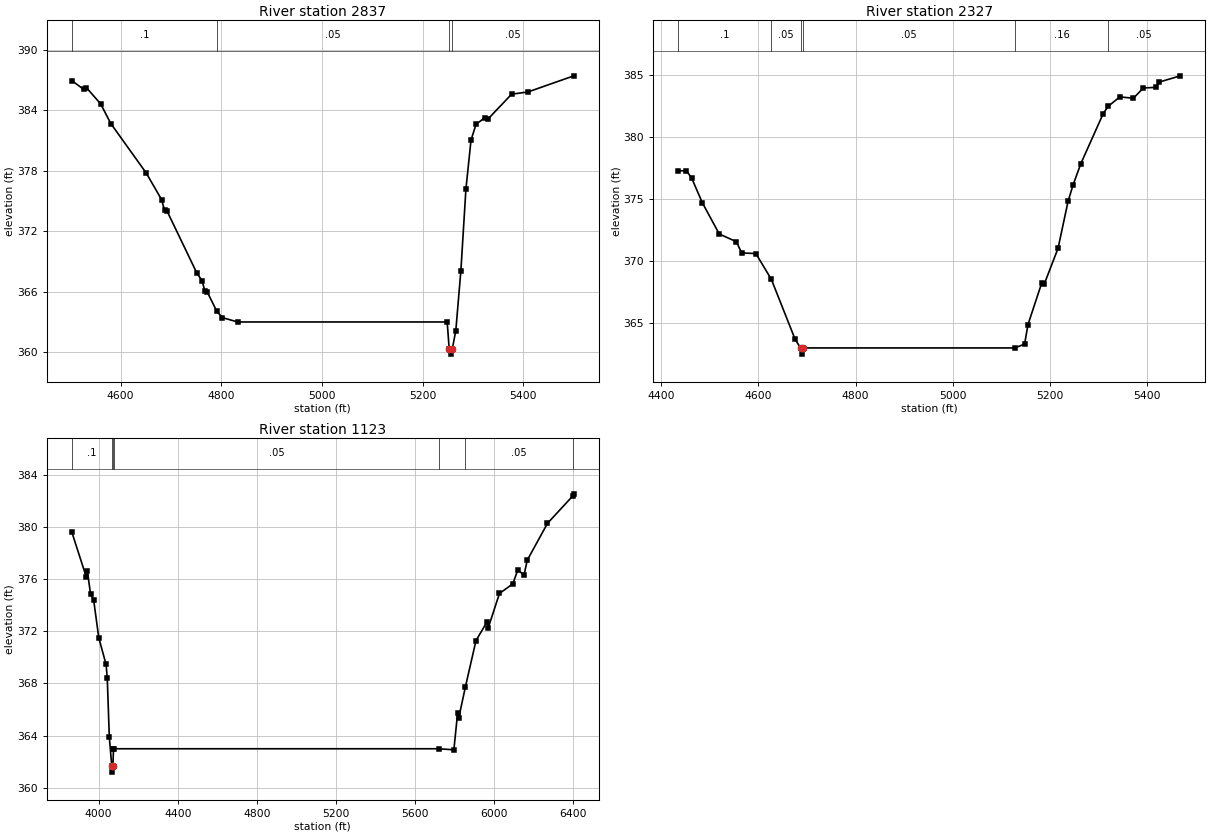
Type RM Length L Ch R = 1,2837,510,510,510
BEGIN DESCRIPTION:
LIES BRANCH 4.0
END DESCRIPTION:
XS GIS Cut Line= 2
      3555878.97     10492219.85      3554889.43     10492094.86
#Sta/Elev= 30
  4503.1  386.95  4526.9  386.07  4532.0  386.26  4560.4  384.64  4580.6  382.69
  4651.1  377.77  4681.4  375.15  4687.4  374.09  4692.4  374.00  4751.9  367.82
  4762.0  367.10  4767.6  366.04  4772.6  365.94  4791.2  364.06  4802.3  363.43
  4832.6  363.00  5248.9  363.00  5252.9  360.31  5255.6  359.81  5258.9  360.31
  5266.0  362.13  5276.1  368.10  5286.1  376.18  5296.2  381.04  5306.3  382.62
  5324.1  383.28  5329.1  383.09  5376.9  385.60  5409.3  385.82  5500.5  387.42
#Mann=4,-1,0
  4503.1     0.1       0  4791.2    0.05       0  5252.9   0.033       0
  5258.9    0.05       0
Bank Sta=5252.9,5258.9
Exp/Cntr=0.3,0.1

Type RM Length L Ch R = 1,2327,1204,1204,1204
BEGIN DESCRIPTION:
LIES BRANCH 3.0
END DESCRIPTION:
XS GIS Cut Line= 2
      3555868.56     10491515.01      3554868.60     10491778.89
#Sta/Elev= 30
  4434.7  377.31  4451.7  377.29  4462.1  376.74  4484.1  374.74  4519.2  372.20
  4554.3  371.58  4565.5  370.67  4594.6  370.62  4626.5  368.54  4675.2  363.72
  4686.6  363.00  4689.3  362.50  4692.6  363.00  5127.8  363.00  5148.2  363.31
  5155.0  364.87  5183.3  368.23  5188.5  368.14  5217.1  371.05  5237.7  374.84
  5248.1  376.17  5263.9  377.87  5310.1  381.92  5320.3  382.51  5344.4  383.27
  5372.2  383.16  5392.9  383.99  5419.8  384.04  5425.0  384.46  5468.9  384.97
#Mann=6,-1,0
  4434.7     0.1       0  4626.5    0.05       0  4686.6   0.033       0
  4692.6    0.05       0  5127.8    0.16       0  5320.3    0.05       0
Bank Sta=4686.6,4692.6
Exp/Cntr=0.3,0.1

Type RM Length L Ch R = 1,1123,0,0,0
BEGIN DESCRIPTION:
LIES BRANCH 1.0
END DESCRIPTION:
XS GIS Cut Line= 4
      3555592.12     10491141.68      3555408.42     10490594.17
      3554517.80     10490583.75      3554163.62     10491594.19
#Sta/Elev= 30
  3864.3  379.61  3937.9  376.15  3943.2  376.63  3959.3  374.84  3974.7  374.43
  4001.0  371.49  4037.8  369.46  4043.7  368.44  4054.2  363.89  4066.4  361.71
  4069.1  361.21  4072.4  361.71  4075.3  363.00  4077.9  363.00  5720.8  363.00
  5796.5  362.92  5815.3  365.72  5820.6  365.33  5855.0  367.75  5908.4  371.29
  5965.1  372.74  5970.4  372.27  6027.1  374.90  6094.4  375.63  6120.1  376.71
  6151.2  376.29  6167.4  377.44  6269.9  380.27  6397.3  382.36  6403.2  382.53
#Mann=7,-1,0
  3864.3     0.1       0  4066.4   0.033       0  4072.4     0.1       0
  4077.9    0.05       0  5720.8     0.1       0  5855.0    0.05       0
  6397.3     0.1       0
Bank Sta=4066.4,4072.4
Exp/Cntr=0.3,0.1

Chan Stop Cuts=-1