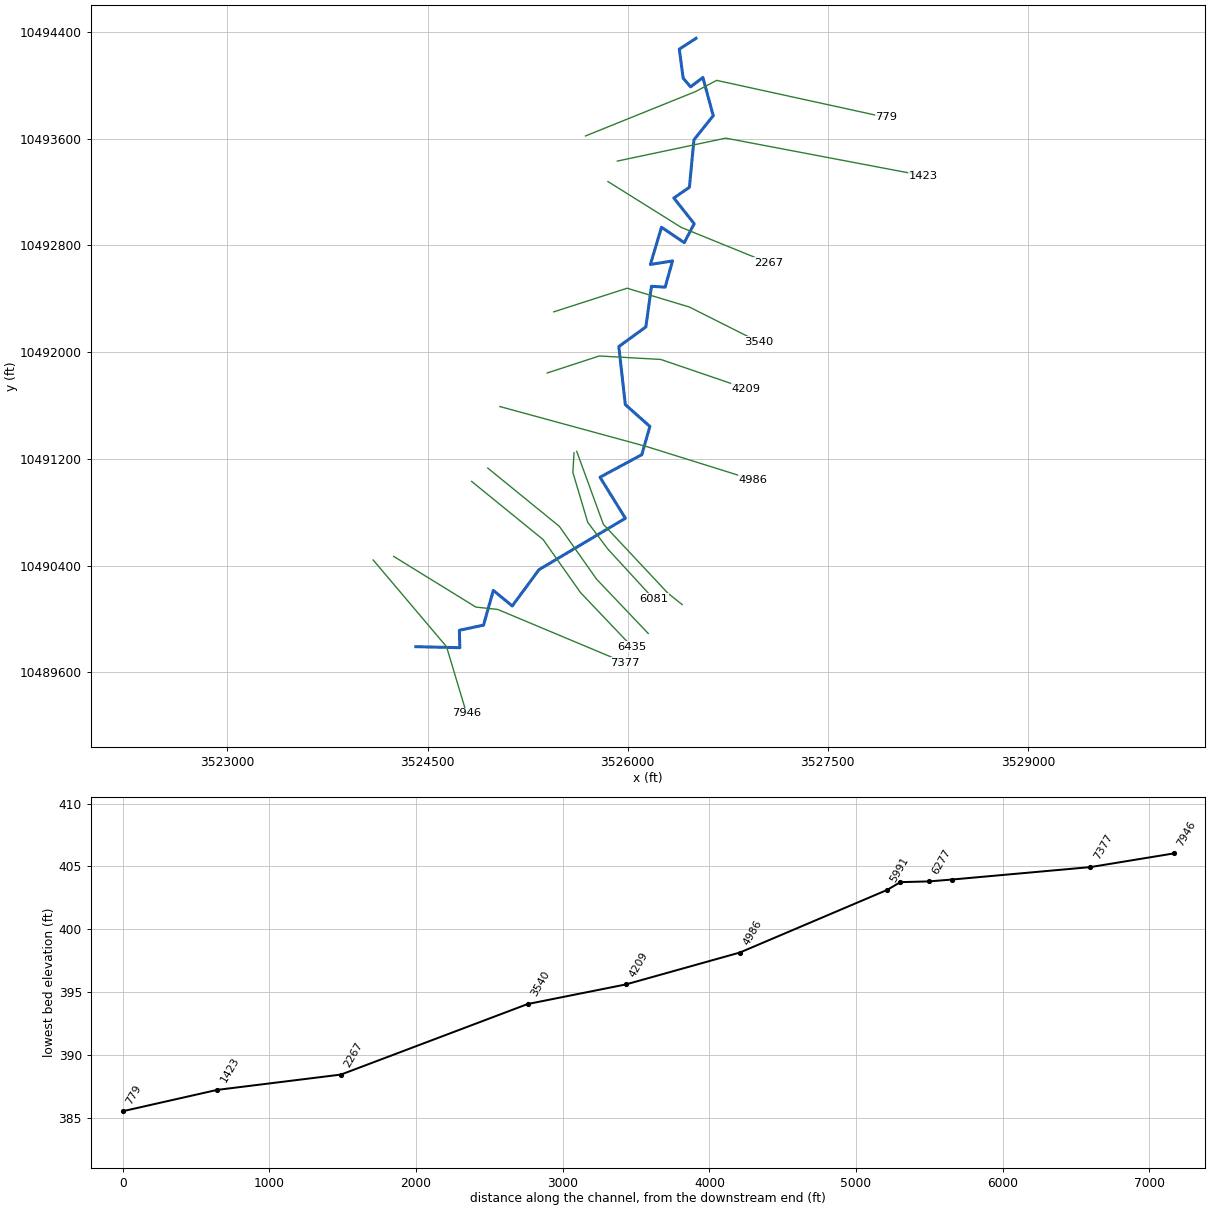
--- LOFTIN CREEK.prj (project) ---

Proj Title=LOFTIN CREEK Base Level Engineering
Current Plan=p01
Default Exp/Contr=0.3,0.1
English Units
Geom File=g01
Flow File=f01
Plan File=p01
BEGIN DESCRIPTION:
LOFTIN CREEK
END DESCRIPTION:

--- LOFTIN CREEK.p01 (plan) ---

Plan Title=Multiple Run
Short Identifier=Multiple
Geom File=g01
Flow File=f01
Subcritical Flow
K Sum by GR= 0
Std Step Tol= 0.01
Critical Tol= 0.01
Num of Std Step Trials= 20
Max Error Tol= 0.3
Flow Tol Ratio= 0.001
Split Flow NTrial= 30
Split Flow Tol= 0.02
Split Flow Ratio= 0.02
Log Output Level= 0
Friction Slope Method= 1
Unsteady Friction Slope Method= 2
Unsteady Bridges Friction Slope Method= 1
Parabolic Critical Depth
Global Vel Dist=  1 , 1 , 1
Global Log Level= 0
CheckData=True
Encroach Param= -1, 0, 0, 0
BEGIN DESCRIPTION:
Multiple Run
END DESCRIPTION:

--- LOFTIN CREEK.f01 (steady flow) ---

Flow Title=Multiple
Number of Profiles=7
Profile Names=10-year,25-year,50-year,1pct_min,100-year,1pct_plu,500-year
River Rch & RM= LOFTIN CREEK,Reach-1,7946
    1345    1877    2321    2092    2830    3827    4194
River Rch & RM= LOFTIN CREEK,Reach-1,6081
    1538    2154    2671    2412    3262    4412    4855
Boundary for River Rch & Prof#=LOFTIN CREEK,Reach-1,1
Up Type=0
Dn Type=3
Dn Slope=0.005
Boundary for River Rch & Prof#=LOFTIN CREEK,Reach-1,2
Up Type=0
Dn Type=3
Dn Slope=0.005
Boundary for River Rch & Prof#=LOFTIN CREEK,Reach-1,3
Up Type=0
Dn Type=3
Dn Slope=0.005
Boundary for River Rch & Prof#=LOFTIN CREEK,Reach-1,4
Up Type=0
Dn Type=3
Dn Slope=0.005
Boundary for River Rch & Prof#=LOFTIN CREEK,Reach-1,5
Up Type=0
Dn Type=3
Dn Slope=0.005
Boundary for River Rch & Prof#=LOFTIN CREEK,Reach-1,6
Up Type=0
Dn Type=3
Dn Slope=0.005
Boundary for River Rch & Prof#=LOFTIN CREEK,Reach-1,7
Up Type=0
Dn Type=3
Dn Slope=0.005

--- LOFTIN CREEK.g01 (geometry) ---

Geom Title=Existing Conditions

River Reach=LOFTIN CREEK,Reach-1
Reach XY= 30
      3524412.11     10489791.64      3524741.90     10489783.99
      3524738.19     10489914.46      3524919.44     10489953.11
      3524992.96     10490213.52      3525134.65     10490096.79
      3525335.05     10490368.58      3525982.84     10490754.13
      3525792.53     10491061.77      3526105.90     10491230.64
      3526166.46     10491442.39      3525982.29     10491606.09
      3525933.54     10492041.19      3526136.30     10492188.43
      3526178.32     10492493.11      3526280.81     10492486.38
      3526336.18     10492683.09      3526170.34     10492656.58
      3526253.47     10492935.51      3526424.05     10492820.06
      3526498.70     10492961.98      3526345.92     10493154.69
      3526462.67     10493234.99      3526496.67     10493590.99
      3526641.31     10493771.85      3526563.60     10494058.23
      3526471.79     10493987.81      3526416.08     10494052.82
      3526386.91     10494270.54      3526512.11     10494351.64

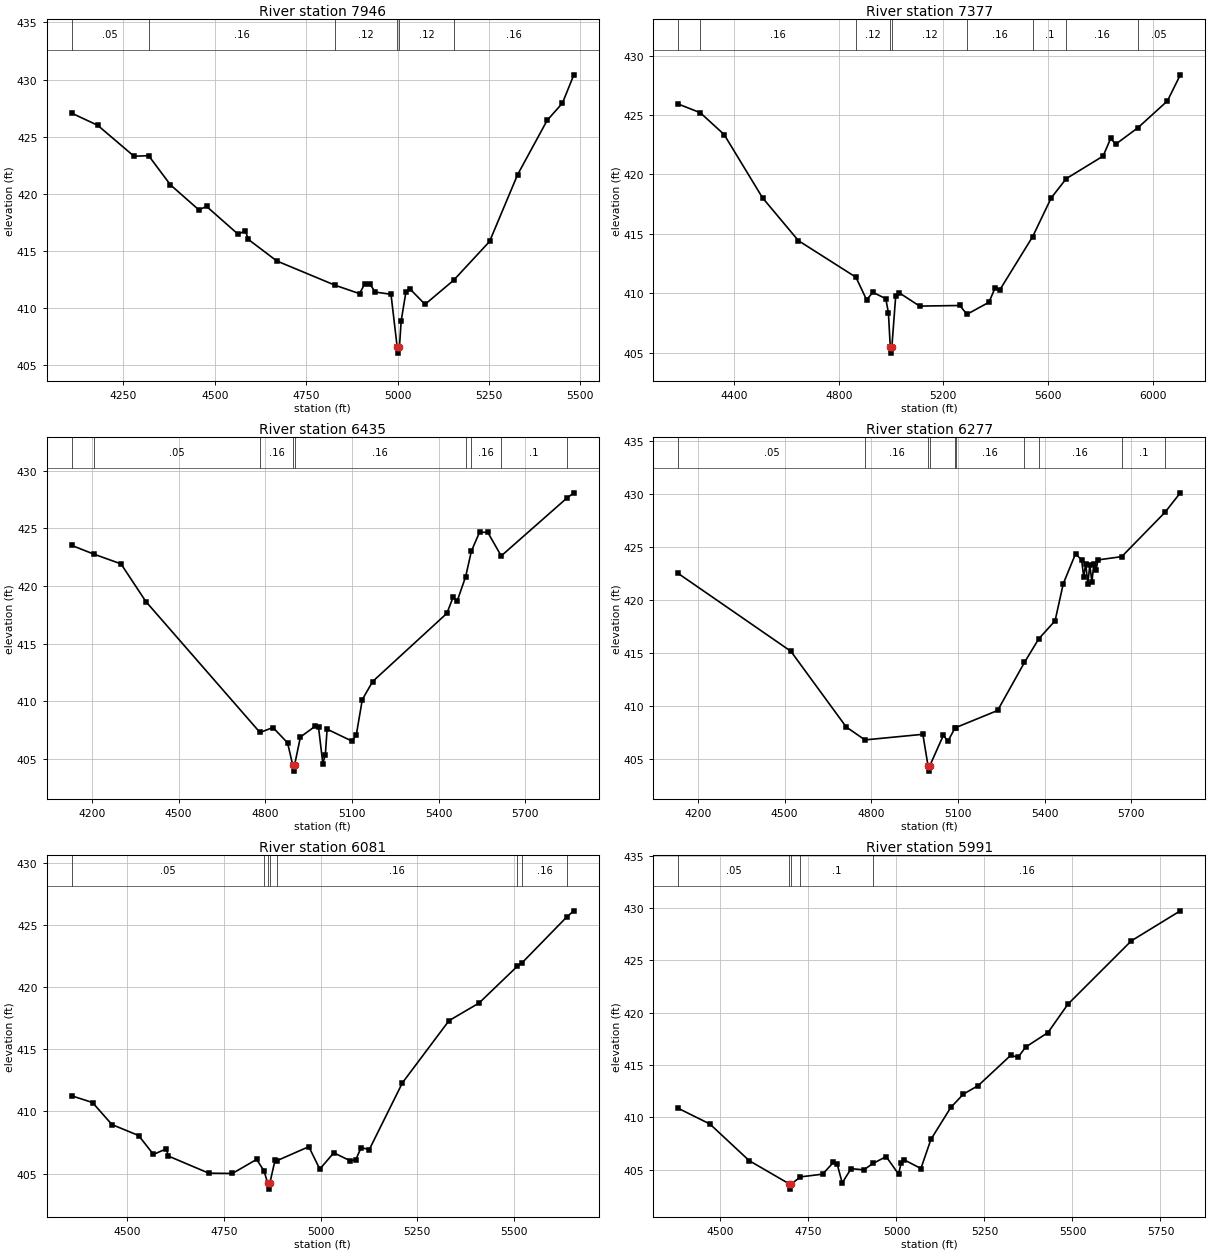
Type RM Length L Ch R = 1,7946,569,569,569
BEGIN DESCRIPTION:
LOFTIN CREEK 14.0
END DESCRIPTION:
XS GIS Cut Line= 3
      3524092.08     10490441.68      3524642.11     10489791.64
      3524792.10     10489291.67
#Sta/Elev= 30
  4108.7  427.05  4179.6  425.99  4279.0  423.28  4319.0  423.33  4378.5  420.78
  4456.5  418.58  4477.3  418.89  4563.1  416.47  4583.9  416.73  4591.6  416.00
  4669.6  414.11  4829.4  411.98  4895.9  411.25  4910.2  412.11  4924.5  412.08
  4938.8  411.39  4982.0  411.19  4999.0  406.54  5001.7  406.04  5005.0  406.54
  5009.8  408.86  5022.9  411.41  5033.3  411.68  5075.1  410.31  5153.3  412.42
  5251.7  415.82  5328.2  421.66  5409.1  426.42  5450.9  427.93  5482.2  430.41
#Mann=6,-1,0
  4108.7    0.05       0  4319.0    0.16       0  4829.4    0.12       0
  4999.0    0.07       0  5005.0    0.12       0  5153.3    0.16       0
Bank Sta=4999,5005
Exp/Cntr=0.3,0.1

Type RM Length L Ch R = 1,7377,942,942,942
BEGIN DESCRIPTION:
LOFTIN CREEK 13.0
END DESCRIPTION:
XS GIS Cut Line= 4
      3524246.39     10490468.08      3524861.77     10490088.51
      3525025.49     10490070.93      3525977.65     10489671.85
#Sta/Elev= 30
  4186.1  425.92  4270.4  425.19  4361.7  423.35  4508.4  418.03  4645.6  414.42
  4865.7  411.34  4906.4  409.44  4930.6  410.07  4979.9  409.53  4989.9  408.35
  4997.0  405.45  4999.7  404.95  5003.0  405.45  5017.7  409.74  5030.2  410.04
  5109.4  408.91  5262.9  408.96  5290.3  408.22  5374.3  409.23  5398.1  410.45
  5416.4  410.29  5541.6  414.76  5612.3  418.01  5670.0  419.64  5811.0  421.54
  5840.2  423.04  5858.6  422.53  5944.4  423.93  6056.8  426.18  6106.2  428.38
#Mann=9,-1,0
  4186.1    0.05       0  4270.4    0.16       0  4865.7    0.12       0
  4997.0    0.07       0  5003.0    0.12       0  5290.3    0.16       0
  5541.6     0.1       0  5670.0    0.16       0  5944.4    0.05       0
Bank Sta=4997,5003
Exp/Cntr=0.3,0.1

Type RM Length L Ch R = 1,6435,158,158,158
BEGIN DESCRIPTION:
LOFTIN CREEK 11.1
END DESCRIPTION:
XS GIS Cut Line= 4
      3524830.45     10491030.42      3525366.51     10490594.19
      3525646.46     10490197.06      3526032.75     10489791.23
#Sta/Elev= 30
  4130.5  423.53  4206.2  422.78  4300.8  421.93  4387.0  418.66  4781.8  407.31
  4826.8  407.74  4877.3  406.41  4895.2  404.46  4897.9  403.96  4901.2  404.46
  4921.7  406.92  4971.6  407.83  4984.4  407.75  4999.2  404.62  5007.9  405.38
  5014.0  407.60  5100.2  406.56  5115.0  407.10  5135.9  410.17  5171.6  411.73
  5428.4  417.64  5449.8  419.02  5464.0  418.70  5493.3  420.81  5513.3  423.04
  5541.7  424.68  5570.0  424.66  5616.5  422.62  5843.4  427.63  5867.8  428.09
#Mann=9,-1,0
  4130.5     0.1       0  4206.2    0.05       0  4781.8    0.16       0
  4895.2    0.07       0  4901.2    0.16       0  5493.3     0.1       0
  5513.3    0.16       0  5616.5     0.1       0  5843.4    0.05       0
Bank Sta=4895.2,4901.2
Exp/Cntr=0.3,0.1

Type RM Length L Ch R = 1,6277,196,196,196
BEGIN DESCRIPTION:
LOFTIN CREEK 11.0
END DESCRIPTION:
XS GIS Cut Line= 4
      3524951.72     10491129.94      3525487.73     10490693.76
      3525767.67     10490296.62      3526153.95     10489890.82
#Sta/Elev= 30
  4132.2  422.49  4521.8  415.14  4713.5  407.98  4778.3  406.76  4978.6  407.29
  4996.5  404.31  4999.2  403.81  5002.5  404.31  5050.0  407.22  5064.8  406.61
  5090.4  407.92  5093.0  407.93  5237.2  409.54  5330.1  414.08  5379.3  416.30
  5436.1  418.02  5464.4  421.52  5506.9  424.35  5527.9  423.76  5535.2  422.15
  5542.1  423.42  5549.4  421.53  5556.3  423.29  5563.5  421.70  5570.4  423.42
  5577.7  422.79  5584.6  423.77  5666.7  424.08  5816.2  428.26  5869.4  430.11
#Mann=10,-1,0
  4132.2    0.05       0  4778.3    0.16       0  4996.5    0.07       0
  5002.5    0.16       0  5090.4    0.05       0  5093.0    0.16       0
  5330.1    0.05       0  5379.3    0.16       0  5666.7     0.1       0
  5816.2    0.16       0
Bank Sta=4996.5,5002.5
Exp/Cntr=0.3,0.1

Type RM Length L Ch R = 1,6081,90,90,90
BEGIN DESCRIPTION:
LOFTIN CREEK 10.0
END DESCRIPTION:
XS GIS Cut Line= 5
      3525597.88     10491245.14      3525589.20     10491097.53
      3525700.40     10490724.14      3525852.31     10490522.32
      3526195.18     10490149.07
#Sta/Elev= 30
  4357.3  411.25  4410.9  410.71  4461.0  408.94  4529.9  408.06  4568.3  406.54
  4601.5  406.99  4606.7  406.41  4711.4  405.03  4772.2  405.01  4834.8  406.14
  4854.0  405.21  4863.1  404.25  4865.8  403.75  4869.1  404.25  4882.5  406.10
  4886.8  406.03  4969.6  407.16  4998.0  405.36  5034.1  406.67  5075.8  406.04
  5090.4  406.09  5104.9  407.09  5125.8  406.93  5211.5  412.30  5331.7  417.29
  5409.4  418.71  5507.7  421.65  5520.4  421.94  5636.3  425.64  5654.2  426.12
#Mann=8,-1,0
  4357.3    0.05       0  4854.0     0.1       0  4863.1    0.07       0
  4869.1     0.1       0  4886.8    0.16       0  5507.7    0.05       0
  5520.4    0.16       0  5636.3    0.05       0
Bank Sta=4863.1,4869.1
Exp/Cntr=0.3,0.1

Type RM Length L Ch R = 1,5991,1005,1005,1005
BEGIN DESCRIPTION:
LOFTIN CREEK 9.0
END DESCRIPTION:
XS GIS Cut Line= 4
      3525617.93     10491255.83      3525817.59     10490708.95
      3526301.53     10490192.46      3526407.98     10490107.30
#Sta/Elev= 30
  4380.0  410.85  4470.0  409.35  4581.6  405.85  4695.4  403.63  4698.2  403.13
  4701.4  403.63  4727.3  404.30  4790.1  404.56  4820.9  405.69  4831.6  405.51
  4845.8  403.72  4871.1  405.09  4906.9  404.97  4933.2  405.58  4970.7  406.24
  5005.9  404.56  5013.2  405.63  5020.1  405.96  5069.4  405.10  5097.8  407.88
  5154.4  410.94  5190.1  412.21  5232.5  413.03  5324.4  415.91  5345.4  415.73
  5366.9  416.70  5430.4  418.09  5487.0  420.80  5667.1  426.85  5806.3  429.72
#Mann=5,-1,0
  4380.0    0.05       0  4695.4    0.07       0  4701.4    0.05       0
  4727.3     0.1       0  4933.2    0.16       0
Bank Sta=4695.4,4701.4
Exp/Cntr=0.3,0.1

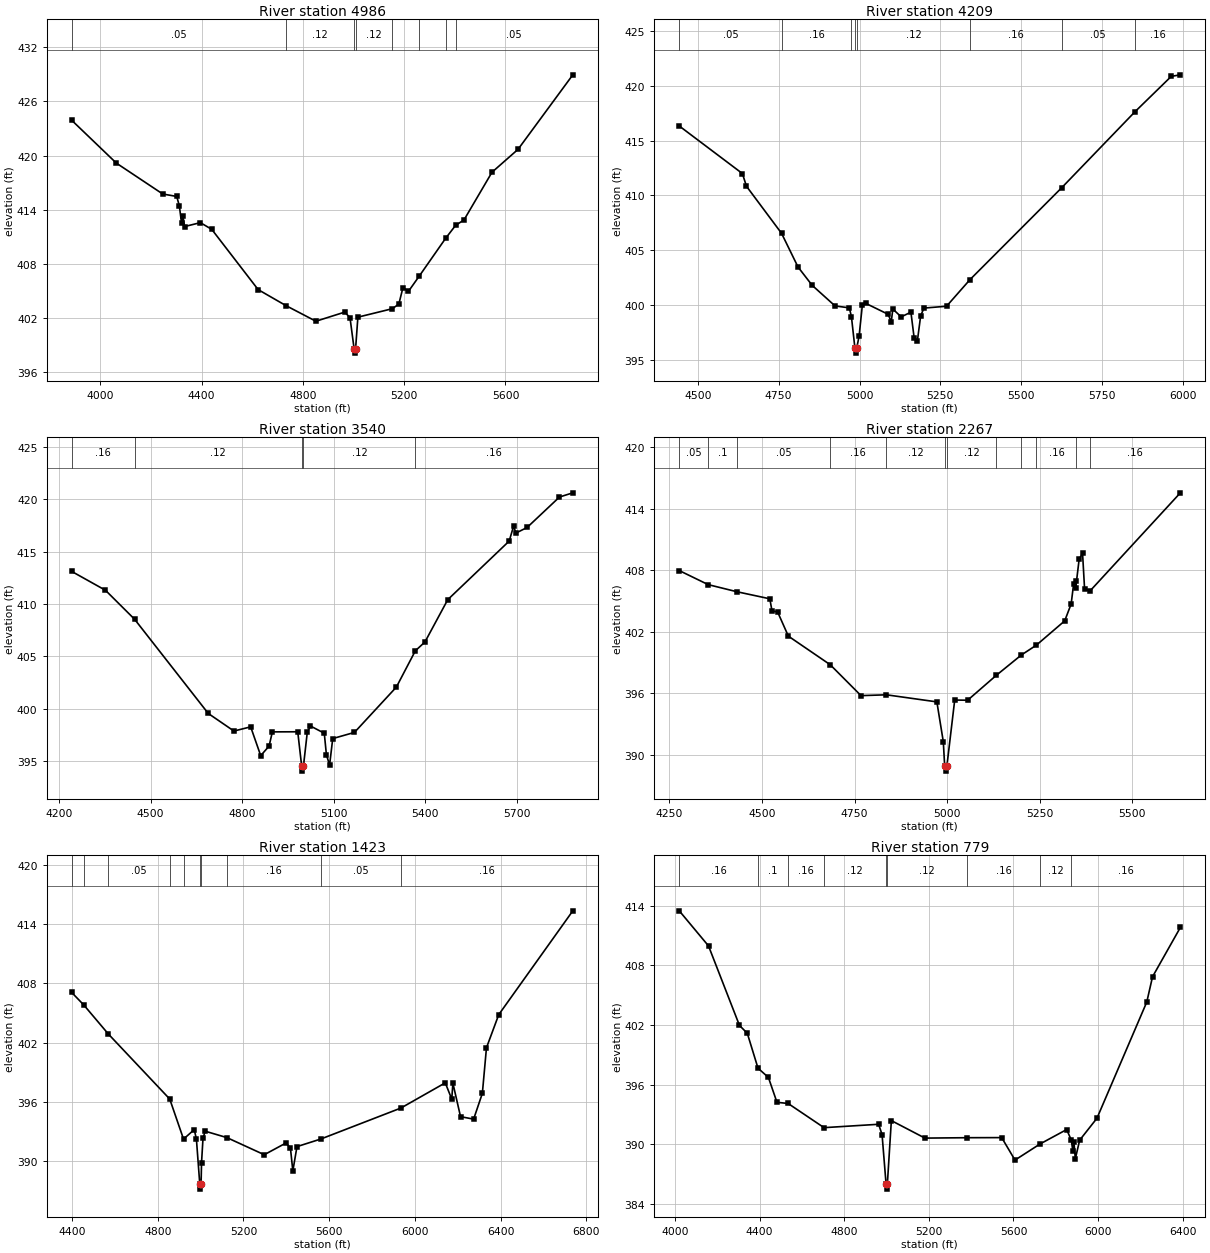
Type RM Length L Ch R = 1,4986,777,777,777
BEGIN DESCRIPTION:
LOFTIN CREEK 8.0
END DESCRIPTION:
XS GIS Cut Line= 3
      3525042.07     10491591.65      3526142.11     10491291.64
      3526942.14     10491041.63
#Sta/Elev= 30
  3887.5  423.91  4063.7  419.17  4246.9  415.75  4302.1  415.48  4312.5  414.43
  4321.1  412.53  4326.3  413.32  4333.2  412.15  4395.4  412.58  4440.3  411.84
  4623.5  405.17  4733.3  403.40  4851.5  401.67  4965.5  402.68  4986.2  402.06
  5002.3  398.64  5005.0  398.14  5008.3  398.64  5017.3  402.12  5153.9  403.06
  5179.1  403.58  5195.3  405.40  5216.8  404.97  5258.7  406.63  5363.6  410.84
  5403.1  412.28  5436.3  412.88  5546.8  418.16  5649.5  420.69  5865.9  428.94
#Mann=8,-1,0
  3887.5    0.05       0  4733.3    0.12       0  5002.3    0.07       0
  5008.3    0.12       0  5153.9    0.16       0  5258.7    0.05       0
  5363.6    0.16       0  5403.1    0.05       0
Bank Sta=5002.3,5008.3
Exp/Cntr=0.3,0.1

Type RM Length L Ch R = 1,4209,669,669,669
BEGIN DESCRIPTION:
LOFTIN CREEK 6.0
END DESCRIPTION:
XS GIS Cut Line= 4
      3525396.60     10491843.07      3525787.20     10491970.67
      3526248.14     10491944.63      3526888.73     10491725.89
#Sta/Elev= 30
  4442.6  416.33  4637.8  411.99  4650.4  410.83  4759.0  406.53  4809.8  403.46
  4853.5  401.79  4924.2  399.91  4968.6  399.73  4975.0  398.92  4985.6  396.10
  4988.4  395.60  4991.6  396.10  4998.7  397.16  5008.7  399.97  5018.7  400.15
  5088.8  399.14  5098.0  398.44  5103.0  399.62  5128.9  398.91  5158.9  399.34
  5168.9  396.99  5178.9  396.72  5189.0  398.99  5199.0  399.71  5269.1  399.88
  5341.6  402.31  5625.0  410.69  5851.4  417.62  5964.0  420.86  5992.1  421.00
#Mann=8,-1,0
  4442.6    0.05       0  4759.0    0.16       0  4975.0    0.12       0
  4985.6    0.07       0  4991.6    0.12       0  5341.6    0.16       0
  5625.0    0.05       0  5851.4    0.16       0
Bank Sta=4985.6,4991.6
Exp/Cntr=0.3,0.1

Type RM Length L Ch R = 1,3540,1273,1273,1273
BEGIN DESCRIPTION:
LOFTIN CREEK 4.0
END DESCRIPTION:
XS GIS Cut Line= 4
      3525446.04     10492301.39      3525995.54     10492478.48
      3526461.68     10492337.86      3526978.47     10492078.16
#Sta/Elev= 30
  4241.5  413.12  4352.1  411.32  4447.6  408.55  4689.1  399.55  4773.2  397.87
  4828.1  398.27  4861.0  395.52  4888.4  396.43  4899.2  397.79  4982.4  397.80
  4995.2  394.54  4997.9  394.04  5001.2  394.54  5013.7  397.76  5024.2  398.35
  5069.4  397.66  5076.4  395.60  5086.8  394.62  5097.1  397.15  5168.3  397.74
  5305.7  402.07  5368.0  405.54  5399.4  406.38  5474.1  410.42  5675.5  416.02
  5689.7  417.42  5697.9  416.79  5734.3  417.32  5840.4  420.23  5884.1  420.63
#Mann=5,-1,0
  4241.5    0.16       0  4447.6    0.12       0  4995.2    0.07       0
  5001.2    0.12       0  5368.0    0.16       0
Bank Sta=4995.2,5001.2
Exp/Cntr=0.3,0.1

Type RM Length L Ch R = 1,2267,844,844,844
BEGIN DESCRIPTION:
LOFTIN CREEK 3.0
END DESCRIPTION:
XS GIS Cut Line= 3
      3525852.30     10493277.97      3526401.79     10492934.21
      3527055.42     10492668.59
#Sta/Elev= 30
  4276.4  407.97  4354.6  406.60  4431.9  405.91  4521.0  405.22  4526.9  404.05
  4542.2  403.93  4571.1  401.58  4684.3  398.79  4767.4  395.78  4836.2  395.86
  4972.3  395.17  4989.7  391.29  4993.4  388.92  4996.2  388.42  4999.4  388.92
  5020.5  395.35  5055.4  395.33  5132.6  397.75  5200.5  399.74  5241.1  400.70
  5317.7  403.07  5335.1  404.72  5341.8  406.68  5347.2  406.24  5349.5  406.93
  5356.7  409.08  5365.9  409.65  5371.3  406.20  5385.7  405.97  5630.1  415.55
#Mann=12,-1,0
  4276.4    0.05       0  4354.6     0.1       0  4431.9    0.05       0
  4684.3    0.16       0  4836.2    0.12       0  4993.4    0.07       0
  4999.4    0.12       0  5132.6    0.05       0  5200.5    0.12       0
  5241.1    0.16       0  5349.5    0.05       0  5385.7    0.16       0
Bank Sta=4993.4,4999.4
Exp/Cntr=0.3,0.1

Type RM Length L Ch R = 1,1423,644,644,644
BEGIN DESCRIPTION:
LOFTIN CREEK 2.0
END DESCRIPTION:
XS GIS Cut Line= 3
      3525922.66     10493431.62      3526735.12     10493603.48
      3528216.93     10493322.23
#Sta/Elev= 30
  4398.6  407.09  4455.2  405.82  4569.5  402.89  4856.1  396.31  4920.4  392.26
  4970.4  393.22  4980.6  392.25  4996.3  387.70  4999.1  387.20  5002.3  387.70
  5004.5  389.88  5011.3  392.34  5021.5  393.06  5123.0  392.41  5297.2  390.68
  5399.0  391.87  5419.4  391.35  5430.6  389.04  5449.9  391.50  5561.4  392.27
  5934.8  395.40  6142.0  397.95  6172.4  396.30  6177.5  397.92  6213.3  394.53
  6274.4  394.28  6315.1  396.89  6334.3  401.50  6391.6  404.85  6737.3  415.35
#Mann=10,-1,0
  4398.6    0.05       0  4455.2     0.1       0  4569.5    0.05       0
  4856.1    0.16       0  4920.4    0.12       0  4996.3    0.07       0
  5002.3    0.12       0  5123.0    0.16       0  5561.4    0.05       0
  5934.8    0.16       0
Bank Sta=4996.3,5002.3
Exp/Cntr=0.3,0.1

Type RM Length L Ch R = 1,779,0,0,0
BEGIN DESCRIPTION:
LOFTIN CREEK 1.0
END DESCRIPTION:
XS GIS Cut Line= 4
      3525683.87     10493619.96      3526510.30     10493953.31
      3526666.55     10494036.64      3527937.24     10493758.89
#Sta/Elev= 30
  4020.0  413.48  4158.3  409.95  4304.5  401.96  4341.6  401.17  4392.2  397.66
  4441.4  396.73  4481.8  394.23  4534.7  394.11  4704.4  391.68  4962.4  392.02
  4978.7  390.99  4997.7  386.00  5000.4  385.50  5003.7  386.00  5022.6  392.39
  5181.4  390.63  5379.6  390.67  5544.3  390.68  5607.1  388.42  5726.4  390.05
  5851.4  391.49  5873.5  390.42  5880.6  389.33  5885.8  390.23  5892.3  388.55
  5912.8  390.42  5994.7  392.63  6230.1  404.31  6257.3  406.85  6388.9  411.81
#Mann=9,-1,0
  4020.0    0.16       0  4392.2     0.1       0  4534.7    0.16       0
  4704.4    0.12       0  4997.7    0.07       0  5003.7    0.12       0
  5379.6    0.16       0  5726.4    0.12       0  5873.5    0.16       0
Bank Sta=4997.7,5003.7
Exp/Cntr=0.3,0.1

Chan Stop Cuts=-1