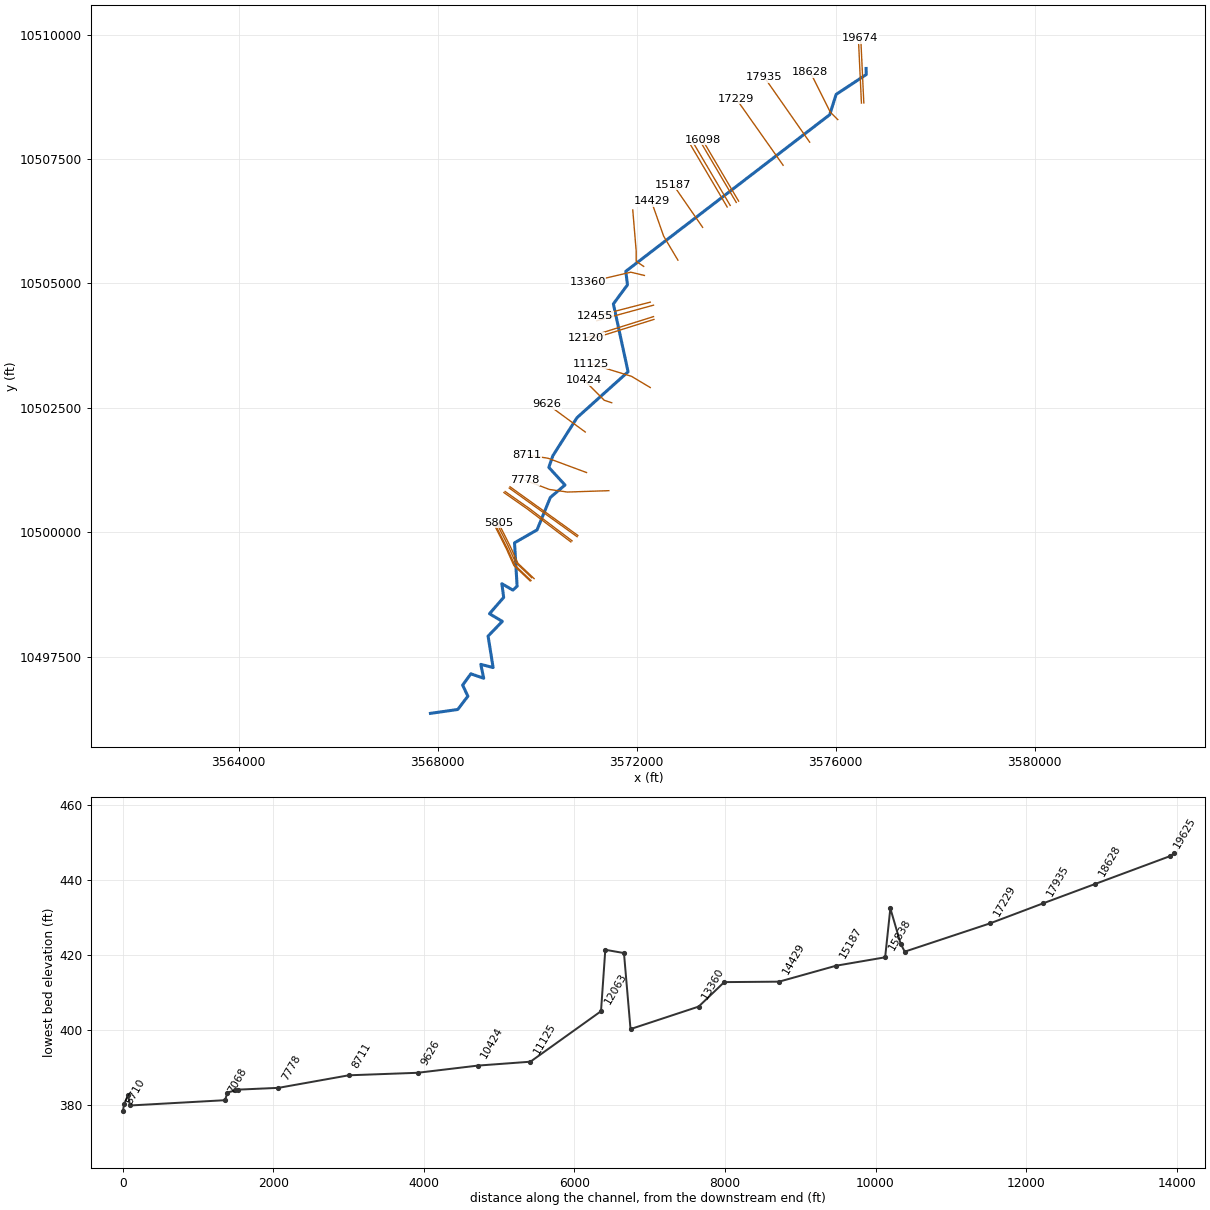
--- LYNN CREEK.prj (project) ---

Proj Title=LYNN CREEK Base Level Engineering
Current Plan=p01
Default Exp/Contr=0.3,0.1
English Units
Geom File=g01
Flow File=f01
Plan File=p01
BEGIN DESCRIPTION:
LYNN CREEK
END DESCRIPTION:

--- LYNN CREEK.p01 (plan) ---

Plan Title=Multiple Run
Short Identifier=Multiple
Geom File=g01
Flow File=f01
Subcritical Flow
K Sum by GR= 0
Std Step Tol= 0.01
Critical Tol= 0.01
Num of Std Step Trials= 20
Max Error Tol= 0.3
Flow Tol Ratio= 0.001
Split Flow NTrial= 30
Split Flow Tol= 0.02
Split Flow Ratio= 0.02
Log Output Level= 0
Friction Slope Method= 1
Unsteady Friction Slope Method= 2
Unsteady Bridges Friction Slope Method= 1
Parabolic Critical Depth
Global Vel Dist=  1 , 1 , 1
Global Log Level= 0
CheckData=True
Encroach Param= -1, 0, 0, 0
BEGIN DESCRIPTION:
Multiple Run
END DESCRIPTION:

--- LYNN CREEK.f01 (steady flow) ---

Flow Title=Multiple
Number of Profiles=7
Profile Names=10-year,25-year,50-year,1pct_min,100-year,1pct_plu,500-year
River Rch & RM= LYNN CREEK,Reach-1,19674
    1439    2018    2505    2267    3065    4146    4578
River Rch & RM= LYNN CREEK,Reach-1,13360
    2742    3970    5032    4639    6274    8485    9736
River Rch & RM= LYNN CREEK,Reach-1,7778
    2668    3837    4842    4441    6006    8123    9228
Boundary for River Rch & Prof#=LYNN CREEK,Reach-1,1
Up Type=0
Dn Type=3
Dn Slope=0.005
Boundary for River Rch & Prof#=LYNN CREEK,Reach-1,2
Up Type=0
Dn Type=3
Dn Slope=0.005
Boundary for River Rch & Prof#=LYNN CREEK,Reach-1,3
Up Type=0
Dn Type=3
Dn Slope=0.005
Boundary for River Rch & Prof#=LYNN CREEK,Reach-1,4
Up Type=0
Dn Type=3
Dn Slope=0.005
Boundary for River Rch & Prof#=LYNN CREEK,Reach-1,5
Up Type=0
Dn Type=3
Dn Slope=0.005
Boundary for River Rch & Prof#=LYNN CREEK,Reach-1,6
Up Type=0
Dn Type=3
Dn Slope=0.005
Boundary for River Rch & Prof#=LYNN CREEK,Reach-1,7
Up Type=0
Dn Type=3
Dn Slope=0.005

--- LYNN CREEK.g01 (geometry) ---

Geom Title=Existing Conditions

River Reach=LYNN CREEK,Reach-1
Reach XY= 30
      3576612.15     10509319.11      3576615.45     10509197.15
      3576009.92     10508798.45      3575880.93     10508390.09
      3571782.73     10505242.37      3571816.11     10504970.10
      3571532.78     10504587.85      3571828.25     10503223.24
      3570802.59     10502301.47      3570318.24     10501538.81
      3570235.16     10501302.98      3570560.27     10500947.60
      3570266.07     10500697.76      3569998.88     10500045.68
      3569546.28     10499785.78      3569598.32     10498912.93
      3569512.77     10498835.33      3569291.94     10498964.29
      3569327.98     10498688.80      3569042.71     10498360.90
      3569301.09     10498206.97      3569014.78     10497911.24
      3569116.05     10497278.84      3568868.24     10497343.04
      3568926.99     10497063.59      3568668.50     10497153.29
      3568503.46     10496926.03      3568608.76     10496703.18
      3568405.26     10496436.38      3567856.26     10496358.18

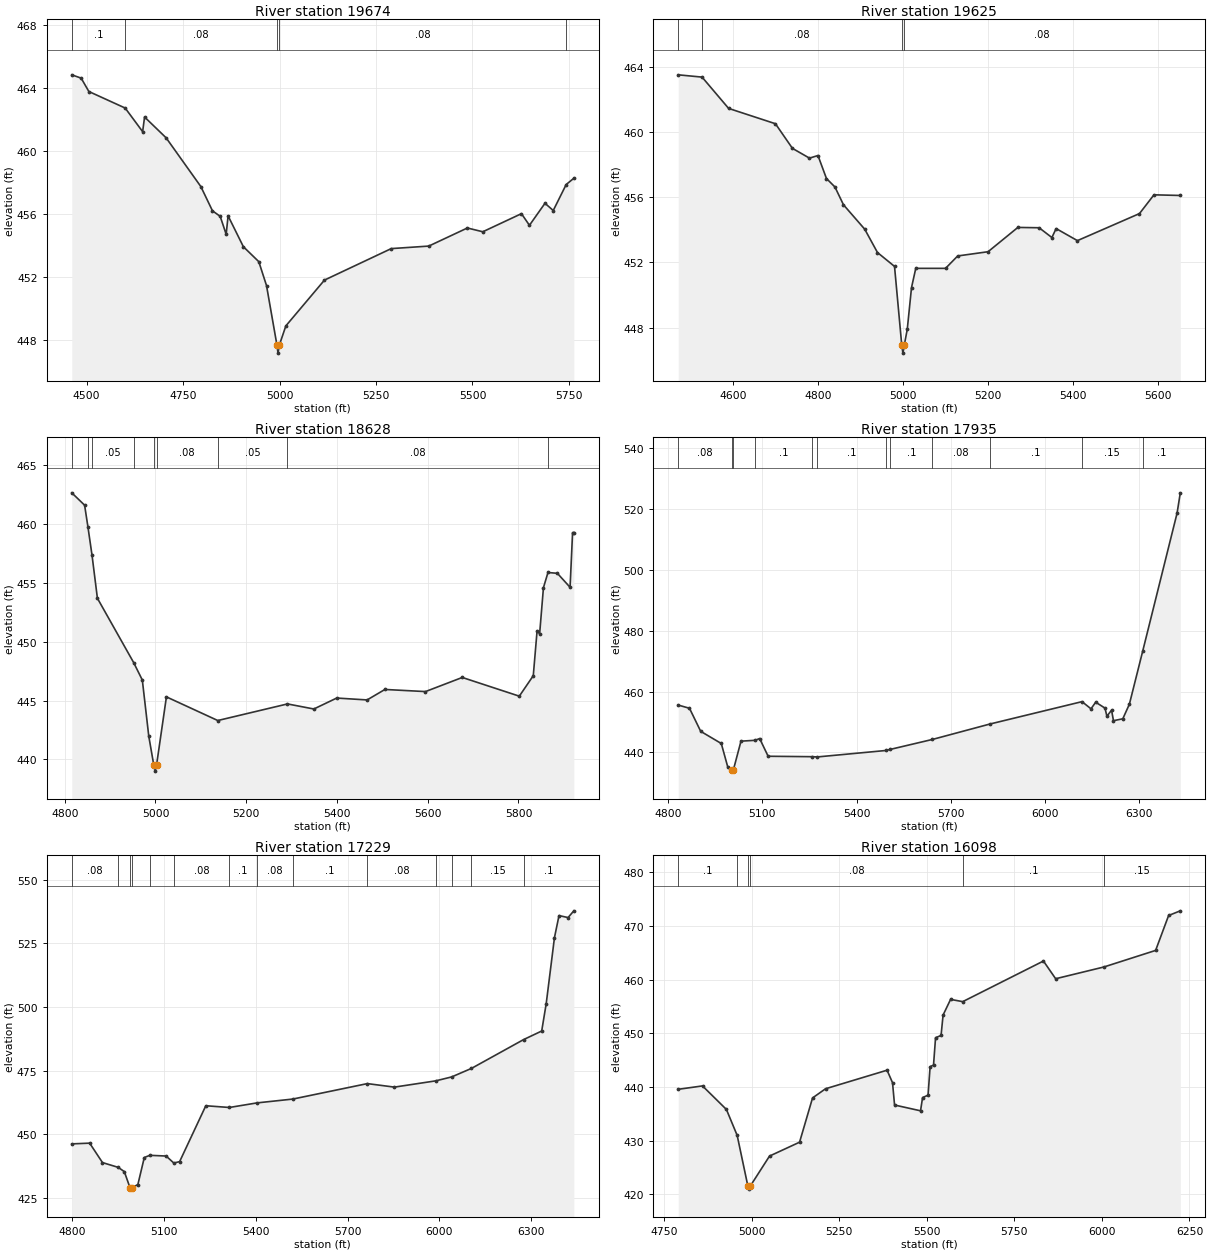
Type RM Length L Ch R = 1,19674,49,49,49
BEGIN DESCRIPTION:
LYNN CREEK 40.01
END DESCRIPTION:
XS GIS Cut Line= 3
      3576565.94     10508627.38      3576510.38     10509807.98
      3576484.73     10509924.69
#Sta/Elev= 30
  4461.4  464.82  4485.7  464.61  4505.7  463.76  4599.8  462.71  4645.1  461.21
  4650.1  462.14  4705.9  460.82  4796.0  457.72  4826.1  456.18  4846.1  455.83
  4861.6  454.69  4866.6  455.86  4906.2  453.90  4946.2  452.95  4966.2  451.43
  4993.3  447.64  4996.0  447.14  4999.3  447.64  5016.3  448.87  5116.4  451.78
  5289.5  453.78  5386.7  453.94  5486.8  455.09  5526.8  454.85  5627.0  456.00
  5647.7  455.26  5688.0  456.66  5709.4  456.20  5742.9  457.85  5762.8  458.25
#Mann=5,-1,0
  4461.4     0.1       0  4599.8    0.08       0  4993.3    0.07       0
  4999.3    0.08       0  5742.9    0.05       0
Bank Sta=4993.3,4999.3
Exp/Cntr=0.3,0.1

Type RM Length L Ch R = 1,19625,997,997,997
BEGIN DESCRIPTION:
LYNN CREEK 40.0
END DESCRIPTION:
XS GIS Cut Line= 2
      3576518.19     10508623.13      3576462.64     10509803.62
#Sta/Elev= 30
  4470.0  463.50  4526.1  463.36  4588.6  461.44  4698.8  460.50  4738.8  458.99
  4778.9  458.39  4798.9  458.55  4818.9  457.14  4838.9  456.62  4858.9  455.53
  4909.0  454.03  4939.0  452.60  4979.1  451.75  4996.1  446.93  4998.9  446.43
  5002.1  446.93  5009.1  447.89  5019.1  450.45  5029.1  451.63  5099.2  451.63
  5127.8  452.39  5199.3  452.65  5269.4  454.14  5319.5  454.12  5349.5  453.52
  5359.5  454.07  5409.6  453.33  5555.7  454.99  5589.8  456.14  5651.8  456.10
#Mann=4,-1,0
  4470.0     0.1       0  4526.1    0.08       0  4996.1    0.07       0
  5002.1    0.08       0
Bank Sta=4996.1,5002.1
Exp/Cntr=0.3,0.1

Type RM Length L Ch R = 1,18628,693,693,693
BEGIN DESCRIPTION:
LYNN CREEK 38.0
END DESCRIPTION:
XS GIS Cut Line= 3
      3576042.09     10508291.66      3575892.11     10508441.64
      3575492.12     10509241.61
#Sta/Elev= 30
  4815.5  462.65  4843.8  461.60  4851.1  459.76  4860.1  457.36  4872.0  453.69
  4951.8  448.23  4971.0  446.74  4985.2  441.97  4996.3  439.50  4999.1  439.00
  5002.3  439.50  5024.1  445.31  5137.3  443.30  5290.9  444.71  5349.0  444.28
  5399.4  445.21  5466.4  445.05  5505.6  445.94  5595.0  445.76  5676.1  446.96
  5801.8  445.37  5832.6  447.11  5841.0  450.93  5846.6  450.67  5855.0  454.59
  5865.0  455.88  5885.7  455.81  5913.7  454.62  5919.2  459.27  5922.0  459.27
#Mann=9,-1,0
  4815.5     0.1       0  4851.1    0.08       0  4860.1    0.05       0
  4951.8    0.08       0  4996.3    0.07       0  5002.3    0.08       0
  5137.3    0.05       0  5290.9    0.08       0  5865.0     0.1       0
Bank Sta=4996.3,5002.3
Exp/Cntr=0.3,0.1

Type RM Length L Ch R = 1,17935,706,706,706
BEGIN DESCRIPTION:
LYNN CREEK 37.0
END DESCRIPTION:
XS GIS Cut Line= 2
      3575478.05     10507837.96      3574562.99     10509147.66
#Sta/Elev= 30
  4832.4  455.56  4868.2  454.51  4903.9  446.92  4969.4  442.92  4990.3  435.08
  5002.1  434.33  5004.9  433.83  5008.1  434.33  5032.1  443.69  5077.2  443.97
  5091.5  444.55  5118.5  438.72  5259.3  438.58  5275.2  438.50  5493.3  440.62
  5507.6  440.99  5641.1  444.25  5824.0  449.32  6117.3  456.69  6145.9  454.33
  6160.8  456.51  6190.4  454.56  6196.5  451.90  6211.3  453.88  6217.4  450.42
  6247.1  451.05  6268.0  455.84  6310.5  473.34  6419.8  518.70  6430.1  525.39
#Mann=12,-1,0
  4832.4    0.08       0  5002.1    0.07       0  5008.1    0.08       0
  5077.2     0.1       0  5259.3    0.08       0  5275.2     0.1       0
  5493.3    0.08       0  5507.6     0.1       0  5641.1    0.08       0
  5824.0     0.1       0  6117.3    0.15       0  6310.5     0.1       0
Bank Sta=5002.1,5008.1
Exp/Cntr=0.3,0.1

Type RM Length L Ch R = 1,17229,1131,1131,1131
BEGIN DESCRIPTION:
LYNN CREEK 35.0
END DESCRIPTION:
XS GIS Cut Line= 2
      3574944.19     10507373.55      3573998.03     10508714.68
#Sta/Elev= 30
  4798.4  446.25  4856.9  446.54  4898.8  438.91  4950.3  437.03  4970.2  435.36
  4988.9  428.99  4991.6  428.49  4994.9  428.99  5014.5  430.30  5035.5  440.90
  5053.6  441.76  5106.9  441.48  5132.0  438.73  5151.0  439.29  5236.6  461.22
  5313.6  460.54  5404.1  462.34  5520.9  463.84  5764.7  469.91  5853.1  468.53
  5988.3  470.99  6040.2  472.53  6105.1  475.88  6275.3  487.18  6334.6  490.55
  6349.4  501.32  6376.4  527.26  6391.2  535.86  6420.8  535.09  6439.7  537.73
#Mann=14,-1,0
  4798.4    0.08       0  4950.3     0.1       0  4988.9    0.07       0
  4994.9     0.1       0  5053.6    0.15       0  5132.0    0.08       0
  5313.6     0.1       0  5404.1    0.08       0  5520.9     0.1       0
  5764.7    0.08       0  5988.3    0.15       0  6040.2     0.1       0
  6105.1    0.15       0  6275.3     0.1       0
Bank Sta=4988.9,4994.9
Exp/Cntr=0.3,0.1

Type RM Length L Ch R = 1,16098,54,54,54
BEGIN DESCRIPTION:
LYNN CREEK 33.03
END DESCRIPTION:
XS GIS Cut Line= 2
      3574050.07     10506653.10      3573321.92     10507888.36
#Sta/Elev= 30
  4790.0  439.58  4859.3  440.21  4927.6  435.82  4958.3  430.99  4989.1  421.47
  4991.9  420.97  4995.1  421.47  5050.7  427.13  5136.5  429.72  5173.6  437.97
  5210.7  439.68  5386.4  443.14  5402.0  440.81  5407.8  436.65  5482.0  435.57
  5487.8  438.04  5503.5  438.48  5509.3  443.79  5519.1  444.10  5524.9  449.20
  5540.6  449.61  5546.4  453.42  5567.8  456.34  5602.5  455.92  5833.0  463.49
  5867.9  460.19  6005.6  462.38  6153.4  465.47  6190.5  471.98  6223.9  472.85
#Mann=6,-1,0
  4790.0     0.1       0  4958.3    0.08       0  4989.1    0.07       0
  4995.1    0.08       0  5602.5     0.1       0  6005.6    0.15       0
Bank Sta=4989.1,4995.1
Exp/Cntr=0.3,0.1

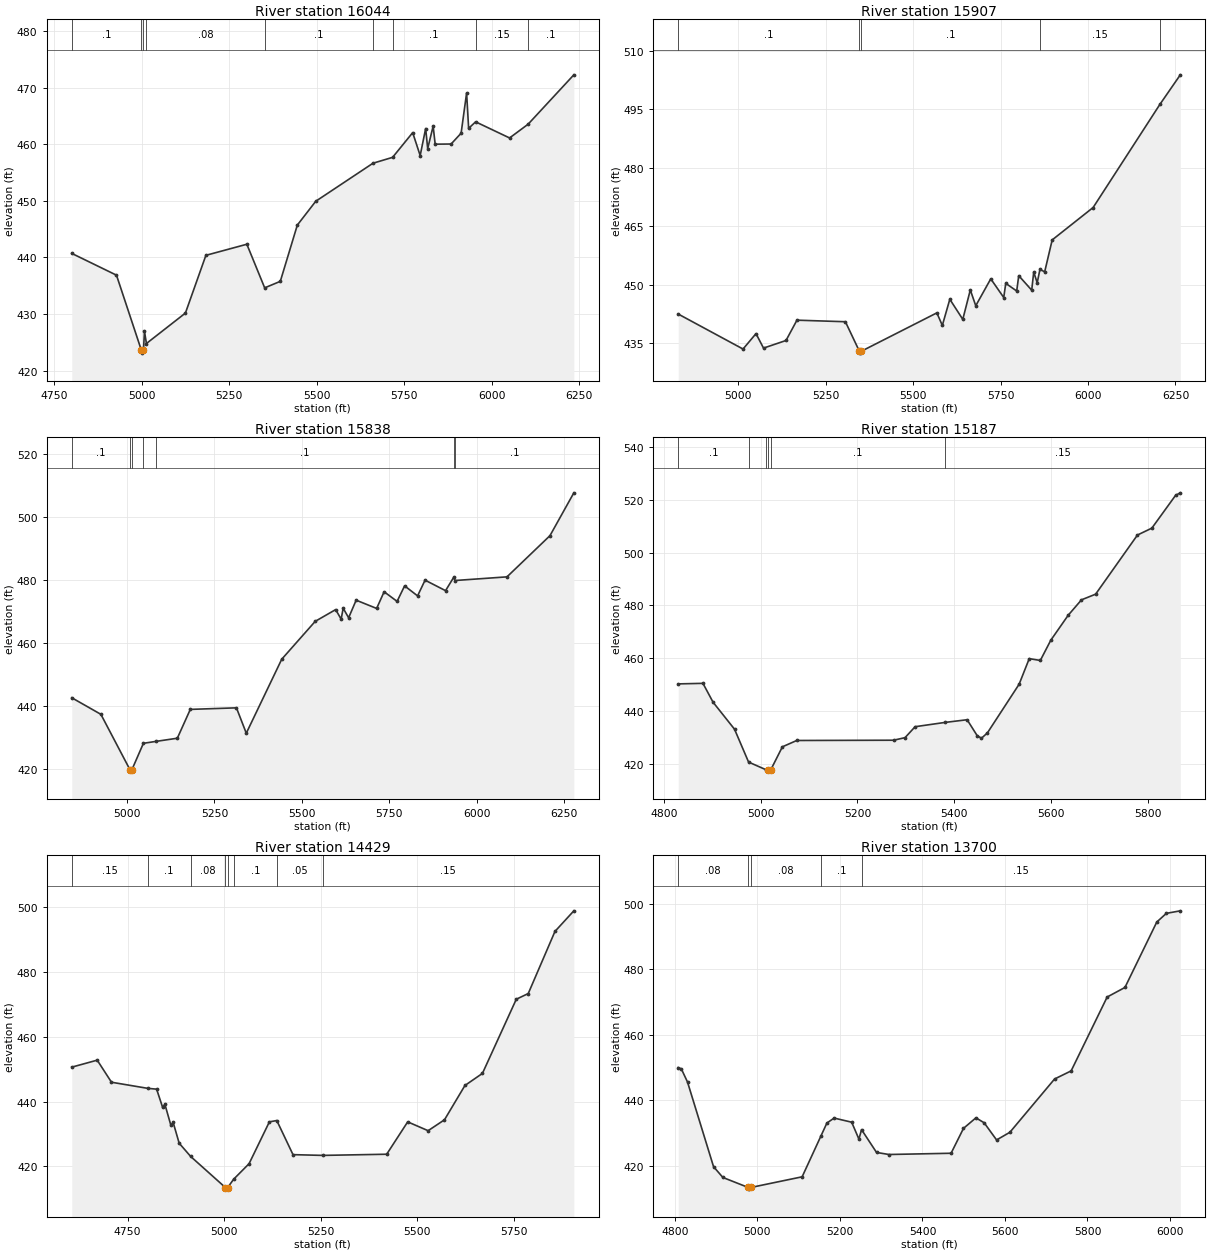
Type RM Length L Ch R = 1,16044,137,137,137
BEGIN DESCRIPTION:
LYNN CREEK 33.0
END DESCRIPTION:
XS GIS Cut Line= 2
      3574002.36     10506627.01      3573273.19     10507863.99
#Sta/Elev= 30
  4799.4  440.71  4927.3  436.86  4998.5  423.58  5001.2  423.08  5004.5  423.58
  5007.3  426.95  5012.9  424.78  5124.4  430.16  5183.0  440.37  5300.1  442.33
  5351.1  434.62  5395.8  435.77  5444.5  445.72  5497.2  449.93  5660.8  456.65
  5716.9  457.69  5774.4  462.06  5795.8  458.01  5811.5  462.79  5817.3  459.24
  5832.9  463.21  5838.7  460.02  5884.3  460.05  5912.9  461.96  5928.6  469.07
  5934.4  462.82  5954.4  463.97  6051.5  461.12  6104.5  463.55  6235.3  472.28
#Mann=9,-1,0
  4799.4     0.1       0  4998.5    0.07       0  5004.5     0.1       0
  5012.9    0.08       0  5351.1     0.1       0  5660.8    0.15       0
  5716.9     0.1       0  5954.4    0.15       0  6104.5     0.1       0
Bank Sta=4998.5,5004.5
Exp/Cntr=0.3,0.1

Type RM Length L Ch R = 1,15907,69,69,69
BEGIN DESCRIPTION:
LYNN CREEK 33.01
END DESCRIPTION:
XS GIS Cut Line= 2
      3573880.80     10506566.30      3573151.63     10507803.28
#Sta/Elev= 30
  4827.9  442.52  5013.2  433.55  5050.3  437.50  5071.8  433.79  5136.1  435.74
  5167.4  440.95  5306.0  440.55  5345.9  433.00  5348.7  432.50  5351.9  433.00
  5567.5  442.82  5583.2  439.60  5604.6  446.31  5641.7  441.16  5663.2  448.70
  5678.8  444.65  5721.7  451.55  5758.8  446.76  5764.6  450.39  5795.9  448.43
  5801.7  452.36  5838.8  448.64  5844.6  453.30  5854.5  450.53  5862.4  453.98
  5875.9  453.34  5897.4  461.53  6014.5  469.84  6205.4  496.28  6263.8  503.86
#Mann=5,-1,0
  4827.9     0.1       0  5345.9    0.07       0  5351.9     0.1       0
  5862.4    0.15       0  6205.4     0.1       0
Bank Sta=5345.9,5351.9
Exp/Cntr=0.3,0.1

Type RM Length L Ch R = 1,15838,651,651,651
BEGIN DESCRIPTION:
LYNN CREEK 33.02
END DESCRIPTION:
XS GIS Cut Line= 2
      3573820.05     10506535.90      3573090.88     10507772.88
#Sta/Elev= 30
  4842.1  442.75  4925.4  437.49  5008.3  419.97  5011.0  419.47  5014.3  419.97
  5047.0  428.30  5083.9  428.92  5144.0  429.91  5181.1  439.06  5313.1  439.55
  5341.2  431.50  5442.6  454.98  5538.3  466.99  5596.8  470.72  5612.5  467.69
  5618.3  471.15  5633.9  468.13  5655.4  473.71  5714.0  471.09  5735.4  476.38
  5772.5  473.33  5794.0  478.25  5831.1  475.07  5852.5  480.06  5911.1  476.73
  5934.1  480.91  5938.3  479.95  6086.8  481.11  6209.7  494.18  6278.0  507.77
#Mann=7,-1,0
  4842.1     0.1       0  5008.3    0.07       0  5014.3     0.1       0
  5047.0    0.08       0  5083.9     0.1       0  5934.1    0.15       0
  5938.3     0.1       0
Bank Sta=5008.3,5014.3
Exp/Cntr=0.3,0.1

Type RM Length L Ch R = 1,15187,758,758,758
BEGIN DESCRIPTION:
LYNN CREEK 31.0
END DESCRIPTION:
XS GIS Cut Line= 2
      3573326.99     10506125.89      3572736.93     10506979.74
#Sta/Elev= 30
  4829.6  450.28  4880.7  450.49  4901.6  443.34  4946.0  433.10  4975.0  420.66
  5010.8  417.78  5014.9  417.73  5017.6  417.23  5020.9  417.73  5044.9  426.44
  5074.6  428.84  5274.7  428.94  5298.4  429.91  5319.3  434.06  5381.0  435.68
  5426.8  436.70  5447.7  430.64  5456.5  429.70  5468.7  431.71  5534.3  450.16
  5555.2  459.85  5578.1  459.16  5599.8  466.84  5635.7  476.28  5663.2  482.13
  5692.4  484.27  5778.9  506.68  5808.7  509.30  5857.7  521.71  5867.5  522.67
#Mann=6,-1,0
  4829.6     0.1       0  4975.0    0.08       0  5010.8     0.1       0
  5014.9    0.07       0  5020.9     0.1       0  5381.0    0.15       0
Bank Sta=5014.9,5020.9
Exp/Cntr=0.3,0.1

Type RM Length L Ch R = 1,14429,729,729,729
BEGIN DESCRIPTION:
LYNN CREEK 29.0
END DESCRIPTION:
XS GIS Cut Line= 3
      3572829.37     10505467.68      3572542.90     10505949.48
      3572297.92     10506647.82
#Sta/Elev= 30
  4605.4  450.66  4671.3  452.82  4708.3  446.00  4801.9  444.12  4825.2  443.86
  4840.8  438.22  4846.6  439.19  4862.2  432.67  4868.0  433.61  4883.6  427.17
  4913.4  423.07  5003.3  413.48  5006.0  412.98  5009.3  413.48  5024.9  416.06
  5064.7  420.84  5117.3  433.76  5136.5  434.17  5178.5  423.63  5255.8  423.40
  5421.2  423.76  5475.6  433.76  5528.5  431.03  5570.9  434.40  5623.9  445.00
  5669.2  448.73  5756.9  471.64  5787.9  473.40  5857.1  492.59  5906.0  498.95
#Mann=8,-1,0
  4605.4    0.15       0  4801.9     0.1       0  4913.4    0.08       0
  5003.3    0.07       0  5009.3    0.08       0  5024.9     0.1       0
  5136.5    0.05       0  5255.8    0.15       0
Bank Sta=5003.3,5009.3
Exp/Cntr=0.3,0.1

Type RM Length L Ch R = 1,13700,340,340,340
BEGIN DESCRIPTION:
LYNN CREEK 27.0
END DESCRIPTION:
XS GIS Cut Line= 4
      3572142.11     10505341.64      3571992.11     10505441.64
      3571992.11     10505641.64      3571922.52     10506475.36
#Sta/Elev= 30
  4808.1  449.96  4815.6  449.57  4830.6  445.54  4893.7  419.71  4916.3  416.42
  4977.9  413.36  4980.6  412.86  4983.9  413.36  5108.4  416.62  5154.3  429.17
  5168.4  433.03  5185.9  434.55  5228.5  433.29  5246.0  428.13  5252.4  431.02
  5288.7  424.06  5318.8  423.43  5469.4  423.81  5499.5  431.41  5529.6  434.62
  5549.6  433.11  5579.7  427.87  5612.0  430.22  5720.2  446.47  5760.4  448.95
  5847.7  471.50  5890.8  474.42  5968.0  494.39  5991.2  497.04  6025.0  497.81
#Mann=5,-1,0
  4808.1    0.08       0  4977.9    0.07       0  4983.9    0.08       0
  5154.3     0.1       0  5252.4    0.15       0
Bank Sta=4977.9,4983.9
Exp/Cntr=0.3,0.1

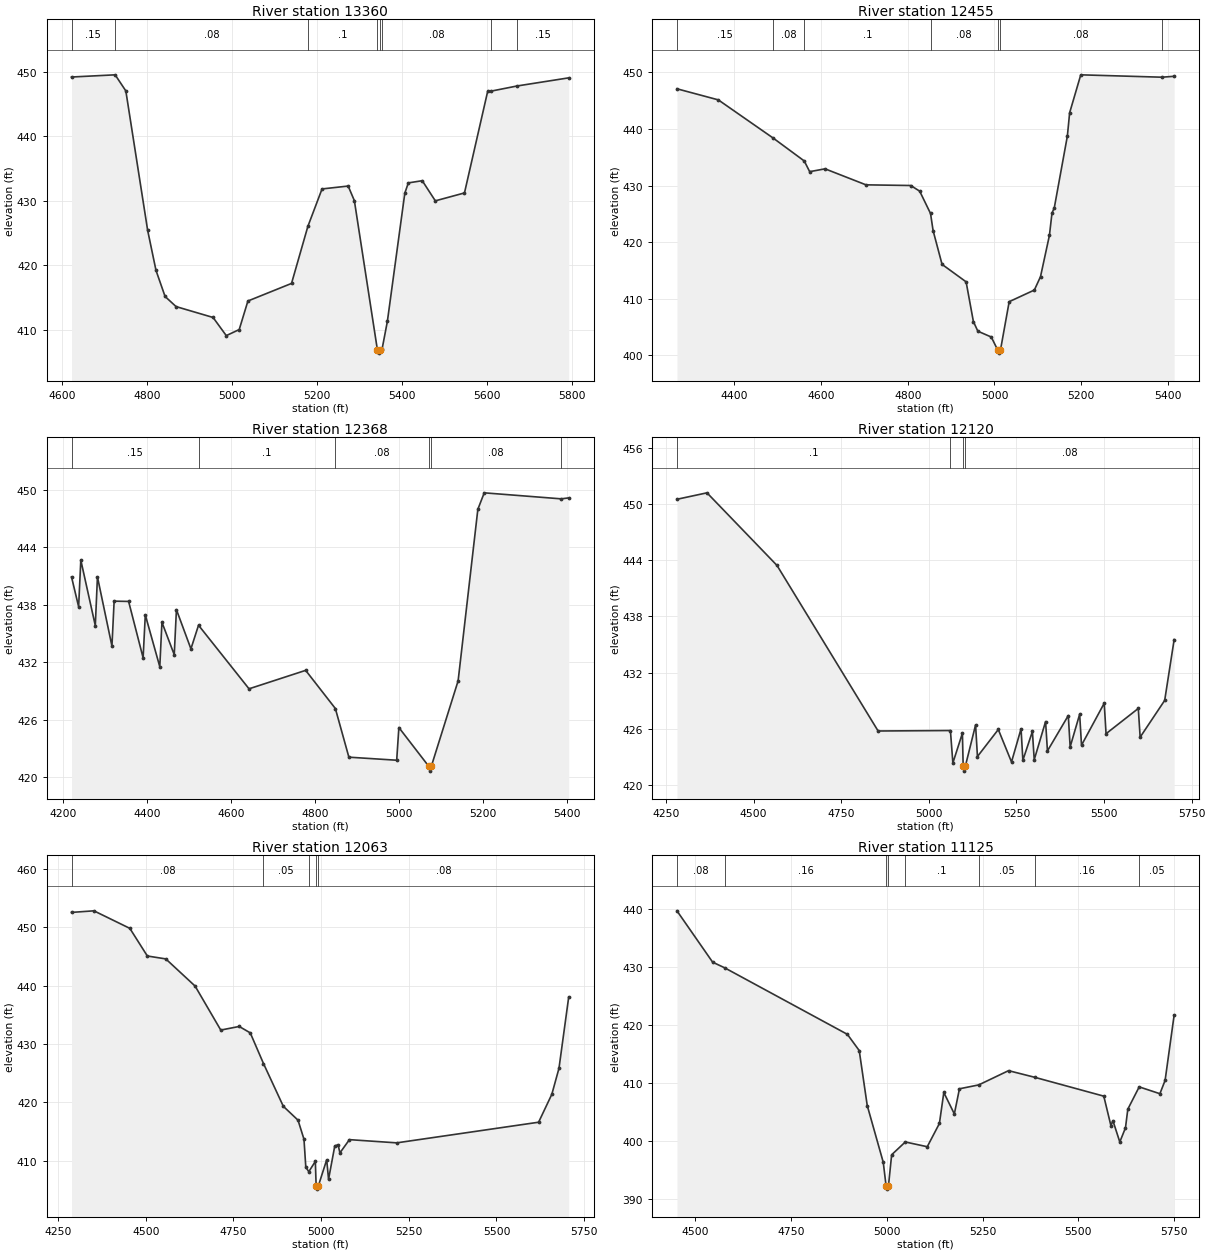
Type RM Length L Ch R = 1,13360,905,905,905
BEGIN DESCRIPTION:
LYNN CREEK 26.0
END DESCRIPTION:
XS GIS Cut Line= 3
      3572156.62     10505159.54      3571883.17     10505224.65
      3571016.09     10505020.89
#Sta/Elev= 30
  4621.4  449.24  4724.2  449.58  4749.4  447.08  4800.8  425.42  4820.5  419.19
  4841.9  415.14  4867.8  413.57  4955.0  411.88  4986.1  409.06  5016.6  410.00
  5037.1  414.44  5139.9  417.17  5178.4  426.03  5211.8  431.85  5273.4  432.30
  5288.0  430.03  5342.3  406.84  5345.1  406.34  5348.3  406.84  5353.5  407.03
  5365.8  411.28  5406.9  431.20  5415.2  432.79  5448.0  433.13  5478.8  430.00
  5547.5  431.23  5602.1  446.99  5609.0  447.03  5671.7  447.85  5793.2  449.11
#Mann=8,-1,0
  4621.4    0.15       0  4724.2    0.08       0  5178.4     0.1       0
  5342.3    0.07       0  5348.3     0.1       0  5353.5    0.08       0
  5609.0     0.1       0  5671.7    0.15       0
Bank Sta=5342.3,5348.3
Exp/Cntr=0.3,0.1

Type RM Length L Ch R = 1,12455,87,87,87
BEGIN DESCRIPTION:
LYNN CREEK 25.0
END DESCRIPTION:
XS GIS Cut Line= 2
      3572274.53     10504622.88      3571163.46     10504336.44
#Sta/Elev= 30
  4267.3  447.11  4362.7  445.15  4489.8  438.37  4561.1  434.34  4573.6  432.45
  4609.1  432.95  4703.5  430.12  4806.8  430.00  4827.5  429.00  4852.5  425.05
  4858.4  422.03  4879.1  416.05  4934.6  412.96  4951.4  405.94  4961.7  404.23
  4992.7  403.20  5007.8  400.85  5010.5  400.35  5013.8  400.85  5034.0  409.45
  5092.1  411.51  5106.3  413.88  5126.9  421.19  5132.8  425.14  5138.0  426.01
  5168.3  438.76  5173.5  442.86  5199.2  449.58  5386.4  449.16  5414.7  449.32
#Mann=7,-1,0
  4267.3    0.15       0  4489.8    0.08       0  4561.1     0.1       0
  4852.5    0.08       0  5007.8    0.07       0  5013.8    0.08       0
  5386.4     0.1       0
Bank Sta=5007.8,5013.8
Exp/Cntr=0.3,0.1

Type RM Length L Ch R = 1,12368,248,248,248
BEGIN DESCRIPTION:
LYNN CREEK 23.02
END DESCRIPTION:
XS GIS Cut Line= 2
      3572339.65     10504562.12      3571198.15     10504249.62
#Sta/Elev= 30
  4220.8  440.91  4237.7  437.80  4242.9  442.67  4277.4  435.82  4282.5  440.92
  4317.0  433.68  4322.2  438.38  4356.7  438.35  4391.2  432.45  4396.4  436.94
  4430.9  431.52  4436.0  436.17  4465.3  432.78  4470.5  437.49  4505.0  433.39
  4523.1  435.86  4643.3  429.21  4778.1  431.14  4848.8  427.15  4881.0  422.06
  4994.8  421.74  5000.0  425.16  5071.2  421.10  5073.9  420.60  5077.2  421.10
  5141.0  430.04  5188.0  447.99  5203.2  449.71  5386.4  449.08  5404.3  449.18
#Mann=6,-1,0
  4220.8    0.15       0  4523.1     0.1       0  4848.8    0.08       0
  5071.2    0.07       0  5077.2    0.08       0  5386.4     0.1       0
Bank Sta=5071.2,5077.2
Exp/Cntr=0.3,0.1

Type RM Length L Ch R = 1,12120,57,57,57
BEGIN DESCRIPTION:
LYNN CREEK 23.0
END DESCRIPTION:
XS GIS Cut Line= 2
      3572339.62     10504332.08      3570986.31     10503907.00
#Sta/Elev= 30
  4281.6  450.53  4367.3  451.22  4567.0  443.46  4855.5  425.76  5061.8  425.81
  5068.8  422.34  5096.0  425.52  5098.2  421.97  5101.0  421.47  5104.2  421.97
  5133.6  426.41  5138.9  423.03  5198.4  425.92  5236.1  422.45  5263.3  425.99
  5268.5  422.63  5295.7  425.71  5300.9  422.69  5333.3  426.77  5338.6  423.63
  5398.1  427.41  5403.4  424.06  5430.5  427.55  5435.8  424.24  5500.6  428.73
  5505.8  425.47  5597.8  428.17  5603.1  425.10  5673.1  429.03  5700.1  435.53
#Mann=4,-1,0
  4281.6     0.1       0  5061.8    0.08       0  5098.2    0.07       0
  5104.2    0.08       0
Bank Sta=5098.2,5104.2
Exp/Cntr=0.3,0.1

Type RM Length L Ch R = 1,12063,938,938,938
BEGIN DESCRIPTION:
LYNN CREEK 23.01
END DESCRIPTION:
XS GIS Cut Line= 2
      3572348.35     10504275.67      3570995.61     10503850.77
#Sta/Elev= 30
  4288.2  452.59  4352.0  452.86  4454.5  449.85  4504.4  445.11  4557.0  444.61
  4640.6  439.95  4713.8  432.40  4766.4  433.02  4797.9  431.92  4835.6  426.66
  4892.2  419.32  4934.1  416.94  4951.1  413.67  4956.3  408.89  4964.8  408.10
  4983.5  409.87  4985.8  405.61  4988.5  405.11  4991.8  405.61  5015.9  410.15
  5021.2  406.80  5038.9  412.51  5048.3  412.73  5053.6  411.33  5080.7  413.60
  5215.6  413.05  5620.2  416.59  5657.9  421.38  5678.3  425.84  5706.1  438.10
#Mann=5,-1,0
  4288.2    0.08       0  4835.6    0.05       0  4964.8    0.08       0
  4985.8    0.07       0  4991.8    0.08       0
Bank Sta=4985.8,4991.8
Exp/Cntr=0.3,0.1

Type RM Length L Ch R = 1,11125,701,701,701
BEGIN DESCRIPTION:
LYNN CREEK 21.0
END DESCRIPTION:
XS GIS Cut Line= 3
      3572273.80     10502906.94      3571896.20     10503132.64
      3571076.54     10503384.17
#Sta/Elev= 30
  4452.7  439.70  4545.8  430.84  4577.6  429.85  4897.4  418.38  4928.3  415.58
  4949.2  406.09  4991.0  396.29  4998.5  392.16  5001.2  391.66  5004.5  392.16
  5012.9  397.59  5048.5  399.80  5105.8  398.98  5137.5  402.99  5149.0  408.34
  5176.5  404.64  5189.8  408.98  5240.1  409.65  5317.9  412.11  5385.9  410.97
  5566.4  407.71  5585.0  402.62  5590.2  403.48  5608.2  399.80  5623.0  402.24
  5629.1  405.46  5658.8  409.31  5712.8  408.13  5726.4  410.43  5750.0  421.71
#Mann=8,-1,0
  4452.7    0.08       0  4577.6    0.16       0  4998.5    0.07       0
  5004.5    0.16       0  5048.5     0.1       0  5240.1    0.05       0
  5385.9    0.16       0  5658.8    0.05       0
Bank Sta=4998.5,5004.5
Exp/Cntr=0.3,0.1

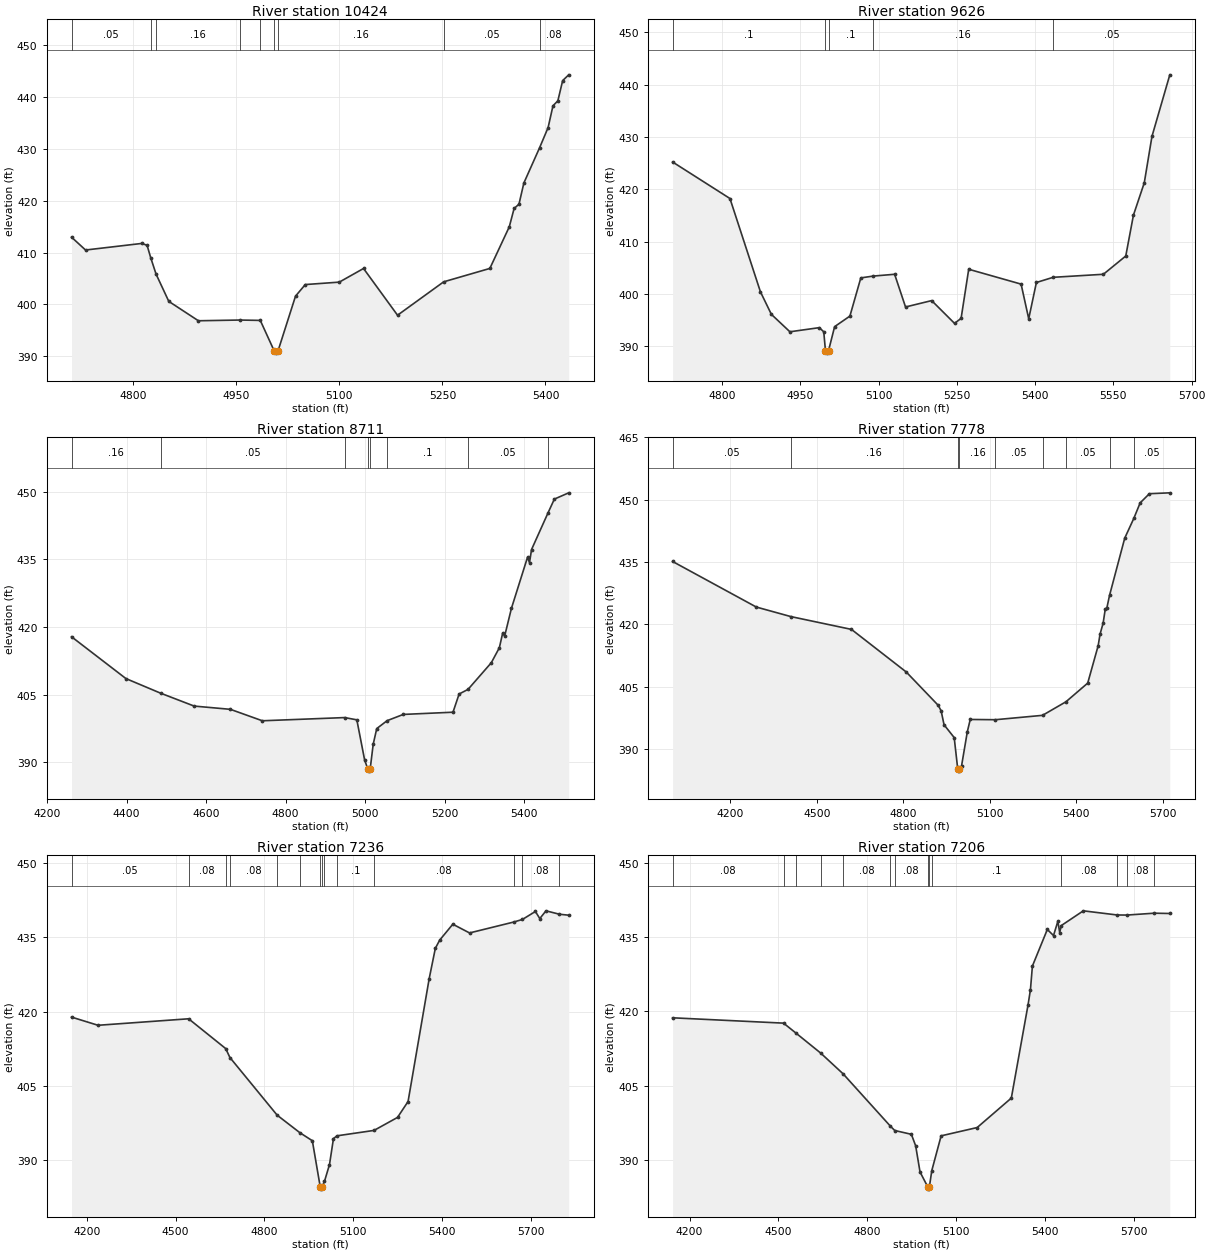
Type RM Length L Ch R = 1,10424,798,798,798
BEGIN DESCRIPTION:
LYNN CREEK 20.0
END DESCRIPTION:
XS GIS Cut Line= 3
      3571499.19     10502601.11      3571349.23     10502651.10
      3570949.20     10503051.12
#Sta/Elev= 30
  4710.0  412.98  4730.4  410.50  4812.3  411.77  4820.0  411.41  4825.3  409.01
  4833.1  405.85  4851.6  400.60  4894.7  396.86  4954.7  397.00  4984.8  396.93
  5004.8  391.12  5007.6  390.62  5010.8  391.12  5036.1  401.61  5050.3  403.84
  5099.8  404.31  5135.1  406.94  5184.6  397.93  5251.8  404.37  5319.0  406.95
  5347.3  414.98  5354.3  418.51  5361.4  419.34  5368.5  423.42  5391.3  430.19
  5403.8  434.11  5410.9  438.31  5418.0  439.27  5425.0  443.17  5433.8  444.28
#Mann=9,-1,0
  4710.0    0.05       0  4825.3     0.1       0  4833.1    0.16       0
  4954.7    0.05       0  4984.8    0.16       0  5004.8    0.07       0
  5010.8    0.16       0  5251.8    0.05       0  5391.3    0.08       0
Bank Sta=5004.8,5010.8
Exp/Cntr=0.3,0.1

Type RM Length L Ch R = 1,9626,915,915,915
BEGIN DESCRIPTION:
LYNN CREEK 18.0
END DESCRIPTION:
XS GIS Cut Line= 2
      3570967.78     10502013.18      3570199.47     10502576.85
#Sta/Elev= 30
  4705.2  425.24  4815.1  418.26  4873.5  400.43  4894.5  396.12  4930.0  392.79
  4986.4  393.58  4994.9  392.78  4998.1  389.21  5000.8  388.71  5004.1  389.21
  5015.7  393.77  5045.0  395.79  5065.9  403.09  5090.0  403.44  5130.7  403.78
  5151.6  397.53  5201.7  398.75  5245.5  394.40  5258.1  395.35  5272.7  404.74
  5373.1  401.90  5387.7  395.28  5402.4  402.21  5434.5  403.20  5530.8  403.78
  5573.7  407.27  5588.4  415.08  5609.2  421.27  5623.9  430.13  5658.1  441.90
#Mann=5,-1,0
  4705.2     0.1       0  4998.1    0.07       0  5004.1     0.1       0
  5090.0    0.16       0  5434.5    0.05       0
Bank Sta=4998.1,5004.1
Exp/Cntr=0.3,0.1

Type RM Length L Ch R = 1,8711,933,933,933
BEGIN DESCRIPTION:
LYNN CREEK 16.0
END DESCRIPTION:
XS GIS Cut Line= 3
      3570993.66     10501198.40      3570218.16     10501486.03
      3569799.75     10501552.00
#Sta/Elev= 30
  4261.7  417.85  4398.6  408.57  4485.6  405.34  4570.2  402.47  4661.3  401.75
  4741.7  399.21  4948.7  399.92  4979.4  399.42  4999.1  390.47  5007.0  388.54
  5009.7  388.04  5013.0  388.54  5020.6  394.01  5029.5  397.48  5055.7  399.24
  5096.4  400.62  5221.3  401.11  5236.7  405.15  5259.1  406.17  5317.7  412.09
  5337.9  415.41  5346.3  418.66  5351.3  418.02  5368.3  424.15  5408.8  435.49
  5413.8  434.29  5418.9  437.20  5460.5  445.36  5476.3  448.39  5512.4  449.78
#Mann=8,-1,0
  4261.7    0.16       0  4485.6    0.05       0  4948.7    0.16       0
  5007.0    0.07       0  5013.0    0.16       0  5055.7     0.1       0
  5259.1    0.05       0  5460.5     0.1       0
Bank Sta=5007,5013
Exp/Cntr=0.3,0.1

Type RM Length L Ch R = 1,7778,542,542,542
BEGIN DESCRIPTION:
LYNN CREEK 14.0
END DESCRIPTION:
XS GIS Cut Line= 4
      3571442.22     10500834.03      3570608.87     10500806.25
      3570247.76     10500858.33      3569755.88     10501045.38
#Sta/Elev= 30
  3999.9  435.14  4290.2  424.18  4410.3  421.88  4620.4  418.80  4810.5  408.55
  4921.4  400.53  4931.5  399.20  4941.6  395.85  4976.8  392.77  4989.1  385.20
  4991.8  384.70  4995.1  385.20  5002.2  385.91  5022.4  394.20  5032.5  397.13
  5119.7  397.07  5283.2  398.12  5364.6  401.39  5440.0  405.88  5476.3  414.88
  5482.8  417.65  5493.5  420.31  5501.0  423.72  5506.4  423.95  5515.7  426.98
  5568.4  440.75  5600.2  445.55  5621.9  449.24  5654.0  451.45  5724.8  451.66
#Mann=9,-1,0
  3999.9    0.05       0  4410.3    0.16       0  4989.1    0.07       0
  4995.1    0.16       0  5119.7    0.05       0  5283.2    0.08       0
  5364.6    0.05       0  5515.7    0.08       0  5600.2    0.05       0
Bank Sta=4989.1,4995.1
Exp/Cntr=0.3,0.1

Type RM Length L Ch R = 1,7236,30,30,30
BEGIN DESCRIPTION:
LYNN CREEK 12.03
END DESCRIPTION:
XS GIS Cut Line= 4
      3570819.58     10499934.30      3570166.41     10500403.02
      3570014.50     10500511.53      3569455.81     10500912.13
#Sta/Elev= 30
  4148.8  418.91  4238.3  417.26  4544.0  418.57  4669.2  412.56  4683.4  410.76
  4842.9  399.13  4919.7  395.59  4961.6  393.98  4988.1  384.72  4990.8  384.22
  4994.1  384.72  5002.6  385.79  5019.5  389.18  5032.9  394.41  5044.8  394.97
  5169.8  396.06  5249.1  398.68  5284.7  401.89  5355.9  426.64  5376.8  432.79
  5391.5  434.44  5435.7  437.64  5492.2  435.88  5641.4  438.08  5670.6  438.60
  5714.5  440.21  5729.3  438.78  5750.2  440.34  5795.8  439.65  5826.9  439.46
#Mann=14,-1,0
  4148.8    0.05       0  4544.0    0.08       0  4669.2     0.1       0
  4683.4    0.08       0  4842.9    0.05       0  4919.7    0.08       0
  4988.1    0.07       0  4994.1    0.08       0  5002.6    0.05       0
  5044.8     0.1       0  5169.8    0.08       0  5641.4     0.1       0
  5670.6    0.08       0  5795.8     0.1       0
Bank Sta=4988.1,4994.1
Exp/Cntr=0.3,0.1

Type RM Length L Ch R = 1,7206,106,106,106
BEGIN DESCRIPTION:
LYNN CREEK 12.02
END DESCRIPTION:
XS GIS Cut Line= 4
      3570804.44     10499908.22      3570151.21     10500376.98
      3569999.30     10500485.48      3569439.62     10500886.81
#Sta/Elev= 30
  4142.8  418.72  4517.5  417.64  4559.3  415.63  4642.8  411.58  4718.8  407.36
  4878.4  396.76  4893.2  395.88  4949.3  395.11  4963.8  392.77  4978.5  387.48
  5004.2  384.50  5006.9  384.00  5010.2  384.50  5018.3  387.77  5049.8  394.80
  5171.5  396.48  5286.9  402.45  5343.4  421.35  5351.5  424.43  5358.1  429.21
  5408.5  436.62  5429.4  435.39  5444.1  438.28  5450.3  435.99  5455.6  437.41
  5530.1  440.40  5644.1  439.56  5676.9  439.54  5769.3  439.92  5822.2  439.86
#Mann=14,-1,0
  4142.8    0.08       0  4517.5     0.1       0  4559.3    0.08       0
  4642.8     0.1       0  4718.8    0.08       0  4878.4    0.05       0
  4893.2    0.08       0  5004.2    0.07       0  5010.2    0.08       0
  5018.3     0.1       0  5455.6    0.08       0  5644.1     0.1       0
  5676.9    0.08       0  5769.3     0.1       0
Bank Sta=5004.2,5010.2
Exp/Cntr=0.3,0.1

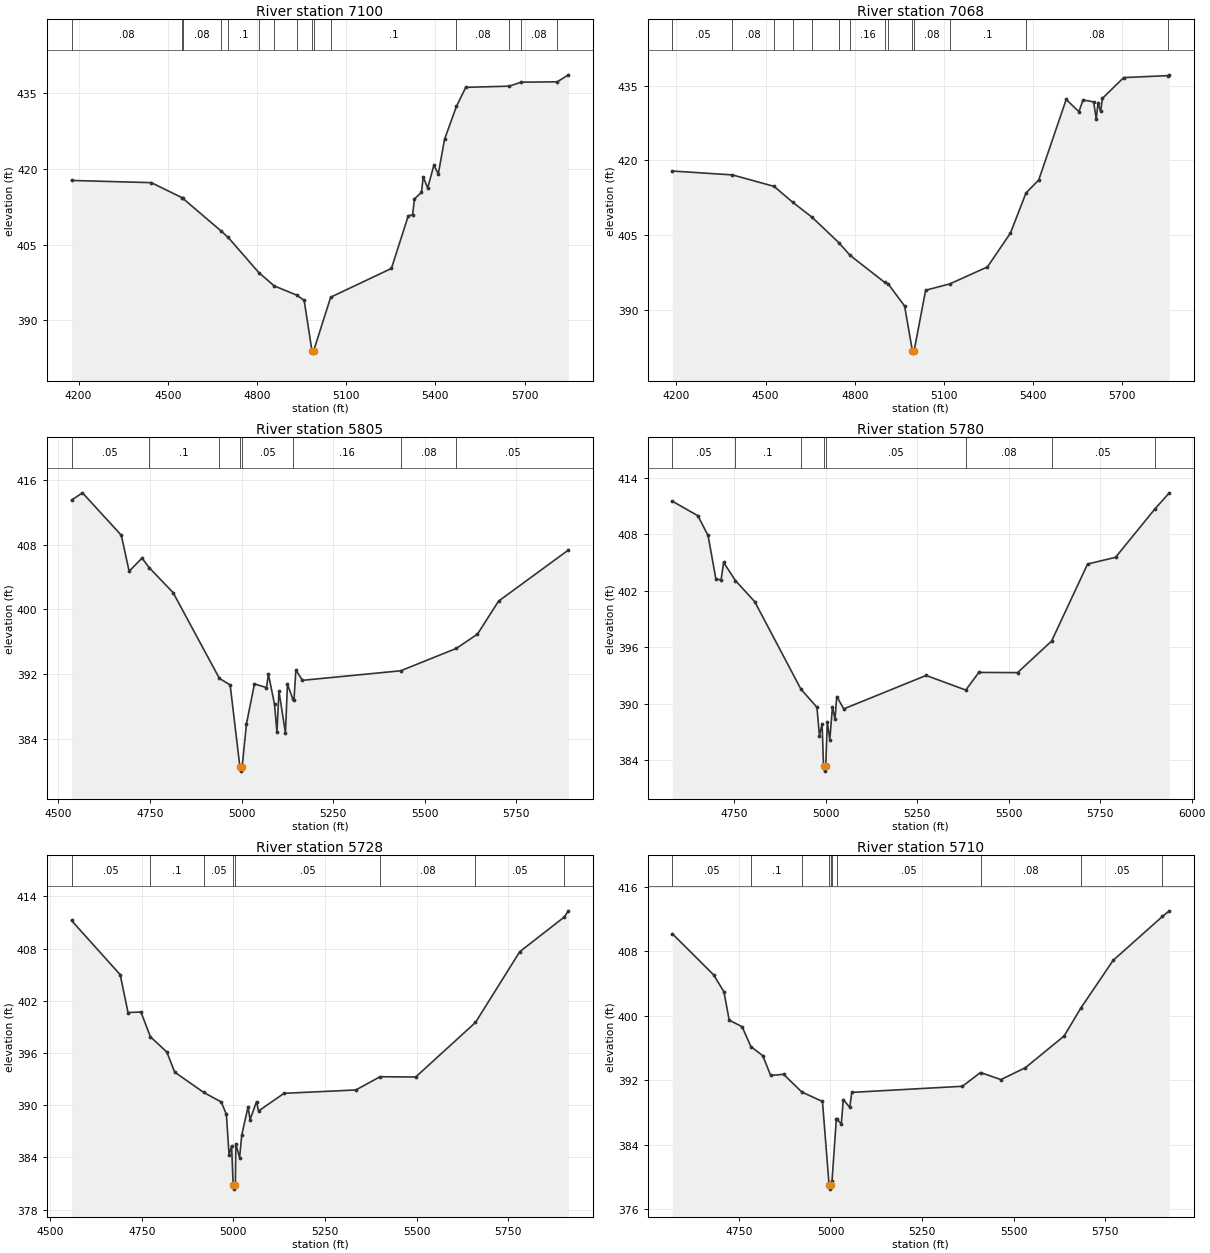
Type RM Length L Ch R = 1,7100,32,32,32
BEGIN DESCRIPTION:
LYNN CREEK 12.0
END DESCRIPTION:
XS GIS Cut Line= 3
      3570702.39     10499825.79      3569827.86     10500487.65
      3569357.61     10500817.05
#Sta/Elev= 30
  4176.5  417.72  4444.8  417.28  4548.9  414.27  4550.6  414.18  4678.4  407.74
  4703.5  406.40  4806.2  399.44  4858.0  396.80  4934.0  394.96  4958.7  393.93
  4984.8  383.96  4987.6  383.46  4990.8  383.96  5047.9  394.56  5252.1  400.26
  5308.6  410.68  5323.4  410.94  5329.5  414.06  5353.0  415.33  5359.1  418.40
  5374.0  416.23  5394.9  420.73  5409.7  419.01  5430.6  425.85  5470.5  432.39
  5502.1  436.19  5647.9  436.42  5688.5  437.21  5809.8  437.29  5847.4  438.67
#Mann=15,-1,0
  4176.5    0.08       0  4548.9     0.1       0  4550.6    0.08       0
  4678.4    0.16       0  4703.5     0.1       0  4806.2    0.16       0
  4858.0     0.1       0  4934.0    0.08       0  4984.8    0.07       0
  4990.8    0.08       0  5047.9     0.1       0  5470.5    0.08       0
  5647.9     0.1       0  5688.5    0.08       0  5809.8     0.1       0
Bank Sta=4984.8,4990.8
Exp/Cntr=0.3,0.1

Type RM Length L Ch R = 1,7068,1263,1263,1263
BEGIN DESCRIPTION:
LYNN CREEK 12.01
END DESCRIPTION:
XS GIS Cut Line= 3
      3570678.57     10499804.05      3569803.99     10500465.95
      3569333.04     10500795.83
#Sta/Elev= 30
  4186.2  417.89  4388.4  417.11  4528.4  414.81  4591.4  411.62  4656.2  408.63
  4745.9  403.56  4784.0  401.00  4900.5  395.58  4911.8  395.31  4967.4  390.85
  4993.6  381.91  4996.3  381.41  4999.6  381.91  5038.2  394.01  5119.5  395.28
  5246.2  398.68  5323.6  405.47  5375.8  413.49  5418.6  416.08  5511.0  432.22
  5553.9  429.78  5567.7  432.14  5603.4  431.74  5612.1  428.33  5618.2  431.55
  5626.9  429.83  5633.0  432.45  5704.5  436.61  5853.8  437.00  5858.0  437.16
#Mann=14,-1,0
  4186.2    0.05       0  4388.4    0.08       0  4528.4    0.16       0
  4591.4    0.08       0  4656.2    0.16       0  4745.9     0.1       0
  4784.0    0.16       0  4900.5     0.1       0  4911.8    0.08       0
  4993.6    0.07       0  4999.6    0.08       0  5119.5     0.1       0
  5375.8    0.08       0  5853.8     0.1       0
Bank Sta=4993.6,4999.6
Exp/Cntr=0.3,0.1

Type RM Length L Ch R = 1,5805,25,25,25
BEGIN DESCRIPTION:
LYNN CREEK 10.03
END DESCRIPTION:
XS GIS Cut Line= 4
      3569939.69     10499066.81      3569613.30     10499375.84
      3569460.52     10499716.12      3569219.22     10500193.52
#Sta/Elev= 30
  4535.7  413.49  4565.7  414.39  4671.7  409.15  4693.1  404.70  4728.3  406.33
  4747.5  405.16  4813.2  402.06  4939.6  391.46  4969.0  390.65  4995.7  380.50
  4998.4  380.00  5001.7  380.50  5013.5  385.83  5035.4  390.78  5068.2  390.32
  5073.6  391.96  5090.2  388.27  5096.8  384.79  5102.3  389.88  5120.0  384.72
  5125.5  390.73  5140.3  388.91  5143.2  388.76  5148.6  392.51  5166.3  391.22
  5434.8  392.40  5586.5  395.16  5644.5  396.93  5702.2  401.01  5893.1  407.33
#Mann=8,-1,0
  4535.7    0.05       0  4747.5     0.1       0  4939.6    0.05       0
  4995.7   0.035       0  5001.7    0.05       0  5140.3    0.16       0
  5434.8    0.08       0  5586.5    0.05       0
Bank Sta=4995.7,5001.7
Exp/Cntr=0.3,0.1

Type RM Length L Ch R = 1,5780,52,52,52
BEGIN DESCRIPTION:
LYNN CREEK 10.0
END DESCRIPTION:
XS GIS Cut Line= 4
      3569892.80     10499084.19      3569566.43     10499393.20
      3569413.65     10499733.48      3569172.33     10500210.90
#Sta/Elev= 30
  4581.6  411.50  4651.2  409.96  4679.1  407.86  4700.6  403.22  4714.7  403.16
  4721.6  405.00  4753.7  403.08  4806.6  400.83  4932.8  391.54  4976.5  389.62
  4983.3  386.59  4990.6  387.86  4994.5  383.34  4997.2  382.84  5000.5  383.34
  5004.8  388.05  5011.7  386.19  5018.9  389.66  5025.8  388.34  5030.6  390.76
  5049.8  389.45  5274.8  393.00  5383.0  391.45  5418.7  393.32  5524.5  393.30
  5617.4  396.65  5715.7  404.83  5792.0  405.54  5899.4  410.67  5939.0  412.39
#Mann=8,-1,0
  4581.6    0.05       0  4753.7     0.1       0  4932.8    0.05       0
  4994.5   0.035       0  5000.5    0.05       0  5383.0    0.08       0
  5617.4    0.05       0  5899.4    0.08       0
Bank Sta=4994.5,5000.5
Exp/Cntr=0.3,0.1

Type RM Length L Ch R = 1,5728,18,18,18
BEGIN DESCRIPTION:
LYNN CREEK 10.01
END DESCRIPTION:
XS GIS Cut Line= 4
      3569877.17     10499028.63      3569550.80     10499337.64
      3569398.02     10499677.92      3569156.89     10500154.99
#Sta/Elev= 30
  4557.9  411.23  4690.8  405.00  4712.2  400.65  4747.4  400.71  4773.4  397.86
  4818.2  396.11  4839.7  393.80  4918.7  391.47  4966.7  390.37  4980.8  388.94
  4988.1  384.28  4995.0  385.32  4999.3  380.85  5002.0  380.35  5005.3  380.85
  5006.6  385.56  5016.8  383.96  5022.7  386.57  5040.0  389.82  5045.4  388.35
  5063.1  390.40  5068.6  389.33  5138.1  391.36  5334.4  391.75  5400.4  393.27
  5497.7  393.24  5661.0  399.51  5781.8  407.64  5903.2  411.62  5914.9  412.34
#Mann=8,-1,0
  4557.9    0.05       0  4773.4     0.1       0  4918.7    0.05       0
  4999.3   0.035       0  5005.3    0.05       0  5400.4    0.08       0
  5661.0    0.05       0  5903.2    0.08       0
Bank Sta=4999.3,5005.3
Exp/Cntr=0.3,0.1

Type RM Length L Ch R = 1,5710,924,924,924
BEGIN DESCRIPTION:
LYNN CREEK 10.02
END DESCRIPTION:
XS GIS Cut Line= 4
      3569859.81     10499019.95      3569533.44     10499328.96
      3569380.66     10499669.24      3569139.34     10500146.67
#Sta/Elev= 30
  4568.1  410.20  4680.8  405.10  4709.1  402.98  4723.3  399.47  4758.5  398.65
  4782.8  396.17  4815.1  395.05  4836.6  392.59  4871.8  392.74  4921.6  390.54
  4978.1  389.36  4996.2  378.97  4998.9  378.47  5002.2  378.97  5004.2  379.48
  5015.9  387.14  5018.0  387.14  5029.5  386.57  5035.0  389.60  5052.7  388.62
  5058.1  390.49  5360.3  391.25  5409.8  392.96  5465.5  392.08  5532.4  393.56
  5638.2  397.50  5683.5  400.95  5771.9  406.89  5906.6  412.35  5925.5  413.05
#Mann=10,-1,0
  4568.1    0.05       0  4782.8     0.1       0  4921.6    0.05       0
  4996.2   0.035       0  5002.2    0.05       0  5004.2    0.16       0
  5018.0    0.05       0  5409.8    0.08       0  5683.5    0.05       0
  5906.6    0.08       0
Bank Sta=4996.2,5002.2
Exp/Cntr=0.3,0.1