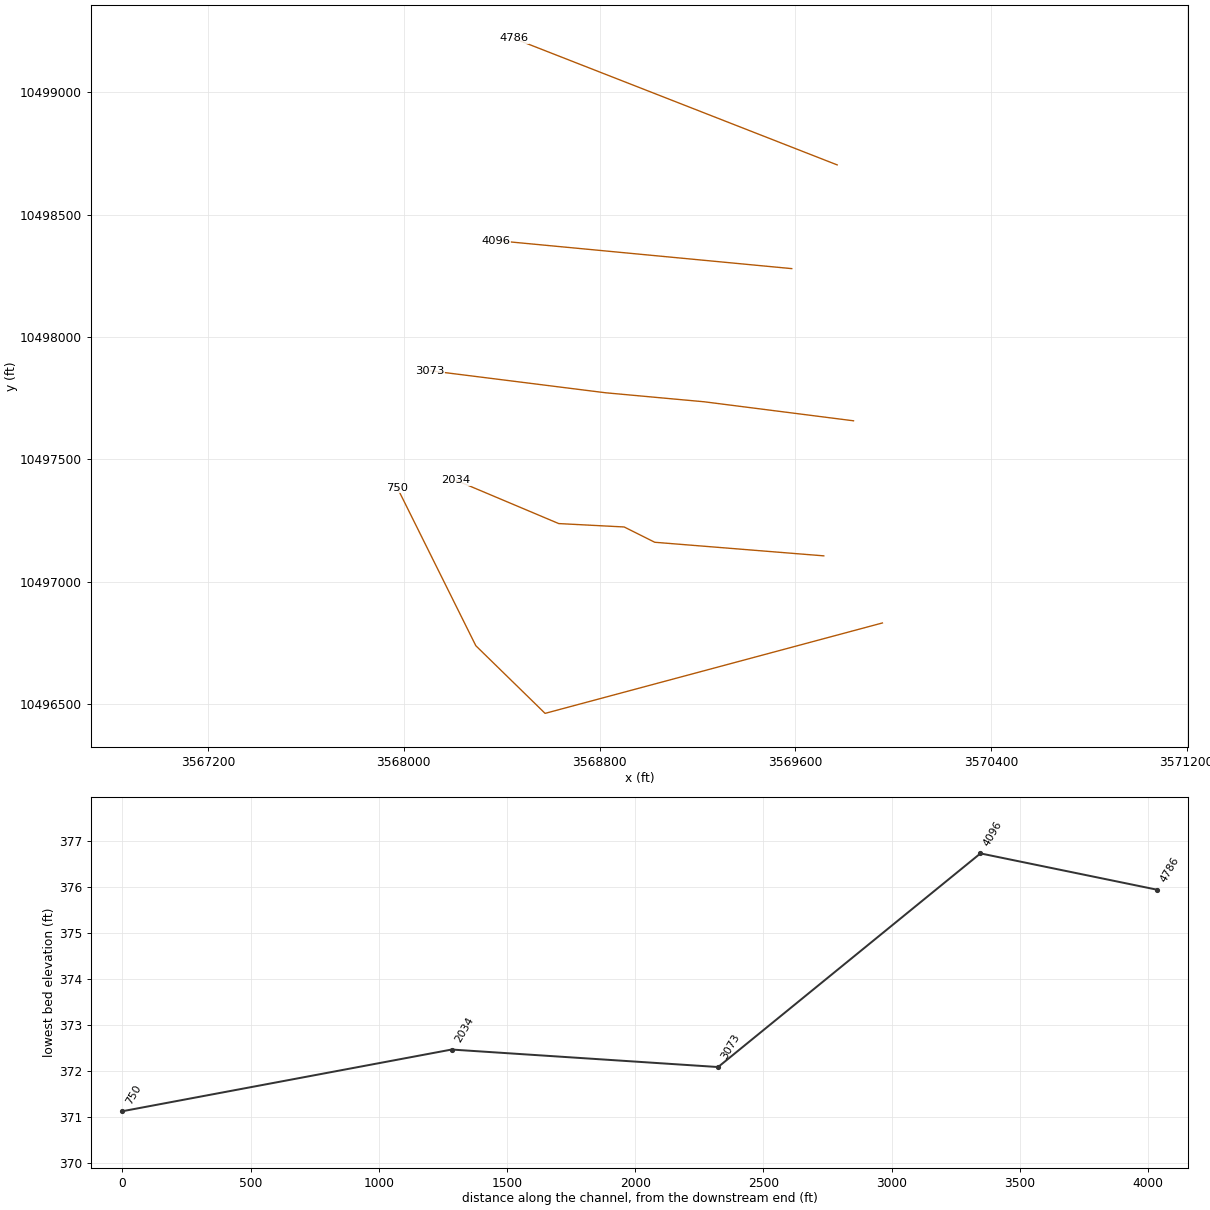
HEC-RAS study LYNN CREEK.prj: LYNN CREEK Base Level Engineering

--- LYNN CREEK.g01 (geometry) --- (continued)

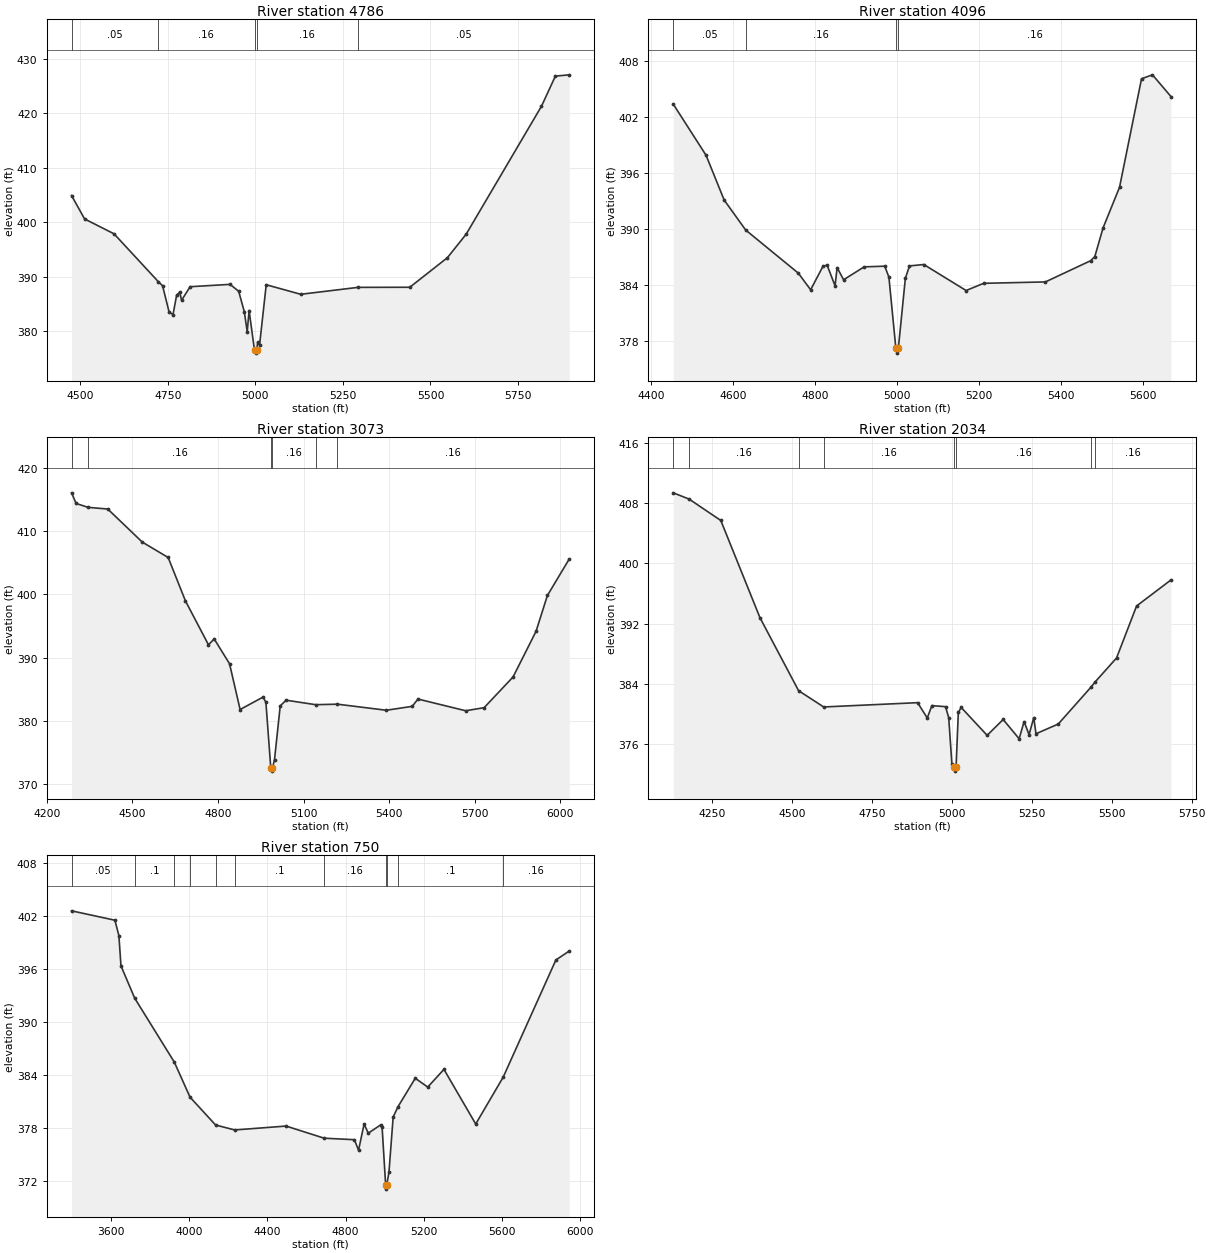
Type RM Length L Ch R = 1,4786,690,690,690
BEGIN DESCRIPTION:
LYNN CREEK 8.0
END DESCRIPTION:
XS GIS Cut Line= 2
      3569771.33     10498702.94      3568448.39     10499220.30
#Sta/Elev= 30
  4475.5  404.87  4512.7  400.57  4596.8  397.84  4722.8  389.08  4735.3  388.31
  4753.8  383.52  4765.1  383.00  4775.3  386.52  4784.2  387.15  4789.6  385.65
  4814.0  388.13  4928.0  388.56  4952.5  387.30  4968.6  383.55  4976.9  379.88
  4982.3  383.76  4997.8  376.44  5000.6  375.94  5003.8  376.44  5006.8  377.96
  5012.1  377.40  5031.2  388.49  5129.7  386.74  5293.3  388.01  5441.0  388.03
  5548.4  393.46  5602.1  397.79  5816.9  421.26  5856.5  426.78  5896.0  427.02
#Mann=5,-1,0
  4475.5    0.05       0  4722.8    0.16       0  4997.8    0.07       0
  5003.8    0.16       0  5293.3    0.05       0
Bank Sta=4997.8,5003.8
Exp/Cntr=0.3,0.1

Type RM Length L Ch R = 1,4096,1023,1023,1023
BEGIN DESCRIPTION:
LYNN CREEK 6.0
END DESCRIPTION:
XS GIS Cut Line= 2
      3569585.51     10498278.99      3568377.23     10498393.57
#Sta/Elev= 30
  4454.8  403.33  4534.7  397.87  4578.8  393.09  4631.4  389.88  4759.6  385.28
  4789.7  383.50  4819.8  386.01  4829.9  386.13  4849.3  383.92  4854.3  385.87
  4870.1  384.57  4920.3  385.95  4970.5  386.02  4980.6  384.85  4997.6  377.23
  5000.4  376.73  5003.6  377.23  5020.7  384.72  5030.8  386.05  5065.7  386.20
  5168.9  383.42  5211.6  384.19  5362.3  384.34  5472.8  386.61  5482.8  387.05
  5502.9  390.11  5543.1  394.46  5596.7  406.05  5623.4  406.47  5668.5  404.15
#Mann=4,-1,0
  4454.8    0.05       0  4631.4    0.16       0  4997.6    0.07       0
  5003.6    0.16       0
Bank Sta=4997.6,5003.6
Exp/Cntr=0.3,0.1

Type RM Length L Ch R = 1,3073,1039,1039,1039
BEGIN DESCRIPTION:
LYNN CREEK 4.0
END DESCRIPTION:
XS GIS Cut Line= 4
      3569838.03     10497656.94      3569228.03     10497734.60
      3568824.15     10497771.53      3568106.28     10497861.69
#Sta/Elev= 30
  4286.7  416.03  4302.8  414.35  4344.3  413.74  4413.6  413.47  4534.6  408.25
  4625.3  405.82  4685.8  398.97  4766.5  392.04  4786.6  392.96  4840.3  389.05
  4877.4  381.82  4957.8  383.78  4967.8  382.97  4984.9  372.59  4987.7  372.09
  4990.9  372.59  4998.0  373.91  5018.0  382.39  5038.5  383.29  5142.2  382.58
  5218.5  382.66  5389.9  381.70  5480.6  382.32  5500.7  383.47  5668.1  381.62
  5732.6  382.11  5834.0  386.96  5914.5  394.16  5954.3  399.82  6030.7  405.57
#Mann=6,-1,0
  4286.7    0.05       0  4344.3    0.16       0  4984.9    0.07       0
  4990.9    0.16       0  5142.2     0.1       0  5218.5    0.16       0
Bank Sta=4984.9,4990.9
Exp/Cntr=0.3,0.1

Type RM Length L Ch R = 1,2034,1284,1284,1284
BEGIN DESCRIPTION:
LYNN CREEK 3.0
END DESCRIPTION:
XS GIS Cut Line= 5
      3569716.50     10497104.86      3569025.54     10497160.41
      3568900.54     10497222.91      3568633.17     10497236.80
      3568213.04     10497413.88
#Sta/Elev= 30
  4128.7  409.34  4178.5  408.50  4277.2  405.68  4399.7  392.80  4520.5  383.13
  4599.0  380.97  4892.8  381.54  4923.0  379.51  4937.5  381.15  4980.1  381.01
  4990.1  379.56  5000.1  373.42  5007.1  372.97  5009.9  372.47  5013.1  372.97
  5020.2  380.26  5029.3  380.90  5110.3  377.21  5160.4  379.31  5210.4  376.76
  5225.9  379.03  5241.4  377.30  5256.2  379.56  5263.1  377.42  5332.8  378.71
  5435.0  383.59  5449.0  384.33  5515.1  387.46  5577.8  394.35  5685.3  397.80
#Mann=8,-1,0
  4128.7    0.05       0  4178.5    0.16       0  4520.5     0.1       0
  4599.0    0.16       0  5007.1    0.07       0  5013.1    0.16       0
  5435.0     0.1       0  5449.0    0.16       0
Bank Sta=5007.1,5013.1
Exp/Cntr=0.3,0.1

Type RM Length L Ch R = 1,750,0,0,0
BEGIN DESCRIPTION:
LYNN CREEK 1.0
END DESCRIPTION:
XS GIS Cut Line= 4
      3569956.12     10496830.56      3568577.34     10496460.96
      3568294.20     10496737.45      3567973.46     10497382.62
#Sta/Elev= 30
  3398.8  402.55  3620.4  401.49  3640.8  399.75  3651.4  396.34  3721.5  392.69
  3924.1  385.47  4004.5  381.51  4135.0  378.37  4232.7  377.81  4495.3  378.25
  4690.0  376.88  4844.6  376.71  4865.8  375.52  4894.1  378.48  4915.4  377.45
  4978.9  378.38  4986.1  378.17  5004.2  371.63  5007.0  371.13  5010.2  371.63
  5021.4  373.08  5042.7  379.27  5067.3  380.43  5155.7  383.65  5219.4  382.65
  5302.3  384.65  5464.7  378.48  5605.5  383.79  5874.4  397.00  5942.5  398.01
#Mann=11,-1,0
  3398.8    0.05       0  3721.5     0.1       0  3924.1    0.16       0
  4004.5     0.1       0  4135.0    0.16       0  4232.7     0.1       0
  4690.0    0.16       0  5004.2    0.07       0  5010.2    0.16       0
  5067.3     0.1       0  5605.5    0.16       0
Bank Sta=5004.2,5010.2
Exp/Cntr=0.3,0.1

Chan Stop Cuts=-1