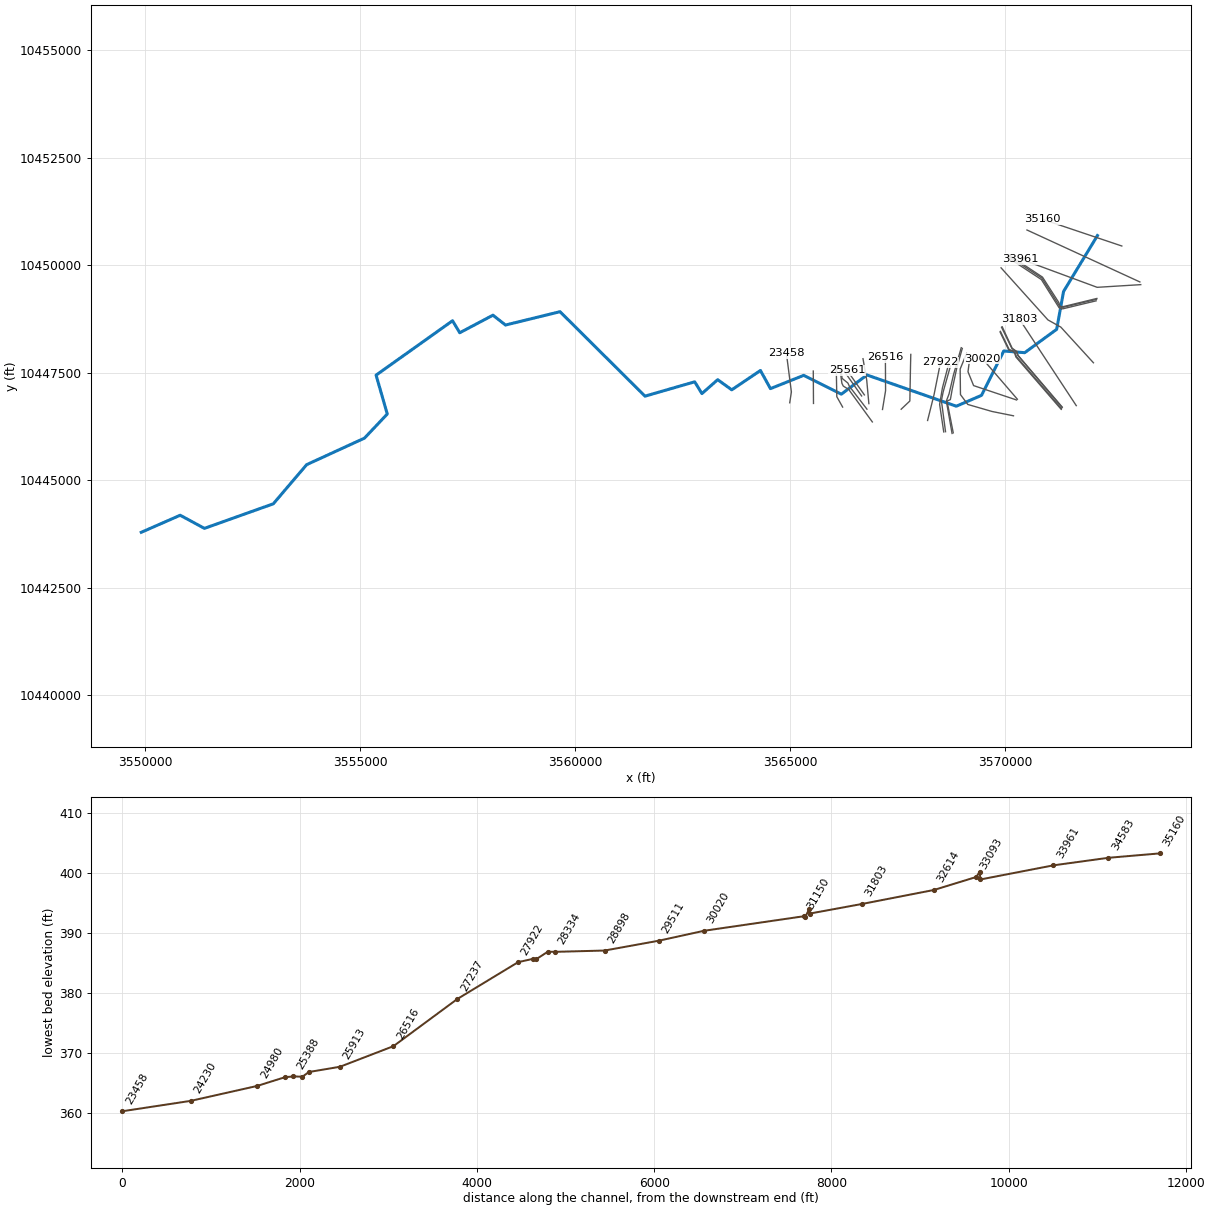
--- MILL CREEK.prj (project) ---

Proj Title=MILL CREEK Base Level Engineering
Current Plan=p01
Default Exp/Contr=0.3,0.1
English Units
Geom File=g01
Flow File=f01
Plan File=p01
Y Axis Title=Elevation
X Axis Title(PF)=Main Channel Distance
X Axis Title(XS)=Station
BEGIN DESCRIPTION:
MILL CREEK
END DESCRIPTION:
DSS Export Rating Curves= 0
DSS Export Rating Curve Sorted= 0
DSS Export Volume Flow Curves= 0
DXF OffsetX= 0
DXF OffsetY= 0
DXF ScaleX= 1
DXF ScaleY= 10

--- MILL CREEK.p01 (plan) ---

Plan Title=Multiple Run
Short Identifier=Multiple
Geom File=g01
Flow File=f01
Subcritical Flow
K Sum by GR= 0
Std Step Tol= 0.01
Critical Tol= 0.01
Num of Std Step Trials= 20
Max Error Tol= 0.3
Flow Tol Ratio= 0.001
Split Flow NTrial= 30
Split Flow Tol= 0.02
Split Flow Ratio= 0.02
Log Output Level= 0
Friction Slope Method= 1
Unsteady Friction Slope Method= 2
Unsteady Bridges Friction Slope Method= 1
Parabolic Critical Depth
Global Vel Dist=  1 , 1 , 1
Global Log Level= 0
CheckData=True
Encroach Param= -1, 0, 0, 0
BEGIN DESCRIPTION:
Multiple Run
END DESCRIPTION:

--- MILL CREEK.f01 (steady flow) ---

Flow Title=Multiple
Program Version=4.10
Number of Profiles= 7
Profile Names=10-year,25-year,50-year,1pct_min,100-year,1pct_plu,500-year
River Rch & RM=MILL CREEK,Reach-1         ,35160
     823    1116    1354    1199    1621    2192    2317
River Rch & RM=MILL CREEK,Reach-1         ,32614
    1370    1906    2353    2115    2860    3868    4219
River Rch & RM=MILL CREEK,Reach-1         ,28334
    2120    3016    3778    3443    4656    6297    7059
River Rch & RM=MILL CREEK,Reach-1         ,23458
    2385    3407    4279    3909    5286    7149    8051
River Rch & RM=MILL CREEK,Reach-1         ,20295
    2786    4004    5049    4627    6258    8463    9597
River Rch & RM=MILL CREEK,Reach-1         ,14969
    3111    4475    5645    5172    6995    9460   10722
River Rch & RM=MILL CREEK,Reach-1         ,4391
    3791    5505    6991    6445    8716   11787   13525
Boundary for River Rch & Prof#=MILL CREEK,Reach-1         , 1
Up Type= 0
Dn Type= 3
Dn Slope=0.00228
Boundary for River Rch & Prof#=MILL CREEK,Reach-1         , 2
Up Type= 0
Dn Type= 3
Dn Slope=0.00228
Boundary for River Rch & Prof#=MILL CREEK,Reach-1         , 3
Up Type= 0
Dn Type= 3
Dn Slope=0.00228
Boundary for River Rch & Prof#=MILL CREEK,Reach-1         , 4
Up Type= 0
Dn Type= 3
Dn Slope=0.00228
Boundary for River Rch & Prof#=MILL CREEK,Reach-1         , 5
Up Type= 0
Dn Type= 3
Dn Slope=0.00228
Boundary for River Rch & Prof#=MILL CREEK,Reach-1         , 6
Up Type= 0
Dn Type= 3
Dn Slope=0.00228
Boundary for River Rch & Prof#=MILL CREEK,Reach-1         , 7
Up Type= 0
Dn Type= 3
Dn Slope=0.00228
DSS Import GetInterval= 0
DSS Import GetPeak= 0
DSS Import FillOption= 0

--- MILL CREEK.g01 (geometry) ---

Geom Title=Existing Conditions
Program Version=4.10

River Reach=MILL CREEK      ,Reach-1
Reach XY= 30
      3572140.83     10450691.86      3571353.21      10449392.4
      3571192.35     10448511.28      3570449.41     10447968.19
      3569963.45     10448008.01      3569445.72     10446975.93
      3568859.78     10446723.76      3566781.66     10447450.08
      3566186.42     10447003.25       3565312.5      10447441.2
      3564539.32     10447132.34      3564306.25     10447553.96
      3563639.06     10447104.22      3563312.15     10447340.33
      3562945.83     10447017.07      3562777.73     10447290.89
      3561622.54     10446957.23      3559647.26     10448921.34
      3558379.16      10448611.1      3558087.87     10448840.25
      3557316.06     10448431.65      3557147.93     10448710.38
      3555370.76     10447445.77      3555631.39      10446542.1
      3555102.03     10445981.67       3553756.4     10445364.03
      3552981.11     10444453.56      3551380.28     10443883.04
      3550817.38     10444188.07      3549912.11     10443791.64

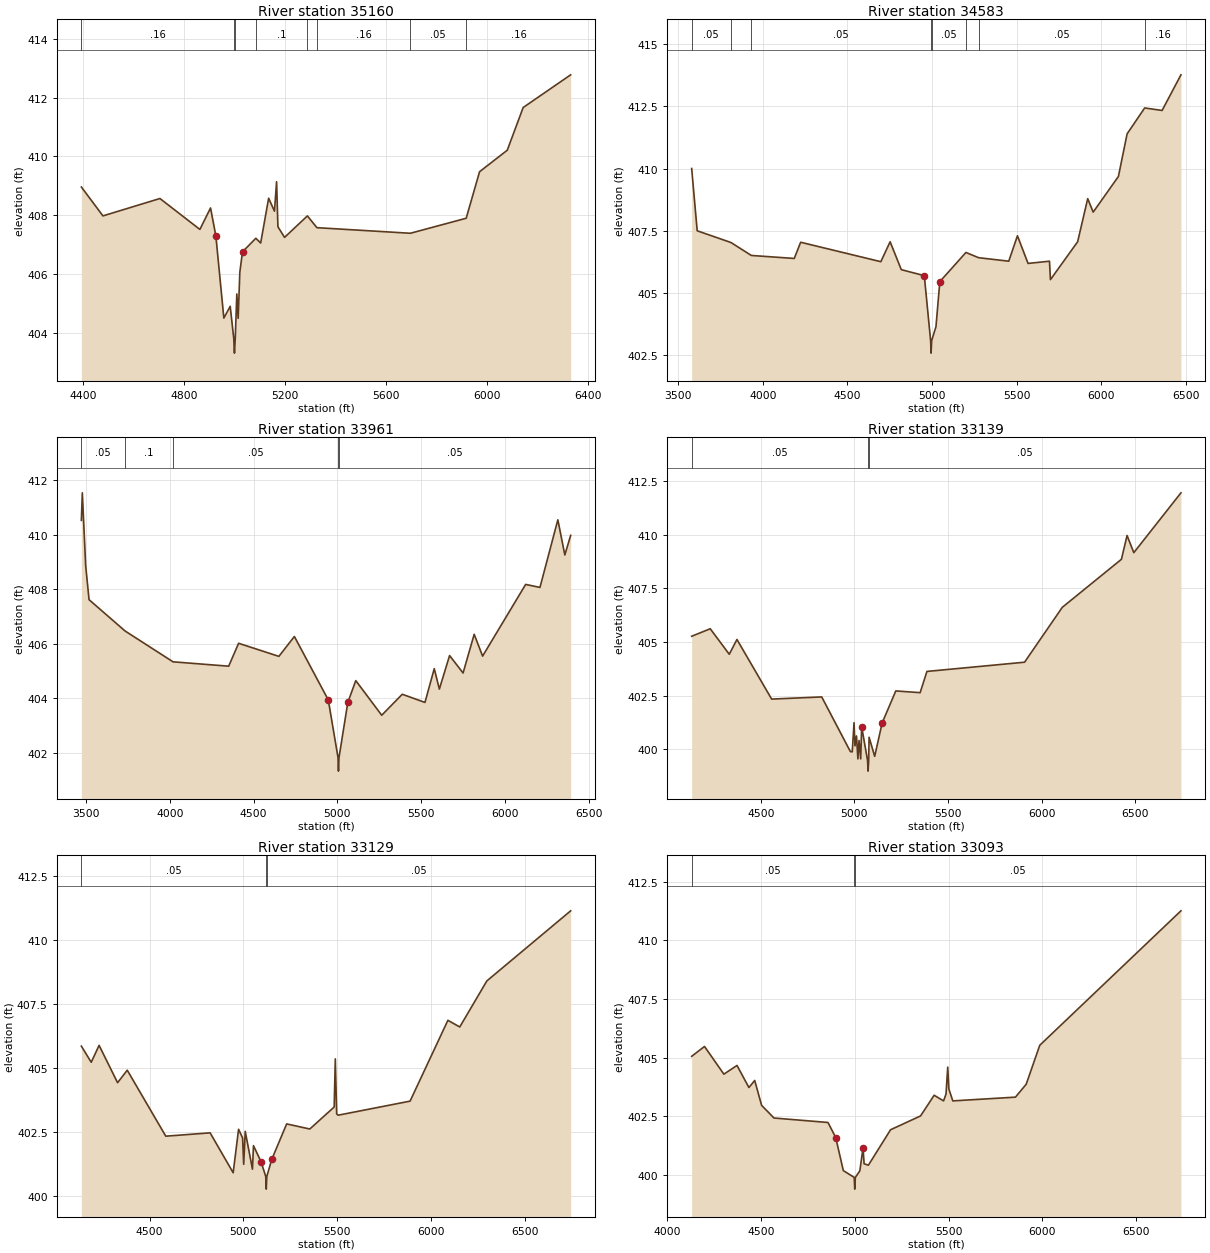
Type RM Length L Ch R = 1 ,35160   ,577,577,577
BEGIN DESCRIPTION:
MILL CREEK 64.01
END DESCRIPTION:
XS GIS Cut Line= 2
      3572706.96     10450449.03      3570870.16     10451067.08
#Sta/Elev= 30
  4393.2  408.96  4478.6  407.98  4704.4  408.57  4862.6  407.52  4904.8  408.25
  4925.9   407.3  4957.5  404.51  4982.7  404.91  4996.7  403.82  4999.5  403.32
  5002.7  403.82  5008.9  405.33  5014.2   404.5  5020.8  406.07  5031.4  406.76
  5084.2  407.22  5103.4  407.06  5134.9  408.58    5158  408.14  5166.4  409.14
  5171.7  407.61    5198  407.25  5288.4  407.98  5326.1  407.58  5696.3  407.39
  5917.4   407.9  5970.4  409.48  6080.1  410.21  6143.1  411.66  6331.2  412.77
#Mann= 8 ,-1 , 0
  4393.2     .16       0  4996.7     .07       0  5002.7     .16       0
  5084.2      .1       0  5288.4     .05       0  5326.1     .16       0
  5696.3     .05       0  5917.4     .16       0
Bank Sta=4925.9,5031.4
XS Rating Curve= 0 ,0
Exp/Cntr=0.3,0.1

Type RM Length L Ch R = 1 ,34583   ,622,622,622
BEGIN DESCRIPTION:
MILL CREEK 64.02
END DESCRIPTION:
XS GIS Cut Line= 2
      3573126.82     10449612.95      3570501.87     10450821.26
#Sta/Elev= 30
  3580.2     410  3612.9   407.5  3812.2  407.03  3932.6  406.51  4186.1  406.39
  4223.9  407.04  4697.3  406.26  4752.3  407.06  4818.3  405.94  4954.1   405.7
  4991.5  403.09  4994.2  402.59  4997.5  403.09    5023  403.65  5045.9  405.46
    5200  406.63  5274.9  406.42  5452.9  406.28  5504.3   407.3  5566.9  406.19
  5693.5  406.28  5699.1  405.54  5859.8  407.06  5919.2  408.79  5951.7  408.25
  6100.5  409.68  6151.9  411.39  6255.7  412.43  6358.6  412.33  6469.9  413.76
#Mann= 8 ,-1 , 0
  3580.2     .05       0  3812.2      .1       0  3932.6     .05       0
  4991.5    .035       0  4997.5     .05       0    5200     .16       0
  5274.9     .05       0  6255.7     .16       0
Bank Sta=4954.1,5045.9
XS Rating Curve= 0 ,0
Exp/Cntr=0.3,0.1

Type RM Length L Ch R = 1 ,33961   ,822,822,822
BEGIN DESCRIPTION:
MILL CREEK 64.03
END DESCRIPTION:
XS GIS Cut Line= 3
      3573147.71     10449550.44       3572133.8     10449487.93
      3570350.47     10450147.14
#Sta/Elev= 30
  3473.5  410.53  3479.1  411.54  3499.1  408.87  3519.2  407.62  3734.3  406.47
  4019.9  405.34  4351.8  405.18  4410.9  406.02  4651.1  405.54  4743.4  406.27
  4945.7  403.94  5003.5  401.83  5006.2  401.33  5009.5  401.83    5062  403.85
  5109.5  404.65  5264.2  403.38  5386.7  404.15  5521.9  403.85  5577.4  405.09
  5607.8  404.34  5668.7  405.57  5749.2  404.93  5815.4  406.35  5865.6  405.55
  6122.3  408.18  6207.6  408.07  6314.2  410.55  6355.9  409.26  6390.6  409.98
#Mann= 5 ,-1 , 0
  3473.5     .05       0  3734.3      .1       0  4019.9     .05       0
  5003.5    .035       0  5009.5     .05       0
Bank Sta=4945.7,5062
XS Rating Curve= 0 ,0
Exp/Cntr=0.3,0.1

Type RM Length L Ch R = 1 ,33139   ,10,10,10
BEGIN DESCRIPTION:
MILL CREEK 64.05
END DESCRIPTION:
XS GIS Cut Line= 6
      3572127.26     10449229.25      3571351.46     10449040.45
      3571275.47     10449046.88      3571237.97     10449141.67
      3570862.96     10449725.08      3570077.02     10450245.63
#Sta/Elev= 30
  4130.8  405.27  4230.1  405.62  4331.7  404.43  4372.8  405.12  4558.1  402.34
  4825.7  402.44  4978.8  399.89  4988.8  399.88  4998.3  401.24  5003.3  400.16
  5011.4  400.62  5018.9  399.55  5024.9  400.41  5033.9  399.55    5039  401.05
  5070.5  399.48  5073.2  398.98  5076.5  399.48  5078.7  400.56  5108.6  399.67
  5148.6  401.23  5221.3  402.72  5351.4  402.64  5387.7  403.63  5909.3  404.06
  6110.9  406.62  6426.8  408.86  6456.9  409.97    6493  409.17  6744.8  411.96
#Mann= 3 ,-1 , 0
  4130.8     .05       0  5070.5    .035       0  5076.5     .05       0
Bank Sta=5039,5148.6
XS Rating Curve= 0 ,0
Exp/Cntr=0.3,0.1

Type RM Length L Ch R = 1 ,33129   ,36,36,36
BEGIN DESCRIPTION:
MILL CREEK 64.0
END DESCRIPTION:
XS GIS Cut Line= 6
      3572119.94     10449208.43      3571349.51     10449023.96
       3571299.6     10449026.13      3571258.37       10449050.
      3570847.99     10449703.65      3570056.75      10450224.2
#Sta/Elev= 30
  4136.2  405.86  4188.7  405.23  4230.7  405.89  4329.3  404.43  4380.8  404.92
  4586.4  402.34  4822.9  402.47  4945.8  400.91  4974.6  402.61  4996.1  402.27
  5001.9  401.24  5010.1  402.53  5048.6  401.05  5054.1  401.97  5093.9  401.35
  5119.4  400.77  5122.2  400.27  5125.4  400.77  5151.5  401.43  5231.1  402.82
  5354.5  402.62  5484.5  403.48  5490.5  405.36  5497.8  403.21  5505.6  403.16
  5889.3  403.71  6091.1  406.87  6154.3  406.61  6298.9  408.41  6745.8  411.15
#Mann= 3 ,-1 , 0
  4136.2     .05       0  5119.4    .035       0  5125.4     .05       0
Bank Sta=5093.9,5151.5
XS Rating Curve= 0 ,0
Exp/Cntr=0.3,0.1

Type RM Length L Ch R = 1 ,33093   ,479,479,479
BEGIN DESCRIPTION:
MILL CREEK 64.04
END DESCRIPTION:
XS GIS Cut Line= 6
      3572109.05      10449173.7      3571338.66     10448989.24
      3571288.75     10448991.41      3571247.51     10449015.28
      3570837.14     10449668.92      3570046.27     10450189.23
#Sta/Elev= 30
    4130  405.06  4198.5  405.48  4301.7   404.3  4371.8  404.67  4435.3  403.73
  4466.2  404.03    4503  402.97    4569  402.43  4856.9  402.24  4898.1   401.6
  4938.7  400.19  4996.8   399.9  4999.6   399.4  5002.8   399.9  5026.8  400.18
  5043.9  401.16  5049.5  400.48  5072.4  400.42  5190.6  401.93  5350.6  402.52
    5423   403.4  5473.3  403.16  5486.3  403.45  5495.4   404.6  5501.4  403.67
  5522.5  403.16  5856.7  403.32  5913.9  403.87  5986.2  405.53  6739.1  411.26
#Mann= 3 ,-1 , 0
    4130     .05       0  4996.8    .035       0  5002.8     .05       0
Bank Sta=4898.1,5043.9
XS Rating Curve= 0 ,0
Exp/Cntr=0.3,0.1

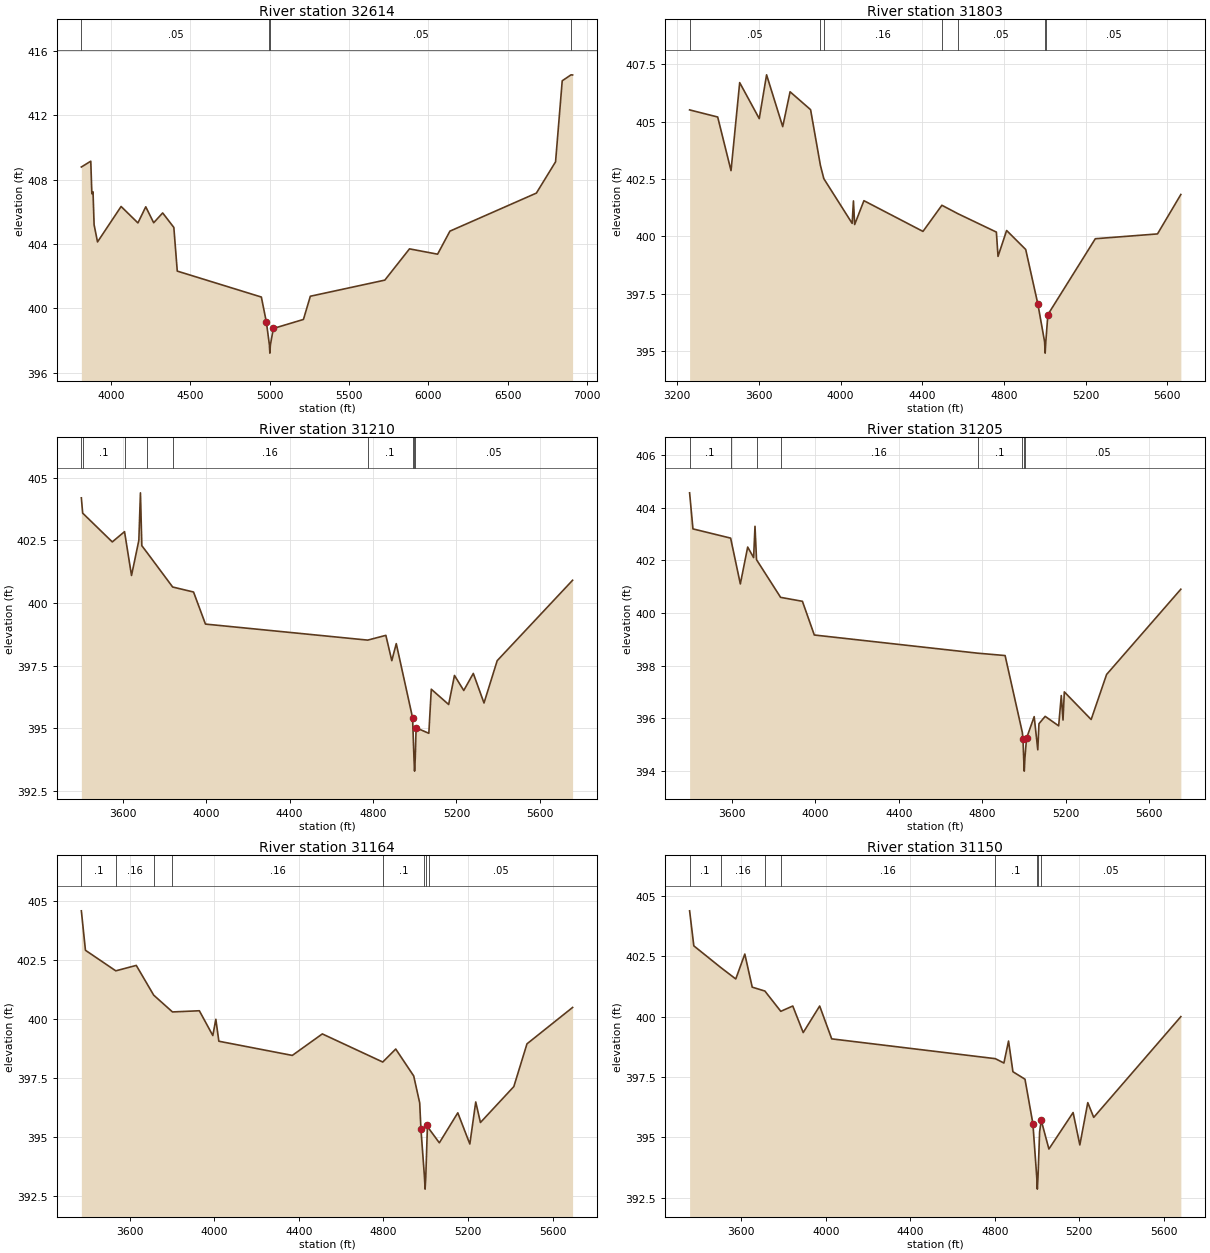
Type RM Length L Ch R = 1 ,32614   ,811,811,811
BEGIN DESCRIPTION:
MILL CREEK 63.0
END DESCRIPTION:
XS GIS Cut Line= 4
      3572047.62      10447733.3      3571289.01     10448563.17
      3570990.17     10448729.67      3569899.92     10449941.45
#Sta/Elev= 30
  3813.7  408.78  3873.1  409.14  3879.9  407.12  3887.3  407.24    3894   405.2
  3915.6  404.13  4064.3  406.33  4170.3  405.31  4219.7  406.31  4269.6  405.32
  4326.3  405.93  4396.7  405.03  4418.3  402.32  4948.4  400.71  4980.3  399.14
  4999.2  397.73  5001.9  397.23  5005.2  397.73  5023.9  398.76  5213.6  399.32
  5257.1  400.76  5726.6  401.76  5882.1   403.7  6059.2  403.37    6137   404.8
  6681.8  407.16  6802.8   409.1  6844.8  414.13  6900.4   414.5  6910.2  414.49
#Mann= 4 ,-1 , 0
  3813.7     .05       0  4999.2    .035       0  5005.2     .05       0
  6900.4     .16       0
Bank Sta=4980.3,5023.9
XS Rating Curve= 0 ,0
Exp/Cntr=0.3,0.1

Type RM Length L Ch R = 1 ,31803   ,593,593,593
BEGIN DESCRIPTION:
MILL CREEK 61.0
END DESCRIPTION:
XS GIS Cut Line= 3
      3571648.31     10446736.79      3570853.19     10447945.09
      3570327.63      10448747.2
#Sta/Elev= 30
  3260.9  405.51  3398.4   405.2  3463.7  402.86  3506.1   406.7  3601.9  405.13
  3637.8  407.04  3716.8  404.78  3752.9   406.3  3853.3  405.52  3901.4  403.09
  3918.1  402.51  4056.8  400.56  4063.1  401.54  4069.1  400.51  4114.4  401.55
  4403.6  400.21  4496.2  401.35  4575.2  400.98    4763  400.18  4771.1  399.12
  4813.2  400.25  4906.7  399.42  4966.2  397.04  4999.1   395.4  5001.9   394.9
  5005.1   395.4  5015.2  396.58  5247.4  399.89  5551.9   400.1  5666.3  401.82
#Mann= 7 ,-1 , 0
  3260.9     .05       0  3901.4      .1       0  3918.1     .16       0
  4496.2      .1       0  4575.2     .05       0  4999.1    .035       0
  5005.1     .05       0
Bank Sta=4966.2,5015.2
XS Rating Curve= 0 ,0
Exp/Cntr=0.3,0.1

Type RM Length L Ch R = 1 ,31210   ,5,5,5
BEGIN DESCRIPTION:
MILL CREEK 60.02
END DESCRIPTION:
XS GIS Cut Line= 5
      3571322.54     10446702.81      3570295.97     10447905.78
      3570262.64     10447996.92      3570158.47     10448070.88
      3569927.32     10448569.68
#Sta/Elev= 30
  3400.9   404.2  3407.2  403.59  3549.2  402.44    3608  402.85  3641.5   401.1
  3676.6   402.5  3684.3   404.4  3690.9  402.29  3716.4  402.01  3838.8  400.64
    3939  400.44  3996.1  399.16  4774.3  398.52  4861.3  398.71  4889.8   397.7
  4911.2  398.38  4989.5  395.42  4996.2  393.79    4999  393.29  5002.2  393.79
  5006.4  395.02  5067.4   394.8  5079.2  396.56  5162.5  395.95  5190.4  397.11
  5234.9  396.51  5280.7  397.19    5332  396.01  5395.3   397.7  5756.9  400.91
#Mann= 9 ,-1 , 0
  3400.9     .05       0  3407.2      .1       0    3608     .16       0
  3716.4      .1       0  3838.8     .16       0  4774.3      .1       0
  4989.5     .05       0  4996.2    .035       0  5002.2     .05       0
Bank Sta=4989.5,5006.4
XS Rating Curve= 0 ,0
Exp/Cntr=0.3,0.1

Type RM Length L Ch R = 1 ,31205   ,41,41,41
BEGIN DESCRIPTION:
MILL CREEK 60.01
END DESCRIPTION:
XS GIS Cut Line= 6
       3571317.6     10446694.67       3570292.8     10447901.18
      3570277.18     10447939.37      3570258.08     10447987.11
      3570152.18     10448065.24      3569911.69     10448558.33
#Sta/Elev= 30
  3396.4  404.56  3412.4  403.19  3593.1  402.84  3639.7   401.1  3674.9   402.5
  3703.4   402.1    3710  403.29  3717.3  402.02  3832.8  400.59  3937.4  400.44
  3994.5  399.16  4777.4  398.47  4909.4  398.38  4992.1  395.46  4995.3   395.2
  4998.5  394.49  5001.3  393.99  5004.5  394.49  5012.3  395.24  5048.9  396.06
  5066.2   394.8  5071.8  395.79  5101.6  396.07  5166.3  395.71  5178.9  396.86
  5187.2  395.93  5193.4     397  5322.1  395.95  5396.1  397.66  5752.3   400.9
#Mann= 8 ,-1 , 0
  3396.4      .1       0  3593.1     .16       0  3717.3      .1       0
  3832.8     .16       0  4777.4      .1       0  4992.1     .05       0
  4998.5    .035       0  5004.5     .05       0
Bank Sta=4995.3,5012.3
XS Rating Curve= 0 ,0
Exp/Cntr=0.3,0.1

Type RM Length L Ch R = 1 ,31164   ,14,14,14
BEGIN DESCRIPTION:
MILL CREEK 60.0
END DESCRIPTION:
XS GIS Cut Line= 6
      3571304.24       10446667.      3570257.28      10447878.1
      3570227.34     10447960.13      3570183.07     10448008.31
      3570089.32     10448040.86      3569884.87     10448464.07
#Sta/Elev= 30
  3371.3  404.57  3390.7   402.9  3534.1  402.03    3631  402.26  3713.5     401
  3802.2  400.29  3929.3  400.34    3993  399.29  4007.2  399.98  4021.5  399.05
  4368.8  398.45  4510.7  399.36  4796.5  398.17  4857.9  398.72  4942.9  397.58
  4971.2  396.44    4977  395.34  4993.9  393.29  4996.7  392.79  4999.9  393.29
  5007.9  395.49  5013.3  395.37  5064.1  394.75  5151.4  396.02  5208.3   394.7
  5236.2  396.48  5258.4  395.61  5416.3  397.13  5478.5  398.94  5694.2  400.48
#Mann= 8 ,-1 , 0
  3371.3      .1       0  3534.1     .16       0  3713.5      .1       0
  3802.2     .16       0  4796.5      .1       0  4993.9     .07       0
  4999.9      .1       0  5013.3     .05       0
Bank Sta=4977,5007.9
XS Rating Curve= 0 ,0
Exp/Cntr=0.3,0.1

Type RM Length L Ch R = 1 ,31150   ,1130,1130,1130
BEGIN DESCRIPTION:
MILL CREEK 60.03
END DESCRIPTION:
XS GIS Cut Line= 6
      3571298.49     10446649.56      3570245.96     10447867.03
      3570214.49     10447957.09      3570168.92     10447997.24
      3570079.94      10448028.7      3569877.53     10448447.59
#Sta/Elev= 30
  3355.9  404.38  3375.9  402.93  3503.9  402.03  3574.4  401.56  3617.2  402.59
  3652.3  401.22  3712.1  401.06  3787.5  400.22  3844.2  400.44  3893.6  399.34
  3971.5  400.44  4028.5  399.08  4803.1  398.26  4843.5  398.08  4865.4  398.99
  4886.2  397.72  4943.3  397.41  4980.7  395.57  4998.9  393.36  5001.7  392.86
  5004.9  393.36  5012.5  395.23  5019.2  395.65  5020.1  395.71  5056.5  394.52
    5171  396.03  5202.9  394.69  5240.5  396.44  5268.6  395.83    5681     400
#Mann= 8 ,-1 , 0
  3355.9      .1       0  3503.9     .16       0  3712.1      .1       0
  3787.5     .16       0  4803.1      .1       0  4998.9     .07       0
  5004.9      .1       0  5019.2     .05       0
Bank Sta=4980.7,5020.1
XS Rating Curve= 0 ,0
Exp/Cntr=0.3,0.1

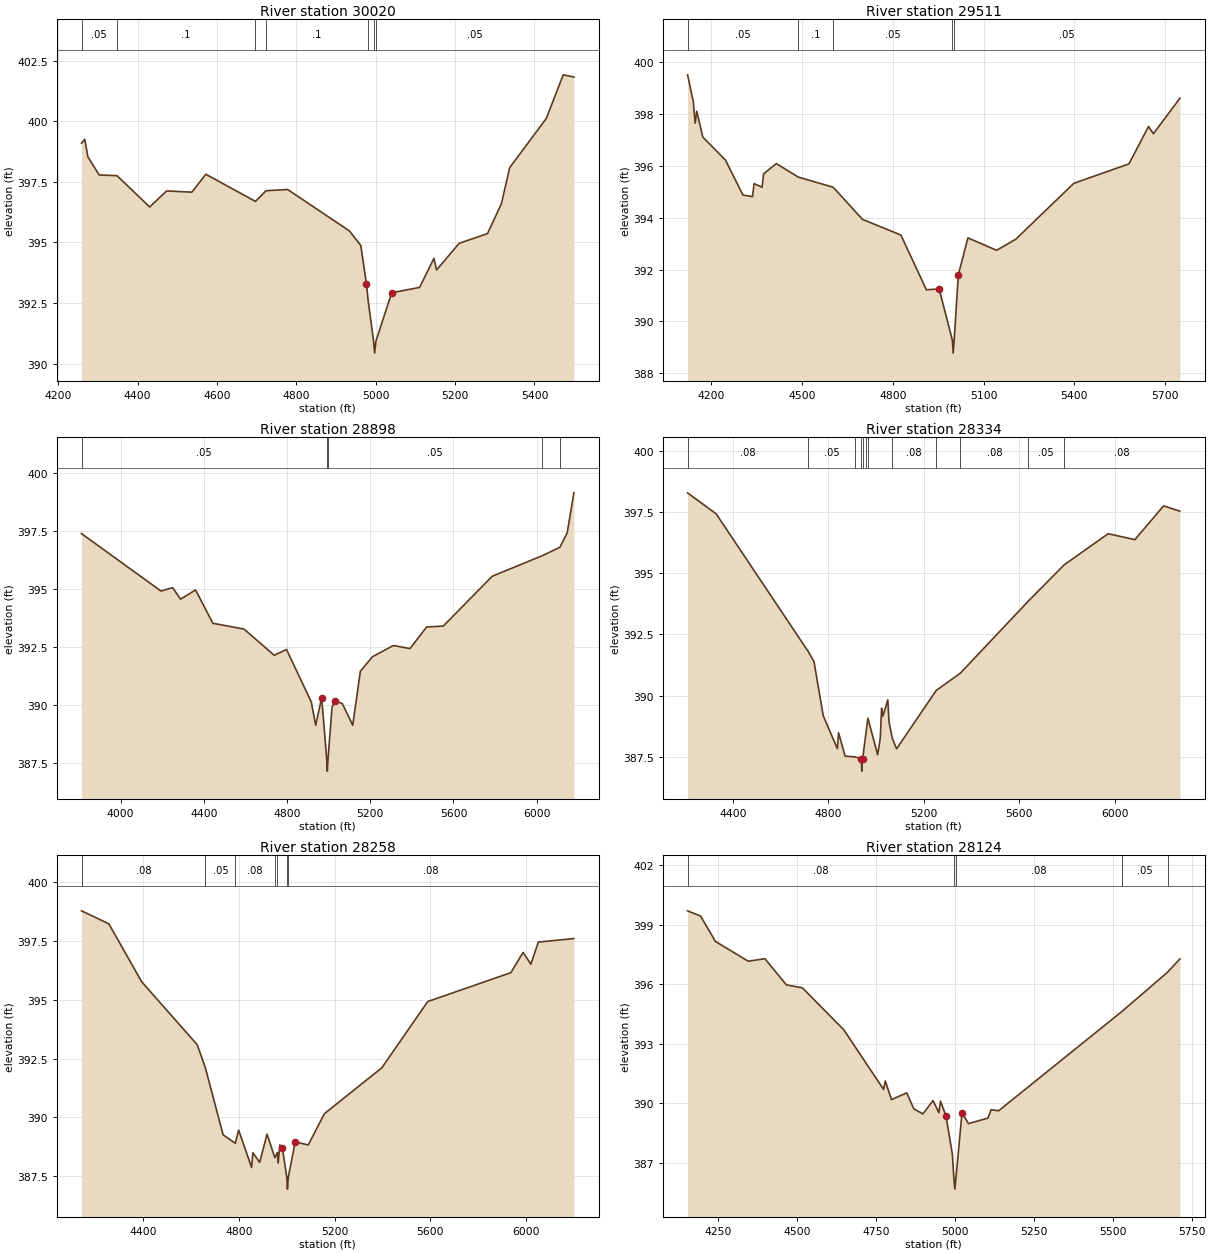
Type RM Length L Ch R = 1 ,30020   ,509,509,509
BEGIN DESCRIPTION:
MILL CREEK 59.0
END DESCRIPTION:
XS GIS Cut Line= 2
      3570279.05     10446886.48       3569469.2     10447826.54
#Sta/Elev= 30
  4258.6  399.09  4266.8  399.25  4274.5  398.53    4303  397.78    4348  397.75
  4430.3  396.46    4473  397.12  4536.7  397.07  4571.8  397.81  4696.8  396.69
  4723.7  397.13    4778  397.18  4933.8  395.47  4962.4  394.87  4976.6  393.29
  4981.4  392.53  4994.5  390.93  4997.2  390.43  5000.5  390.93  5040.3  392.92
  5110.5  393.14  5146.7  394.34  5153.3  393.86  5210.3  394.96  5281.6  395.36
  5316.7  396.59  5337.6  398.08  5429.8  400.11  5472.5  401.91  5499.4  401.82
#Mann= 7 ,-1 , 0
  4258.6     .05       0    4348      .1       0  4696.8     .05       0
  4723.7      .1       0  4981.4     .05       0  4994.5     .03       0
  5000.5     .05       0
Bank Sta=4976.6,5040.3
XS Rating Curve= 0 ,0
Exp/Cntr=0.3,0.1

Type RM Length L Ch R = 1 ,29511   ,613,613,613
BEGIN DESCRIPTION:
MILL CREEK 57.0
END DESCRIPTION:
XS GIS Cut Line= 4
      3570260.02     10446868.41      3569261.73     10447202.62
      3569131.52      10447523.8      3569160.49     10447748.52
#Sta/Elev= 30
  4122.5   399.5  4141.4  398.47  4147.6  397.64  4152.8   398.1    4173   397.1
  4247.5  396.22  4305.4  394.87    4337  394.81  4342.2  395.31  4368.5  395.17
  4373.8  395.69  4415.6  396.08  4488.4  395.56  4603.4  395.17  4700.3  393.93
  4826.9  393.33  4911.2  391.22  4953.4  391.25  4996.9  389.28  4999.6  388.78
  5002.9  389.28  5016.7   391.8  5048.3  393.22  5143.2  392.74  5206.6  393.17
  5397.9  395.32  5580.1  396.07  5644.7  397.51  5660.8  397.23  5748.4   398.6
#Mann= 5 ,-1 , 0
  4122.5     .05       0  4488.4      .1       0  4603.4     .05       0
  4996.9     .03       0  5002.9     .05       0
Bank Sta=4953.4,5016.7
XS Rating Curve= 0 ,0
Exp/Cntr=0.3,0.1

Type RM Length L Ch R = 1 ,28898   ,564,564,564
BEGIN DESCRIPTION:
MILL CREEK 56.0
END DESCRIPTION:
XS GIS Cut Line= 6
      3570188.73     10446500.57      3569688.77     10446601.25
      3569126.27     10446764.45      3568956.13     10446993.61
      3568949.18     10447587.36      3569097.81      10447950.3
#Sta/Elev= 30
    3812  397.39  4194.2  394.91  4250.1  395.06    4288  394.56  4360.2  394.96
  4443.5  393.52  4593.5  393.27  4738.2  392.14  4797.5  392.39  4916.7  390.12
  4937.6  389.12  4966.5  390.31  4990.9  387.64  4993.6  387.14  4996.9  387.64
  5016.3  389.89  5029.3  390.18  5066.1  390.05  5115.9  389.12  5152.5  391.45
  5211.1  392.08  5311.2  392.56  5391.2  392.43  5471.2  393.36  5551.2   393.4
  5786.5  395.55  6027.9  396.44  6111.8   396.8  6146.8  397.42  6179.1  399.15
#Mann= 5 ,-1 , 0
    3812     .05       0  4990.9     .03       0  4996.9     .05       0
  6027.9     .08       0  6111.8     .05       0
Bank Sta=4966.5,5029.3
XS Rating Curve= 0 ,0
Exp/Cntr=0.3,0.1

Type RM Length L Ch R = 1 ,28334   ,76,76,76
BEGIN DESCRIPTION:
MILL CREEK 55.01
END DESCRIPTION:
XS GIS Cut Line= 6
      3568788.62     10446103.88      3568643.21     10446843.94
      3568721.34     10446876.49      3568764.74     10447119.54
      3568873.25     10447625.19      3568998.94     10448067.27
#Sta/Elev= 30
  4209.9  398.28  4329.9  397.42  4714.9  391.81  4739.5  391.39  4778.3  389.18
  4837.3  387.84  4842.4  388.49    4870  387.53  4912.1   387.5  4937.1  387.42
  4939.8  386.92  4943.1  387.42  4956.1  388.39  4965.4  389.08  5006.2  387.59
  5017.1  388.26  5022.8  389.49  5028.2  389.17  5048.7  389.83    5054  388.91
  5067.7  388.26  5085.5  387.83  5251.2  390.21  5352.7  390.92  5637.3  393.86
  5787.5  395.34  5971.7  396.61  6083.7  396.37  6204.2  397.75  6272.4  397.53
#Mann= 12 ,-1 , 0
  4209.9     .08       0  4714.9     .05       0  4912.1      .1       0
  4937.1     .07       0  4943.1      .1       0  4956.1     .08       0
  4965.4      .1       0  5067.7     .08       0  5251.2     .05       0
  5352.7     .08       0  5637.3     .05       0  5787.5     .08       0
Bank Sta=4937.1,4943.1
XS Rating Curve= 0 ,0
Exp/Cntr=0.3,0.1

Type RM Length L Ch R = 1 ,28258   ,134,134,134
BEGIN DESCRIPTION:
MILL CREEK 55.0
END DESCRIPTION:
XS GIS Cut Line= 5
      3568760.83      10446089.6      3568628.02      10446842.2
      3568690.52     10447008.87      3568792.08     10447446.37
      3568974.37     10448084.37
#Sta/Elev= 30
    4144  398.79  4257.8  398.24  4395.2  395.77  4627.1  393.09  4660.9  392.11
    4735  389.26    4786   388.9  4799.7  389.46  4853.9  387.87    4859   388.5
  4887.4  388.09  4918.3  389.29  4950.7  388.29  4961.6  388.51  4964.5  388.06
  4971.7  388.83  4982.4  388.69  5000.8  387.45  5003.5  386.95  5006.8  387.45
  5035.8  388.96  5090.2  388.83  5157.7  390.16  5397.1  392.11  5588.9  394.93
  5936.1  396.16  5986.7  397.02  6019.3  396.52  6050.5  397.46  6198.9  397.61
#Mann= 7 ,-1 , 0
    4144     .08       0  4660.9     .05       0    4786     .08       0
  4950.7      .1       0  4961.6     .08       0  5000.8     .07       0
  5006.8     .08       0
Bank Sta=4982.4,5035.8
XS Rating Curve= 0 ,0
Exp/Cntr=0.3,0.1

Type RM Length L Ch R = 1 ,28124   ,30,30,30
BEGIN DESCRIPTION:
MILL CREEK 54.1
END DESCRIPTION:
XS GIS Cut Line= 4
      3568608.99     10446130.94      3568513.03     10446853.22
      3568554.26     10447057.22       3568723.3     10447657.52
#Sta/Elev= 30
  4152.5  399.69  4193.6  399.43  4240.8  398.15  4344.9  397.15  4397.5  397.28
  4465.7  395.96  4516.4  395.81  4647.5   393.7  4773.9  390.69    4779  391.12
  4798.8  390.18  4847.2  390.52  4869.4  389.72  4898.3  389.46  4930.5  390.13
    4949  389.52  4954.1   390.1  4971.3  389.37  4991.7  387.44  4996.7  386.17
  4999.5  385.67  5002.7  386.17  5022.3  389.52  5042.8  388.97  5104.6  389.25
  5114.6  389.67  5138.6  389.62  5530.6  394.64  5673.8   396.6  5712.9  397.27
#Mann= 5 ,-1 , 0
  4152.5     .08       0  4996.7     .07       0  5002.7     .08       0
  5530.6     .05       0  5673.8     .08       0
Bank Sta=4971.3,5022.3
XS Rating Curve= 0 ,0
Exp/Cntr=0.3,0.1

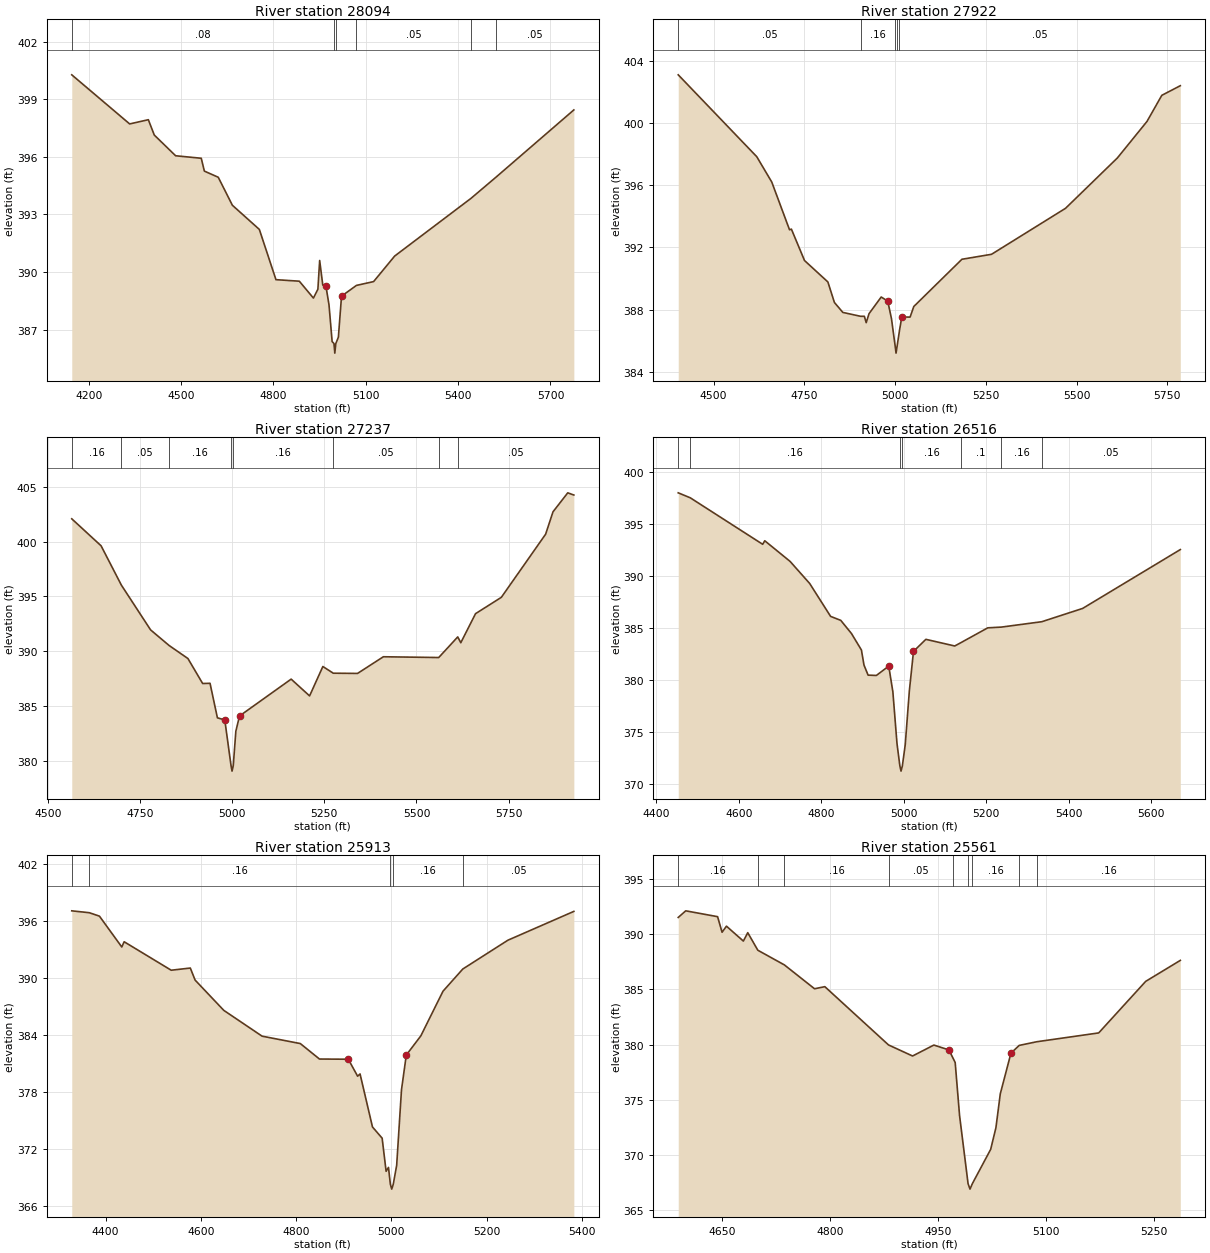
Type RM Length L Ch R = 1 ,28094   ,172,172,172
BEGIN DESCRIPTION:
MILL CREEK 54.11
END DESCRIPTION:
XS GIS Cut Line= 4
      3568567.26     10446125.58      3568471.77     10446765.81
      3568536.87     10447149.93      3568686.62     10447725.04
#Sta/Elev= 30
  4144.7  400.28  4332.8  397.72  4393.5  397.94  4412.8  397.14  4482.1  396.06
  4565.4  395.93  4575.5  395.26  4620.6  394.94  4666.5  393.48  4754.1  392.22
  4808.1   389.6    4884  389.52  4929.8  388.64  4944.3   389.1  4950.1   390.6
  4960.2  389.32  4970.4  389.27  4980.5  388.28  4990.6  386.37  4996.6  386.27
  4999.3  385.77  5002.6  386.27  5010.9   386.6  5021.1  388.74  5069.5   389.3
  5125.4   389.5  5193.7  390.83  5441.8  393.84  5522.7  394.94  5775.9  398.45
#Mann= 6 ,-1 , 0
  4144.7     .08       0  4996.6     .07       0  5002.6     .08       0
  5069.5     .05       0  5441.8     .08       0  5522.7     .05       0
Bank Sta=4970.4,5021.1
XS Rating Curve= 0 ,0
Exp/Cntr=0.3,0.1

Type RM Length L Ch R = 1 ,27922   ,685,685,685
BEGIN DESCRIPTION:
MILL CREEK 54.0
END DESCRIPTION:
XS GIS Cut Line= 3
      3568192.11     10446391.67      3568342.11     10446991.64
      3568492.11     10447741.65
#Sta/Elev= 30
  4402.5  403.11  4618.9  397.84  4660.2  396.21  4709.1  393.14  4714.3  393.18
  4750.4  391.16  4814.8  389.78  4832.8  388.46    4856  387.82  4904.9  387.57
  4915.3  387.57  4920.4  387.16  4928.2  387.74  4961.7  388.81  4979.7  388.55
    4990  387.42  4999.9   385.7  5002.6   385.2  5005.9   385.7  5012.1  386.66
  5018.4  387.52  5041.3  387.52  5051.5   388.2  5184.1  391.24  5265.7  391.56
  5469.6  394.52  5612.4  397.76    5694  400.11  5734.8  401.79  5785.8  402.41
#Mann= 5 ,-1 , 0
  4402.5     .05       0  4904.9     .16       0  4999.9     .07       0
  5005.9     .16       0  5012.1     .05       0
Bank Sta=4979.7,5018.4
XS Rating Curve= 0 ,0
Exp/Cntr=0.3,0.1

Type RM Length L Ch R = 1 ,27237   ,721,721,721
BEGIN DESCRIPTION:
MILL CREEK 53.0
END DESCRIPTION:
XS GIS Cut Line= 4
      3567577.69     10446653.56      3567779.52     10446844.54
      3567794.72     10447654.01      3567801.19     10447928.16
#Sta/Elev= 30
  4565.1  402.08  4644.6  399.62  4699.7  396.03  4778.9  391.95    4829  390.53
  4880.1  389.34  4920.1  387.06  4940.1  387.08  4960.1  383.93  4980.1  383.74
  4997.1  379.57  4999.8  379.07  5003.1  379.57  5010.1  382.71  5020.1   384.1
  5160.1  387.46  5210.1  385.93  5246.1  388.61  5274.4     388  5340.2  387.98
  5410.2   389.5  5560.4  389.43  5611.9  391.31  5620.2  390.78  5660.2  393.43
  5730.2  394.92  5850.3  400.68  5870.3  402.72  5910.3  404.45  5926.8  404.25
#Mann= 8 ,-1 , 0
  4565.1     .16       0  4699.7     .05       0    4829     .16       0
  4997.1     .07       0  5003.1     .16       0  5274.4     .05       0
  5560.4     .16       0  5611.9     .05       0
Bank Sta=4980.1,5020.1
XS Rating Curve= 0 ,0
Exp/Cntr=0.3,0.1

Type RM Length L Ch R = 1 ,26516   ,603,603,603
BEGIN DESCRIPTION:
MILL CREEK 52.0
END DESCRIPTION:
XS GIS Cut Line= 3
      3567143.68     10446647.11      3567215.29     10447085.43
      3567210.96     10447858.38
#Sta/Elev= 30
  4453.4  398.03  4482.6  397.55  4658.1  393.07  4663.2  393.41  4724.6  391.42
  4772.1  389.29  4822.8  386.12  4847.4  385.74  4873.4  384.47  4897.5  382.88
  4903.7  381.43  4913.7  380.46  4933.7  380.43  4963.7  381.33  4973.7  378.86
  4983.7  373.87  4990.7  371.71  4993.5  371.21  4996.7  371.71  5003.7  373.76
  5013.7  378.96  5023.7  382.75  5053.7  383.91  5123.7  383.27  5138.6  383.59
  5203.8  385.02  5236.7  385.09  5334.8  385.61  5433.8  386.89  5670.5  392.56
#Mann= 7 ,-1 , 0
  4453.4      .1       0  4482.6     .16       0  4990.7     .07       0
  4996.7     .16       0  5138.6      .1       0  5236.7     .16       0
  5334.8     .05       0
Bank Sta=4963.7,5023.7
XS Rating Curve= 0 ,0
Exp/Cntr=0.3,0.1

Type RM Length L Ch R = 1 ,25913   ,352,352,352
BEGIN DESCRIPTION:
MILL CREEK 51.0
END DESCRIPTION:
XS GIS Cut Line= 3
      3566826.84     10446783.76      3566776.92     10447328.49
      3566690.38     10447828.24
#Sta/Elev= 30
  4329.1  397.11  4365.9  396.91  4387.2  396.55  4434.1   393.3  4439.1  393.85
  4537.9  390.85    4578  391.08  4588.1  389.81  4648.3  386.62  4728.7   383.9
    4809  383.12  4849.2  381.49  4909.8  381.47  4929.3  379.68  4934.4  379.92
  4960.5  374.33  4980.8  373.15  4989.1  369.66  4994.1  370.07  4998.1  368.28
  5000.9  367.78  5004.1  368.28  5011.3  370.29  5021.4  378.24  5031.5  381.91
    5062  383.93  5108.6  388.64  5150.2  390.98  5244.7  394.01  5383.3  397.05
#Mann= 5 ,-1 , 0
  4329.1     .08       0  4365.9     .16       0  4998.1     .07       0
  5004.1     .16       0  5150.2     .05       0
Bank Sta=4909.8,5031.5
XS Rating Curve= 0 ,0
Exp/Cntr=0.3,0.1

Type RM Length L Ch R = 1 ,25561   ,72,72,72
BEGIN DESCRIPTION:
MILL CREEK 50.1
END DESCRIPTION:
XS GIS Cut Line= 2
      3566722.23     10446986.91      3566320.09     10447556.94
#Sta/Elev= 30
  4588.9  391.51  4599.3  392.11  4643.6  391.58  4649.8  390.17  4655.9  390.72
  4679.4  389.37  4685.5  390.13  4699.5  388.54  4736.4  387.21  4778.3  385.05
  4792.6  385.24  4881.1  379.96  4914.5  378.96  4944.1  379.95    4965  379.51
  4970.2  378.83  4973.7  378.37  4979.8  373.56  4991.6   367.4  4994.3   366.9
  4997.6   367.4    5023   370.5  5030.3  372.46  5036.4  375.54  5051.2  379.22
  5062.7  379.92    5087  380.25  5173.1  381.05  5238.4  385.72  5286.5  387.62
#Mann= 9 ,-1 , 0
  4588.9     .16       0  4699.5     .08       0  4736.4     .16       0
  4881.1     .05       0  4970.2     .16       0  4991.6     .07       0
  4997.6     .16       0  5062.7     .05       0    5087     .16       0
Bank Sta=4965,5051.2
XS Rating Curve= 0 ,0
Exp/Cntr=0.3,0.1

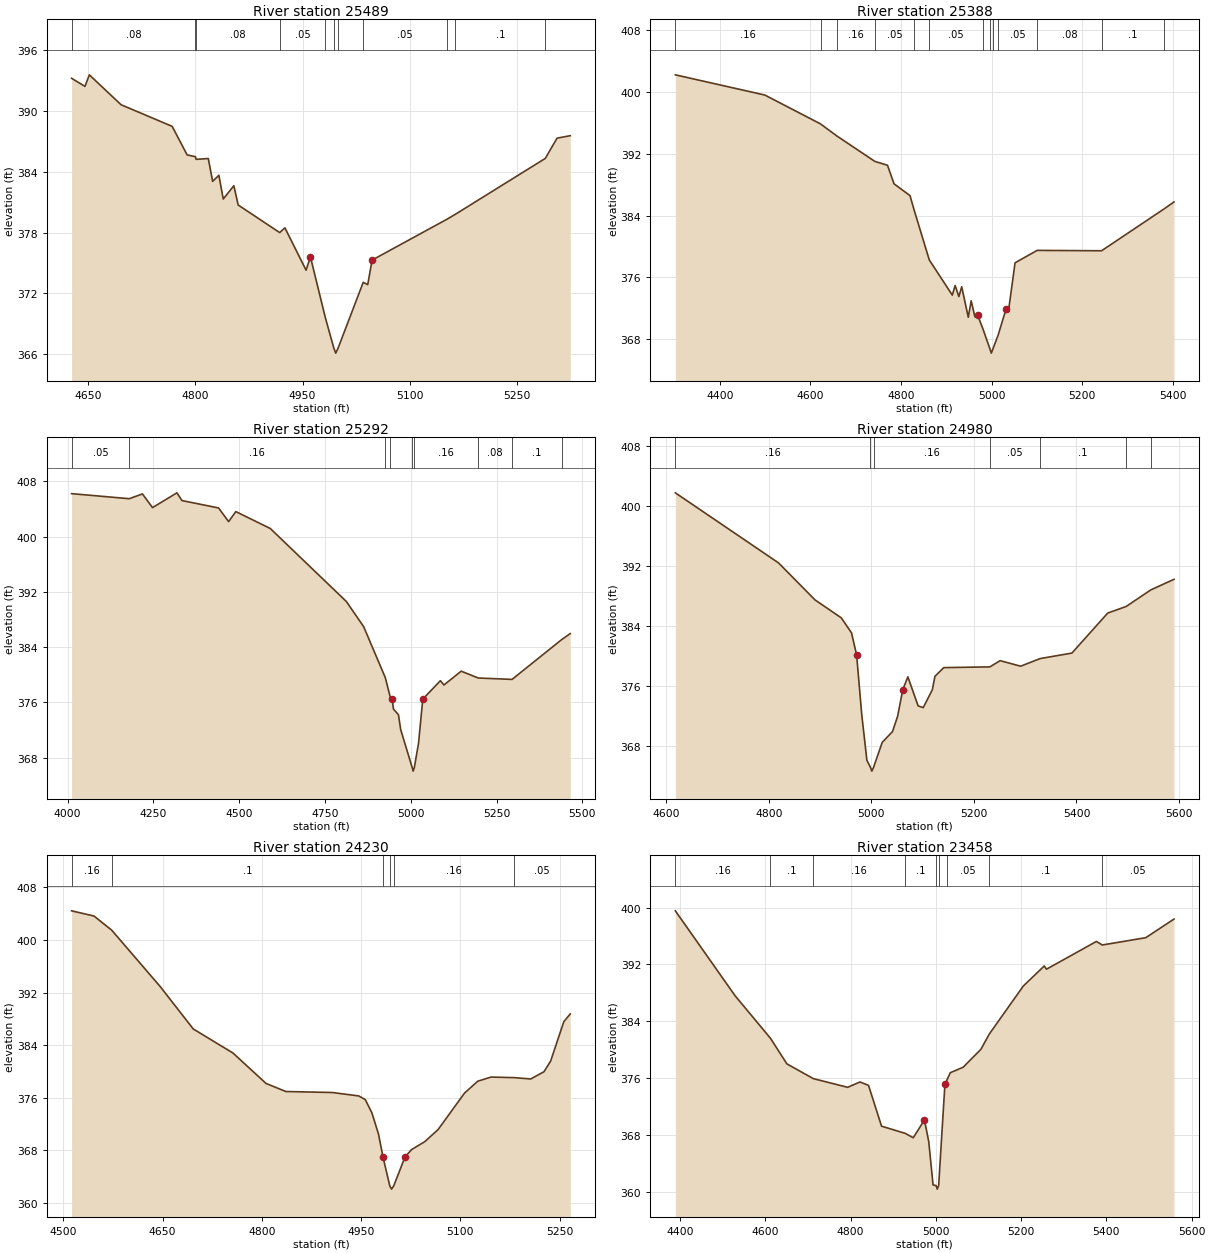
Type RM Length L Ch R = 1 ,25489   ,101,101,101
BEGIN DESCRIPTION:
MILL CREEK 50.0
END DESCRIPTION:
XS GIS Cut Line= 2
      3566658.42     10446962.18      3566256.57      10447531.8
#Sta/Elev= 30
  4627.1  393.21  4645.8  392.41  4651.9  393.55  4696.3   390.6  4767.7  388.47
  4788.6  385.66  4800.3  385.48  4801.1  385.22  4818.2   385.3  4824.3  383.05
    4833  383.65  4839.1  381.31  4853.9  382.62    4860  380.72    4918     378
  4925.3  378.47  4954.9   374.3    4961   375.6  4981.9   369.6  4993.7  366.62
  4996.4  366.12  4999.7  366.62  5034.8   373.1  5041.1  372.87  5047.2  375.29
  5151.7  379.31  5163.5   379.8  5289.3  385.31  5305.8  387.31  5324.2  387.55
#Mann= 11 ,-1 , 0
  4627.1     .08       0  4800.3     .05       0  4801.1     .08       0
    4918     .05       0  4981.9     .08       0  4993.7     .07       0
  4999.7     .08       0  5034.8     .05       0  5151.7     .16       0
  5163.5      .1       0  5289.3     .16       0
Bank Sta=4961,5047.2
XS Rating Curve= 0 ,0
Exp/Cntr=0.3,0.1

Type RM Length L Ch R = 1 ,25388   ,96,96,96
BEGIN DESCRIPTION:
MILL CREEK 49.0
END DESCRIPTION:
XS GIS Cut Line= 5
      3566782.42     10446654.96      3566373.27     10447187.43
      3566339.42     10447261.64      3566202.77     10447372.37
      3566187.15       10447544.
#Sta/Elev= 30
  4301.6  402.25  4499.2  399.63  4622.2  395.89  4658.2  394.33  4742.4  391.02
  4770.1  390.53  4784.6  388.12  4819.9  386.59  4829.2  384.68  4862.5  378.25
  4913.3  373.69  4919.6  374.94  4927.8   373.5  4934.1  374.77  4948.6  370.82
    4955  372.95  4963.2  370.88  4969.5  371.06  4981.5  369.22  4996.7  366.67
  4999.5  366.17  5002.7  366.67  5014.4  368.48  5031.7  371.83  5037.2  371.56
  5051.9  377.88  5100.7  379.49    5243  379.44  5380.8  384.86  5402.9  385.77
#Mann= 13 ,-1 , 0
  4301.6     .16       0  4622.2     .08       0  4658.2     .16       0
  4742.4     .05       0  4829.2     .16       0  4862.5     .05       0
  4981.5     .08       0  4996.7     .07       0  5002.7     .08       0
  5014.4     .05       0  5100.7     .08       0    5243      .1       0
  5380.8     .16       0
Bank Sta=4969.5,5031.7
XS Rating Curve= 0 ,0
Exp/Cntr=0.3,0.1

Type RM Length L Ch R = 1 ,25292   ,312,312,312
BEGIN DESCRIPTION:
MILL CREEK 48.0
END DESCRIPTION:
XS GIS Cut Line= 5
       3566907.4     10446358.12      3566357.65     10447113.21
      3566232.12      10447191.7       3566200.1     10447255.13
       3566158.5     10447551.81
#Sta/Elev= 30
  4011.8  406.21  4179.6  405.48  4218.2  406.17  4247.6  404.19  4318.7  406.33
  4333.3  405.21    4440  404.14  4469.3  402.16  4490.2  403.61  4590.6  401.17
  4812.4  390.59  4862.6  386.96  4925.7  379.58  4940.6  376.67  4945.8  376.46
  4949.4  375.03  4964.1   374.2  4970.6  372.04  5004.2  366.54  5006.9  366.04
  5010.2  366.54  5022.5  370.06  5034.9  376.46  5086.2  379.13  5096.6  378.51
  5146.8  380.51  5196.5  379.52    5295  379.32  5440.3  385.11  5464.5  385.95
#Mann= 9 ,-1 , 0
  4011.8     .05       0  4179.6     .16       0  4925.7     .05       0
  4940.6     .16       0  5004.2     .07       0  5010.2     .16       0
  5196.5     .08       0    5295      .1       0  5440.3     .16       0
Bank Sta=4945.8,5034.9
XS Rating Curve= 0 ,0
Exp/Cntr=0.3,0.1

Type RM Length L Ch R = 1 ,24980   ,750,750,750
BEGIN DESCRIPTION:
MILL CREEK 47.0
END DESCRIPTION:
XS GIS Cut Line= 3
      3566216.79     10446703.29      3566081.35      10446945.5
      3566068.33     10447640.77
#Sta/Elev= 30
  4617.4  401.75  4818.8  392.39  4889.8  387.46  4941.1  385.06  4961.1  383.06
  4971.1   380.1  4981.1  372.14  4991.1  366.05  4998.1  365.09  5000.8  364.59
  5004.1  365.09  5021.1  368.44  5041.1  369.87  5051.1  371.92  5061.1  375.45
  5071.1  377.18  5091.1   373.3  5101.1  373.07  5118.9  375.47  5123.9  377.25
  5141.1  378.41  5231.1  378.51  5251.1  379.34  5291.1   378.6  5329.2  379.62
  5391.1  380.35  5461.1   385.7  5496.9  386.57  5545.1  388.79  5590.3   390.2
#Mann= 7 ,-1 , 0
  4617.4     .16       0  4998.1     .07       0  5004.1     .16       0
  5231.1     .05       0  5329.2      .1       0  5496.9     .16       0
  5545.1      .1       0
Bank Sta=4971.1,5061.1
XS Rating Curve= 0 ,0
Exp/Cntr=0.3,0.1

Type RM Length L Ch R = 1 ,24230   ,772,772,772
BEGIN DESCRIPTION:
MILL CREEK 46.0
END DESCRIPTION:
XS GIS Cut Line= 2
      3565539.51     10446787.87      3565534.31     10447541.35
#Sta/Elev= 30
  4512.5  404.44  4546.3  403.65    4573  401.51  4646.3  392.93  4696.3  386.47
  4756.3  382.81  4806.3  378.18  4836.3  376.95  4906.3   376.8  4946.3  376.28
  4956.3  375.72  4966.3   373.7  4976.3  370.47  4983.1  366.97  4993.3   362.6
    4996   362.1  4999.3   362.6  5016.3  366.99  5026.3  368.12  5046.3  369.33
  5066.3  371.16  5106.3  376.72  5126.3  378.52  5146.3  379.15  5181.3  379.06
  5206.3  378.86  5226.3  379.96  5236.3  381.56  5256.3  387.58    5266  388.75
#Mann= 6 ,-1 , 0
  4512.5     .16       0    4573      .1       0  4983.1     .16       0
  4993.3     .07       0  4999.3     .16       0  5181.3     .05       0
Bank Sta=4983.1,5016.3
XS Rating Curve= 0 ,0
Exp/Cntr=0.3,0.1

Type RM Length L Ch R = 1 ,23458   ,446,446,446
BEGIN DESCRIPTION:
MILL CREEK 45.0
END DESCRIPTION:
XS GIS Cut Line= 3
      3564986.74     10446803.16       3565025.8     10447054.87
      3564908.61     10447962.01
#Sta/Elev= 30
  4389.2  399.54  4529.3  387.59  4612.3   381.6  4650.8     378  4712.9  375.92
  4793.4   374.7  4822.2  375.45  4842.3  374.97  4872.8  369.23  4928.4  368.22
  4947.1   367.6  4973.4   370.1  4983.5  367.05  4993.6  360.96  5000.7  360.87
  5003.4  360.37  5006.7  360.87  5021.4   375.1  5026.9  375.83  5033.9  376.75
  5064.2  377.53  5105.8  380.05  5125.3  382.18  5205.3  388.96  5254.4  391.78
  5259.5  391.32  5376.7  395.23  5390.4  394.73  5492.5  395.76  5558.6  398.38
#Mann= 9 ,-1 , 0
  4389.2     .16       0  4612.3      .1       0  4712.9     .16       0
  4928.4      .1       0  5000.7     .07       0  5006.7      .1       0
  5026.9     .05       0  5125.3      .1       0  5390.4     .05       0
Bank Sta=4973.4,5021.4
XS Rating Curve= 0 ,0
Exp/Cntr=0.3,0.1