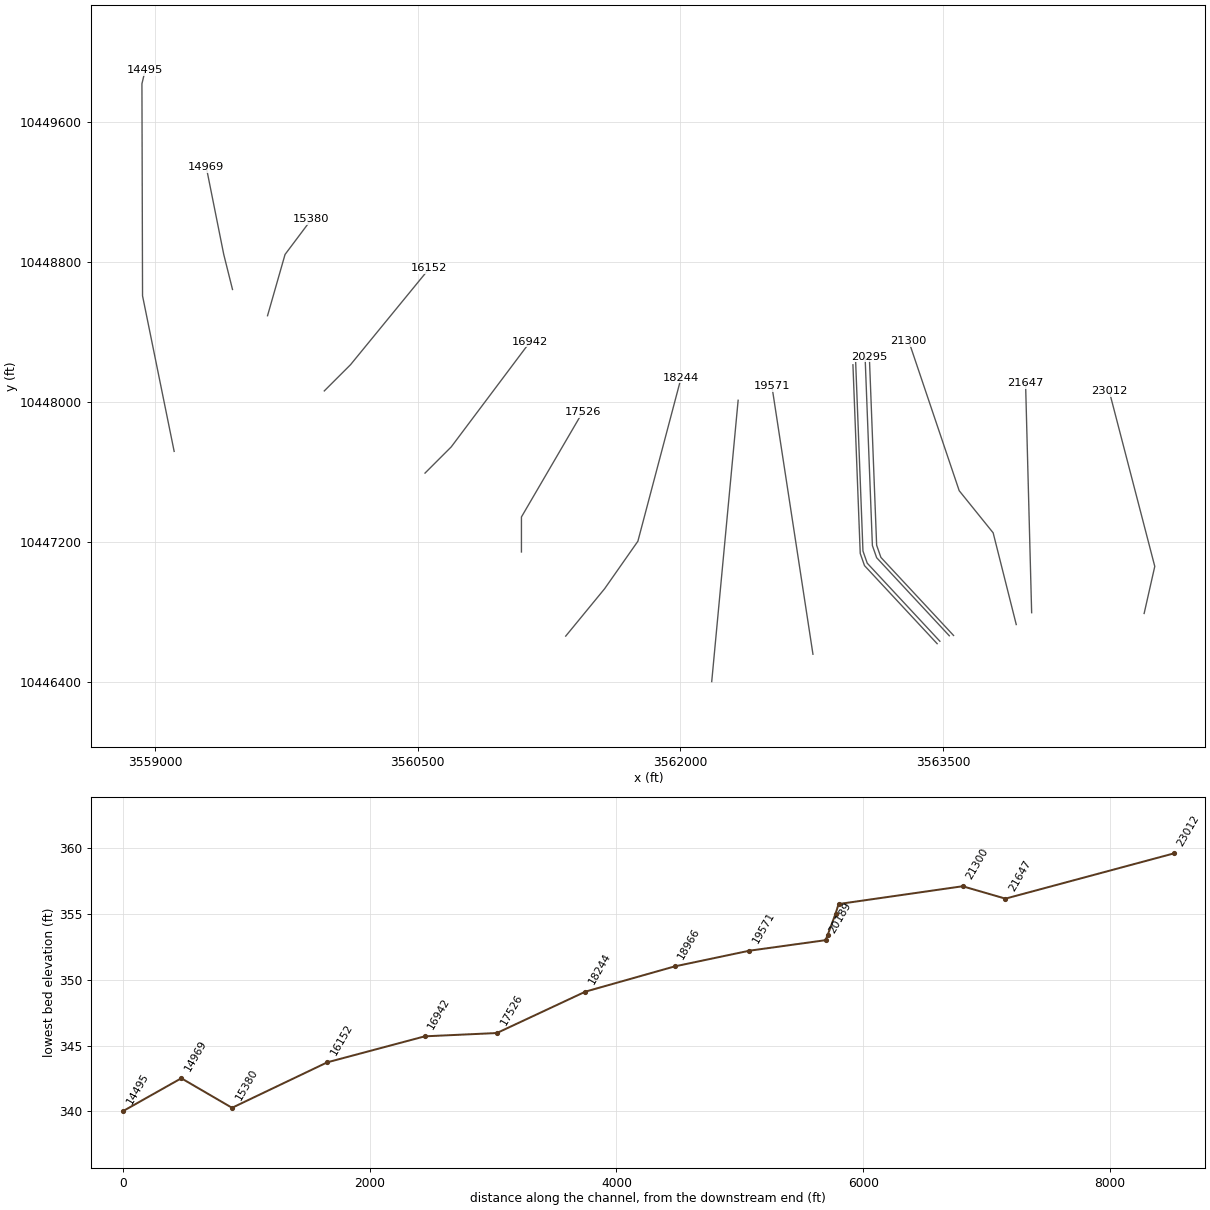
HEC-RAS study MILL CREEK.prj: MILL CREEK Base Level Engineering

--- MILL CREEK.g01 (geometry) --- (continued)

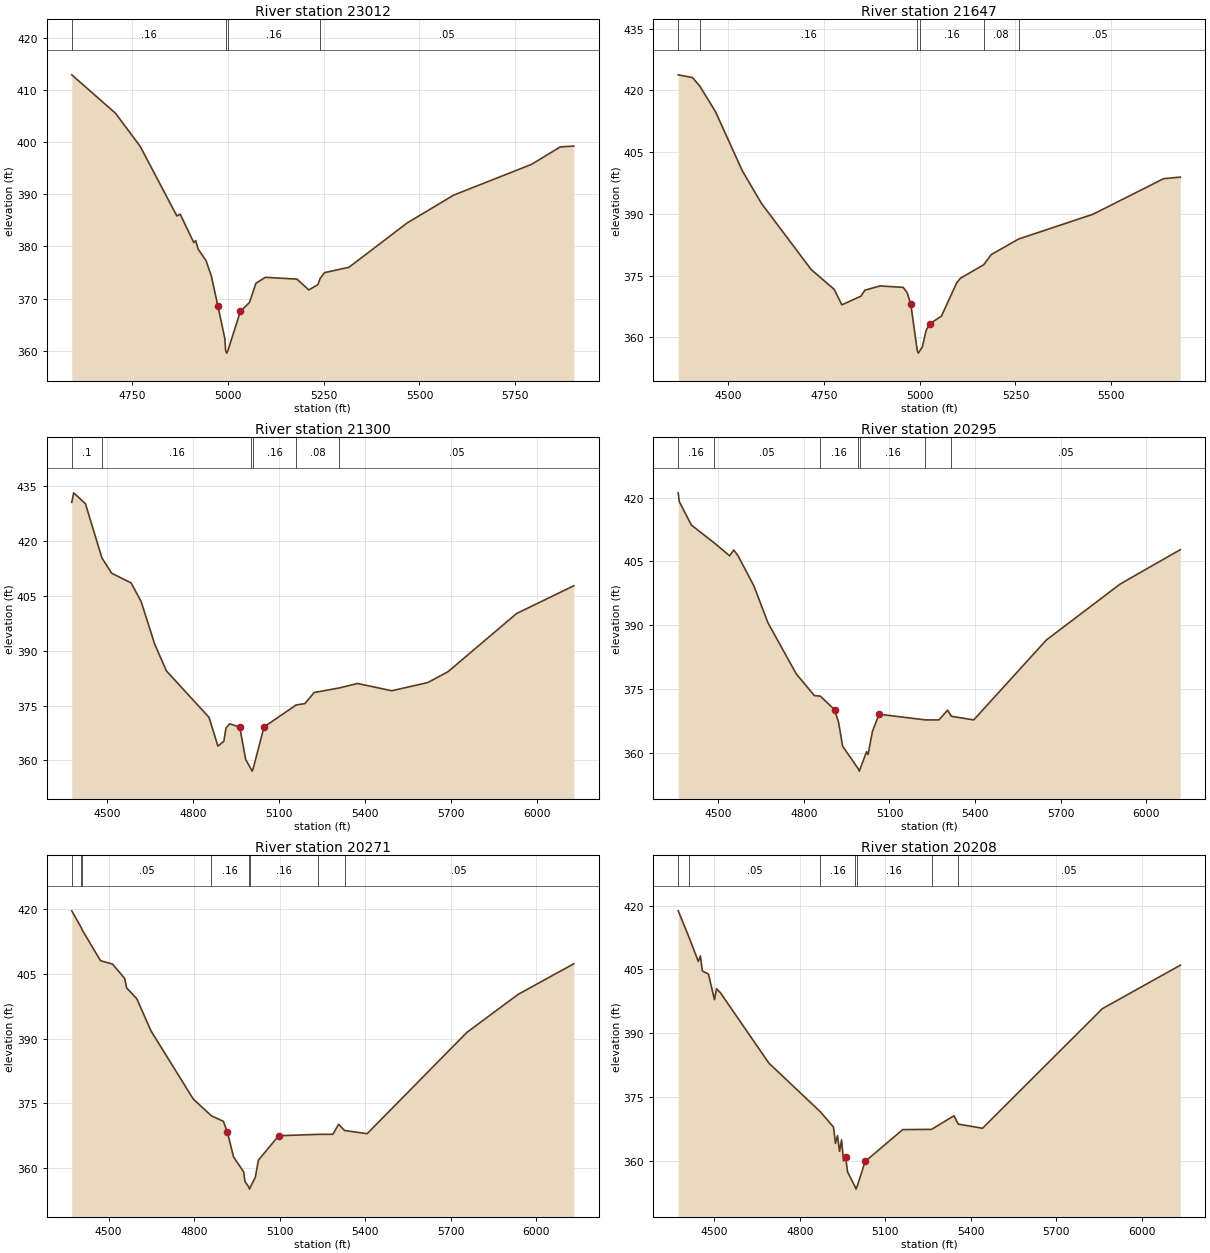
Type RM Length L Ch R = 1 ,23012   ,1365,1365,1365
BEGIN DESCRIPTION:
MILL CREEK 44.0
END DESCRIPTION:
XS GIS Cut Line= 3
       3564648.2     10446790.15      3564708.96     10447059.21
      3564448.54     10448061.81
#Sta/Elev= 30
  4591.6  412.88  4705.9  405.52  4770.4  399.18  4866.1  385.85    4875  386.18
  4910.3  380.75  4915.5  381.12  4921.6  379.51  4942.3   377.3  4956.1  374.38
  4973.3  368.63  4991.5  362.36  4993.6  360.07  4996.4  359.57  4999.6  360.07
    5032  367.56  5055.9  369.28  5072.6  372.94  5097.2  374.09  5179.9  373.75
  5210.9  371.68  5234.8  372.71  5240.6   373.9  5252.2  374.99  5315.9  376.02
  5467.7   384.5  5589.4  389.84  5792.2  395.71  5868.1  399.08  5903.3  399.23
#Mann= 4 ,-1 , 0
  4591.6     .16       0  4993.6     .07       0  4999.6     .16       0
  5240.6     .05       0
Bank Sta=4973.3,5032
XS Rating Curve= 0 ,0
Exp/Cntr=0.3,0.1

Type RM Length L Ch R = 1 ,21647   ,347,347,347
BEGIN DESCRIPTION:
MILL CREEK 42.0
END DESCRIPTION:
XS GIS Cut Line= 2
      3564005.83     10446794.48      3563971.11     10448105.22
#Sta/Elev= 30
  4369.3  423.81  4406.5  423.15  4425.6  421.07  4466.5  414.87  4536.5   400.5
  4586.5  392.57  4716.6  376.45  4776.6  371.65  4796.6  367.88  4846.6     370
  4856.6  371.44  4896.6  372.48  4956.7  372.13  4966.7  370.91  4976.7  368.05
  4993.7  356.64  4996.4  356.14  4999.7  356.64  5006.7  357.64  5016.7  361.66
  5026.7  363.31  5056.7  365.14  5096.7  373.27  5106.7  374.38    5167  377.62
  5186.7   380.1  5258.1  383.88    5453  389.93  5636.9  398.56  5680.5  398.94
#Mann= 6 ,-1 , 0
  4369.3      .1       0  4425.6     .16       0  4993.7     .07       0
  4999.7     .16       0    5167     .08       0  5258.1     .05       0
Bank Sta=4976.7,5026.7
XS Rating Curve= 0 ,0
Exp/Cntr=0.3,0.1

Type RM Length L Ch R = 1 ,21300   ,1005,1005,1005
BEGIN DESCRIPTION:
MILL CREEK 40.0
END DESCRIPTION:
XS GIS Cut Line= 4
      3563917.88     10446726.83      3563785.95      10447251.1
      3563592.11     10447491.64      3563303.59     10448347.48
#Sta/Elev= 30
  4376.5  430.61  4383.2  433.22  4424.3  430.24  4481.7  415.42  4515.5  411.24
  4583.6  408.58  4618.6   403.5  4665.8  391.85  4706.9   384.5  4855.8  371.78
  4886.7  363.93  4907.3  365.23  4914.8  368.86  4927.7  370.04  4962.9  369.12
  4983.7  360.24  5003.1  357.58  5005.8  357.08  5009.1  357.58  5047.7  369.18
  5160.1  375.19  5190.1  375.55  5222.8   378.6  5310.7  379.84  5373.8  381.06
  5493.6  379.07  5619.6  381.32  5690.4  384.31  5929.1  400.19  6129.2   407.8
#Mann= 6 ,-1 , 0
  4376.5      .1       0  4481.7     .16       0  5003.1     .07       0
  5009.1     .16       0  5160.1     .08       0  5310.7     .05       0
Bank Sta=4962.9,5047.7
XS Rating Curve= 0 ,0
Exp/Cntr=0.3,0.1

Type RM Length L Ch R = 1 ,20295   ,24,24,24
BEGIN DESCRIPTION:
MILL CREEK 39.03
END DESCRIPTION:
XS GIS Cut Line= 4
      3563559.84     10446664.46      3563144.94     10447110.61
      3563120.63     10447180.06        3563079.     10448257.42
#Sta/Elev= 30
  4359.2  421.12  4362.7  419.09  4405.2  413.56    4485  409.38  4539.6  406.32
  4553.7  407.68  4567.9  406.47  4624.6  399.25  4673.9  390.58  4773.1  378.59
  4836.6  373.49  4857.5  373.35  4907.5  370.18  4921.6  367.18  4935.8  361.59
  4991.1  356.23  4993.9  355.73  4997.1  356.23  5019.8   360.3  5025.1  359.65
  5040.2  365.03  5063.6   369.1  5225.8  367.77  5273.8  367.77  5303.8  370.04
  5317.3  368.62  5395.6  367.76  5650.2  386.53  5909.7  399.71  6120.2  407.76
#Mann= 7 ,-1 , 0
  4359.2     .16       0    4485     .05       0  4857.5     .16       0
  4991.1     .07       0  4997.1     .16       0  5225.8     .08       0
  5317.3     .05       0
Bank Sta=4907.5,5063.6
XS Rating Curve= 0 ,0
Exp/Cntr=0.3,0.1

Type RM Length L Ch R = 1 ,20271   ,63,63,63
BEGIN DESCRIPTION:
MILL CREEK 39.0
END DESCRIPTION:
XS GIS Cut Line= 4
      3563535.54     10446662.72      3563120.63     10447108.87
      3563096.33     10447178.32      3563054.66     10448256.48
#Sta/Elev= 30
  4370.9  419.69    4405  415.69  4407.7  415.23  4471.6  408.11  4514.1  407.31
  4556.6  403.97  4563.5  401.78  4599.2  399.25  4648.5  391.83    4797  375.97
  4860.8  372.05    4903  370.76  4917.2  368.19  4938.7  362.49  4973.9  359.04
  4978.6   356.8  4991.9  355.51  4994.7  355.01  4997.9  355.51  5014.9  357.76
  5025.9  361.75  5097.1  367.42  5235.9  367.74  5287.2  367.76  5307.3  370.08
  5328.1  368.64  5407.3  367.89  5757.6  391.45  5937.7  400.29  6132.7  407.39
#Mann= 8 ,-1 , 0
  4370.9     .16       0    4405      .1       0  4407.7     .05       0
  4860.8     .16       0  4991.9     .07       0  4997.9     .16       0
  5235.9     .08       0  5328.1     .05       0
Bank Sta=4917.2,5097.1
XS Rating Curve= 0 ,0
Exp/Cntr=0.3,0.1

Type RM Length L Ch R = 1 ,20208   ,19,19,19
BEGIN DESCRIPTION:
MILL CREEK 39.01
END DESCRIPTION:
XS GIS Cut Line= 4
      3563481.71     10446631.48      3563066.81     10447077.62
      3563042.51     10447147.07      3563000.84     10448225.24
#Sta/Elev= 30
    4373  418.75  4411.2  412.48  4443.4  406.88  4450.8  408.16  4457.6  404.62
  4479.1  403.91  4500.1  397.89  4507.4  400.46  4521.6  399.47  4691.1     383
  4871.4   371.6  4917.9  367.98  4924.7  364.17    4932  365.99  4938.9  362.28
  4946.2  364.98    4953  360.03  4960.4  361.03  4967.2  357.46  4994.1  353.92
  4996.9  353.42  5000.1  353.92  5028.9  359.91  5160.5  367.39  5261.9  367.45
  5340.6  370.64  5355.3  368.69  5440.7  367.71    5861  395.77  6134.8  405.98
#Mann= 7 ,-1 , 0
    4373      .1       0  4411.2     .05       0  4871.4     .16       0
  4994.1     .07       0  5000.1     .16       0  5261.9     .08       0
  5355.3     .05       0
Bank Sta=4960.4,5028.9
XS Rating Curve= 0 ,0
Exp/Cntr=0.3,0.1

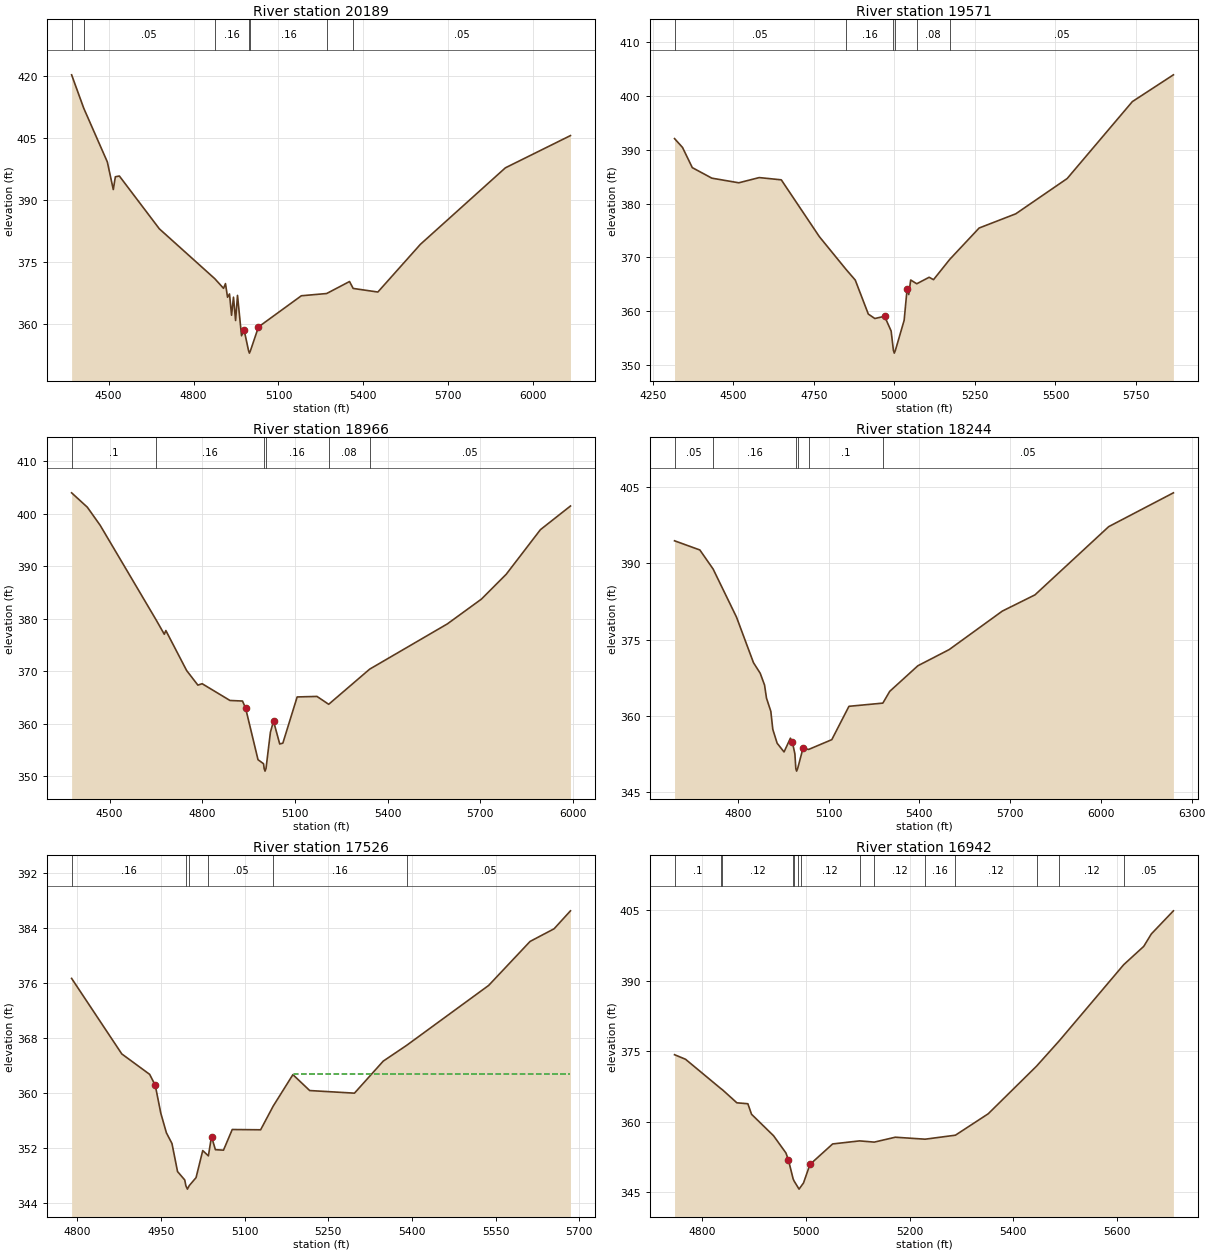
Type RM Length L Ch R = 1 ,20189   ,618,618,618
BEGIN DESCRIPTION:
MILL CREEK 39.02
END DESCRIPTION:
XS GIS Cut Line= 4
       3563466.1     10446617.57      3563051.19     10447063.74
      3563026.88     10447133.18      3562985.22     10448211.33
#Sta/Elev= 30
  4369.4  420.23  4412.4  412.14  4495.6  399.18  4516.6  392.51  4523.9   395.6
  4538.1  395.78  4679.3  383.02  4875.1  370.97    4906  368.64  4912.8  369.79
  4920.1  366.49    4927  367.29  4934.3  362.14  4941.1  366.51  4948.5  360.87
  4955.3  366.94  4969.5  357.18  4978.7  358.57  4994.6  353.49  4997.4  352.99
  5000.6  353.49  5029.4  359.32  5180.8  366.85  5270.1  367.39  5350.9  370.29
  5363.8  368.62    5451  367.75  5601.1  379.27  5901.3  397.76  6131.2  405.55
#Mann= 7 ,-1 , 0
  4369.4      .1       0  4412.4     .05       0  4875.1     .16       0
  4994.6     .07       0  5000.6     .16       0  5270.1     .08       0
  5363.8     .05       0
Bank Sta=4978.7,5029.4
XS Rating Curve= 0 ,0
Exp/Cntr=0.3,0.1

Type RM Length L Ch R = 1 ,19571   ,605,605,605
BEGIN DESCRIPTION:
MILL CREEK 38.0
END DESCRIPTION:
XS GIS Cut Line= 2
      3562756.92     10446557.21      3562522.68     10448087.59
#Sta/Elev= 30
  4317.9  392.09  4342.6  390.45    4373  386.69  4433.7  384.73  4517.3  383.87
  4580.7  384.84  4649.2  384.42  4767.5  373.84  4849.2  367.83  4878.8  365.77
  4919.3  359.45  4939.5  358.63  4969.8  359.04  4990.1   356.3  4997.2  352.69
  4999.9  352.19  5003.2  352.69  5030.5   358.3  5039.7  364.18  5044.7  363.09
  5050.8  365.79  5069.6  365.09  5108.1   366.3  5121.6  365.85  5171.9  369.62
  5263.2  375.46  5376.9   378.1  5536.4  384.66  5738.7  398.97  5866.1  403.95
#Mann= 6 ,-1 , 0
  4317.9     .05       0  4849.2     .16       0  4997.2     .07       0
  5003.2     .16       0  5069.6     .08       0  5171.9     .05       0
Bank Sta=4969.8,5039.7
XS Rating Curve= 0 ,0
Exp/Cntr=0.3,0.1

Type RM Length L Ch R = 1 ,18966   ,722,722,722
BEGIN DESCRIPTION:
MILL CREEK 36.0
END DESCRIPTION:
XS GIS Cut Line= 2
      3562178.79     10446400.98      3562329.66     10448008.51
#Sta/Elev= 30
  4377.1  404.01    4428  401.27  4469.6  397.82    4651  379.77  4677.1  377.07
  4682.1  377.78  4749.4  370.16  4785.8  367.38  4799.6  367.65  4889.6  364.46
  4930.2  364.35  4940.2  363.01  4980.4  353.18  4998.3  352.41  5000.3   351.5
  5003.1     351  5006.3   351.5  5020.6  358.42  5030.6  360.52  5050.7  356.17
  5060.8  356.33  5107.1  365.13  5171.2  365.23  5209.2  363.73  5341.7  370.42
  5593.1  379.04  5703.6  383.77  5783.9  388.51  5894.4  396.99  5991.7   401.5
#Mann= 6 ,-1 , 0
  4377.1      .1       0    4651     .16       0  5000.3     .07       0
  5006.3     .16       0  5209.2     .08       0  5341.7     .05       0
Bank Sta=4940.2,5030.6
XS Rating Curve= 0 ,0
Exp/Cntr=0.3,0.1

Type RM Length L Ch R = 1 ,18244   ,718,718,718
BEGIN DESCRIPTION:
MILL CREEK 35.0
END DESCRIPTION:
XS GIS Cut Line= 4
      3561344.97     10446660.81       3561567.2     10446931.65
      3561757.08     10447202.93      3562004.27     10448138.35
#Sta/Elev= 30
  4590.7  394.47  4674.4  392.66  4718.1  388.92  4795.6  379.42  4851.6  370.46
  4873.9  368.37  4888.2  366.05  4894.7  363.46    4909  360.87  4915.5  357.32
  4929.8  354.59  4952.7  352.87  4973.7  355.58  4979.8  354.92  4988.5  352.49
  4991.6  349.59  4994.3  349.09  4997.6  349.59  5015.5  353.63  5033.9  353.36
  5110.5  355.29  5167.2  361.86  5279.3  362.49  5301.9   364.8    5395  369.85
  5498.4  373.03  5674.2  380.62    5782  383.81  6025.9  397.26  6239.7  403.92
#Mann= 6 ,-1 , 0
  4590.7     .05       0  4718.1     .16       0  4991.6     .07       0
  4997.6     .16       0  5033.9      .1       0  5279.3     .05       0
Bank Sta=4979.8,5015.5
XS Rating Curve= 0 ,0
Exp/Cntr=0.3,0.1

Type RM Length L Ch R = 1 ,17526   ,584,584,584
BEGIN DESCRIPTION:
MILL CREEK 33.0
END DESCRIPTION:
XS GIS Cut Line= 3
      3561092.11      10447141.6      3561092.11     10447341.64
      3561442.12     10447941.67
#Sta/Elev= 30
  4789.7  376.67  4879.7  365.66  4929.7  362.68  4939.7  361.09  4949.7  357.01
  4959.7  354.16  4969.7   352.6  4979.7  348.51  4992.6  347.29  4994.6  346.45
  4997.4  345.95  5000.6  346.45  5012.9  347.63  5024.9  351.57    5035   350.8
  5040.6  353.61  5047.6   351.7  5062.1  351.63  5077.8  354.64  5128.7   354.6
  5151.3  358.06  5186.6  362.64  5216.7  360.32    5297  359.94  5348.6  364.61
  5390.6  366.91  5537.6  375.64    5612  382.06    5655   383.9  5684.4  386.52
#Mann= 6 ,-1 , 0
  4789.7     .16       0  4994.6     .07       0  5000.6     .16       0
    5035     .05       0  5151.3     .16       0  5390.6     .05       0
#XS Ineff= 2 , 0
                         5188.19          362.67
Permanent Ineff=
       F       F
Bank Sta=4939.7,5040.6
XS Rating Curve= 0 ,0
Exp/Cntr=0.3,0.1

Type RM Length L Ch R = 1 ,16942   ,790,790,790
BEGIN DESCRIPTION:
MILL CREEK 32.0
END DESCRIPTION:
XS GIS Cut Line= 3
      3560541.44     10447592.36      3560691.41     10447742.34
      3561141.41     10448342.34
#Sta/Elev= 30
  4746.8  374.29    4768  373.32  4836.6  367.04  4838.7  366.88    4867  364.06
  4888.2  363.86  4895.3  361.62  4937.7  357.06  4961.6   353.4  4966.3  351.96
  4975.5  347.89  4977.3  347.44  4984.2   346.2  4986.9   345.7  4990.2   346.2
  4995.5  347.01    5008  350.95  5051.7  355.31  5103.7  355.96    5132   355.7
  5172.6  356.74  5230.1  356.32  5288.5  357.17  5351.7  361.72    5445  371.86
  5489.2   377.3    5613  393.43  5651.7  397.33  5666.3  399.97  5708.9  404.89
#Mann= 14 ,-1 , 0
  4746.8      .1       0  4836.6     .16       0  4838.7     .12       0
  4975.5     .16       0  4977.3     .12       0  4984.2     .07       0
  4990.2     .12       0  5103.7     .05       0    5132     .12       0
  5230.1     .16       0  5288.5     .12       0    5445     .05       0
  5489.2     .12       0    5613     .05       0
Bank Sta=4966.3,5008
XS Rating Curve= 0 ,0
Exp/Cntr=0.3,0.1

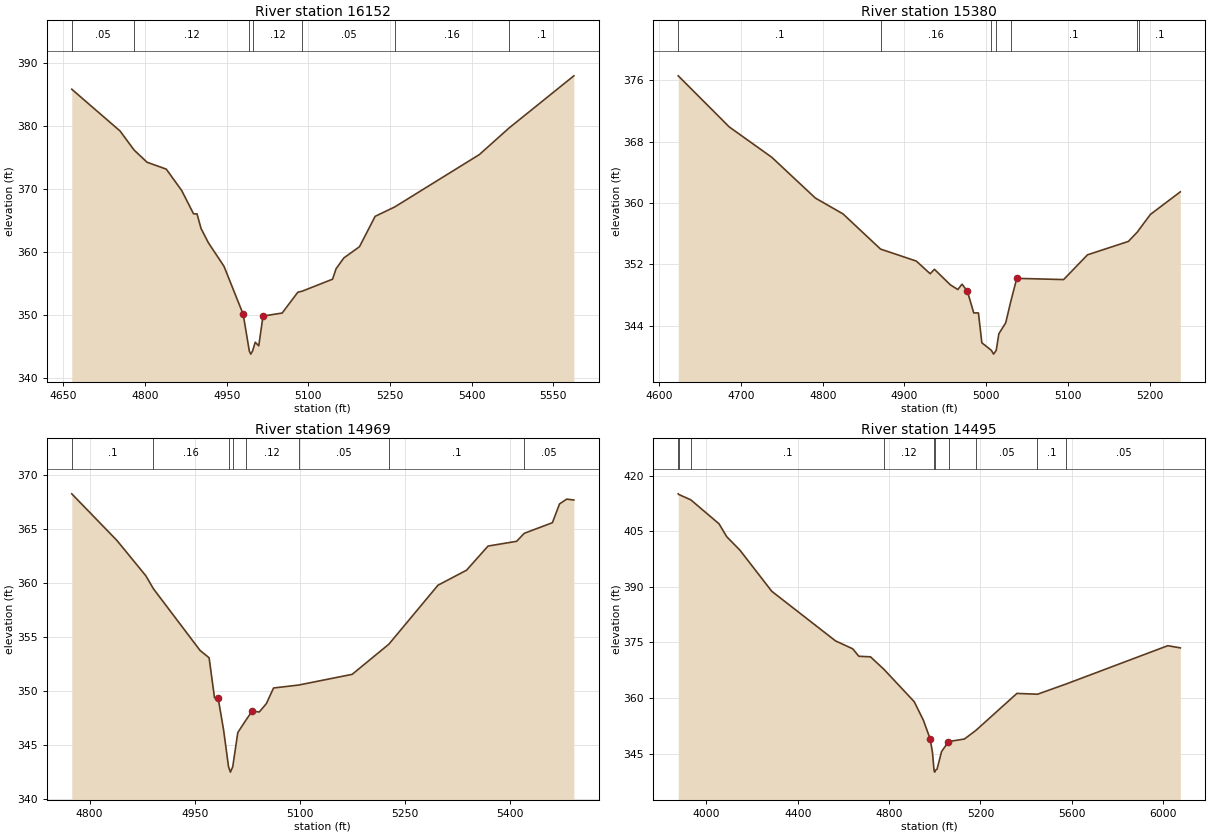
Type RM Length L Ch R = 1 ,16152   ,772,772,772
BEGIN DESCRIPTION:
MILL CREEK 31.0
END DESCRIPTION:
XS GIS Cut Line= 3
       3559966.2     10448061.95      3560116.22     10448211.97
      3560566.22     10448761.97
#Sta/Elev= 30
  4665.3  385.83  4754.1  379.19  4779.9  376.16  4803.6  374.23    4839  373.13
  4867.3  369.74  4889.1  366.03  4895.5  366.02  4902.9   363.7  4916.4  361.43
  4945.1  357.69  4980.4  350.05  4991.6  344.23  4994.3  343.73  4997.6  344.23
  5002.5  345.62    5009  345.05  5016.8  349.78    5052  350.26  5080.7  353.56
  5089.3  353.75  5144.6  355.64  5151.1   357.3  5165.4  359.02  5194.1   360.8
  5222.9  365.63  5259.1  367.13  5414.5  375.45  5469.2  379.68  5588.1  387.96
#Mann= 7 ,-1 , 0
  4665.3     .05       0  4779.9     .12       0  4991.6     .07       0
  4997.6     .12       0  5089.3     .05       0  5259.1     .16       0
  5469.2      .1       0
Bank Sta=4980.4,5016.8
XS Rating Curve= 0 ,0
Exp/Cntr=0.3,0.1

Type RM Length L Ch R = 1 ,15380   ,411,411,411
BEGIN DESCRIPTION:
MILL CREEK 28.0
END DESCRIPTION:
XS GIS Cut Line= 3
      3559642.11     10448491.65      3559742.11     10448841.64
      3559892.11     10449041.64
#Sta/Elev= 30
  4623.3   376.6  4685.7  369.93  4737.7  365.97    4791  360.65  4824.8  358.58
  4870.7  353.99  4914.5  352.42  4931.4  350.77  4936.6  351.35  4956.1  349.32
  4965.2  348.71  4970.4  349.41  4976.9  348.48  4984.7  345.66  4990.4  345.66
  4994.6  341.76  5006.2  340.78  5008.9  340.28  5012.2  340.78  5015.4  342.94
  5023.8  344.37  5029.9  347.12  5037.3  350.17  5094.6  350.01  5123.8  353.24
  5173.8  354.99  5184.9  356.23  5186.4  356.46  5200.8  358.52  5237.3  361.46
#Mann= 7 ,-1 , 0
  4623.3      .1       0  4870.7     .16       0  5006.2     .07       0
  5012.2     .16       0  5029.9      .1       0  5184.9     .05       0
  5186.4      .1       0
Bank Sta=4976.9,5037.3
XS Rating Curve= 0 ,0
Exp/Cntr=0.3,0.1

Type RM Length L Ch R = 1 ,14969   ,474,474,474
BEGIN DESCRIPTION:
MILL CREEK 27.0
END DESCRIPTION:
XS GIS Cut Line= 3
      3559442.11     10448641.62      3559392.11     10448841.64
       3559292.1     10449341.67
#Sta/Elev= 30
  4774.5  368.25  4838.9  363.94  4880.2  360.67    4891  359.47  4957.5  353.77
  4970.4  353.09  4978.1  349.39  4983.2  349.39  4990.9  346.48  4998.1  343.02
  5000.8  342.52  5004.1  343.02  5011.3  346.18  5022.7  347.31  5031.7  348.16
  5041.9  348.08  5052.1  348.86  5062.3   350.3    5098  350.57  5174.4  351.56
  5226.8  354.35  5296.8   359.8  5337.6  361.19  5368.2  363.42    5409  363.86
  5419.9   364.6    5460  365.58  5470.2  367.32  5480.4  367.76  5490.6  367.68
#Mann= 8 ,-1 , 0
  4774.5      .1       0    4891     .16       0  4998.1     .07       0
  5004.1     .16       0  5022.7     .12       0    5098     .05       0
  5226.8      .1       0  5419.9     .05       0
Bank Sta=4983.2,5031.7
XS Rating Curve= 0 ,0
Exp/Cntr=0.3,0.1

Type RM Length L Ch R = 1 ,14495   ,991,991,991
BEGIN DESCRIPTION:
MILL CREEK 26.0
END DESCRIPTION:
XS GIS Cut Line= 4
      3559108.86      10447716.4      3558928.31     10448605.26
      3558924.84     10449817.07      3558943.42     10449895.06
#Sta/Elev= 30
  3876.5  415.08  3878.4  414.92  3931.5  413.46  4055.3  406.99  4088.6  403.54
  4147.2  399.85  4286.1   388.8  4565.5  375.41  4640.5  373.29  4667.6  371.27
  4718.6  371.12    4778  367.71  4909.9  359.03  4949.9  354.07  4979.9  348.97
  4989.9  345.39  4996.9  340.52  4999.6  340.02  5002.9  340.52  5009.9  340.78
  5029.9  345.58  5059.9  348.18  5061.6  348.27  5129.9  348.95  5179.9  351.26
  5359.9  361.25    5450  361.03  5576.3  363.81  6020.6  374.12  6075.5  373.53
#Mann= 10 ,-1 , 0
  3876.5      .1       0  3878.4     .16       0  3931.5      .1       0
    4778     .12       0  4996.9     .07       0  5002.9     .12       0
  5061.6      .1       0  5179.9     .05       0    5450      .1       0
  5576.3     .05       0
Bank Sta=4979.9,5059.9
XS Rating Curve= 0 ,0
Exp/Cntr=0.3,0.1