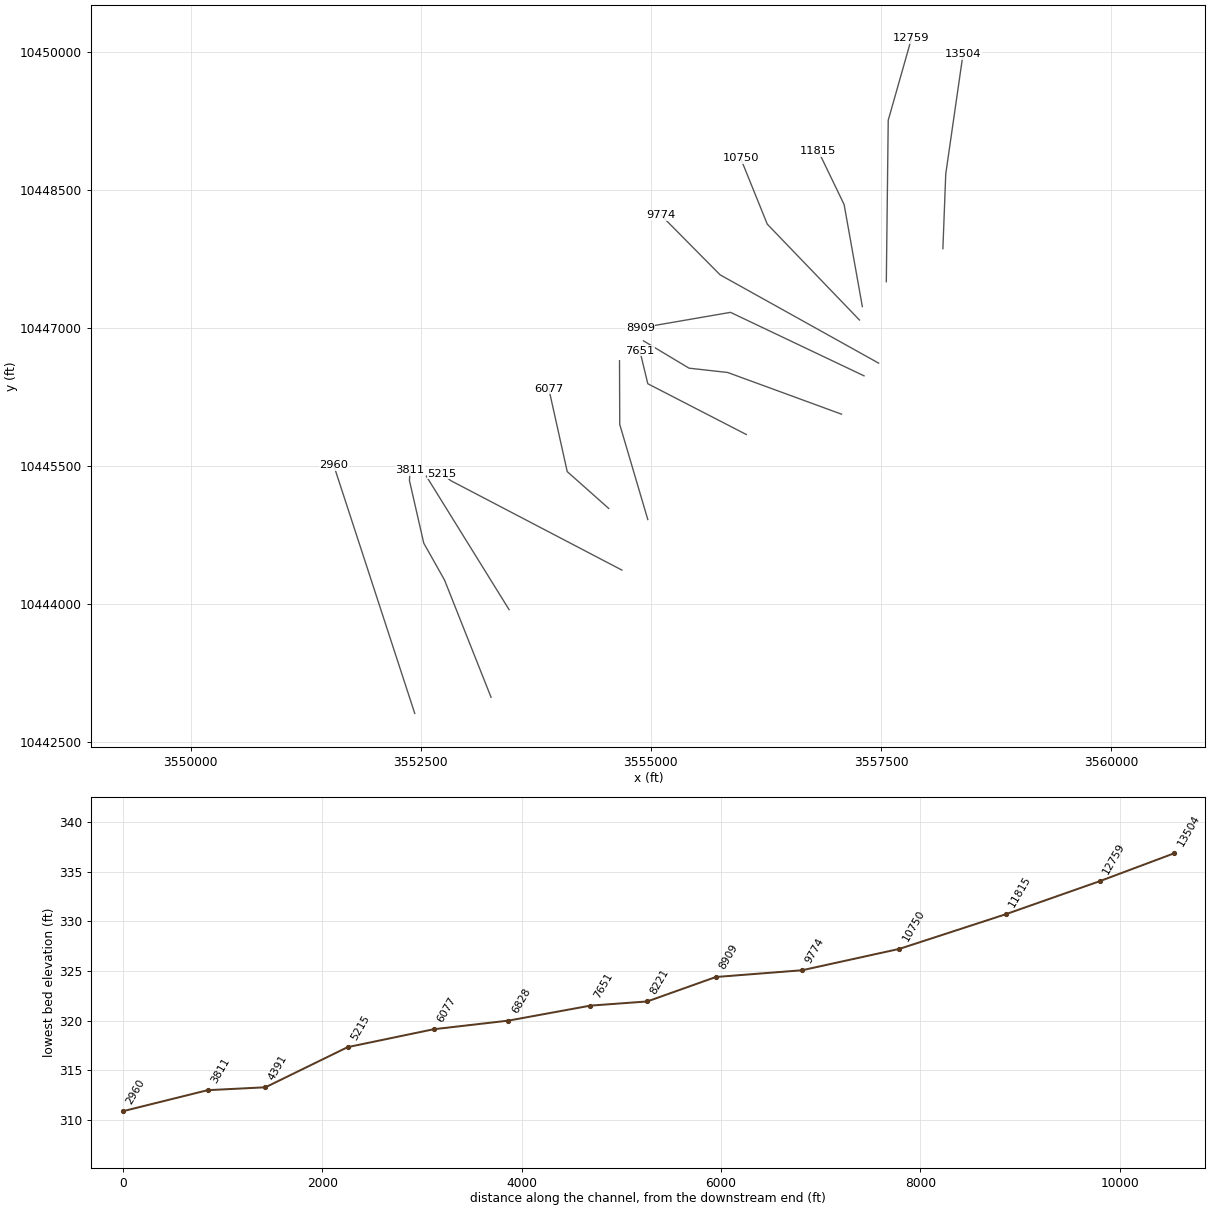
HEC-RAS study MILL CREEK.prj: MILL CREEK Base Level Engineering

--- MILL CREEK.g01 (geometry) --- (continued)

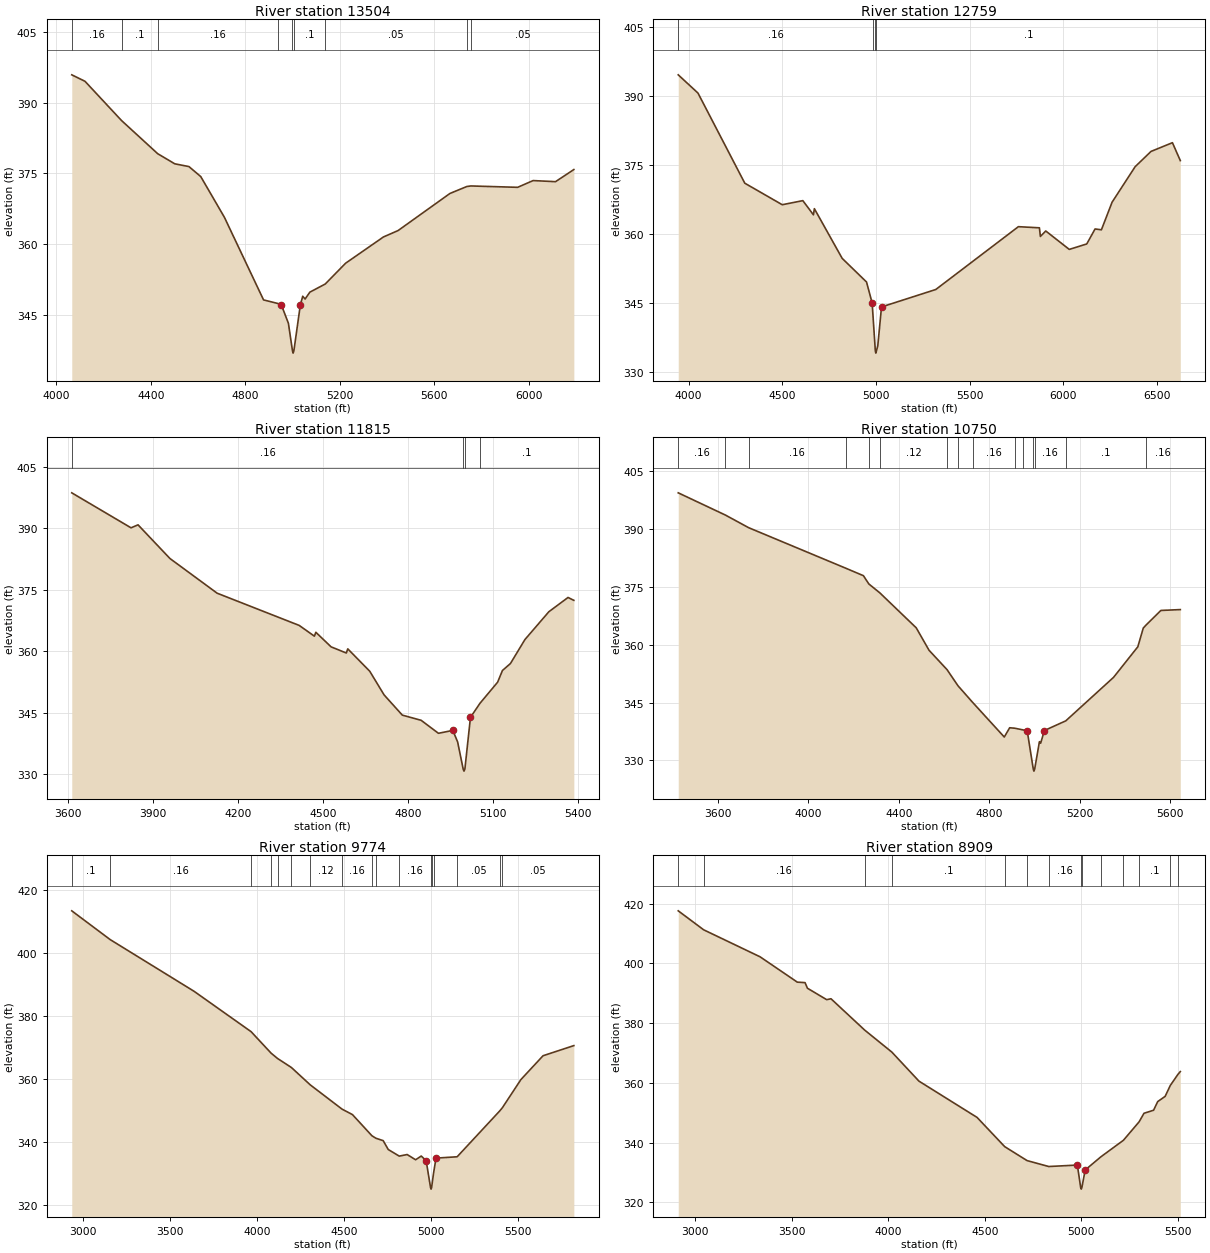
Type RM Length L Ch R = 1 ,13504   ,745,745,745
BEGIN DESCRIPTION:
MILL CREEK 24.0
END DESCRIPTION:
XS GIS Cut Line= 3
       3558173.1     10447865.64      3558204.29      10448678.2
      3558391.59     10449978.43
#Sta/Elev= 30
  4064.7  395.89  4120.7  394.52  4275.5  386.19  4428.6  379.16    4501  377.01
  4561.1  376.42  4611.1   374.3  4711.2  365.67  4877.1  348.13  4938.8  347.36
  4952.1  347.12  4982.4  343.17  4999.6  337.34  5002.3  336.84  5005.6  337.34
  5032.8  347.02    5043  348.91  5053.1  348.32  5073.3  349.78  5138.3   351.5
  5224.8  355.92    5385  361.49  5447.1  362.85  5666.7  370.72  5738.1  372.19
  5755.3  372.31  5953.5  372.02  6018.9  373.45  6113.9  373.22  6191.5  375.79
#Mann= 9 ,-1 , 0
  4064.7     .16       0  4275.5      .1       0  4428.6     .16       0
  4938.8      .1       0  4999.6     .07       0  5005.6      .1       0
  5138.3     .05       0  5738.1      .1       0  5755.3     .05       0
Bank Sta=4952.1,5032.8
XS Rating Curve= 0 ,0
Exp/Cntr=0.3,0.1

Type RM Length L Ch R = 1 ,12759   ,944,944,944
BEGIN DESCRIPTION:
MILL CREEK 22.0
END DESCRIPTION:
XS GIS Cut Line= 3
      3557558.52     10447506.26      3557579.35     10449261.51
      3557832.11     10450152.06
#Sta/Elev= 30
  3944.3  394.65  4049.7  390.68  4299.7  371.05  4499.7  366.36  4609.7  367.25
  4666.3  364.16  4671.3   365.5  4819.7  354.68  4949.8  349.53  4979.8  344.96
  4985.1  341.71  4996.8  334.54  4999.5  334.04  5002.8  334.54  5009.8   335.6
  5029.8   344.1  5319.8   347.9  5760.8  361.58    5873  361.33  5878.2  359.45
  5906.9  360.64  6032.5  356.63  6125.9  357.82  6170.2  361.08  6204.1   360.9
  6261.1  366.91    6384  374.63    6469  377.97  6583.4  379.87  6625.4  375.97
#Mann= 4 ,-1 , 0
  3944.3     .16       0  4985.1      .1       0  4996.8     .07       0
  5002.8      .1       0
Bank Sta=4979.8,5029.8
XS Rating Curve= 0 ,0
Exp/Cntr=0.3,0.1

Type RM Length L Ch R = 1 ,11815   ,1065,1065,1065
BEGIN DESCRIPTION:
MILL CREEK 21.0
END DESCRIPTION:
XS GIS Cut Line= 3
       3557298.1     10447235.48      3557100.18     10448344.85
      3556819.32     10448927.39
#Sta/Elev= 30
  3613.1  398.69  3822.5  390.14  3847.2  390.87    3960  382.64  4126.7  374.17
  4416.3  366.31  4470.2  363.68  4475.3  364.63  4529.1  361.07    4583  359.56
  4588.1  360.58  4665.6  355.12  4716.4  349.33  4780.8  344.39  4847.4  343.12
  4908.4  339.95  4959.2  340.66  4976.2  337.84  4995.8  331.21  4998.6  330.71
  5001.8  331.21  5021.5  343.84    5055  347.27  5117.5  352.44  5134.5  355.29
  5162.7  356.99  5213.8  362.84  5298.4  369.64  5366.2  373.13  5386.7  372.43
#Mann= 4 ,-1 , 0
  3613.1     .16       0  4995.8     .07       0  5001.8     .16       0
    5055      .1       0
Bank Sta=4959.2,5021.5
XS Rating Curve= 0 ,0
Exp/Cntr=0.3,0.1

Type RM Length L Ch R = 1 ,10750   ,976,976,976
BEGIN DESCRIPTION:
MILL CREEK 19.0
END DESCRIPTION:
XS GIS Cut Line= 3
      3557266.85     10447089.64      3556265.23     10448131.96
      3555975.87     10448848.36
#Sta/Elev= 30
  3425.5   399.3  3634.3  393.53  3736.3  390.28  4167.2  379.74  4243.7  377.84
  4267.6   375.7  4315.9  373.41    4477  364.34  4533.6  358.53  4613.4  353.49
  4661.1  349.36  4725.6  345.07    4866  336.06  4889.8  338.46  4912.6  338.34
  4949.4   337.9  4967.6  337.56  4994.2  327.73  4996.9  327.23  5000.2  327.73
  5021.3  334.86  5026.7  334.46  5043.3  337.75  5137.7  340.25  5348.7  351.51
    5456  359.43  5480.1  364.28  5492.7  365.08  5557.9  368.84  5643.7  369.06
#Mann= 15 ,-1 , 0
  3425.5     .16       0  3634.3     .12       0  3736.3     .16       0
  4167.2     .12       0  4267.6     .16       0  4315.9     .12       0
  4613.4      .1       0  4661.1     .12       0  4725.6     .16       0
  4912.6     .12       0  4949.4     .16       0  4994.2     .07       0
  5000.2     .16       0  5137.7      .1       0  5492.7     .16       0
Bank Sta=4967.6,5043.3
XS Rating Curve= 0 ,0
Exp/Cntr=0.3,0.1

Type RM Length L Ch R = 1 ,9774    ,865,865,865
BEGIN DESCRIPTION:
MILL CREEK 17.0
END DESCRIPTION:
XS GIS Cut Line= 3
      3557475.21     10446620.87      3555752.88     10447580.87
      3555110.58     10448230.28
#Sta/Elev= 30
    2937  413.25  3157.6  404.14  3638.9  387.79  3967.5  374.97  4083.2  368.12
  4119.6  366.47  4198.9  363.62  4307.8   358.1    4490  350.43    4550  348.69
  4661.7     342  4684.4  341.21  4726.5  340.44  4755.7  337.63  4818.7  335.54
  4864.3  336.04  4912.9  334.38  4945.3  335.56  4973.5  334.08  4998.8  325.58
  5001.6  325.08  5004.8  325.58  5016.2  330.19  5030.1   334.9  5151.6  335.33
  5395.6  349.81  5411.9   350.9    5518  359.79  5645.3  367.34  5822.2  370.55
#Mann= 17 ,-1 , 0
    2937      .1       0  3157.6     .16       0  3967.5     .12       0
  4083.2     .16       0  4119.6     .12       0  4198.9      .1       0
  4307.8     .12       0    4490     .16       0  4661.7      .1       0
  4684.4     .12       0  4818.7     .16       0  4998.8     .07       0
  5004.8     .16       0  5016.2      .1       0  5151.6     .05       0
  5395.6     .08       0  5411.9     .05       0
Bank Sta=4973.5,5030.1
XS Rating Curve= 0 ,0
Exp/Cntr=0.3,0.1

Type RM Length L Ch R = 1 ,8909    ,688,688,688
BEGIN DESCRIPTION:
MILL CREEK 16.0
END DESCRIPTION:
XS GIS Cut Line= 3
      3557316.33     10446482.87      3555865.81     10447172.97
      3554886.84     10447003.74
#Sta/Elev= 30
  2912.5  417.59    3044  411.24  3336.4  402.19  3529.1  393.71    3569  393.55
  3581.6  391.67  3681.3  387.84  3703.4  388.15  3878.2  377.64  4018.7  370.28
    4159  360.56  4459.8  348.42  4602.9  338.63  4718.9  333.95  4831.1  331.97
  4979.2  332.46  4996.5   324.9  4999.3   324.4  5002.5   324.9  5019.8  330.81
    5101  335.22  5217.9  340.77    5299  346.94  5324.3   349.8  5373.9  350.82
  5395.3  353.71  5433.7  355.46  5460.4  359.11  5499.5  362.78  5512.3  363.76
#Mann= 14 ,-1 , 0
  2912.5     .05       0    3044     .16       0  3878.2     .12       0
  4018.7      .1       0  4602.9     .16       0  4718.9     .12       0
  4831.1     .16       0  4996.5     .07       0  5002.5     .16       0
    5101      .1       0  5217.9     .16       0    5299      .1       0
  5460.4     .16       0  5499.5      .1       0
Bank Sta=4979.2,5019.8
XS Rating Curve= 0 ,0
Exp/Cntr=0.3,0.1

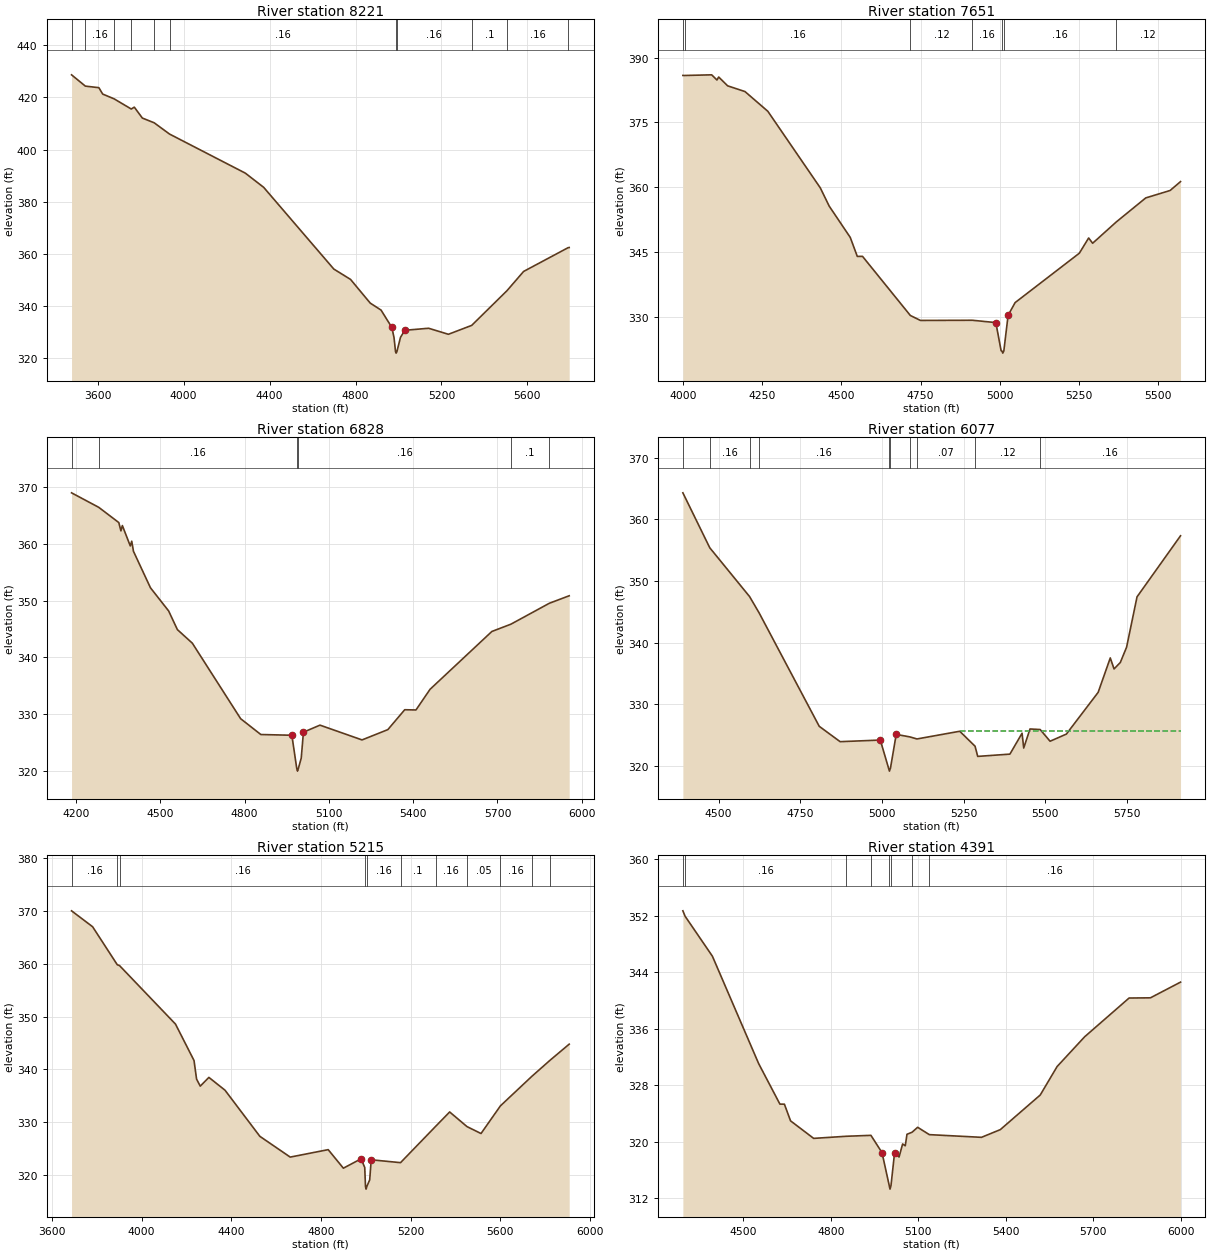
Type RM Length L Ch R = 1 ,8221    ,570,570,570
BEGIN DESCRIPTION:
MILL CREEK 15.0
END DESCRIPTION:
XS GIS Cut Line= 4
      3557071.51     10446066.21      3555834.56     10446519.33
      3555415.29      10446566.2      3554920.53     10446863.06
#Sta/Elev= 30
  3478.2  428.69  3542.4  424.36  3605.4  423.76  3623.1  421.31  3676.7  419.46
    3756  415.58  3770.3  416.29  3807.7  412.11  3862.8  410.29  3934.3  405.97
    4287  390.98  4372.2  385.55  4698.7   354.2  4776.8  350.21  4868.4  341.13
  4918.7  338.45  4969.1  331.78  4979.1  327.88  4986.2  322.44  4988.9  321.94
  4992.2  322.44  5009.3  328.01  5029.4   330.7  5140.1  331.48  5232.3  329.17
  5340.6  332.58  5504.7  345.88  5582.2  353.27  5789.2  362.38  5794.4  362.45
#Mann= 11 ,-1 , 0
  3478.2     .05       0  3542.4     .16       0  3676.7      .1       0
    3756     .16       0  3862.8      .1       0  3934.3     .16       0
  4986.2     .07       0  4992.2     .16       0  5340.6      .1       0
  5504.7     .16       0  5789.2     .12       0
Bank Sta=4969.1,5029.4
XS Rating Curve= 0 ,0
Exp/Cntr=0.3,0.1

Type RM Length L Ch R = 1 ,7651    ,823,823,823
BEGIN DESCRIPTION:
MILL CREEK 13.0
END DESCRIPTION:
XS GIS Cut Line= 3
      3556037.73     10445844.83      3554967.37     10446396.93
      3554881.44     10446753.67
#Sta/Elev= 30
  3999.3  385.91  4005.3   385.9  4090.3  386.05  4106.8  384.85  4112.4  385.54
  4140.6   383.5  4195.4  382.17  4267.5   377.6  4433.2  359.84  4461.3  355.61
  4527.8  348.35    4550  343.95  4566.5  343.96  4717.5  330.25  4749.4   329.1
  4913.5  329.14  4987.5   328.6  5004.1  322.08  5006.7  322.02  5009.4  321.52
  5012.7  322.02  5026.2   330.3  5048.4  333.24  5251.1  344.69  5280.5  348.22
  5293.1     347  5367.5  351.92  5460.8  357.51  5537.7  359.23  5570.6  361.29
#Mann= 7 ,-1 , 0
  3999.3      .1       0  4005.3     .16       0  4717.5     .12       0
  4913.5     .16       0  5006.7     .07       0  5012.7     .16       0
  5367.5     .12       0
Bank Sta=4987.5,5026.2
XS Rating Curve= 0 ,0
Exp/Cntr=0.3,0.1

Type RM Length L Ch R = 1 ,6828    ,751,751,751
BEGIN DESCRIPTION:
MILL CREEK 11.0
END DESCRIPTION:
XS GIS Cut Line= 3
      3554967.38     10444920.36      3554662.68     10445954.22
      3554660.08     10446646.79
#Sta/Elev= 30
  4184.7  368.97  4281.4  366.42  4352.8  363.74  4360.3  362.28  4365.5  363.21
  4393.6  359.63  4398.8  360.46    4405  358.68  4465.5  352.26  4530.1  348.19
  4561.3   344.9  4614.4  342.52  4786.3  329.23  4858.1  326.45  4968.5  326.32
  4985.8  320.51  4988.5  320.01  4991.8  320.51  5001.8   322.3  5009.6  326.86
  5068.5   328.1  5218.1   325.5  5309.9  327.31  5369.9  330.81    5410  330.77
    5460   334.4    5680  344.58  5747.7  345.86  5884.4  349.54  5955.1  350.86
#Mann= 6 ,-1 , 0
  4184.7      .1       0  4281.4     .16       0  4985.8     .07       0
  4991.8     .16       0  5747.7      .1       0  5884.4     .16       0
Bank Sta=4968.5,5009.6
XS Rating Curve= 0 ,0
Exp/Cntr=0.3,0.1

Type RM Length L Ch R = 1 ,6077    ,862,862,862
BEGIN DESCRIPTION:
MILL CREEK 9.0
END DESCRIPTION:
XS GIS Cut Line= 3
      3554542.07     10445041.67      3554092.11     10445441.64
       3553892.1     10446341.66
#Sta/Elev= 30
  4390.6   364.3  4472.9  355.39  4594.8  347.47  4624.2  344.81  4808.2  326.41
  4872.2  323.92  4995.2  324.18  5020.4  319.64  5023.1  319.14  5026.4  319.64
  5043.9   325.1  5086.1  324.69  5107.5  324.36  5238.5  325.61  5285.4  323.18
  5293.5  321.53  5392.1   321.9  5429.3  325.29  5434.4  322.89  5453.6  325.98
  5484.8  325.89  5515.1  323.99    5565  325.15  5662.3  331.92  5699.5  337.51
    5711  335.72  5730.2  336.77  5749.4  339.25  5781.4  347.42  5914.6  357.33
#Mann= 10 ,-1 , 0
  4390.6      .1       0  4472.9     .16       0  4594.8      .1       0
  4624.2     .16       0  5020.4     .07       0  5026.4     .16       0
  5086.1     .12       0  5107.5     .07       0  5285.4     .12       0
  5484.8     .16       0
#XS Ineff= 2 , 0
                         5238.96          325.71
Permanent Ineff=
       F       F
Bank Sta=4995.2,5043.9
XS Rating Curve= 0 ,0
Exp/Cntr=0.3,0.1

Type RM Length L Ch R = 1 ,5215    ,824,824,824
BEGIN DESCRIPTION:
MILL CREEK 7.0
END DESCRIPTION:
XS GIS Cut Line= 3
      3554686.13     10444370.89      3552829.35     10445342.24
       3552731.1     10445417.23
#Sta/Elev= 30
  3687.9     370  3781.8  366.99  3891.8   359.8  3901.8  359.64  4151.4  348.57
  4234.1  341.67  4245.4  338.16  4261.8  336.83  4300.3  338.48  4372.2  336.06
  4527.6  327.33    4663   323.4  4832.3  324.81    4900   321.3    4979  323.08
  4995.3  321.43  4998.6  317.84  5001.3  317.34  5004.6  317.84  5017.4  319.09
  5024.2  322.89  5154.9  322.35  5310.8  329.19    5374  331.94  5451.3  329.17
  5513.8  327.86  5600.2  333.09  5739.9  338.66    5822  341.74    5907  344.77
#Mann= 11 ,-1 , 0
  3687.9     .16       0  3891.8     .12       0  3901.8     .16       0
  4998.6     .07       0  5004.6     .16       0  5154.9      .1       0
  5310.8     .16       0  5451.3     .05       0  5600.2     .16       0
  5739.9      .1       0    5822     .16       0
Bank Sta=4979,5024.2
XS Rating Curve= 0 ,0
Exp/Cntr=0.3,0.1

Type RM Length L Ch R = 1 ,4391    ,580,580,580
BEGIN DESCRIPTION:
MILL CREEK 6.0
END DESCRIPTION:
XS GIS Cut Line= 2
      3553460.64     10443940.77      3552561.35     10445392.14
#Sta/Elev= 30
  4292.6  352.68  4300.3  351.91  4393.9  346.26  4552.4  331.08  4625.5  325.33
  4640.9  325.32  4662.1  322.96  4741.3  320.48  4853.5  320.78  4937.8  320.91
  4975.9  318.46  5000.6   313.8  5003.3   313.3  5006.6   313.8  5018.9  318.43
  5034.3  317.84  5046.5  319.69  5055.6  319.43  5061.5  321.06  5078.9  321.35
  5098.1  322.05  5138.2  321.01  5317.1  320.63  5381.7  321.72  5518.7  326.62
  5576.6  330.65  5671.1  334.86  5823.5  340.34  5896.8  340.37    6000  342.59
#Mann= 8 ,-1 , 0
  4292.6     .05       0  4300.3     .16       0  4853.5     .05       0
  4937.8     .16       0  5000.6     .07       0  5006.6     .16       0
  5078.9     .05       0  5138.2     .16       0
Bank Sta=4975.9,5018.9
XS Rating Curve= 0 ,0
Exp/Cntr=0.3,0.1

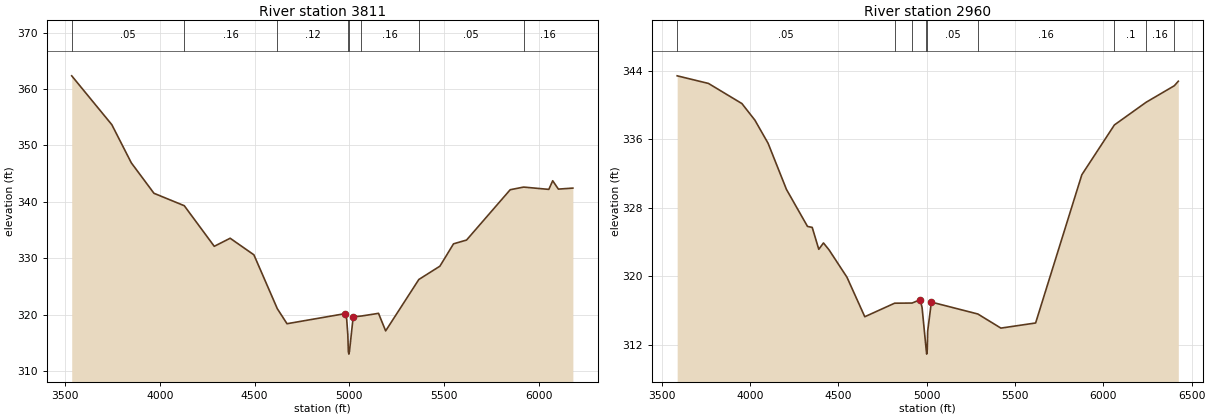
Type RM Length L Ch R = 1 ,3811    ,851,851,851
BEGIN DESCRIPTION:
MILL CREEK 5.0
END DESCRIPTION:
XS GIS Cut Line= 5
      3553264.46     10442988.51      3552759.57     10444261.85
      3552533.47     10444663.92      3552377.86     10445345.07
      3552385.34     10445457.86
#Sta/Elev= 30
  3536.1  362.34  3747.6  353.68  3850.3  346.92  3969.8  341.52  4129.6  339.32
  4287.8  332.12  4371.6  333.55  4496.9  330.61  4620.2  321.07  4671.4   318.4
  4976.2  320.18    4986  319.25  4992.1  316.51  4994.8  313.51  4997.6  313.01
  5000.8  313.51  5020.4  319.62  5062.7  319.76    5154  320.24  5191.6  317.13
  5366.6  326.24  5477.7   328.6  5549.5  332.56  5618.2  333.23  5848.4  342.15
  5919.3  342.62  6052.1  342.21  6072.5  343.74  6102.5  342.26  6178.9  342.44
#Mann= 8 ,-1 , 0
  3536.1     .05       0  4129.6     .16       0  4620.2     .12       0
  4994.8     .07       0  5000.8     .12       0  5062.7     .16       0
  5366.6     .05       0  5919.3     .16       0
Bank Sta=4976.2,5020.4
XS Rating Curve= 0 ,0
Exp/Cntr=0.3,0.1

Type RM Length L Ch R = 1 ,2960    ,0,0,0
BEGIN DESCRIPTION:
MILL CREEK 1.0
END DESCRIPTION:
XS GIS Cut Line= 2
      3552435.47     10442813.18      3551555.25     10445511.12
#Sta/Elev= 30
  3586.7  343.41  3763.9  342.52  3953.2  340.17  4026.9  338.23  4101.5  335.53
  4205.7  330.13  4324.8  325.81  4351.4   325.7  4388.6  323.14  4415.2  323.88
  4447.1  323.06  4548.1  319.88  4649.1  315.26    4818  316.84  4917.2  316.86
  4962.8  317.25  4973.6  316.33  4996.9  311.39  4999.7  310.89  5002.9  311.39
  5005.2  313.57  5026.2  316.97  5289.2  315.58  5419.9  313.93  5616.5  314.53
  5878.2  331.85  6062.6  337.67  6242.2  340.32  6401.9  342.25  6424.6  342.78
#Mann= 9 ,-1 , 0
  3586.7     .05       0    4818     .16       0  4917.2     .05       0
  4996.9    .035       0  5002.9     .05       0  5289.2     .16       0
  6062.6      .1       0  6242.2     .16       0  6401.9     .12       0
Bank Sta=4962.8,5026.2
XS Rating Curve= 0 ,0
Exp/Cntr=0.3,0.1

Chan Stop Cuts=-1
Use User Specified Reach Order=0
Composite Channel Slope=5