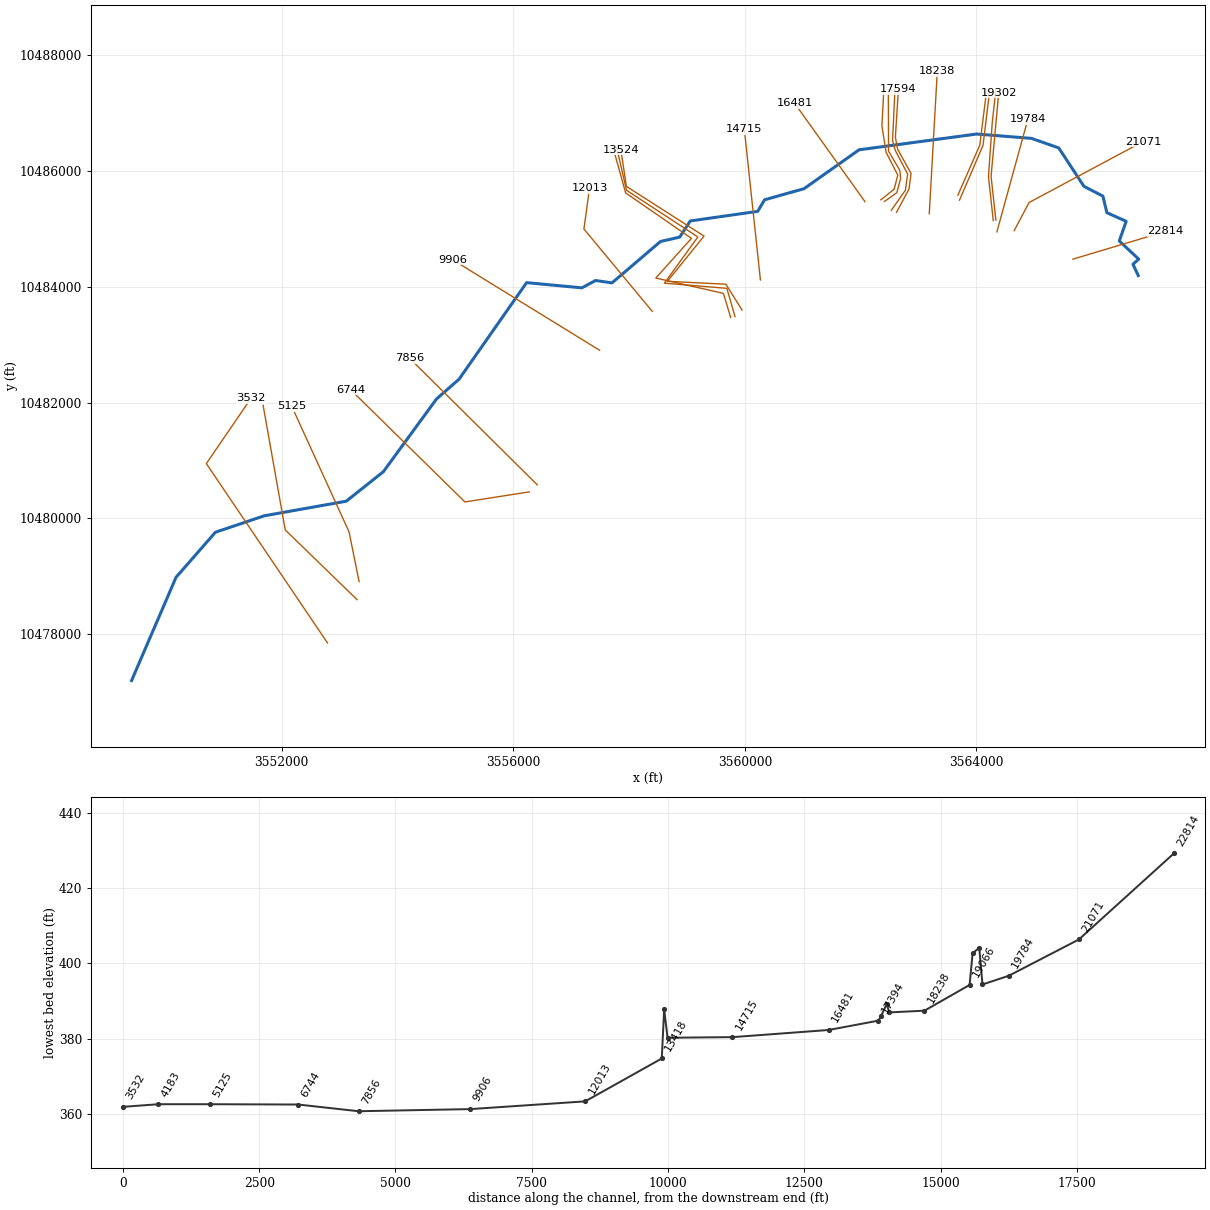
--- MINE CREEK.prj (project) ---

Proj Title=MINE CREEK Base Level Engineering
Current Plan=p01
Default Exp/Contr=0.3,0.1
English Units
Geom File=g01
Flow File=f01
Plan File=p01
BEGIN DESCRIPTION:
MINE CREEK
END DESCRIPTION:

--- MINE CREEK.p01 (plan) ---

Plan Title=Multiple Run
Short Identifier=Multiple
Geom File=g01
Flow File=f01
Subcritical Flow
K Sum by GR= 0
Std Step Tol= 0.01
Critical Tol= 0.01
Num of Std Step Trials= 20
Max Error Tol= 0.3
Flow Tol Ratio= 0.001
Split Flow NTrial= 30
Split Flow Tol= 0.02
Split Flow Ratio= 0.02
Log Output Level= 0
Friction Slope Method= 1
Unsteady Friction Slope Method= 2
Unsteady Bridges Friction Slope Method= 1
Parabolic Critical Depth
Global Vel Dist=  1 , 1 , 1
Global Log Level= 0
CheckData=True
Encroach Param= -1, 0, 0, 0
BEGIN DESCRIPTION:
Multiple Run
END DESCRIPTION:

--- MINE CREEK.f01 (steady flow) ---

Flow Title=Multiple
Number of Profiles=7
Profile Names=10-year,25-year,50-year,1pct_min,100-year,1pct_plu,500-year
River Rch & RM= MINE CREEK,Reach-1,22814
    1845    2662    3371    3113    4210    5694    6553
River Rch & RM= MINE CREEK,Reach-1,19784
    1933    2786    3524    3248    4393    5941    6813
River Rch & RM= MINE CREEK,Reach-1,19066
    2213    3211    4080    3777    5108    6909    7992
River Rch & RM= MINE CREEK,Reach-1,17439
    2675    3899    4966    4605    6227    8422    9773
River Rch & RM= MINE CREEK,Reach-1,12013
    2902    4246    5424    5041    6817    9220   10753
River Rch & RM= MINE CREEK,Reach-1,9906
    2944    4288    5460    5055    6837    9246   10703
River Rch & RM= MINE CREEK,Reach-1,5125
    3566    5231    6692    6222    8414   11379   13280
Boundary for River Rch & Prof#=MINE CREEK,Reach-1,1
Up Type=0
Dn Type=3
Dn Slope=0.005
Boundary for River Rch & Prof#=MINE CREEK,Reach-1,2
Up Type=0
Dn Type=3
Dn Slope=0.005
Boundary for River Rch & Prof#=MINE CREEK,Reach-1,3
Up Type=0
Dn Type=3
Dn Slope=0.005
Boundary for River Rch & Prof#=MINE CREEK,Reach-1,4
Up Type=0
Dn Type=3
Dn Slope=0.005
Boundary for River Rch & Prof#=MINE CREEK,Reach-1,5
Up Type=0
Dn Type=3
Dn Slope=0.005
Boundary for River Rch & Prof#=MINE CREEK,Reach-1,6
Up Type=0
Dn Type=3
Dn Slope=0.005
Boundary for River Rch & Prof#=MINE CREEK,Reach-1,7
Up Type=0
Dn Type=3
Dn Slope=0.005

--- MINE CREEK.g01 (geometry) ---

Geom Title=Existing Conditions

River Reach=MINE CREEK,Reach-1
Reach XY= 30
      3566794.70     10484195.14      3566702.26     10484391.89
      3566802.92     10484478.72      3566466.90     10484792.82
      3566585.91     10485132.83      3566252.84     10485282.15
      3566183.48     10485568.87      3565857.13     10485736.59
      3565420.81     10486401.54      3564949.89     10486566.47
      3564002.33     10486641.64      3561972.05     10486368.99
      3561021.53     10485697.11      3560339.55     10485504.84
      3560221.50     10485305.19      3559057.00     10485139.21
      3558873.67     10484860.10      3558542.94     10484784.58
      3557705.18     10484069.32      3557418.16     10484109.43
      3557184.82     10483982.87      3556229.06     10484072.79
      3555063.02     10482405.00      3554672.40     10482061.25
      3553755.73     10480806.05      3553115.11     10480295.63
      3551698.12     10480042.94      3550854.81     10479759.28
      3550173.71     10478979.56      3549405.92     10477195.07

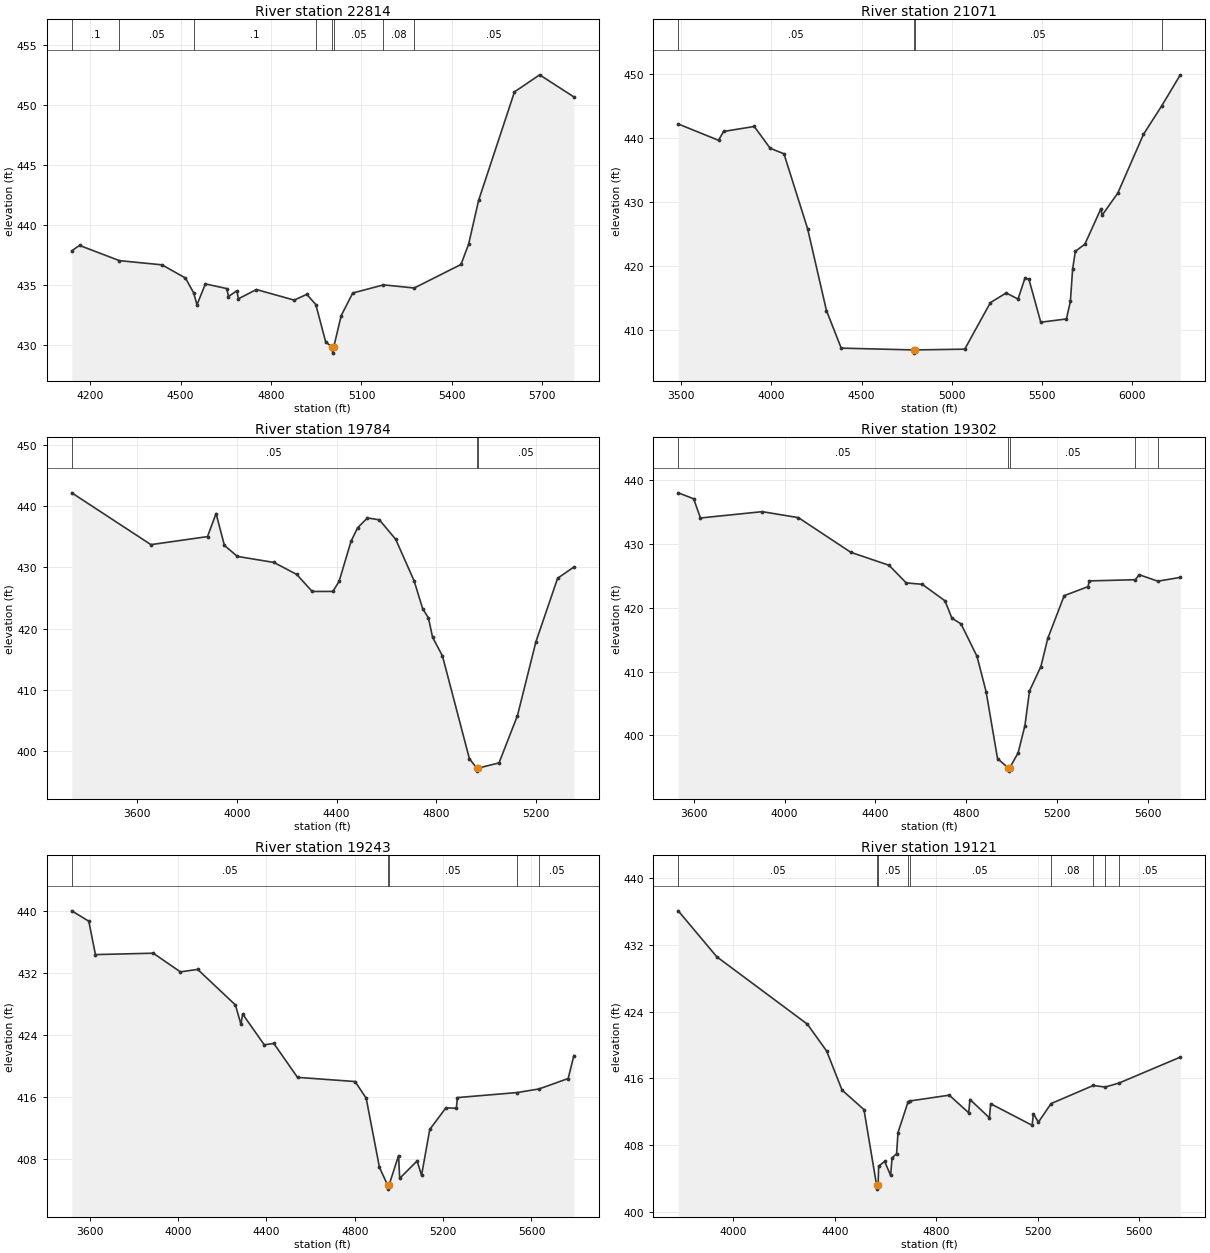
Type RM Length L Ch R = 1,22814,1743,1743,1743
BEGIN DESCRIPTION:
MINE CREEK 3.1
END DESCRIPTION:
XS GIS Cut Line= 2
      3565665.20     10484478.45      3567260.84     10484957.14
#Sta/Elev= 30
  4138.7  437.85  4164.4  438.30  4296.8  437.03  4438.2  436.68  4515.9  435.58
  4543.0  434.35  4554.2  433.35  4582.0  435.09  4653.3  434.70  4658.6  434.04
  4686.4  434.52  4691.6  433.85  4751.4  434.62  4876.7  433.74  4918.5  434.22
  4948.4  433.37  4981.1  430.27  5001.8  429.82  5004.6  429.32  5007.8  429.82
  5032.7  432.45  5071.0  434.33  5173.0  435.01  5275.0  434.75  5430.1  436.71
  5455.5  438.41  5488.6  442.05  5607.6  451.10  5691.1  452.52  5804.6  450.68
#Mann=8,-1,0
  4138.7     0.1       0  4296.8    0.05       0  4543.0     0.1       0
  4948.4    0.05       0  5001.8    0.03       0  5007.8    0.05       0
  5173.0    0.08       0  5275.0    0.05       0
Bank Sta=5001.8,5007.8
Exp/Cntr=0.3,0.1

Type RM Length L Ch R = 1,21071,1287,1287,1287
BEGIN DESCRIPTION:
MINE CREEK 3.2
END DESCRIPTION:
XS GIS Cut Line= 3
      3564651.29     10484971.46      3564908.26     10485457.62
      3566878.79     10486512.27
#Sta/Elev= 30
  3482.8  442.20  3706.4  439.65  3734.1  441.03  3904.5  441.81  3992.5  438.41
  4069.2  437.54  4200.8  425.79  4304.9  413.05  4386.9  407.17  4789.4  406.89
  4792.2  406.39  4795.4  406.89  5071.9  407.01  5214.2  414.28  5301.9  415.79
  5367.7  414.84  5405.9  418.11  5427.9  417.95  5493.7  411.22  5635.9  411.73
  5657.9  414.46  5670.3  419.50  5685.5  422.30  5738.4  423.42  5827.7  428.98
  5833.4  427.92  5921.1  431.41  6063.3  440.58  6163.7  444.99  6267.7  449.88
#Mann=4,-1,0
  3482.8    0.05       0  4789.4   0.033       0  4795.4    0.05       0
  6163.7    0.08       0
Bank Sta=4789.4,4795.4
Exp/Cntr=0.3,0.1

Type RM Length L Ch R = 1,19784,482,482,482
BEGIN DESCRIPTION:
MINE CREEK 3.3
END DESCRIPTION:
XS GIS Cut Line= 2
      3564352.71     10484950.72      3564887.27     10486894.56
#Sta/Elev= 30
  3336.4  442.17  3654.2  433.71  3881.4  435.02  3915.8  438.79  3949.3  433.59
  4001.1  431.79  4148.2  430.80  4239.7  428.84  4301.9  426.06  4384.9  426.07
  4409.9  427.72  4457.5  434.23  4483.9  436.45  4523.5  438.07  4571.5  437.76
  4637.1  434.58  4711.1  427.79  4745.5  423.23  4768.6  421.75  4785.1  418.58
  4824.7  415.55  4933.1  398.74  4962.6  397.22  4965.4  396.72  4968.6  397.22
  5051.9  398.06  5126.0  405.79  5200.0  417.83  5287.2  428.22  5352.4  430.05
#Mann=3,-1,0
  3336.4    0.05       0  4962.6    0.03       0  4968.6    0.05       0
Bank Sta=4962.6,4968.6
Exp/Cntr=0.3,0.1

Type RM Length L Ch R = 1,19302,59,59,59
BEGIN DESCRIPTION:
MINE CREEK 3.5
END DESCRIPTION:
XS GIS Cut Line= 3
      3564335.34     10485154.38      3564252.01     10485911.32
      3564383.95     10487352.28
#Sta/Elev= 30
  3532.5  438.00  3600.2  437.07  3630.3  434.06  3902.0  435.05  4061.3  434.11
  4291.7  428.68  4459.8  426.65  4535.3  423.89  4605.6  423.67  4706.0  421.08
  4736.2  418.37  4776.3  417.47  4846.6  412.39  4886.8  406.84  4937.0  396.37
  4984.2  394.90  4987.0  394.40  4990.2  394.90  5027.4  397.24  5057.5  401.54
  5077.6  406.96  5127.8  410.79  5157.9  415.19  5230.3  421.89  5335.3  423.31
  5340.3  424.20  5542.9  424.39  5560.4  425.17  5641.8  424.16  5741.0  424.75
#Mann=5,-1,0
  3532.5    0.05       0  4984.2    0.03       0  4990.2    0.05       0
  5542.9    0.08       0  5641.8    0.05       0
Bank Sta=4984.2,4990.2
Exp/Cntr=0.3,0.1

Type RM Length L Ch R = 1,19243,122,122,122
BEGIN DESCRIPTION:
MINE CREEK 3.4
END DESCRIPTION:
XS GIS Cut Line= 4
      3564290.20     10485145.12      3564206.87     10485907.85
      3564272.84     10486841.88      3564335.27     10487407.22
#Sta/Elev= 30
  3519.3  440.08  3596.3  438.74  3626.5  434.43  3888.0  434.61  4010.9  432.20
  4089.2  432.52  4260.2  427.92  4284.9  425.43  4292.7  426.75  4390.6  422.78
  4433.8  422.96  4541.0  418.58  4801.6  418.04  4851.8  415.89  4911.9  406.96
  4949.0  404.65  4951.8  404.15  4955.0  404.65  4998.4  408.48  5003.4  405.54
  5082.3  407.79  5102.4  405.93  5139.5  411.85  5212.7  414.65  5259.8  414.59
  5264.9  415.97  5535.7  416.62  5634.8  417.09  5766.0  418.43  5791.7  421.39
#Mann=5,-1,0
  3519.3    0.05       0  4949.0    0.03       0  4955.0    0.05       0
  5535.7    0.08       0  5634.8    0.05       0
Bank Sta=4949,4955
Exp/Cntr=0.3,0.1

Type RM Length L Ch R = 1,19121,55,55,55
BEGIN DESCRIPTION:
MINE CREEK 3.6
END DESCRIPTION:
XS GIS Cut Line= 3
      3563706.86     10485498.12      3564113.12     10486446.04
      3564227.67     10487386.78
#Sta/Elev= 30
  3783.3  436.09  3935.1  430.59  4292.3  422.51  4368.5  419.28  4429.0  414.61
  4515.4  412.27  4565.0  403.24  4567.7  402.74  4571.0  403.24  4573.4  405.50
  4597.0  406.06  4620.5  404.38  4626.0  406.46  4644.1  407.00  4649.5  409.52
  4689.4  413.21  4694.9  413.30  4851.6  414.00  4928.2  411.89  4933.2  413.48
  5009.8  411.29  5014.9  412.97  5178.2  410.39  5183.2  411.76  5203.1  410.77
  5252.8  412.99  5419.0  415.16  5466.4  414.97  5522.2  415.47  5762.3  418.56
#Mann=9,-1,0
  3783.3    0.05       0  4565.0    0.03       0  4571.0    0.05       0
  4689.4     0.1       0  4694.9    0.05       0  5252.8    0.08       0
  5419.0    0.05       0  5466.4    0.08       0  5522.2    0.05       0
Bank Sta=4565,4571
Exp/Cntr=0.3,0.1

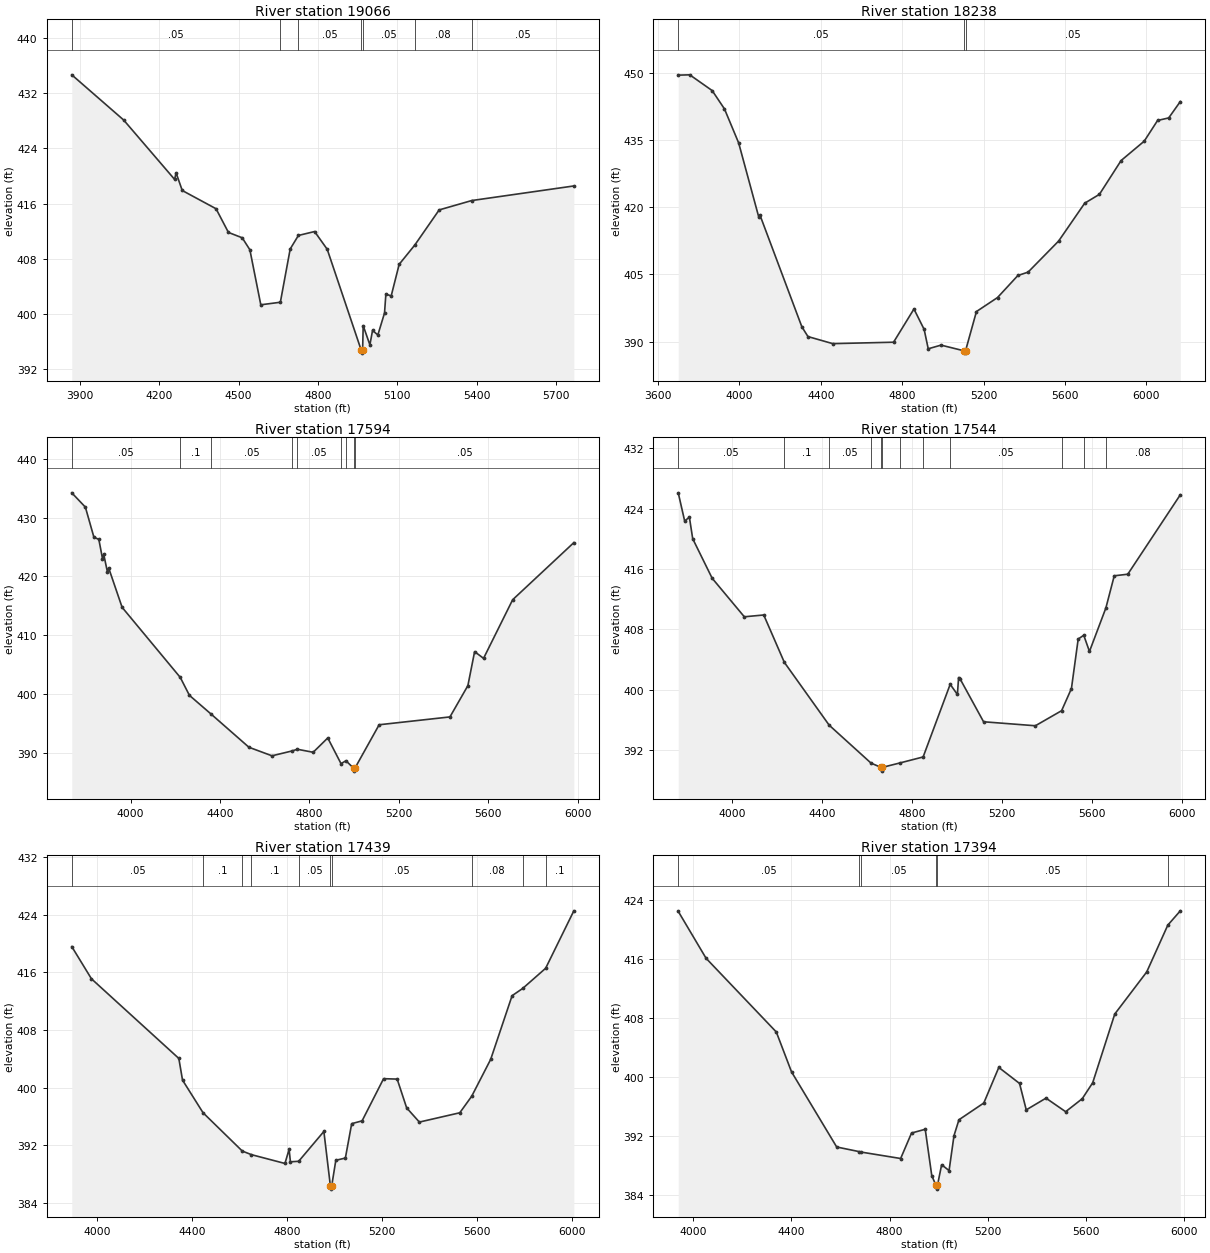
Type RM Length L Ch R = 1,19066,828,828,828
BEGIN DESCRIPTION:
MINE CREEK 3.7
END DESCRIPTION:
XS GIS Cut Line= 3
      3563679.11     10485584.98      3564057.56     10486449.51
      3564175.57     10487397.05
#Sta/Elev= 30
  3869.5  434.70  4065.9  428.13  4258.4  419.51  4263.9  420.47  4287.3  417.90
  4415.1  415.25  4461.9  411.81  4514.1  411.03  4543.0  409.29  4584.3  401.30
  4658.3  401.67  4695.5  409.41  4726.5  411.37  4787.7  411.94  4835.5  409.36
  4963.4  394.78  4966.2  394.28  4969.4  394.78  4971.5  398.27  4996.8  395.48
  5006.9  397.57  5027.0  396.92  5052.2  400.11  5057.3  402.85  5077.4  402.59
  5107.6  407.18  5166.5  409.97  5258.8  415.08  5381.9  416.44  5768.1  418.56
#Mann=7,-1,0
  3869.5    0.05       0  4658.3     0.1       0  4726.5    0.05       0
  4963.4    0.03       0  4969.4    0.05       0  5166.5    0.08       0
  5381.9    0.05       0
Bank Sta=4963.4,4969.4
Exp/Cntr=0.3,0.1

Type RM Length L Ch R = 1,18238,644,644,644
BEGIN DESCRIPTION:
MINE CREEK 3.18
END DESCRIPTION:
XS GIS Cut Line= 2
      3563184.59     10485265.14      3563323.37     10487728.53
#Sta/Elev= 30
  3699.0  449.55  3755.6  449.62  3865.8  446.10  3926.2  442.00  3996.0  434.39
  4095.2  417.75  4100.2  418.32  4306.5  393.30  4336.5  391.12  4458.3  389.54
  4757.2  389.86  4857.3  397.28  4907.4  392.73  4927.5  388.39  4990.4  389.21
  5104.7  387.92  5107.5  387.42  5110.7  387.92  5164.4  396.71  5268.0  399.84
  5368.1  404.77  5418.2  405.52  5568.5  412.48  5696.5  420.93  5768.8  422.91
  5875.5  430.47  5989.1  434.80  6054.6  439.42  6109.3  439.99  6166.3  443.65
#Mann=3,-1,0
  3699.0    0.05       0  5104.7    0.03       0  5110.7    0.05       0
Bank Sta=5104.7,5110.7
Exp/Cntr=0.3,0.1

Type RM Length L Ch R = 1,17594,50,50,50
BEGIN DESCRIPTION:
MINE CREEK 3.12
END DESCRIPTION:
XS GIS Cut Line= 6
      3562620.06     10485289.78      3562835.34     10485692.57
      3562870.06     10485959.93      3562637.42     10486380.07
      3562599.23     10486588.40      3562651.31     10487414.80
#Sta/Elev= 30
  3737.1  434.19  3798.0  431.76  3836.2  426.65  3858.2  426.29  3874.5  423.04
  3880.1  423.75  3896.4  420.79  3902.1  421.45  3962.3  414.76  4222.6  402.86
  4263.5  399.82  4359.0  396.69  4529.8  391.01  4632.9  389.56  4722.1  390.38
  4746.5  390.67  4817.2  390.16  4882.5  392.59  4941.8  388.23  4963.9  388.72
  4998.0  387.46  5000.8  386.96  5004.0  387.46  5112.4  394.83  5429.2  396.16
  5509.4  401.47  5539.5  407.24  5579.5  406.10  5709.8  416.05  5983.5  425.74
#Mann=9,-1,0
  3737.1    0.05       0  4222.6     0.1       0  4359.0    0.05       0
  4722.1     0.1       0  4746.5    0.05       0  4941.8     0.1       0
  4963.9    0.05       0  4998.0    0.03       0  5004.0    0.05       0
Bank Sta=4998,5004
Exp/Cntr=0.3,0.1

Type RM Length L Ch R = 1,17544,105,105,105
BEGIN DESCRIPTION:
MINE CREEK 3.8
END DESCRIPTION:
XS GIS Cut Line= 6
      3562529.80     10485324.54      3562772.84     10485671.74
      3562811.03     10485949.51      3562595.76     10486362.71
      3562550.62     10486529.38      3562592.29     10487414.82
#Sta/Elev= 30
  3762.4  426.10  3791.0  422.36  3811.9  422.87  3826.7  420.01  3913.0  414.77
  4056.0  409.65  4142.3  409.89  4233.7  403.61  4432.9  395.27  4619.1  390.23
  4663.2  389.67  4665.9  389.17  4669.2  389.67  4747.9  390.26  4850.4  391.05
  4970.6  400.69  5002.7  399.34  5007.9  401.59  5015.7  401.35  5118.9  395.72
  5349.1  395.19  5465.6  397.19  5509.3  400.13  5539.3  406.70  5564.0  407.20
  5589.4  405.05  5662.4  410.83  5699.5  415.09  5759.6  415.30  5993.0  425.84
#Mann=12,-1,0
  3762.4    0.05       0  4233.7     0.1       0  4432.9    0.05       0
  4619.1     0.1       0  4663.2    0.03       0  4669.2     0.1       0
  4747.9    0.05       0  4850.4     0.1       0  4970.6    0.05       0
  5465.6    0.08       0  5564.0     0.1       0  5662.4    0.08       0
Bank Sta=4663.2,4669.2
Exp/Cntr=0.3,0.1

Type RM Length L Ch R = 1,17439,45,45,45
BEGIN DESCRIPTION:
MINE CREEK 3.10
END DESCRIPTION:
XS GIS Cut Line= 6
      3562411.69     10485477.26      3562623.53     10485626.60
      3562689.51     10485873.13      3562675.62     10486015.49
      3562481.17     10486345.35      3562477.70     10487411.29
#Sta/Elev= 30
  3892.6  419.56  3975.5  415.09  4343.3  404.05  4358.9  401.04  4445.4  396.51
  4610.5  391.20  4649.1  390.70  4790.1  389.48  4807.6  391.44  4813.1  389.71
  4847.9  389.78  4954.0  393.92  4981.2  386.42  4983.9  385.92  4987.2  386.42
  5004.3  389.92  5044.5  390.23  5071.1  395.00  5114.9  395.39  5205.4  401.24
  5262.6  401.18  5302.5  397.19  5356.0  395.22  5526.2  396.51  5576.3  398.80
  5656.3  403.92  5746.4  412.75  5791.2  413.76  5887.6  416.55  6006.4  424.52
#Mann=10,-1,0
  3892.6    0.05       0  4445.4     0.1       0  4610.5    0.05       0
  4649.1     0.1       0  4847.9    0.05       0  4981.2    0.07       0
  4987.2    0.05       0  5576.3    0.08       0  5791.2    0.05       0
  5887.6     0.1       0
Bank Sta=4981.2,4987.2
Exp/Cntr=0.3,0.1

Type RM Length L Ch R = 1,17394,913,913,913
BEGIN DESCRIPTION:
MINE CREEK 3.11
END DESCRIPTION:
XS GIS Cut Line= 6
      3562349.21     10485505.06      3562578.40     10485689.10
      3562640.90     10485932.15      3562439.51     10486324.51
      3562366.59     10486779.38      3562397.75     10487378.37
#Sta/Elev= 30
  3938.8  422.41  4052.3  416.05  4338.6  406.06  4400.6  400.66  4584.7  390.48
  4675.1  389.86  4682.6  389.80  4845.4  388.92  4889.8  392.37  4945.6  392.88
  4972.2  386.61  4989.4  385.27  4992.1  384.77  4995.4  385.27  5012.5  388.08
  5042.8  387.28  5062.9  392.02  5083.1  394.17  5184.4  396.44  5245.5  401.26
  5330.1  399.09  5357.4  395.51  5437.9  397.10  5518.0  395.26  5585.6  397.02
  5628.2  399.18  5718.3  408.50  5848.5  414.20  5934.4  420.54  5985.4  422.48
#Mann=6,-1,0
  3938.8    0.05       0  4675.1     0.1       0  4682.6    0.05       0
  4989.4    0.03       0  4995.4    0.05       0  5934.4     0.1       0
Bank Sta=4989.4,4995.4
Exp/Cntr=0.3,0.1

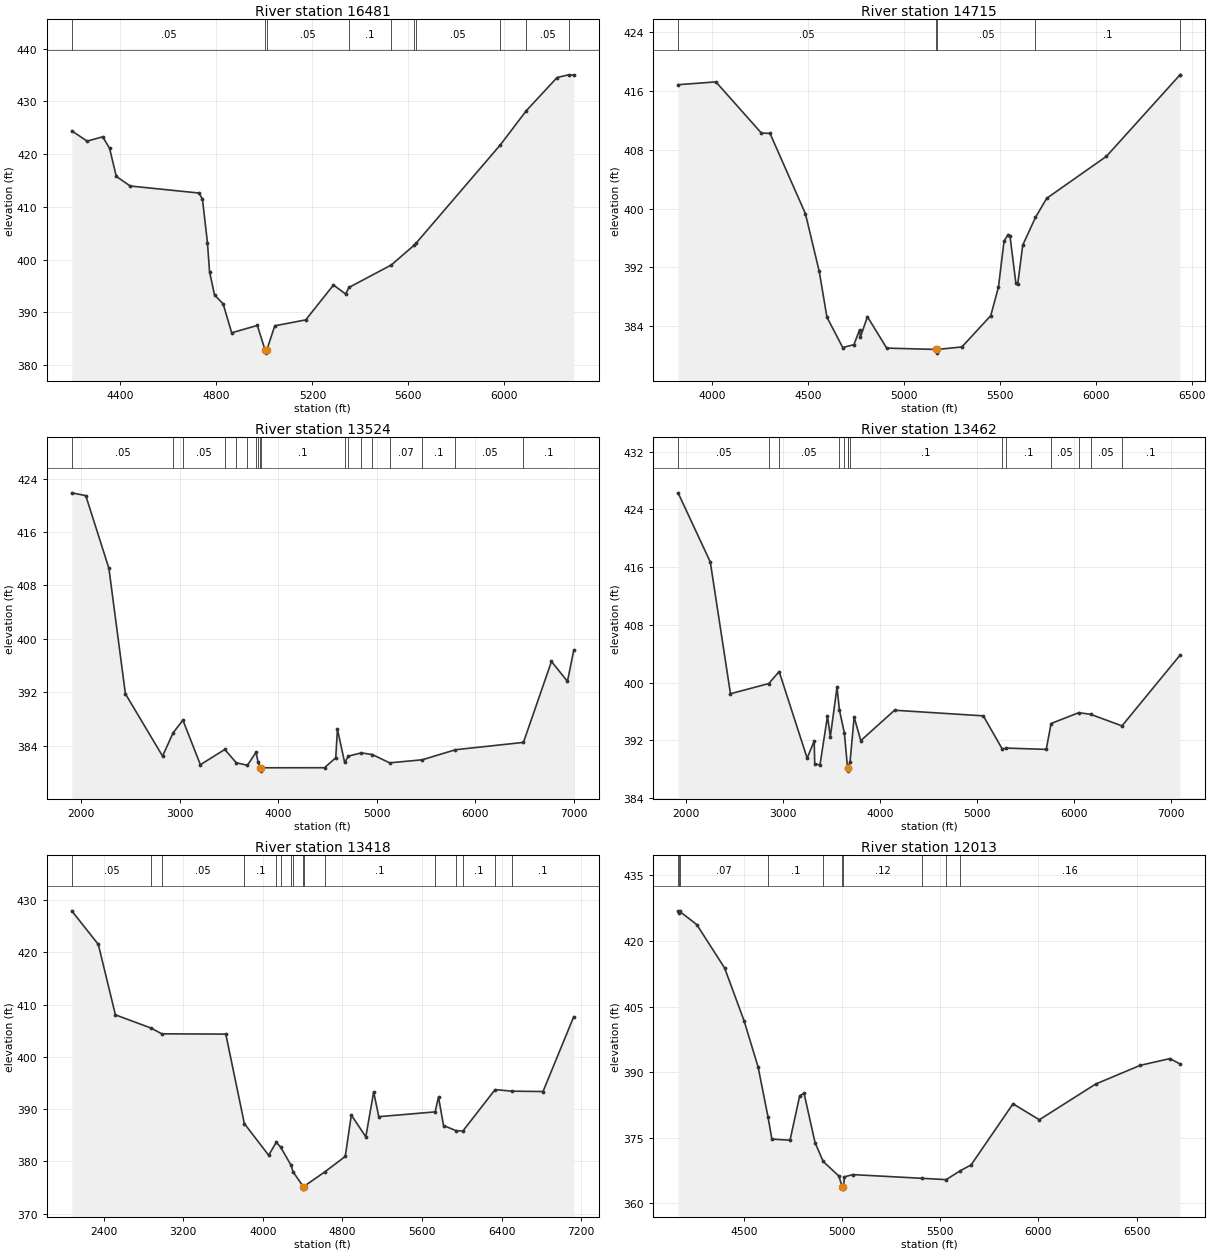
Type RM Length L Ch R = 1,16481,1766,1766,1766
BEGIN DESCRIPTION:
MINE CREEK 3.19
END DESCRIPTION:
XS GIS Cut Line= 2
      3562073.46     10485473.49      3560858.20     10487174.84
#Sta/Elev= 30
  4197.6  424.41  4261.5  422.45  4326.7  423.28  4355.1  421.08  4383.2  415.77
  4441.1  413.95  4727.3  412.62  4742.0  411.47  4762.9  403.16  4771.5  397.71
  4792.4  393.29  4828.1  391.62  4863.7  386.13  4970.6  387.53  5003.4  382.78
  5006.2  382.28  5009.4  382.78  5043.3  387.46  5172.2  388.58  5287.7  395.19
  5338.1  393.49  5352.4  394.73  5528.5  398.98  5624.3  402.75  5631.9  403.12
  5983.2  421.77  6091.0  428.22  6219.2  434.51  6267.2  435.02  6288.4  434.97
#Mann=10,-1,0
  4197.6    0.05       0  5003.4    0.03       0  5009.4    0.05       0
  5352.4     0.1       0  5528.5    0.16       0  5624.3     0.1       0
  5631.9    0.05       0  5983.2     0.1       0  6091.0    0.05       0
  6267.2     0.1       0
Bank Sta=5003.4,5009.4
Exp/Cntr=0.3,0.1

Type RM Length L Ch R = 1,14715,1191,1191,1191
BEGIN DESCRIPTION:
MINE CREEK 3.20
END DESCRIPTION:
XS GIS Cut Line= 2
      3560267.92     10484119.31      3559990.15     10486723.44
#Sta/Elev= 30
  3820.5  416.82  4017.8  417.20  4255.3  410.25  4300.1  410.21  4484.9  399.31
  4557.0  391.47  4597.2  385.25  4679.7  381.13  4738.0  381.52  4767.1  383.50
  4772.1  382.56  4808.4  385.32  4909.0  381.05  5167.4  380.87  5170.2  380.37
  5173.4  380.87  5301.2  381.21  5452.0  385.46  5492.3  389.36  5521.3  395.59
  5542.5  396.47  5552.6  396.22  5582.8  389.90  5592.8  389.75  5618.7  395.03
  5685.3  398.80  5743.7  401.39  6055.4  407.09  6439.3  418.16  6439.4  418.16
#Mann=5,-1,0
  3820.5    0.05       0  5167.4   0.035       0  5173.4    0.05       0
  5685.3     0.1       0  6439.3    0.16       0
Bank Sta=5167.4,5173.4
Exp/Cntr=0.3,0.1

Type RM Length L Ch R = 1,13524,62,62,62
BEGIN DESCRIPTION:
MINE CREEK 3.14
END DESCRIPTION:
XS GIS Cut Line= 6
      3559949.61     10483601.24      3559671.86     10484045.65
      3558660.57     10484096.00      3559294.25     10484877.25
      3557953.11     10485736.62      3557857.34     10486369.75
#Sta/Elev= 30
  1905.6  421.86  2047.9  421.44  2282.6  410.56  2449.9  391.79  2827.3  382.46
  2935.0  385.96  3033.9  387.84  3211.1  381.17  3458.7  383.45  3575.0  381.47
  3688.3  381.08  3775.7  383.02  3796.9  381.58  3819.1  380.71  3821.9  380.21
  3825.1  380.71  4471.1  380.72  4585.1  382.21  4602.5  386.48  4675.3  381.52
  4714.6  382.46  4845.3  382.94  4956.5  382.69  5132.0  381.45  5464.3  381.91
  5799.3  383.41  6490.5  384.51  6774.9  396.62  6937.0  393.65  7000.5  398.27
#Mann=18,-1,0
  1905.6    0.05       0  2935.0     0.1       0  3033.9    0.05       0
  3458.7     0.1       0  3575.0    0.05       0  3688.3     0.1       0
  3775.7    0.05       0  3796.9     0.1       0  3819.1    0.07       0
  3825.1     0.1       0  4675.3    0.07       0  4714.6     0.1       0
  4845.3    0.07       0  4956.5     0.1       0  5132.0    0.07       0
  5464.3     0.1       0  5799.3    0.05       0  6490.5     0.1       0
Bank Sta=3819.1,3825.1
Exp/Cntr=0.3,0.1

Type RM Length L Ch R = 1,13462,44,44,44
BEGIN DESCRIPTION:
MINE CREEK 3.13
END DESCRIPTION:
XS GIS Cut Line= 6
      3559829.12     10483486.28      3559688.06     10483974.54
      3558610.22     10484063.88      3559187.48     10484862.49
      3557954.84     10485669.78      3557785.31     10486407.12
#Sta/Elev= 30
  1914.8  426.28  2247.3  416.71  2455.6  398.47  2850.8  399.88  2958.1  401.54
  3247.3  389.55  3319.8  391.94  3325.2  388.81  3379.0  388.59  3456.9  395.36
  3486.5  392.53  3555.3  399.39  3580.2  396.22  3631.5  393.02  3663.8  388.26
  3666.6  387.76  3669.8  388.26  3690.0  389.05  3732.0  395.25  3800.7  391.98
  4149.4  396.19  5065.4  395.41  5261.0  390.82  5302.7  390.95  5714.9  390.77
  5765.0  394.35  6050.2  395.85  6171.8  395.63  6496.5  394.02  7095.7  403.81
#Mann=14,-1,0
  1914.8    0.05       0  2850.8     0.1       0  2958.1    0.05       0
  3580.2     0.1       0  3631.5    0.05       0  3663.8    0.07       0
  3669.8    0.05       0  3690.0     0.1       0  5261.0    0.07       0
  5302.7     0.1       0  5765.0    0.05       0  6050.2     0.1       0
  6171.8    0.05       0  6496.5     0.1       0
Bank Sta=3663.8,3669.8
Exp/Cntr=0.3,0.1

Type RM Length L Ch R = 1,13418,1405,1405,1405
BEGIN DESCRIPTION:
MINE CREEK 3.15
END DESCRIPTION:
XS GIS Cut Line= 6
      3559754.32     10483471.00      3559628.45     10483887.67
      3558460.92     10484152.42      3559077.24     10484838.19
      3557940.09     10485623.78      3557723.07     10486405.02
#Sta/Elev= 30
  2079.3  427.92  2346.3  421.49  2518.0  408.02  2879.3  405.47  2983.1  404.39
  3627.2  404.34  3813.9  387.21  4058.2  381.16  4134.4  383.64  4178.9  382.71
  4284.2  379.21  4303.2  377.99  4405.1  375.18  4407.9  374.68  4411.1  375.18
  4622.7  377.99  4827.7  380.93  4888.9  388.85  5034.5  384.68  5113.2  393.28
  5164.8  388.54  5730.9  389.46  5764.9  392.29  5815.4  386.85  5940.5  385.87
  6009.4  385.79  6333.5  393.72  6500.0  393.42  6815.2  393.35  7123.5  407.65
#Mann=16,-1,0
  2079.3    0.05       0  2879.3     0.1       0  2983.1    0.05       0
  3813.9     0.1       0  4134.4    0.16       0  4178.9     0.1       0
  4284.2    0.16       0  4303.2    0.12       0  4405.1    0.07       0
  4411.1    0.12       0  4622.7     0.1       0  5730.9    0.05       0
  5940.5    0.16       0  6009.4     0.1       0  6333.5    0.05       0
  6500.0     0.1       0
Bank Sta=4405.1,4411.1
Exp/Cntr=0.3,0.1

Type RM Length L Ch R = 1,12013,2107,2107,2107
BEGIN DESCRIPTION:
MINE CREEK 3.22
END DESCRIPTION:
XS GIS Cut Line= 3
      3558400.17     10483575.88      3557219.60     10484999.50
      3557315.08     10485702.60
#Sta/Elev= 30
  4162.5  426.88  4165.9  426.43  4170.5  426.76  4257.9  423.73  4399.8  413.81
  4498.8  401.77  4570.4  391.21  4621.2  379.72  4640.7  374.70  4733.2  374.44
  4782.7  384.62  4804.8  385.16  4860.8  373.90  4902.3  369.58  4981.9  366.27
  4999.7  363.76  5002.5  363.26  5005.7  363.76  5010.6  366.07  5053.4  366.58
  5406.9  365.73  5529.2  365.43  5600.2  367.44  5656.5  368.80  5870.1  382.77
  6004.2  379.12  6291.1  387.27  6518.7  391.56  6670.1  393.10  6721.5  391.87
#Mann=10,-1,0
  4162.5    0.07       0  4165.9    0.05       0  4170.5    0.07       0
  4621.2     0.1       0  4902.3    0.12       0  4999.7    0.07       0
  5005.7    0.12       0  5406.9    0.16       0  5529.2    0.12       0
  5600.2    0.16       0
Bank Sta=4999.7,5005.7
Exp/Cntr=0.3,0.1

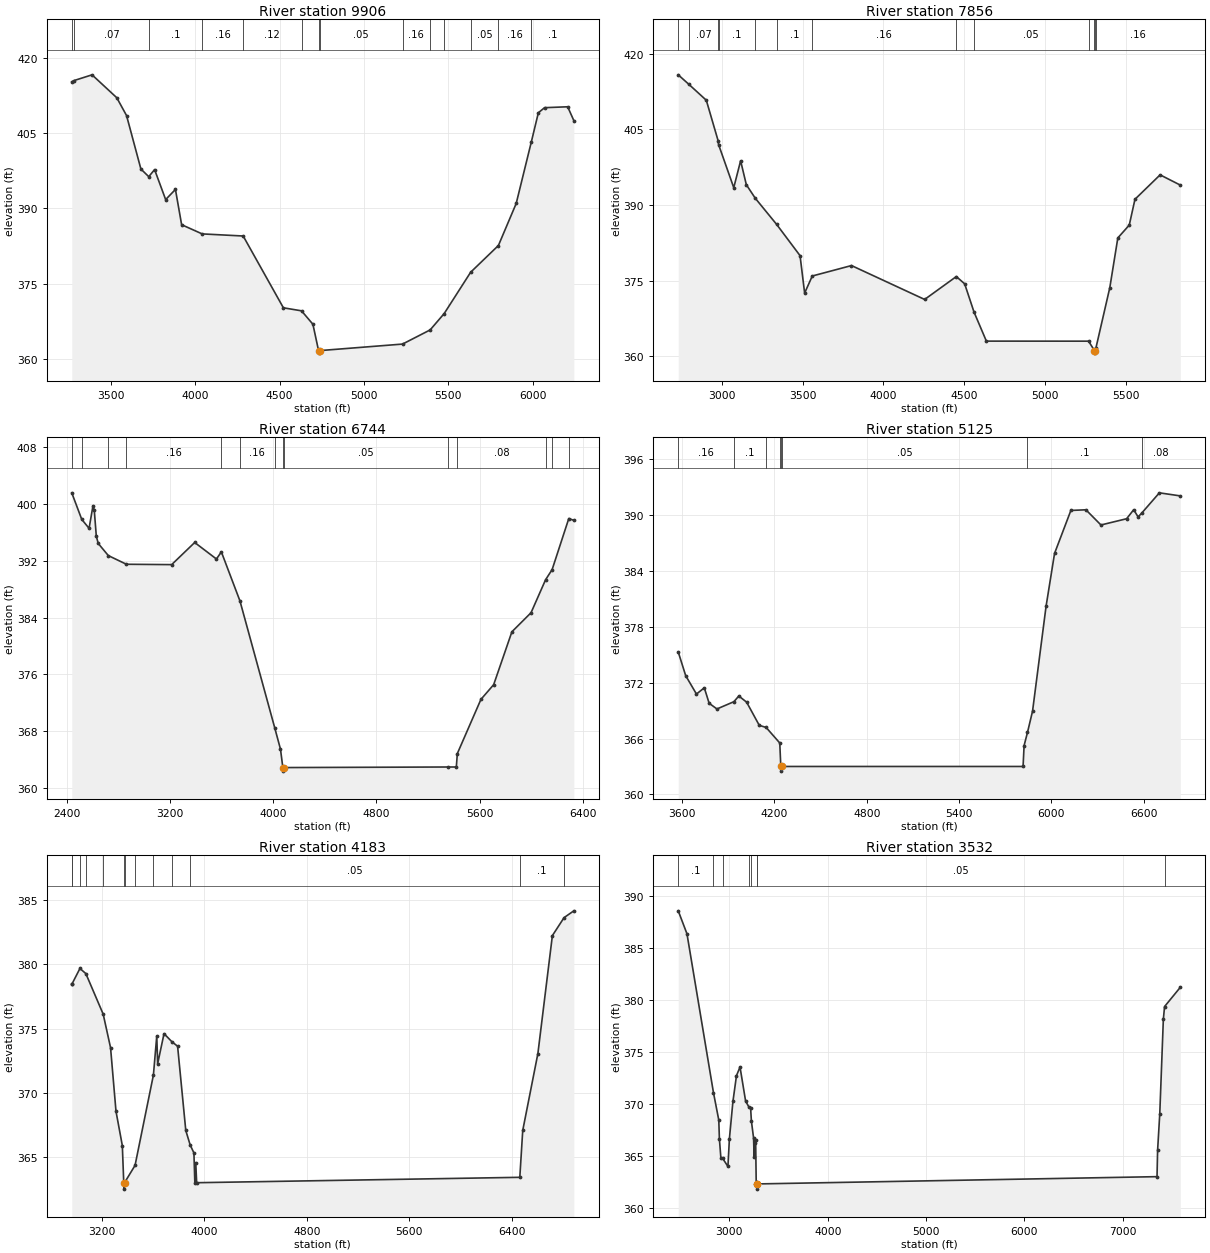
Type RM Length L Ch R = 1,9906,2050,2050,2050
BEGIN DESCRIPTION:
MINE CREEK 3.17
END DESCRIPTION:
XS GIS Cut Line= 2
      3557490.11     10482904.03      3554956.26     10484466.00
#Sta/Elev= 30
  3268.2  415.20  3282.6  415.46  3388.4  416.59  3535.1  412.03  3593.0  408.48
  3678.1  397.84  3724.6  396.32  3759.2  397.73  3824.8  391.76  3882.8  393.78
  3919.5  386.76  4041.2  384.93  4284.4  384.51  4522.8  370.22  4630.2  369.62
  4697.8  366.95  4731.3  361.70  4734.0  361.20  4737.3  361.70  5229.1  363.00
  5392.9  365.82  5476.2  369.08  5633.0  377.30  5797.6  382.62  5903.1  390.99
  5992.2  403.16  6034.4  409.04  6071.1  410.05  6208.2  410.23  6244.8  407.48
#Mann=14,-1,0
  3268.2    0.16       0  3282.6    0.07       0  3724.6     0.1       0
  4041.2    0.16       0  4284.4    0.12       0  4630.2    0.05       0
  4731.3   0.033       0  4737.3    0.05       0  5229.1    0.16       0
  5392.9     0.1       0  5476.2    0.16       0  5633.0    0.05       0
  5797.6    0.16       0  5992.2     0.1       0
Bank Sta=4731.3,4737.3
Exp/Cntr=0.3,0.1

Type RM Length L Ch R = 1,7856,1112,1112,1112
BEGIN DESCRIPTION:
MINE CREEK 3.16
END DESCRIPTION:
XS GIS Cut Line= 2
      3556413.78     10480577.60      3554208.91     10482765.11
#Sta/Elev= 30
  2730.6  415.80  2795.5  413.94  2904.3  410.76  2976.9  402.78  2980.1  401.98
  3074.0  393.43  3116.5  398.76  3151.8  394.02  3207.0  391.34  3339.0  386.16
  3484.2  379.95  3512.5  372.53  3559.8  375.92  3802.4  377.99  4254.9  371.27
  4450.9  375.81  4502.4  374.37  4560.5  368.76  4636.8  363.01  5269.0  363.00
  5305.5  361.13  5308.3  360.63  5311.5  361.13  5314.8  361.69  5400.4  373.62
  5450.0  383.47  5520.7  386.01  5556.0  391.13  5711.6  395.97  5836.5  393.94
#Mann=13,-1,0
  2730.6    0.16       0  2795.5    0.07       0  2976.9    0.16       0
  2980.1     0.1       0  3207.0    0.05       0  3339.0     0.1       0
  3559.8    0.16       0  4450.9    0.07       0  4560.5    0.05       0
  5269.0     0.1       0  5305.5   0.033       0  5311.5     0.1       0
  5314.8    0.16       0
Bank Sta=5305.5,5311.5
Exp/Cntr=0.3,0.1

Type RM Length L Ch R = 1,6744,1619,1619,1619
BEGIN DESCRIPTION:
MINE CREEK 3.21
END DESCRIPTION:
XS GIS Cut Line= 3
      3556274.83     10480456.09      3555163.75     10480282.49
      3553185.99     10482225.55
#Sta/Elev= 30
  2435.0  401.53  2512.4  397.80  2569.3  396.54  2599.7  399.72  2609.8  399.05
  2625.4  395.45  2640.2  394.42  2718.7  392.71  2859.3  391.49  3210.4  391.44
  3389.2  394.55  3557.9  392.23  3596.1  393.23  3740.4  386.34  4009.7  368.55
  4055.1  365.50  4073.4  362.92  4076.1  362.42  4079.4  362.92  5355.8  363.00
  5419.9  363.00  5427.8  364.89  5610.8  372.50  5709.8  374.57  5851.2  382.00
  5999.8  384.68  6112.8  389.32  6163.5  390.74  6292.9  397.92  6332.1  397.66
#Mann=14,-1,0
  2435.0    0.07       0  2512.4     0.1       0  2718.7    0.05       0
  2859.3    0.16       0  3596.1    0.05       0  3740.4    0.16       0
  4009.7    0.05       0  4073.4   0.033       0  4079.4    0.05       0
  5355.8     0.1       0  5427.8    0.08       0  6112.8     0.1       0
  6163.5    0.05       0  6292.9     0.1       0
Bank Sta=4073.4,4079.4
Exp/Cntr=0.3,0.1

Type RM Length L Ch R = 1,5125,942,942,942
BEGIN DESCRIPTION:
MINE CREEK 3.0
END DESCRIPTION:
XS GIS Cut Line= 3
      3553336.00     10478905.57      3553162.39     10479764.91
      3552172.82     10481935.03
#Sta/Elev= 30
  3575.3  375.29  3623.8  372.74  3693.7  370.77  3744.7  371.44  3776.1  369.78
  3826.8  369.17  3936.9  369.95  3968.9  370.56  4019.6  369.90  4101.8  367.41
  4146.1  367.19  4234.9  365.52  4241.6  363.00  4244.4  362.50  4247.6  363.00
  5815.6  363.00  5822.2  365.24  5844.2  366.65  5877.2  368.94  5965.1  380.20
  6020.1  385.86  6126.1  390.47  6223.8  390.54  6321.5  388.91  6488.3  389.58
  6534.3  390.55  6562.9  389.77  6587.7  390.21  6701.1  392.36  6837.1  392.03
#Mann=8,-1,0
  3575.3    0.16       0  3936.9     0.1       0  4146.1    0.07       0
  4234.9    0.05       0  4241.6   0.033       0  4247.6    0.05       0
  5844.2     0.1       0  6587.7    0.08       0
Bank Sta=4241.6,4247.6
Exp/Cntr=0.3,0.1

Type RM Length L Ch R = 1,4183,651,651,651
BEGIN DESCRIPTION:
MINE CREEK 1.0
END DESCRIPTION:
XS GIS Cut Line= 3
      3553301.31     10478593.01      3552059.96     10479799.64
      3551678.01     10481952.46
#Sta/Elev= 30
  2965.8  378.50  2969.0  378.51  3029.5  379.69  3075.7  379.29  3211.0  376.13
  3268.4  373.52  3310.9  368.56  3360.3  365.89  3371.4  363.00  3374.2  362.50
  3377.4  363.00  3459.6  364.35  3602.9  371.39  3629.0  374.43  3636.0  372.27
  3685.6  374.61  3746.3  373.99  3791.6  373.63  3855.4  367.07  3889.7  365.94
  3918.9  365.32  3926.1  363.00  3933.1  364.57  3940.3  363.00  6461.8  363.42
  6484.6  367.07  6602.8  373.06  6715.9  382.25  6807.1  383.65  6883.4  384.18
#Mann=13,-1,0
  2965.8     0.1       0  2969.0    0.08       0  3029.5    0.05       0
  3075.7     0.1       0  3211.0    0.16       0  3371.4   0.033       0
  3377.4    0.16       0  3459.6    0.05       0  3602.9     0.1       0
  3746.3    0.07       0  3889.7    0.05       0  6461.8     0.1       0
  6807.1    0.16       0
Bank Sta=3371.4,3377.4
Exp/Cntr=0.3,0.1

Type RM Length L Ch R = 1,3532,0,0,0
BEGIN DESCRIPTION:
MINE CREEK 2.0
END DESCRIPTION:
XS GIS Cut Line= 3
      3552789.13     10477846.51      3550697.12     10480945.47
      3551469.69     10482073.95
#Sta/Elev= 30
  2479.5  388.58  2568.3  386.37  2837.9  371.08  2892.0  368.44  2898.1  366.63
  2913.0  364.83  2931.7  364.75  2985.0  363.98  2999.9  366.65  3035.9  370.24
  3071.9  372.72  3107.9  373.55  3164.8  370.27  3196.1  369.74  3215.8  369.58
  3223.6  368.35  3245.7  366.73  3251.7  364.85  3257.9  366.28  3266.7  366.53
  3272.7  362.36  3278.7  362.30  3281.4  361.80  3284.7  362.30  7349.2  363.00
  7355.2  365.54  7377.3  369.07  7413.6  378.15  7426.1  379.37  7586.1  381.22
#Mann=8,-1,0
  2479.5     0.1       0  2837.9    0.05       0  2931.7     0.1       0
  3196.1    0.07       0  3223.6    0.05       0  3278.7   0.033       0
  3284.7    0.05       0  7426.1     0.1       0
Bank Sta=3278.7,3284.7
Exp/Cntr=0.3,0.1

Chan Stop Cuts=-1