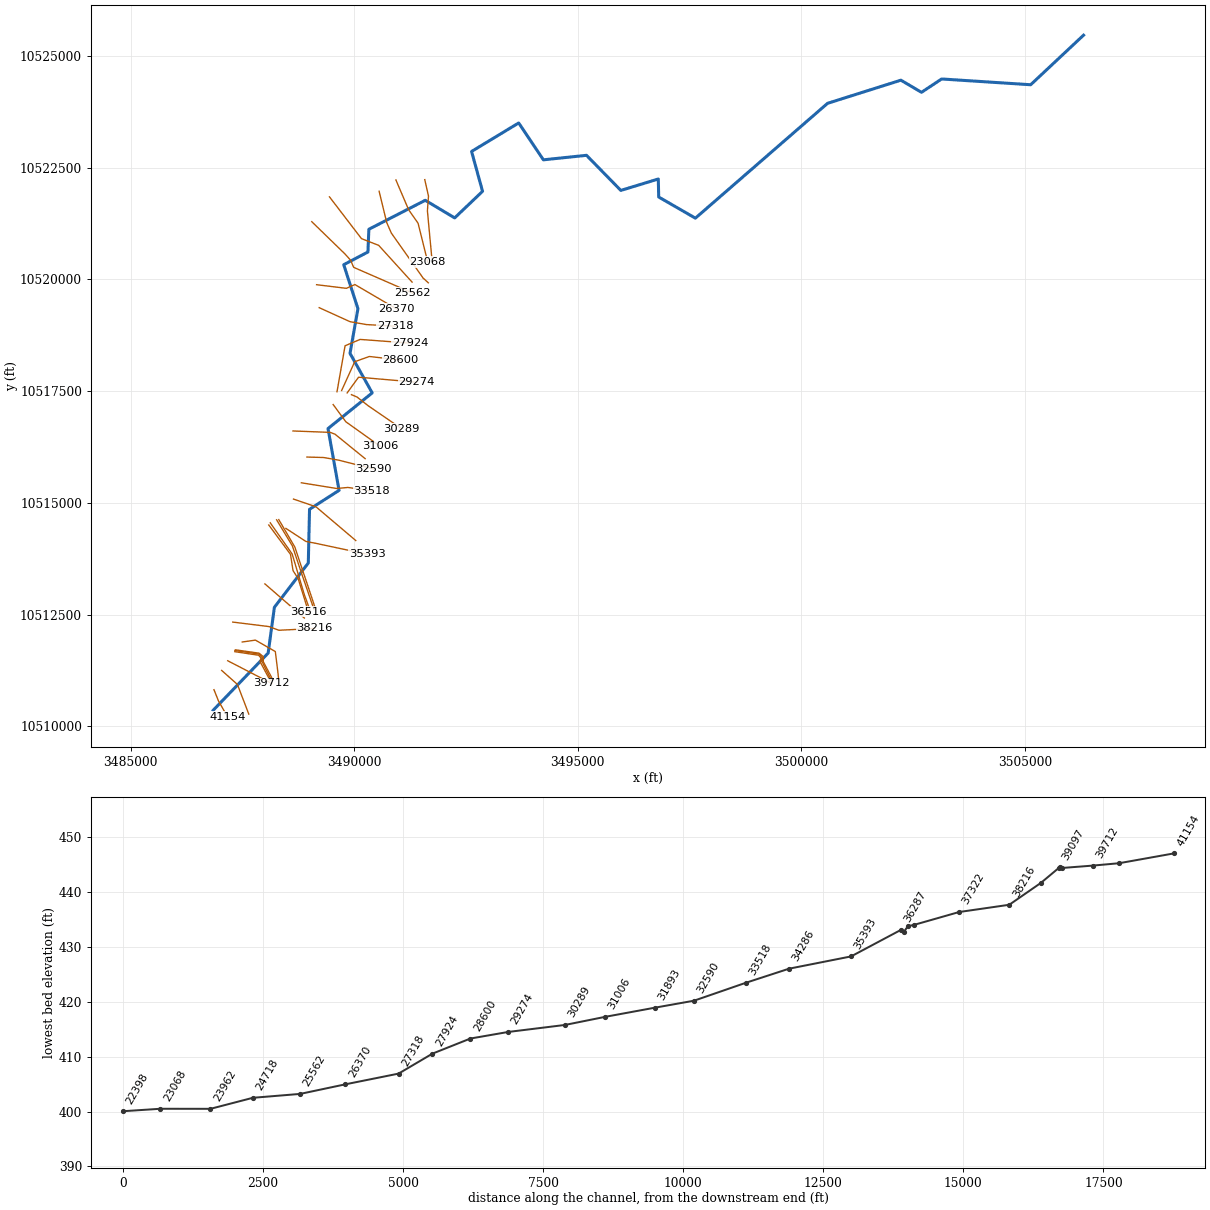
--- MONTGOMERY CREEK.prj (project) ---

Proj Title=MONTGOMERY CREEK Base Level Engineering
Current Plan=p01
Default Exp/Contr=0.3,0.1
English Units
Geom File=g01
Flow File=f01
Plan File=p01
Y Axis Title=Elevation
X Axis Title(PF)=Main Channel Distance
X Axis Title(XS)=Station
BEGIN DESCRIPTION:
MONTGOMERY CREEK
END DESCRIPTION:
DSS Export Rating Curves= 0
DSS Export Rating Curve Sorted= 0
DSS Export Volume Flow Curves= 0
DXF OffsetX= 0
DXF OffsetY= 0
DXF ScaleX= 1
DXF ScaleY= 10

--- MONTGOMERY CREEK.p01 (plan) ---

Plan Title=Multiple Run
Short Identifier=Multiple
Geom File=g01
Flow File=f01
Subcritical Flow
K Sum by GR= 0
Std Step Tol= 0.01
Critical Tol= 0.01
Num of Std Step Trials= 20
Max Error Tol= 0.3
Flow Tol Ratio= 0.001
Split Flow NTrial= 30
Split Flow Tol= 0.02
Split Flow Ratio= 0.02
Log Output Level= 0
Friction Slope Method= 1
Unsteady Friction Slope Method= 2
Unsteady Bridges Friction Slope Method= 1
Parabolic Critical Depth
Global Vel Dist=  1 , 1 , 1
Global Log Level= 0
CheckData=True
Encroach Param= -1, 0, 0, 0
BEGIN DESCRIPTION:
Multiple Run
END DESCRIPTION:

--- MONTGOMERY CREEK.f01 (steady flow) ---

Flow Title=Multiple
Program Version=4.10
Number of Profiles= 7
Profile Names=10-year,25-year,50-year,1pct_min,100-year,1pct_plu,500-year
River Rch & RM=MONTGOMERY CREEK,Reach-1         ,41154
    1127    1558    1915    1717    2322    3140    3404
River Rch & RM=MONTGOMERY CREEK,Reach-1         ,38216
    2152    3062    3837    3496    4728    6395    7169
River Rch & RM=MONTGOMERY CREEK,Reach-1         ,27318
    3576    5188    6585    6070    8209   11101   12735
River Rch & RM=MONTGOMERY CREEK,Reach-1         ,19311
    4028    5854    7438    6860    9277   12547   14408
River Rch & RM=MONTGOMERY CREEK,Reach-1         ,11019
    4144    6003    7611    7002    9469   12806   14629
River Rch & RM=MONTGOMERY CREEK,Reach-1         ,9313
    6152    9041   11575   10743   14528   19648   22844
Boundary for River Rch & Prof#=MONTGOMERY CREEK,Reach-1         , 1
Up Type= 0
Dn Type= 3
Dn Slope=0.00118
Boundary for River Rch & Prof#=MONTGOMERY CREEK,Reach-1         , 2
Up Type= 0
Dn Type= 3
Dn Slope=0.00118
Boundary for River Rch & Prof#=MONTGOMERY CREEK,Reach-1         , 3
Up Type= 0
Dn Type= 3
Dn Slope=0.00118
Boundary for River Rch & Prof#=MONTGOMERY CREEK,Reach-1         , 4
Up Type= 0
Dn Type= 3
Dn Slope=0.00118
Boundary for River Rch & Prof#=MONTGOMERY CREEK,Reach-1         , 5
Up Type= 0
Dn Type= 3
Dn Slope=0.00118
Boundary for River Rch & Prof#=MONTGOMERY CREEK,Reach-1         , 6
Up Type= 0
Dn Type= 3
Dn Slope=0.00118
Boundary for River Rch & Prof#=MONTGOMERY CREEK,Reach-1         , 7
Up Type= 0
Dn Type= 3
Dn Slope=0.00118
DSS Import GetInterval= 0
DSS Import GetPeak= 0
DSS Import FillOption= 0

--- MONTGOMERY CREEK.g01 (geometry) ---

Geom Title=Existing Conditions
Program Version=4.10

River Reach=MONTGOMERY CREEK,Reach-1
Reach XY= 30
      3486842.11     10510361.64       3488072.1     10511641.81
      3488211.95     10512666.94      3488970.33     10513657.19
      3488998.05     10514859.16      3489658.59     10515282.43
      3489411.36     10516664.99      3490400.14      10517463.1
      3489903.55     10518347.66      3490081.06     10519346.84
      3489762.93     10520331.32      3490304.44     10520615.14
       3490325.4     10521123.81      3491586.95      10521771.7
      3492244.75     10521377.87      3492868.91     10521972.55
       3492623.2     10522864.51      3493677.15     10523502.18
      3494229.79     10522677.29      3495194.74     10522777.95
      3495962.49     10521992.77      3496800.55     10522248.54
      3496809.63     10521845.32      3497630.38     10521372.19
      3500587.28     10523941.22      3502227.95     10524459.15
      3502689.06     10524187.27      3503138.82     10524486.25
      3505131.27     10524357.08       3506314.1     10525465.52

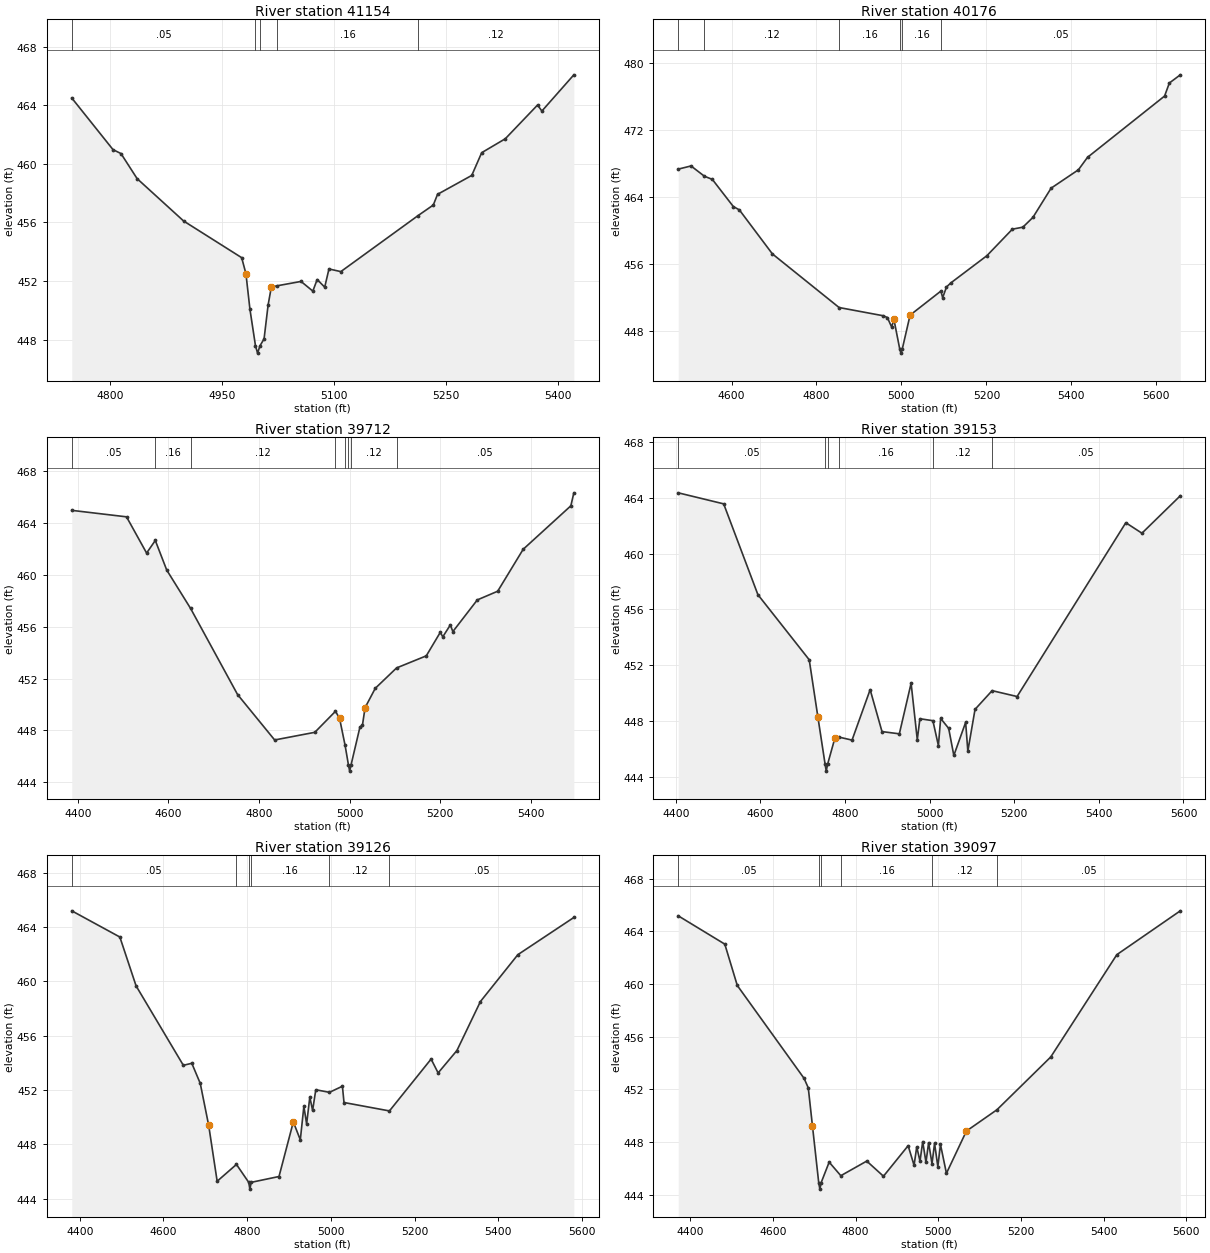
Type RM Length L Ch R = 1 ,41154   ,978,978,978
BEGIN DESCRIPTION:
MONTGOMERY CREEK 61.0
END DESCRIPTION:
XS GIS Cut Line= 3
      3486860.34     10510822.87      3486960.33     10510572.89
      3487160.31     10510222.93
#Sta/Elev= 30
  4748.5  464.49  4803.7  460.97  4814.4   460.7    4836  458.99  4898.3   456.1
    4976   453.6  4981.7  452.51  4987.1  450.07  4994.5  447.59  4997.3  447.09
  5000.5  447.59    5006  448.06  5011.4  450.37  5015.7  451.59  5023.3  451.68
  5055.5  451.98  5071.3  451.32  5077.1  452.11  5087.2  451.59  5092.9  452.83
  5108.8  452.65  5212.2  456.47  5232.6  457.19  5238.3  457.92  5284.1  459.21
  5297.4  460.76    5329  461.71  5372.2  464.01    5378   463.6  5420.8  466.07
#Mann= 5 ,-1 , 0
  4748.5     .05       0  4994.5    .035       0  5000.5     .05       0
  5023.3     .16       0  5212.2     .12       0
Bank Sta=4981.7,5015.7
XS Rating Curve= 0 ,0
Exp/Cntr=0.3,0.1

Type RM Length L Ch R = 1 ,40176   ,464,464,464
BEGIN DESCRIPTION:
MONTGOMERY CREEK 59.0
END DESCRIPTION:
XS GIS Cut Line= 3
      3487031.81     10511254.21       3487384.4      10510941.1
      3487638.63     10510277.59
#Sta/Elev= 30
  4474.5  467.33  4504.6  467.71  4536.1  466.48  4554.8   466.1  4604.2  462.85
  4618.4  462.45  4696.2  457.18  4853.2  450.76  4957.6  449.77  4966.9  449.56
  4976.9  448.43  4982.3  449.34    4996   445.8  4998.8   445.3    5002   445.8
  5020.4  449.85  5092.9  452.73  5097.1  451.94  5106.1  453.22  5116.4  453.71
  5201.1  456.96  5261.2  460.14  5285.9  460.38  5309.6  461.55  5352.4  465.05
  5416.7  467.25  5438.1  468.74  5619.6  476.08  5630.8  477.64  5656.6  478.62
#Mann= 6 ,-1 , 0
  4474.5     .05       0  4536.1     .12       0  4853.2     .16       0
    4996     .07       0    5002     .16       0  5092.9     .05       0
Bank Sta=4982.3,5020.4
XS Rating Curve= 0 ,0
Exp/Cntr=0.3,0.1

Type RM Length L Ch R = 1 ,39712   ,559,559,559
BEGIN DESCRIPTION:
MONTGOMERY CREEK 58.0
END DESCRIPTION:
XS GIS Cut Line= 2
      3487167.01     10511470.63      3488151.44     10510962.79
#Sta/Elev= 30
  4386.8  464.96  4507.6  464.46  4551.9  461.67  4571.1  462.64  4596.3  460.36
    4649   457.4  4752.6  450.77  4834.4  447.27    4923  447.86  4968.6  449.48
  4977.6  448.94  4989.8  446.86  4997.1  445.37  4999.9  444.87  5003.1  445.37
  5022.5  448.25  5028.2  448.43  5033.9  449.76  5056.4  451.25  5103.4  452.82
  5168.9  453.75  5199.8  455.56  5205.4  455.22    5222  456.13  5227.6  455.62
  5281.5  458.06  5326.5  458.73  5382.7  461.96  5487.9  465.31  5494.5  466.31
#Mann= 8 ,-1 , 0
  4386.8     .05       0  4571.1     .16       0    4649     .12       0
  4968.6     .16       0  4989.8     .12       0  4997.1     .07       0
  5003.1     .12       0  5103.4     .05       0
Bank Sta=4977.6,5033.9
XS Rating Curve= 0 ,0
Exp/Cntr=0.3,0.1

Type RM Length L Ch R = 1 ,39153   ,27,27,27
BEGIN DESCRIPTION:
MONTGOMERY CREEK 58.1
END DESCRIPTION:
XS GIS Cut Line= 5
      3487325.92     10511673.74      3487862.34     10511593.02
      3487911.82     10511527.92      3487890.99     10511449.79
      3488119.78       10511026.
#Sta/Elev= 30
  4405.8  464.35  4513.2  463.56  4594.1  457.06  4715.4   452.4  4735.7  448.34
  4752.9  444.93  4755.6  444.43  4758.9  444.93  4776.1   446.8  4785.1  446.87
  4816.6  446.65  4859.4  450.26  4887.4  447.26  4928.4   447.1  4956.2  450.72
  4970.8  446.68    4977  448.18  5007.7  448.04  5020.7  446.26  5026.1   448.2
    5045  447.49  5057.2  445.55  5085.1  447.92  5090.3  445.86  5107.3  448.85
  5147.7  450.19  5206.7  449.77  5463.7  462.21  5501.8  461.46  5592.5  464.14
#Mann= 6 ,-1 , 0
  4405.8     .05       0  4752.9     .07       0  4758.9     .05       0
  4785.1     .16       0  5007.7     .12       0  5147.7     .05       0
Bank Sta=4735.7,4776.1
XS Rating Curve= 0 ,0
Exp/Cntr=0.3,0.1

Type RM Length L Ch R = 1 ,39126   ,29,29,29
BEGIN DESCRIPTION:
MONTGOMERY CREEK 58.2
END DESCRIPTION:
XS GIS Cut Line= 6
      3487328.46      10511699.8      3487870.16     10511619.06
      3487937.86     10511540.94      3487930.05     10511462.81
      3488091.51     10511137.29       3488145.3     10511045.07
#Sta/Elev= 30
  4380.9   465.2  4495.8  463.27  4534.6  459.67  4647.5  453.82  4667.7  453.97
  4687.9  452.49  4708.1  449.39  4728.3  445.28  4774.4  446.52  4803.7   445.2
  4806.5   444.7  4809.7   445.2  4876.1  445.63  4910.3  449.65    4927  448.33
  4935.5   450.8  4942.1   449.5  4949.7  451.48  4956.4   450.5    4964  452.02
  4996.6  451.83  5027.6  452.28  5031.4  451.08    5140  450.46  5239.5  454.28
  5256.3  453.26  5301.2  454.91  5357.4  458.52  5446.8  461.97  5580.6  464.71
#Mann= 6 ,-1 , 0
  4380.9     .05       0  4774.4     .16       0  4803.7     .07       0
  4809.7     .16       0  4996.6     .12       0    5140     .05       0
Bank Sta=4708.1,4910.3
XS Rating Curve= 0 ,0
Exp/Cntr=0.3,0.1

Type RM Length L Ch R = 1 ,39097   ,315,315,315
BEGIN DESCRIPTION:
MONTGOMERY CREEK 58.3
END DESCRIPTION:
XS GIS Cut Line= 6
      3487340.64     10511714.55      3487867.99     10511640.76
      3487963.47     10511562.64      3487963.47     10511486.68
      3487963.47     10511449.79      3488171.31     10511055.76
#Sta/Elev= 30
  4371.1  465.17  4483.7  463.02  4513.9  459.88  4675.5  452.82  4685.6   452.1
  4695.7  449.21  4710.8  444.91  4713.6  444.41  4716.8  444.91  4736.1  446.46
  4764.3  445.43    4827  446.54  4867.4  445.39  4927.1  447.71  4941.4  446.22
  4947.9  447.62  4955.8  446.53  4962.3  448.02  4970.2  446.45  4976.6  447.94
  4984.8  446.34    4991  447.89  4998.9  446.12  5005.3   447.8  5019.7  445.61
    5068  448.82  5141.9  450.44    5272  454.45  5431.8  462.22  5585.3  465.55
#Mann= 6 ,-1 , 0
  4371.1     .05       0  4710.8     .07       0  4716.8     .05       0
  4764.3     .16       0  4984.8     .12       0  5141.9     .05       0
Bank Sta=4695.7,5068
XS Rating Curve= 0 ,0
Exp/Cntr=0.3,0.1

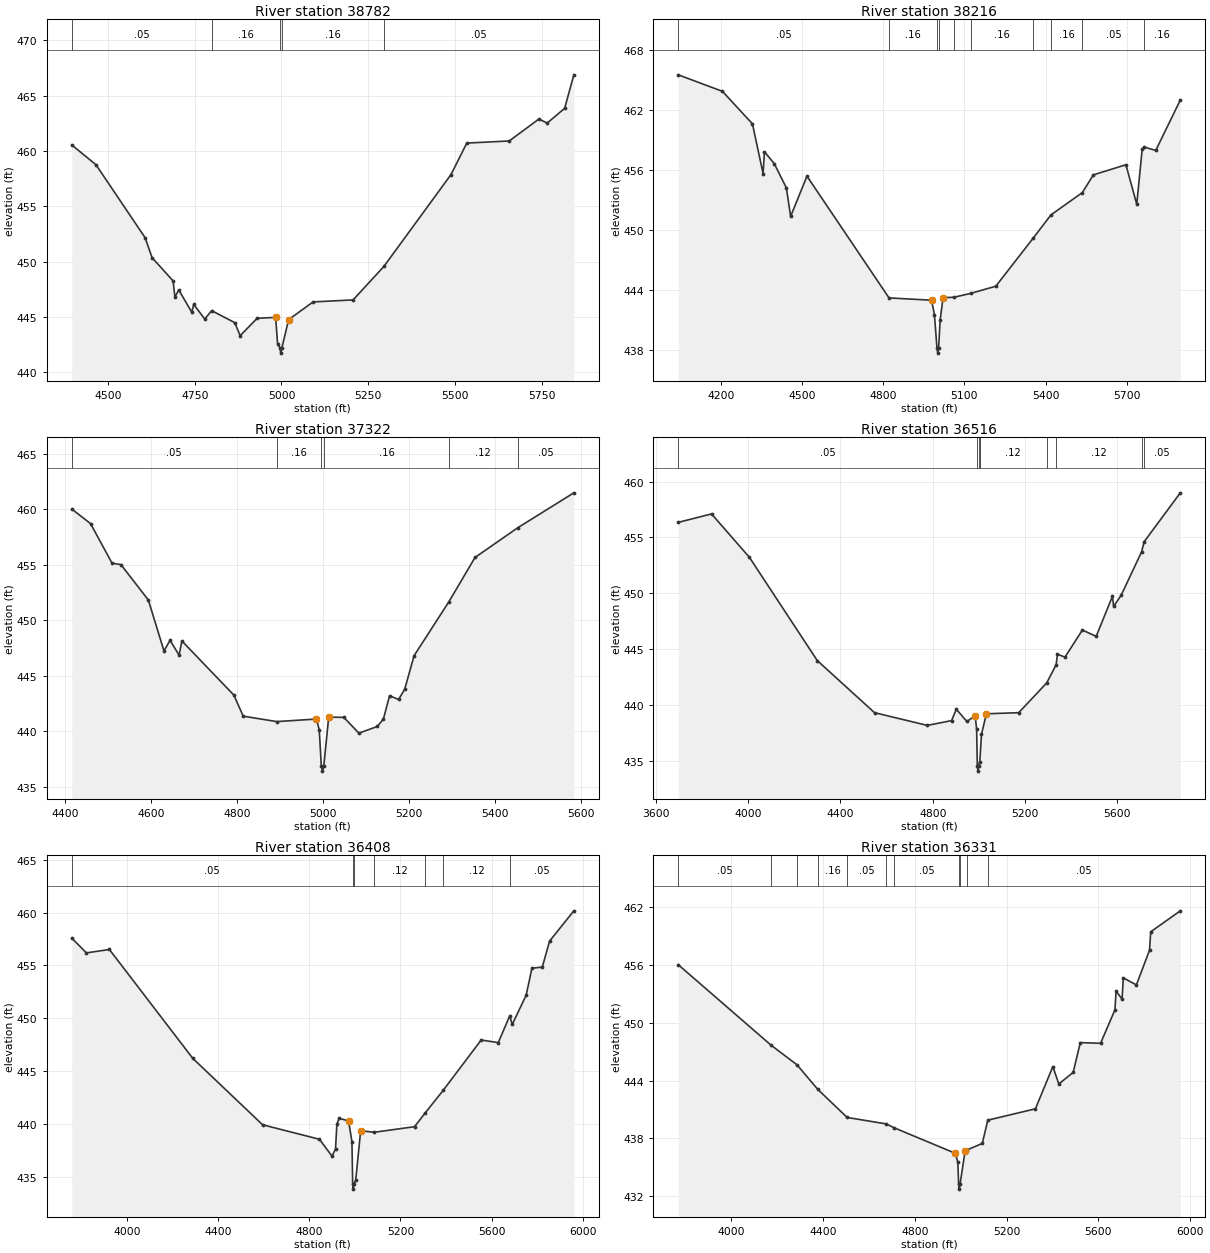
Type RM Length L Ch R = 1 ,38782   ,566,566,566
BEGIN DESCRIPTION:
MONTGOMERY CREEK 56.0
END DESCRIPTION:
XS GIS Cut Line= 5
      3487492.97     10511890.33      3487787.26       10511932.
      3488232.57     10511676.79      3488287.26     10511234.08
      3488307.95     10511045.26
#Sta/Elev= 30
  4395.8  460.54  4465.6  458.75    4607  452.16  4627.2  450.35  4687.8  448.25
  4692.9  446.79  4704.1  447.43  4741.5  445.42  4747.2  446.13  4778.9   444.8
  4798.7  445.56  4865.2  444.48    4881   443.3  4929.9  444.87  4983.2  444.95
  4988.9  442.51  4995.3  442.22    4998  441.72  5001.3  442.22  5020.6  444.75
  5091.1  446.35  5206.3  446.53  5295.1  449.56  5488.3  457.86  5533.9  460.71
  5656.1   460.9  5741.5  462.88  5765.5  462.52  5815.8  463.85  5842.3  466.88
#Mann= 5 ,-1 , 0
  4395.8     .05       0  4798.7     .16       0  4995.3     .07       0
  5001.3     .16       0  5295.1     .05       0
Bank Sta=4983.2,5020.6
XS Rating Curve= 0 ,0
Exp/Cntr=0.3,0.1

Type RM Length L Ch R = 1 ,38216   ,894,894,894
BEGIN DESCRIPTION:
MONTGOMERY CREEK 55.0
END DESCRIPTION:
XS GIS Cut Line= 5
      3487280.05     10512335.59      3488086.53     10512235.95
       3488313.1     10512152.61      3488893.82     10512181.26
      3489112.74     10512195.01
#Sta/Elev= 30
  4043.1  465.54  4206.4  463.89  4317.2  460.64  4356.6  455.67  4361.6  457.85
  4397.8  456.67  4442.7  454.23  4458.3  451.39  4518.7  455.41  4821.8  443.24
  4978.9  443.01  4989.5  441.58    4999  438.22  5001.8  437.72    5005  438.22
  5010.8  441.07  5021.5  443.27  5060.8   443.3  5124.8   443.7  5216.3  444.41
  5355.4  449.25  5420.1  451.54  5536.1  453.77  5576.7  455.54  5696.9  456.55
    5737   452.6    5757   458.1  5764.7  458.32  5807.1  457.98  5897.9  463.02
#Mann= 10 ,-1 , 0
  4043.1     .05       0  4821.8     .16       0    4999     .07       0
    5005     .16       0  5060.8     .12       0  5124.8     .16       0
  5355.4     .12       0  5420.1     .16       0  5536.1     .05       0
  5764.7     .16       0
Bank Sta=4978.9,5021.5
XS Rating Curve= 0 ,0
Exp/Cntr=0.3,0.1

Type RM Length L Ch R = 1 ,37322   ,806,806,806
BEGIN DESCRIPTION:
MONTGOMERY CREEK 54.0
END DESCRIPTION:
XS GIS Cut Line= 2
      3487999.13     10513190.23      3488880.88     10512426.52
#Sta/Elev= 30
    4416     460  4459.6  458.69  4509.5  455.13  4530.4  454.99    4594   451.8
  4630.2  447.22  4644.4  448.18  4665.3  446.84  4671.9  448.12  4792.5  443.25
  4814.4  441.35  4892.2  440.86  4984.4  441.09    4991  440.13  4995.7   436.9
  4998.4   436.4  5001.7   436.9  5012.9  441.26    5048  441.24  5083.1  439.82
  5125.9  440.42  5140.1   441.1  5154.4  443.19  5175.3  442.85  5189.5  443.77
  5211.4   446.8  5292.5  451.67  5352.9  455.64    5452  458.31  5582.5  461.46
#Mann= 6 ,-1 , 0
    4416     .05       0  4892.2     .16       0  4995.7     .07       0
  5001.7     .16       0  5292.5     .12       0    5452     .05       0
Bank Sta=4984.4,5012.9
XS Rating Curve= 0 ,0
Exp/Cntr=0.3,0.1

Type RM Length L Ch R = 1 ,36516   ,108,108,108
BEGIN DESCRIPTION:
MONTGOMERY CREEK 52.1
END DESCRIPTION:
XS GIS Cut Line= 5
      3488085.91     10514507.63      3488572.05     10513851.34
      3488628.48     10513487.62      3488743.06     10513307.94
      3488974.29     10512564.89
#Sta/Elev= 30
    3697  456.35  3841.3  457.11  4005.4  453.22  4299.7  443.96  4547.8  439.29
  4776.5  438.15  4881.8  438.58  4902.3   439.6    4948   438.5  4983.8  439.01
  4990.3  437.82  4993.2  434.55  4995.9  434.05  4999.2  434.55  5004.1   434.9
  5011.4  437.35  5032.6  439.19  5172.7  439.29  5294.1  441.96    5335  443.59
  5340.6  444.53  5373.2  444.27  5448.7   446.7  5508.5  446.13  5578.9  449.72
  5584.1  448.82  5616.6  449.81  5705.5  453.72  5716.5  454.62  5873.1     459
#Mann= 8 ,-1 , 0
    3697     .05       0  4993.2     .04       0  4999.2     .05       0
  5004.1     .12       0  5294.1     .16       0    5335     .12       0
  5705.5     .16       0  5716.5     .05       0
Bank Sta=4983.8,5032.6
XS Rating Curve= 0 ,0
Exp/Cntr=0.3,0.1

Type RM Length L Ch R = 1 ,36408   ,77,77,77
BEGIN DESCRIPTION:
MONTGOMERY CREEK 52.0
END DESCRIPTION:
XS GIS Cut Line= 4
      3488118.86      10514557.2      3488609.31     10513858.43
      3488881.01     10512951.53      3489019.02     10512571.34
#Sta/Elev= 30
  3756.5  457.58  3820.7  456.18  3921.8   456.5  4287.8   446.2  4594.6  439.91
  4844.1  438.54  4899.2  436.95  4914.8  437.61  4920.7  439.96  4930.5  440.52
  4972.2  440.28  4986.9   438.3  4990.1  434.32  4992.9  433.82  4996.1  434.32
  5003.5  434.67  5025.2  439.35    5084   439.2  5261.9  439.73  5309.6  441.06
  5387.6  443.17  5554.3  447.93  5629.7  447.69  5679.8  450.22  5690.9  449.41
  5752.1  452.18  5777.4  454.73  5822.8  454.83  5854.7  457.29  5961.4  460.16
#Mann= 7 ,-1 , 0
  3756.5     .05       0  4990.1     .04       0  4996.1     .05       0
    5084     .12       0  5309.6     .05       0  5387.6     .12       0
  5679.8     .05       0
Bank Sta=4972.2,5025.2
XS Rating Curve= 0 ,0
Exp/Cntr=0.3,0.1

Type RM Length L Ch R = 1 ,36331   ,44,44,44
BEGIN DESCRIPTION:
MONTGOMERY CREEK 51.0
END DESCRIPTION:
XS GIS Cut Line= 4
       3488261.2     10514623.42      3488615.38     10514037.46
      3488834.13     10513383.82      3489099.11     10512614.86
#Sta/Elev= 30
  3769.6  456.04  4174.7  447.66  4286.7  445.64  4377.9  443.07  4505.6  440.16
  4675.9  439.49  4709.9  439.09  4977.1  436.43  4987.7   435.5  4991.2  433.21
  4993.9  432.71  4997.2  433.21  5019.3  436.67  5029.5   436.8  5094.2  437.46
  5118.3  439.88  5325.7  441.06  5401.6  445.45  5427.5  443.64    5490  444.84
  5521.2  447.94  5609.5  447.87    5672  451.34  5677.2  453.29  5703.2  452.47
  5708.5  454.67  5765.6  453.94  5822.7  457.54    5828  459.46  5956.9  461.64
#Mann= 11 ,-1 , 0
  3769.6     .05       0  4174.7     .16       0  4286.7     .05       0
  4377.9     .16       0  4505.6     .05       0  4675.9     .16       0
  4709.9     .05       0  4991.2     .04       0  4997.2     .05       0
  5029.5     .16       0  5118.3     .05       0
Bank Sta=4977.1,5019.3
XS Rating Curve= 0 ,0
Exp/Cntr=0.3,0.1

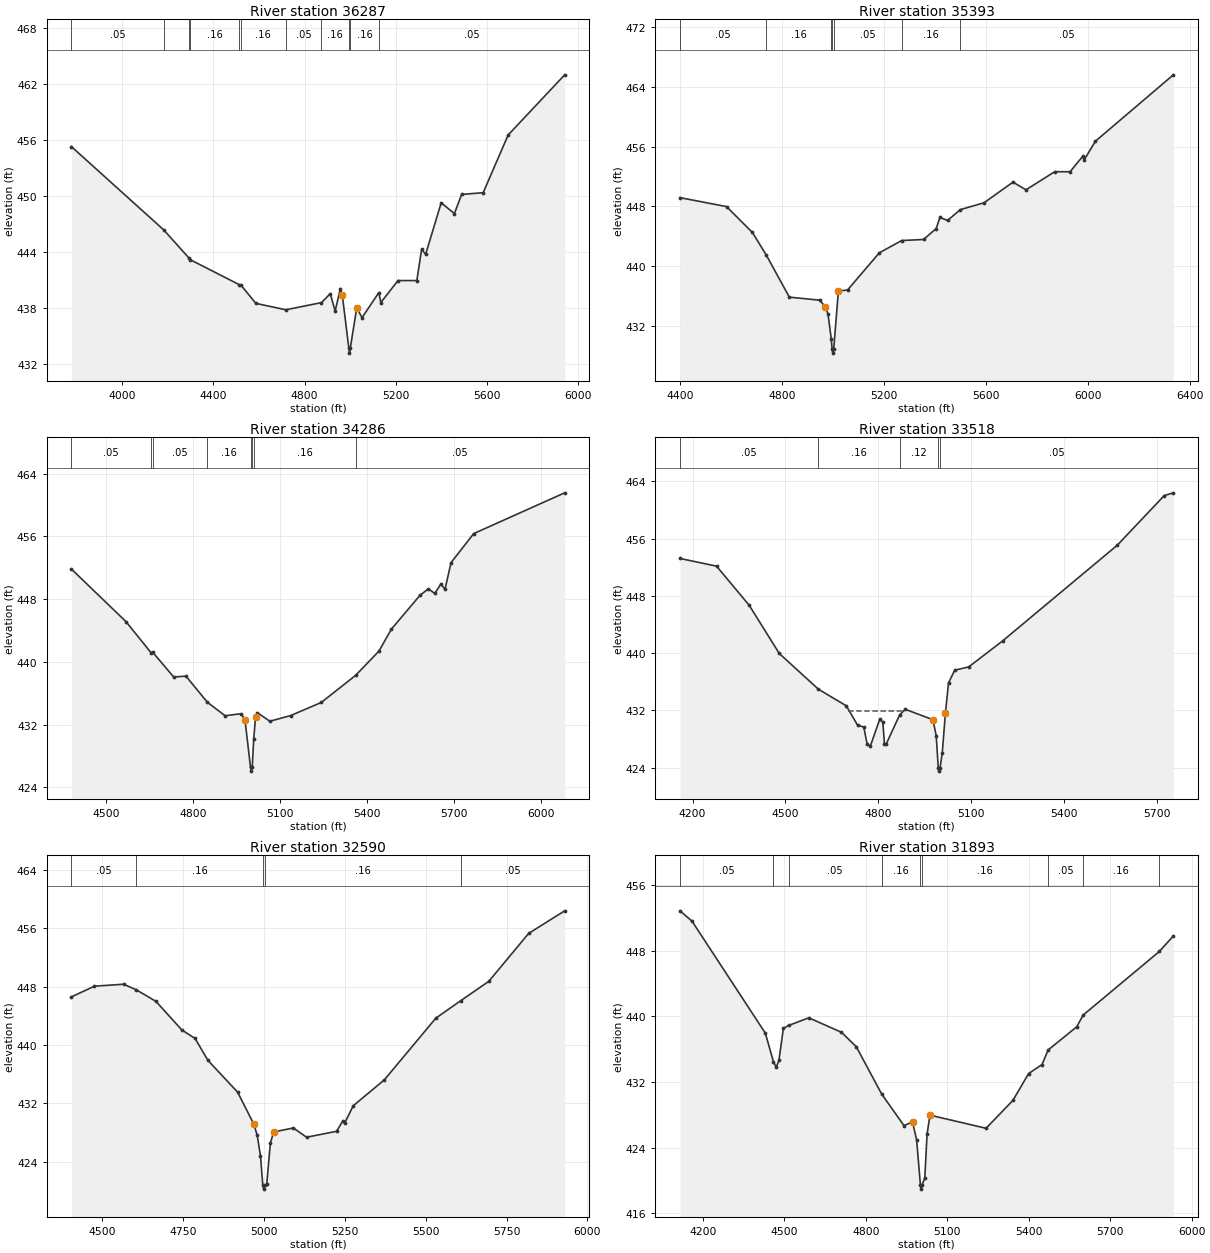
Type RM Length L Ch R = 1 ,36287   ,894,894,894
BEGIN DESCRIPTION:
MONTGOMERY CREEK 51.1
END DESCRIPTION:
XS GIS Cut Line= 3
      3488309.83      10514628.6      3488670.07     10514012.29
       3489130.1     10512636.54
#Sta/Elev= 30
  3776.3  455.28  4181.9  446.35  4292.9  443.33  4297.5  443.17  4513.1  440.49
  4519.8  440.46  4585.8  438.49  4717.3   437.8  4873.7  438.57  4912.6  439.53
  4933.7  437.66  4956.9  440.08  4965.3  439.34    4994  433.66  4996.7  433.16
    5000  433.66  5028.6  438.01  5051.7  436.96  5125.7  439.65  5134.1  438.57
  5209.6  440.93  5292.2  440.93  5313.3  444.29  5330.7  443.73  5399.1  449.26
    5457   448.1  5488.6  450.15  5583.3  450.34  5692.9  456.52  5940.8  462.96
#Mann= 11 ,-1 , 0
  3776.3     .05       0  4181.9     .16       0  4292.9     .05       0
  4297.5     .16       0  4513.1     .05       0  4519.8     .16       0
  4717.3     .05       0  4873.7     .16       0    4994     .07       0
    5000     .16       0  5125.7     .05       0
Bank Sta=4965.3,5028.6
XS Rating Curve= 0 ,0
Exp/Cntr=0.3,0.1

Type RM Length L Ch R = 1 ,35393   ,1107,1107,1107
BEGIN DESCRIPTION:
MONTGOMERY CREEK 49.0
END DESCRIPTION:
XS GIS Cut Line= 4
      3488469.32     10514431.28      3488917.26     10514139.59
      3489162.05     10514092.72      3490287.04     10513853.14
#Sta/Elev= 30
  4401.2  449.15  4583.5  447.95  4684.8  444.49  4739.3  441.46  4829.7  435.81
  4948.6   435.4  4971.2  434.49  4981.4  433.53    4994  430.25  4997.6   428.8
  5000.4   428.3  5003.6   428.8  5022.1  436.64  5057.8  436.76  5182.5  441.75
  5270.4   443.4    5356  443.54  5405.5  445.01  5420.2   446.5    5450  446.09
    5500  447.54  5593.6  448.47  5706.5  451.23  5757.6   450.2  5870.1  452.63
  5930.3  452.62  5979.9   454.7    5985  454.16  6029.4  456.71  6335.2  465.62
#Mann= 7 ,-1 , 0
  4401.2     .05       0  4739.3     .16       0    4994     .05       0
  4997.6    .035       0  5003.6     .05       0  5270.4     .16       0
    5500     .05       0
Bank Sta=4971.2,5022.1
XS Rating Curve= 0 ,0
Exp/Cntr=0.3,0.1

Type RM Length L Ch R = 1 ,34286   ,768,768,768
BEGIN DESCRIPTION:
MONTGOMERY CREEK 48.0
END DESCRIPTION:
XS GIS Cut Line= 3
      3488638.61     10515087.51      3489141.22     10514915.63
      3490031.85     10514160.42
#Sta/Elev= 30
  4381.3  451.83  4569.7  445.11    4656  441.15  4661.2  441.23  4733.8  438.06
    4776  438.17  4849.8  434.84  4910.9  433.12  4966.1  433.38  4979.3   432.6
  4998.3  426.56    5001  426.06  5004.3  426.56  5009.4  430.17  5015.6  432.92
  5022.1  433.51    5065  432.42  5136.4  433.14  5241.8  434.81  5360.1  438.26
  5440.6  441.36  5483.5  444.16  5582.3  448.49  5610.9   449.3  5632.9  448.71
  5653.8  449.91  5668.1  449.25  5688.9  452.64  5766.9  456.34  6080.2  461.54
#Mann= 8 ,-1 , 0
  4381.3     .05       0    4656     .16       0  4661.2     .05       0
  4849.8     .16       0  4998.3     .07       0  5004.3     .16       0
  5009.4     .16       0  5360.1     .05       0
Bank Sta=4979.3,5015.6
XS Rating Curve= 0 ,0
Exp/Cntr=0.3,0.1

Type RM Length L Ch R = 1 ,33518   ,928,928,928
BEGIN DESCRIPTION:
MONTGOMERY CREEK 46.0
END DESCRIPTION:
XS GIS Cut Line= 4
      3488815.69      10515452.1      3489604.76     10515324.49
      3489859.97     10515347.93      3490391.26     10515267.19
#Sta/Elev= 30
  4159.5  453.23  4277.4  452.16  4382.7   446.7    4480  439.95  4606.4  434.95
  4696.3  432.64  4733.3   429.9  4752.9  429.67  4763.7  427.28  4773.8  426.97
  4804.2  430.72  4814.3  430.38  4819.7  427.31  4824.8  427.24  4868.4  431.33
  4886.5  432.15  4976.2  430.69  4986.8  428.45  4993.3     424  4996.1   423.5
  4999.3     424  5006.4  426.09  5016.4  431.57  5026.5  435.83  5046.5  437.61
  5091.7  438.07  5201.6  441.72  5571.3  455.08    5723  462.02  5752.5  462.41
#Mann= 5 ,-1 , 0
  4159.5     .05       0  4606.4     .16       0  4868.4     .12       0
  4993.3    .035       0  4999.3     .05       0
#XS Ineff= 1 ,-1
 4703.21 4880.41  431.88
Permanent Ineff=
       F
Bank Sta=4976.2,5016.4
XS Rating Curve= 0 ,0
Exp/Cntr=0.3,0.1

Type RM Length L Ch R = 1 ,32590   ,697,697,697
BEGIN DESCRIPTION:
MONTGOMERY CREEK 44.0
END DESCRIPTION:
XS GIS Cut Line= 4
      3488940.72     10516027.61       3489315.7      10516017.2
      3489654.24      10515957.3      3490435.53     10515759.37
#Sta/Elev= 30
  4404.8  446.59  4476.2  448.06  4566.3  448.33  4605.9  447.56  4666.3  445.98
  4746.3  442.06  4787.3  440.89  4827.1  437.88  4918.5  433.54  4969.2  429.11
  4979.4   427.6  4989.5  424.74  4996.7  420.72  4999.4  420.22  5002.7  420.72
  5008.7  420.88    5020  426.52  5030.2  428.06  5091.1  428.61  5131.8  427.34
  5224.7  428.15  5244.4  429.62  5249.5  429.27  5276.3  431.66  5372.5  435.22
  5531.3  443.67  5608.1  446.06  5695.3  448.73  5818.3   455.3  5929.7   458.4
#Mann= 5 ,-1 , 0
  4404.8     .05       0  4605.9     .16       0  4996.7     .07       0
  5002.7     .16       0  5608.1     .05       0
Bank Sta=4969.2,5030.2
XS Rating Curve= 0 ,0
Exp/Cntr=0.3,0.1

Type RM Length L Ch R = 1 ,31893   ,887,887,887
BEGIN DESCRIPTION:
MONTGOMERY CREEK 42.0
END DESCRIPTION:
XS GIS Cut Line= 4
      3488628.17     10516610.95      3489461.53      10516579.7
      3489569.03     10516538.52      3490242.11     10515991.64
#Sta/Elev= 30
  4116.3  452.84  4160.3  451.59  4430.5  437.94  4460.4  434.44  4470.5   433.8
  4480.5  434.62  4496.8  438.52  4516.1  438.88  4590.6  439.81  4710.6  438.05
  4765.3  436.29  4858.7  430.53  4940.8  426.69  4972.3  427.14  4987.5  424.93
  5001.4  419.45  5004.2  418.95  5007.4  419.45  5017.6  420.33  5025.8  425.62
  5036.5  427.96    5243  426.36  5342.1  429.76  5399.6  433.02  5449.2  434.12
  5471.5  435.89    5577  438.72  5600.6  440.15    5881  447.89  5932.6  449.78
#Mann= 9 ,-1 , 0
  4116.3     .05       0  4460.4     .16       0  4516.1     .05       0
  4858.7     .16       0  5001.4     .07       0  5007.4     .16       0
  5471.5     .05       0  5600.6     .16       0    5881     .05       0
Bank Sta=4972.3,5036.5
XS Rating Curve= 0 ,0
Exp/Cntr=0.3,0.1

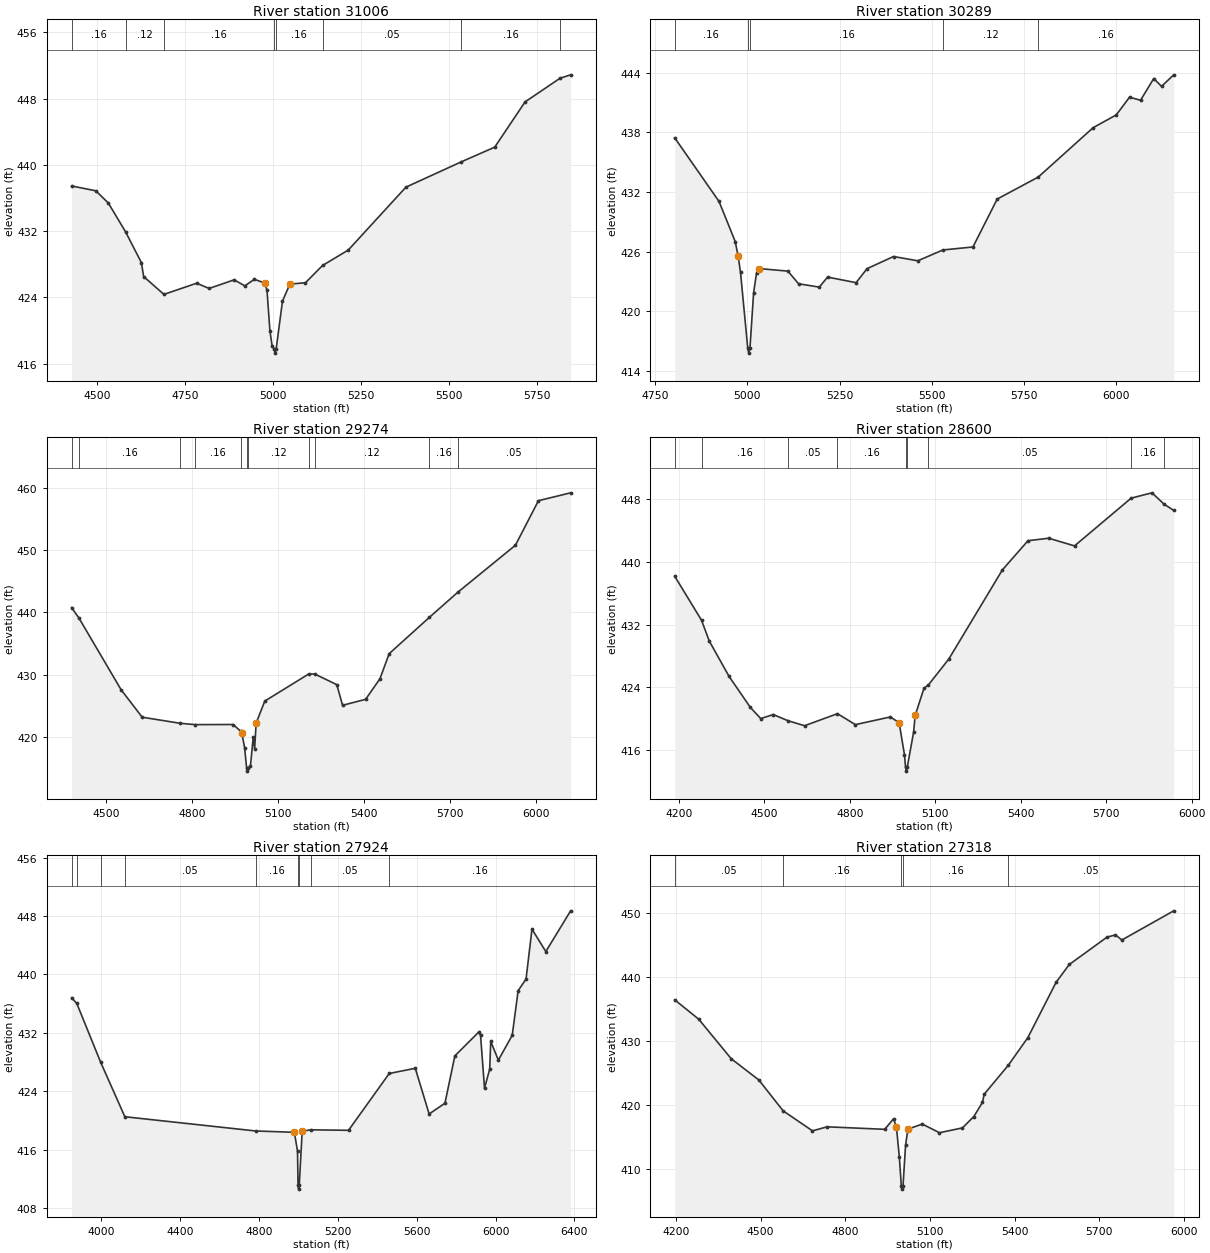
Type RM Length L Ch R = 1 ,31006   ,717,717,717
BEGIN DESCRIPTION:
MONTGOMERY CREEK 40.0
END DESCRIPTION:
XS GIS Cut Line= 3
      3489526.64     10517202.09      3489810.49     10516816.68
       3490573.5     10516272.41
#Sta/Elev= 30
  4428.4  437.46    4497  436.88  4532.4  435.41  4581.3  431.94  4626.5   428.2
  4632.7  426.53  4690.3  424.37  4783.1  425.72  4818.6  425.09  4889.6  426.13
  4919.8   425.4  4946.8  426.19  4976.3  425.75  4982.7  424.92  4991.1  419.95
  4997.2  418.19  5002.8  417.78  5005.6  417.28  5008.8  417.78  5026.7  423.56
  5047.6  425.61  5091.9  425.78  5140.4  427.86  5213.5  429.73    5377  437.32
  5534.3  440.38    5629  442.15    5715  447.61  5814.3  450.47  5844.3  450.88
#Mann= 8 ,-1 , 0
  4428.4     .16       0  4581.3     .12       0  4690.3     .16       0
  5002.8     .07       0  5008.8     .16       0  5140.4     .05       0
  5534.3     .16       0  5814.3     .05       0
Bank Sta=4976.3,5047.6
XS Rating Curve= 0 ,0
Exp/Cntr=0.3,0.1

Type RM Length L Ch R = 1 ,30289   ,1015,1015,1015
BEGIN DESCRIPTION:
MONTGOMERY CREEK 39.0
END DESCRIPTION:
XS GIS Cut Line= 4
       3489935.5     10517423.44       3490063.1     10517368.76
      3490305.28     10517178.66      3491051.91     10516666.16
#Sta/Elev= 30
  4803.4  437.46  4923.5  431.06  4967.3  427.03  4975.4  425.54  4981.7  423.92
  5001.3   416.3    5004   415.8  5007.3   416.3  5017.2  421.87  5025.1  423.86
  5031.5  424.31  5110.1  424.05    5139  422.78  5195.2  422.44  5217.6  423.45
  5294.9  422.89  5324.7   424.3  5396.4  425.52  5462.1  425.09  5530.2  426.18
  5611.6  426.48  5677.3   431.3  5788.8  433.52  5937.2  438.48  6000.1  439.77
  6035.9  441.55  6065.7  441.24  6101.6  443.43  6122.6  442.64  6155.7   443.8
#Mann= 5 ,-1 , 0
  4803.4     .16       0  5001.3     .07       0  5007.3     .16       0
  5530.2     .12       0  5788.8     .16       0
Bank Sta=4975.4,5031.5
XS Rating Curve= 0 ,0
Exp/Cntr=0.3,0.1

Type RM Length L Ch R = 1 ,29274   ,674,674,674
BEGIN DESCRIPTION:
MONTGOMERY CREEK 38.0
END DESCRIPTION:
XS GIS Cut Line= 3
      3489839.14     10517462.52      3490094.35     10517814.07
      3491393.81     10517702.09
#Sta/Elev= 30
    4381  440.75  4406.4  439.09  4553.4  427.58  4626.9  423.17  4758.7   422.2
  4810.4  421.98  4943.7     422  4970.2  420.92  4973.8  420.67  4983.8  418.27
  4990.8  415.02  4993.6  414.52  4996.8  415.02  5003.9  415.27  5013.7  419.93
  5018.7  418.12  5023.9  422.22  5054.1  425.76  5207.7  430.12  5228.6  430.09
    5305  428.39  5325.1  425.08  5405.4  426.04  5455.5  429.36  5487.5  433.37
    5627  439.17  5726.6  443.22  5927.3  450.76  6007.6  457.91  6119.7  459.17
#Mann= 11 ,-1 , 0
    4381     .12       0  4406.4     .16       0  4758.7     .12       0
  4810.4     .16       0  4970.2     .12       0  4990.8     .07       0
  4996.8     .12       0  5207.7     .16       0  5228.6     .12       0
    5627     .16       0  5726.6     .05       0
Bank Sta=4973.8,5023.9
XS Rating Curve= 0 ,0
Exp/Cntr=0.3,0.1

Type RM Length L Ch R = 1 ,28600   ,676,676,676
BEGIN DESCRIPTION:
MONTGOMERY CREEK 37.0
END DESCRIPTION:
XS GIS Cut Line= 4
      3489716.71     10517516.54      3490008.41     10518160.43
      3490336.53     10518277.61      3491028.14     10518199.61
#Sta/Elev= 30
  4185.8  438.18  4279.8  432.57  4307.3   429.9  4376.6   425.4  4451.4  421.44
  4487.8  420.02  4531.7  420.54  4583.3  419.75  4641.5  419.11    4757  420.65
  4819.7  419.25  4942.6  420.23  4973.4   419.5  4992.2  415.39  4995.9  413.82
  4998.7  413.32  5001.9  413.82    5024  418.25  5029.7  420.43  5060.5  423.88
    5076  424.31  5147.6  427.61  5335.6  438.98  5425.5  442.71  5498.3  443.03
  5588.9  442.05  5787.6  448.14  5860.6  448.82  5903.8  447.36  5937.1  446.58
#Mann= 9 ,-1 , 0
  4185.8     .12       0  4279.8     .16       0  4583.3     .05       0
    4757     .16       0  4995.9     .07       0  5001.9     .16       0
    5076     .05       0  5787.6     .16       0  5903.8     .12       0
Bank Sta=4973.4,5029.7
XS Rating Curve= 0 ,0
Exp/Cntr=0.3,0.1

Type RM Length L Ch R = 1 ,27924   ,606,606,606
BEGIN DESCRIPTION:
MONTGOMERY CREEK 36.0
END DESCRIPTION:
XS GIS Cut Line= 4
      3489612.57     10517489.38      3489793.13      10518517.2
      3490129.94     10518659.56      3491247.52     10518576.26
#Sta/Elev= 30
  3850.8  436.79  3876.9  436.03    3998  427.96  4120.7  420.49  4783.9  418.54
  4980.1  418.36    4996  415.78  4998.8  411.07  5001.6  410.57  5004.8  411.07
  5019.7   418.5  5062.7   418.7  5254.7  418.63  5461.1  426.42  5593.1  427.13
  5663.3  420.87  5743.5  422.34  5793.7  428.83    5914  432.07    5924  431.67
  5944.1   424.4  5970.5  427.03  5975.6  430.81  6014.3  428.25  6084.5  431.64
  6114.6  437.77  6154.7  439.36  6184.7   446.2  6254.9  443.13  6380.7  448.71
#Mann= 9 ,-1 , 0
  3850.8     .16       0  3876.9     .12       0    3998     .16       0
  4120.7     .05       0  4783.9     .16       0  4998.8     .07       0
  5004.8     .16       0  5062.7     .05       0  5461.1     .16       0
Bank Sta=4980.1,5019.7
XS Rating Curve= 0 ,0
Exp/Cntr=0.3,0.1

Type RM Length L Ch R = 1 ,27318   ,948,948,948
BEGIN DESCRIPTION:
MONTGOMERY CREEK 34.0
END DESCRIPTION:
XS GIS Cut Line= 4
       3489214.8     10519369.59      3489902.29     10519057.09
      3490266.87     10518991.64      3490908.12     10518956.46
#Sta/Elev= 30
  4195.5  436.48  4280.5  433.46  4395.8  427.28  4493.6  423.96  4579.7  419.14
  4683.6  416.02  4735.3  416.65  4939.5  416.26  4970.8  417.91    4981  416.59
  4991.1  411.98  4998.3  407.42    5001  406.92  5004.3  407.42  5013.2  413.74
  5021.6  416.29  5072.4  417.08  5133.4  415.73  5214.6  416.48  5255.3  418.26
  5285.8  420.47  5291.8  421.74  5377.5  426.28  5446.5  430.58  5546.7  439.23
  5593.3     442  5726.9  446.27    5757  446.62  5779.7  445.83  5963.3  450.38
#Mann= 5 ,-1 , 0
  4195.5     .05       0  4579.7     .16       0  4998.3     .07       0
  5004.3     .16       0  5377.5     .05       0
Bank Sta=4981,5021.6
XS Rating Curve= 0 ,0
Exp/Cntr=0.3,0.1

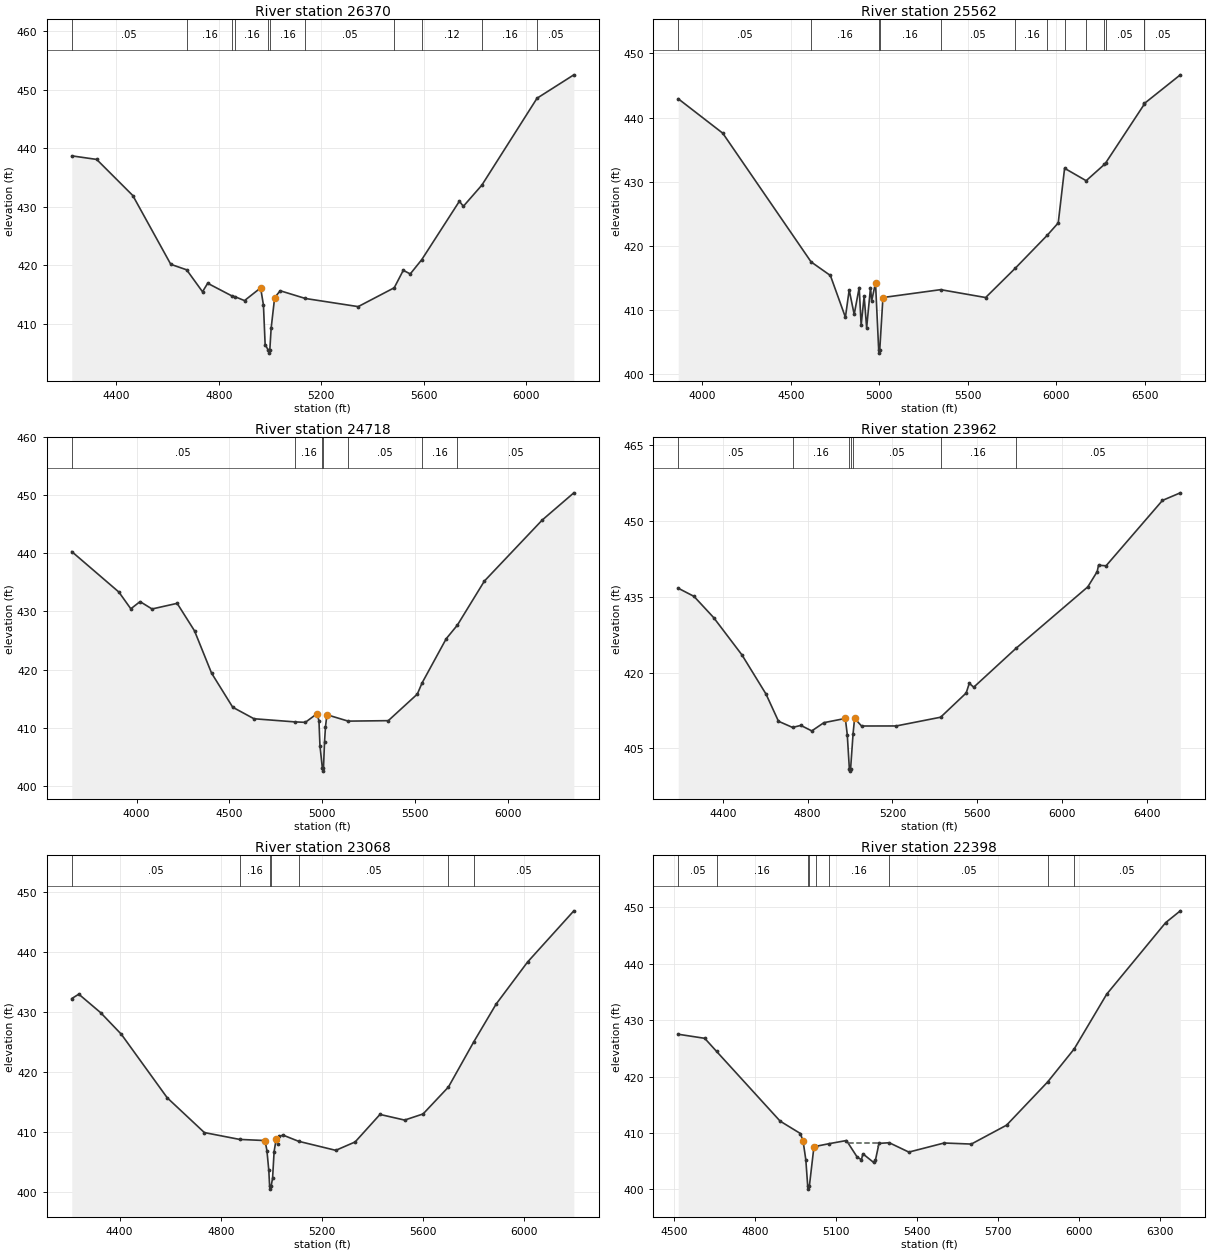
Type RM Length L Ch R = 1 ,26370   ,808,808,808
BEGIN DESCRIPTION:
MONTGOMERY CREEK 32.0
END DESCRIPTION:
XS GIS Cut Line= 4
      3489155.75     10519883.48      3489822.01     10519802.56
       3490013.4     10519886.95      3490943.95     10519341.82
#Sta/Elev= 30
  4226.6  438.69  4323.7  438.08  4464.7  431.91  4612.9  420.15  4674.8  419.21
  4736.7  415.46  4756.8  416.91    4853  414.71  4862.5  414.63  4900.5  413.95
  4963.4  416.12  4974.4  413.19    4981  406.44  4993.2  405.47    4996  404.97
  4999.2  405.47  5004.4  409.21  5018.1  414.47  5039.9  415.63  5138.1  414.31
    5344  412.92  5484.6  416.14  5519.9  419.12  5547.2  418.51  5591.9  420.94
  5738.8  430.93  5754.4  430.07  5826.6  433.69  6041.8  448.54  6185.4  452.54
#Mann= 11 ,-1 , 0
  4226.6     .05       0  4674.8     .16       0    4853     .12       0
  4862.5     .16       0  4993.2     .07       0  4999.2     .16       0
  5138.1     .05       0  5484.6     .16       0  5591.9     .12       0
  5826.6     .16       0  6041.8     .05       0
Bank Sta=4963.4,5018.1
XS Rating Curve= 0 ,0
Exp/Cntr=0.3,0.1

Type RM Length L Ch R = 1 ,25562   ,844,844,844
BEGIN DESCRIPTION:
MONTGOMERY CREEK 30.0
END DESCRIPTION:
XS GIS Cut Line= 5
      3489048.09     10521293.24      3489791.18     10520570.98
      3489916.18     10520432.09      3489985.43     10520271.89
      3491304.26     10519696.33
#Sta/Elev= 30
  3863.7  442.93  4115.2  437.56  4614.4  417.46  4723.3  415.34  4808.2  408.82
  4829.5  413.08  4857.8  409.27  4886.1  413.46  4897.1  407.57    4914  412.11
  4928.2  407.18  4949.9  413.44  4956.6  411.39  4978.3   414.2  4996.2  403.72
    4999  403.22  5002.2  403.72  5020.2   411.9  5346.3  413.13  5600.4   411.9
  5769.1  416.51  5948.8  421.63  6010.6  423.55  6046.5  432.08  6168.4  430.14
  6271.3  432.68  6278.2   432.9  6496.2  442.06  6497.8  442.21  6700.3  446.67
#Mann= 13 ,-1 , 0
  3863.7     .05       0  4614.4     .16       0  4996.2     .07       0
  5002.2     .16       0  5346.3     .05       0  5769.1     .16       0
  5948.8     .12       0  6046.5     .16       0  6168.4     .05       0
  6271.3     .12       0  6278.2     .05       0  6496.2     .16       0
  6497.8     .05       0
Bank Sta=4978.3,5020.2
XS Rating Curve= 0 ,0
Exp/Cntr=0.3,0.1

Type RM Length L Ch R = 1 ,24718   ,756,756,756
BEGIN DESCRIPTION:
MONTGOMERY CREEK 28.0
END DESCRIPTION:
XS GIS Cut Line= 4
      3489443.93     10521848.79      3490159.23     10520914.73
      3490545.12     10520763.33      3491292.12     10519941.63
#Sta/Elev= 30
  3651.5  440.31  3904.8  433.35  3969.2  430.46    4019   431.7  4083.4  430.43
  4218.5   431.4  4311.9  426.67  4403.6  419.39  4517.6  413.51  4631.9  411.53
  4850.8  410.99  4908.3  410.91  4970.7  412.39  4981.5  411.21  4986.9  406.89
  4999.9  403.01  5002.7  402.51  5005.9  403.01  5011.4  407.49  5016.7  410.16
  5024.4  412.22  5138.5  411.12  5354.6   411.2  5510.7  415.77  5536.3  417.69
  5666.1   425.3  5726.3  427.65  5871.5  435.23    6183  445.75    6353  450.43
#Mann= 7 ,-1 , 0
  3651.5     .05       0  4850.8     .16       0  4999.9     .07       0
  5005.9     .16       0  5138.5     .05       0  5536.3     .16       0
  5726.3     .05       0
Bank Sta=4970.7,5024.4
XS Rating Curve= 0 ,0
Exp/Cntr=0.3,0.1

Type RM Length L Ch R = 1 ,23962   ,894,894,894
BEGIN DESCRIPTION:
MONTGOMERY CREEK 26.0
END DESCRIPTION:
XS GIS Cut Line= 6
      3490555.07     10521973.75       3490725.2     10521272.37
      3490829.37     10521036.26      3491548.12      10520018.9
      3491558.54     10520015.43      3491654.96     10519925.89
#Sta/Elev= 30
  4189.9   436.7  4264.1  435.09  4356.7   430.9  4490.4   423.5  4603.7  415.77
  4662.7  410.37    4729  409.15  4768.3  409.55  4819.8  408.46  4876.8  410.09
    4978  410.93  4987.1  407.74  4996.9     401  4999.6   400.5  5002.9     401
  5014.5   407.9  5021.7  410.94  5054.5  409.43    5218  409.44  5427.4  411.17
  5547.9  415.96  5562.7  417.88  5583.6  417.11  5782.6  424.79  6121.6  436.97
    6166     440  6172.1  441.25  6207.8  441.14  6473.8  454.08  6557.9  455.58
#Mann= 7 ,-1 , 0
  4189.9     .05       0    4729     .16       0  4996.9     .07       0
  5002.9     .16       0  5014.5     .05       0  5427.4     .16       0
  5782.6     .05       0
Bank Sta=4978,5021.7
XS Rating Curve= 0 ,0
Exp/Cntr=0.3,0.1

Type RM Length L Ch R = 1 ,23068   ,670,670,670
BEGIN DESCRIPTION:
MONTGOMERY CREEK 25.0
END DESCRIPTION:
XS GIS Cut Line= 4
      3490930.08     10522227.19      3491214.79     10521560.56
      3491426.59     10521258.48      3491642.09     10520391.69
#Sta/Elev= 30
  4210.6  432.25  4238.4  432.98  4325.1  429.89  4406.8   426.3  4588.4  415.72
  4735.4  409.93  4874.9  408.79  4975.6   408.6    4983   406.9  4990.4  403.62
  4993.6  401.01  4996.3  400.51  4999.6  401.01  5005.3  402.32  5011.4  406.77
  5019.7  408.89  5026.2  408.02  5032.3  409.32  5047.1   409.5    5108  408.48
  5255.4  406.97  5332.1  408.37  5430.4  412.95  5527.9  412.01  5600.9  413.03
  5701.3  417.52  5801.4  425.03  5890.2  431.34  6014.2  438.32  6197.6  446.86
#Mann= 7 ,-1 , 0
  4210.6     .05       0  4874.9     .16       0  4993.6     .07       0
  4999.6     .16       0    5108     .05       0  5701.3      .1       0
  5801.4     .05       0
Bank Sta=4975.6,5019.7
XS Rating Curve= 0 ,0
Exp/Cntr=0.3,0.1

Type RM Length L Ch R = 1 ,22398   ,856,856,856
BEGIN DESCRIPTION:
MONTGOMERY CREEK 23.0
END DESCRIPTION:
XS GIS Cut Line= 4
       3491575.9     10522234.15      3491659.23     10521866.12
      3491634.93     10521536.26       3491742.1     10520391.67
#Sta/Elev= 30
  4516.2  427.49  4614.2  426.77  4658.3  424.44  4893.3   412.1  4968.2  409.91
  4978.3  408.52  4988.3  405.24  4995.3  400.56  4998.1  400.06  5001.3  400.56
  5018.4   407.6  5026.5  407.65  5072.3  408.09  5138.7  408.67  5178.8   405.7
  5194.2  405.28  5199.3  406.32    5239  404.79  5245.8  405.19  5259.1  408.16
  5296.8  408.28  5369.5  406.62  5500.1  408.23  5600.6  408.04  5731.1  411.39
  5883.2  419.05  5981.4   424.9  6101.7   434.6  6319.5  447.25  6373.9  449.35
#Mann= 9 ,-1 , 0
  4516.2     .05       0  4658.3     .16       0  4995.3     .07       0
  5001.3     .16       0  5026.5     .12       0  5072.3     .16       0
  5296.8     .05       0  5883.2      .1       0  5981.4     .05       0
#XS Ineff= 1 ,-1
 5144.56 5256.48  408.24
Permanent Ineff=
       F
Bank Sta=4978.3,5018.4
XS Rating Curve= 0 ,0
Exp/Cntr=0.3,0.1