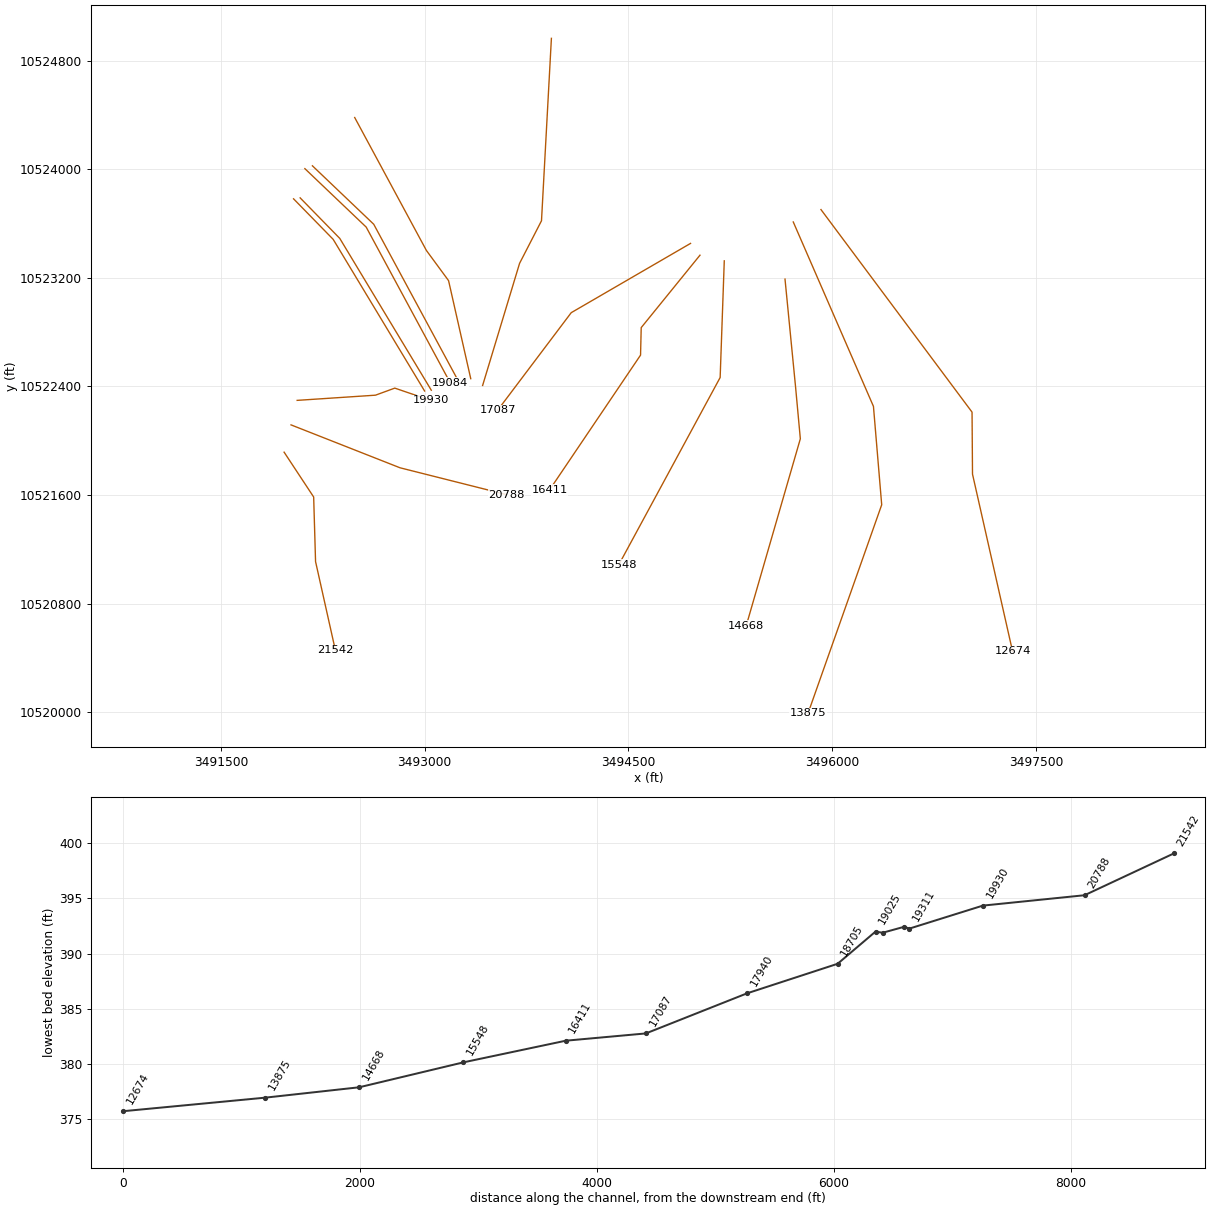
HEC-RAS study MONTGOMERY CREEK.prj: MONTGOMERY CREEK Base Level Engineering

--- MONTGOMERY CREEK.g01 (geometry) --- (continued)

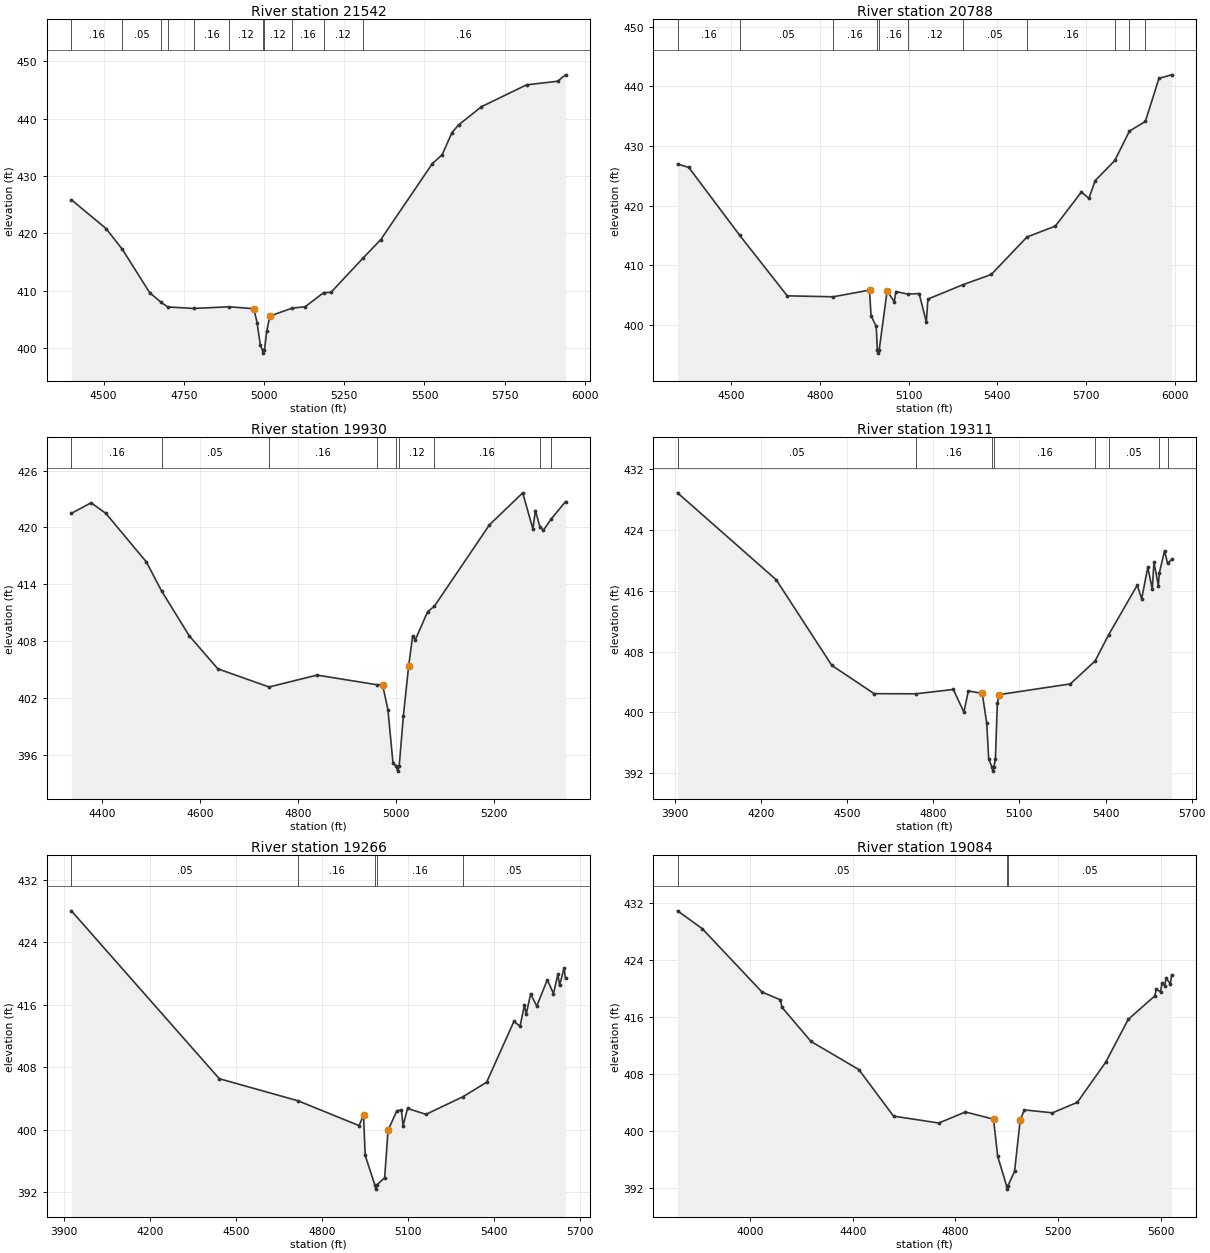
Type RM Length L Ch R = 1 ,21542   ,754,754,754
BEGIN DESCRIPTION:
MONTGOMERY CREEK 22.0
END DESCRIPTION:
XS GIS Cut Line= 4
      3491965.95     10521915.09      3492183.54     10521584.87
      3492197.43     10521109.18      3492343.23     10520456.52
#Sta/Elev= 30
  4399.5  425.85    4508   420.8  4558.7  417.17  4643.5  409.64  4678.8  407.96
  4699.9  407.14  4780.8  406.88  4891.6  407.17  4968.3  406.83  4978.3   404.4
  4988.3  400.52  4995.3  399.58    4998  399.08  5001.3  399.58  5008.3   402.9
  5018.3  405.56  5087.6  406.93  5128.3  407.18  5185.7  409.63  5208.4  409.68
  5308.4  415.66  5363.4  418.86  5524.5  432.15  5555.2  433.71  5585.6  437.56
  5606.5  438.91  5677.6  442.09  5818.1   445.9  5915.2  446.53  5939.6  447.65
#Mann= 11 ,-1 , 0
  4399.5     .16       0  4558.7     .05       0  4678.8     .12       0
  4699.9     .05       0  4780.8     .16       0  4891.6     .12       0
  4995.3     .07       0  5001.3     .12       0  5087.6     .16       0
  5185.7     .12       0  5308.4     .16       0
Bank Sta=4968.3,5018.3
XS Rating Curve= 0 ,0
Exp/Cntr=0.3,0.1

Type RM Length L Ch R = 1 ,20788   ,858,858,858
BEGIN DESCRIPTION:
MONTGOMERY CREEK 20.0
END DESCRIPTION:
XS GIS Cut Line= 3
      3492016.86     10522116.12      3492818.95     10521800.15
      3493603.69     10521602.23
#Sta/Elev= 30
  4318.6  426.97  4356.5  426.41    4529  415.02  4689.7  404.89  4844.9  404.73
  4967.9  405.85  4973.2  401.55  4990.6  399.78  4994.6  395.79  4997.4  395.29
  5000.6  395.79  5027.4  405.71  5051.8   403.9  5057.2  405.61  5097.4  405.18
  5135.7  405.27  5160.1  400.54  5165.5  404.35  5282.7  406.73  5379.9  408.47
  5500.4  414.74  5596.5  416.58  5684.9   422.3  5709.9  421.21  5731.1  424.18
  5797.8  427.58    5847  432.49  5900.8   434.1  5947.1  441.34    5990  441.92
#Mann= 11 ,-1 , 0
  4318.6     .16       0    4529     .05       0  4844.9     .16       0
  4994.6     .07       0  5000.6     .16       0  5097.4     .12       0
  5282.7     .05       0  5500.4     .16       0  5797.8     .05       0
    5847     .16       0  5900.8     .05       0
Bank Sta=4967.9,5027.4
XS Rating Curve= 0 ,0
Exp/Cntr=0.3,0.1

Type RM Length L Ch R = 1 ,19930   ,619,619,619
BEGIN DESCRIPTION:
MONTGOMERY CREEK 18.0
END DESCRIPTION:
XS GIS Cut Line= 4
        3492062.     10522296.67       3492638.4     10522334.87
      3492780.76     10522386.95      3493044.69     10522296.66
#Sta/Elev= 30
  4337.8  421.49    4378   422.6  4408.1  421.49  4490.9  416.37  4521.7  413.33
  4578.4  408.59  4636.7  405.12  4741.1  403.21    4839  404.46    4962  403.44
  4972.7  403.45  4983.7  400.82  4993.9  395.25  5000.6  394.85  5003.4  394.35
  5006.6  394.85  5015.2  400.18  5025.9  405.39  5034.1   408.6  5039.5  408.17
  5064.7  411.14  5078.3   411.7  5190.8  420.28  5258.7  423.65  5279.4  419.86
  5284.7  421.78  5293.9  420.04    5301  419.71  5316.6  420.88    5346  422.73
#Mann= 9 ,-1 , 0
  4337.8     .16       0  4521.7     .05       0  4741.1     .16       0
    4962     .12       0  5000.6     .07       0  5006.6     .12       0
  5078.3     .16       0  5293.9     .05       0  5316.6     .16       0
Bank Sta=4972.7,5025.9
XS Rating Curve= 0 ,0
Exp/Cntr=0.3,0.1

Type RM Length L Ch R = 1 ,19311   ,45,45,45
BEGIN DESCRIPTION:
MONTGOMERY CREEK 17.3
END DESCRIPTION:
XS GIS Cut Line= 3
       3492035.5     10523781.26      3492327.14     10523482.68
      3493000.15     10522365.63
#Sta/Elev= 30
  3908.9  428.87  4252.8  417.43  4446.3  406.18  4593.8  402.46  4738.9  402.44
  4869.6  403.01  4906.5  400.04    4922  402.82  4970.5  402.49  4986.1  398.57
  4992.9  393.91  5004.4  392.77  5007.2  392.27  5010.4  392.77  5016.3  393.88
    5023  401.17  5028.8  402.33  5277.3  403.74  5363.4  406.75    5411  410.22
  5510.4  416.72  5525.9  414.93  5547.2  419.08  5562.8  416.21  5568.6  419.77
  5584.1  416.63  5587.1  418.29  5605.5  421.24  5616.2  419.61  5630.4  420.11
#Mann= 8 ,-1 , 0
  3908.9     .05       0  4738.9     .16       0  5004.4     .07       0
  5010.4     .16       0  5363.4     .12       0    5411     .05       0
  5587.1     .16       0  5616.2     .05       0
Bank Sta=4970.5,5028.8
XS Rating Curve= 0 ,0
Exp/Cntr=0.3,0.1

Type RM Length L Ch R = 1 ,19266   ,182,182,182
BEGIN DESCRIPTION:
MONTGOMERY CREEK 17.0
END DESCRIPTION:
XS GIS Cut Line= 3
      3492084.09     10523788.23      3492375.76     10523489.62
      3493049.36     10522371.58
#Sta/Elev= 30
  3925.3  428.01  4440.9  406.55  4715.8  403.72  4928.3  400.55  4943.8  401.89
  4949.7  396.73  4983.5  392.93  4986.3  392.43  4989.5  392.93  5017.5   393.9
  5029.3  399.94  5060.3  402.47  5075.9  402.53  5081.7  400.53  5097.2  402.75
  5161.3  401.99    5291  404.25    5373   406.1  5468.1  413.87  5489.5  413.26
    5505  415.98  5510.8  414.77  5526.4   417.4  5547.7  415.83  5584.6  419.19
    5606  417.43  5621.5  419.92  5627.3  418.47  5642.9   420.7    5648  419.36
#Mann= 5 ,-1 , 0
  3925.3     .05       0  4715.8     .16       0  4983.5     .07       0
  4989.5     .16       0    5291     .05       0
Bank Sta=4943.8,5029.3
XS Rating Curve= 0 ,0
Exp/Cntr=0.3,0.1

Type RM Length L Ch R = 1 ,19084   ,59,59,59
BEGIN DESCRIPTION:
MONTGOMERY CREEK 17.1
END DESCRIPTION:
XS GIS Cut Line= 3
       3492118.8     10524003.52       3492570.2     10523572.95
      3493187.68     10522428.19
#Sta/Elev= 30
  3717.8  430.92  3813.4  428.44  4046.8  419.53  4117.6  418.45  4124.5  417.39
  4237.7   412.6  4423.8  408.66    4559  402.13  4735.2  401.16    4839  402.71
  4948.5   401.7  4964.7  396.48  4999.1  392.39  5001.9  391.89  5005.1  392.39
  5030.4  394.39  5052.3  401.58  5068.5     403  5177.9  402.59  5274.8  404.06
  5385.5   409.7  5473.1   415.7  5576.9     419  5582.6  419.98  5598.8  419.53
  5604.5  420.78    5615  420.44  5620.7   421.5  5636.9  420.67  5642.3  421.94
#Mann= 3 ,-1 , 0
  3717.8     .05       0  4999.1     .04       0  5005.1     .05       0
Bank Sta=4948.5,5052.3
XS Rating Curve= 0 ,0
Exp/Cntr=0.3,0.1

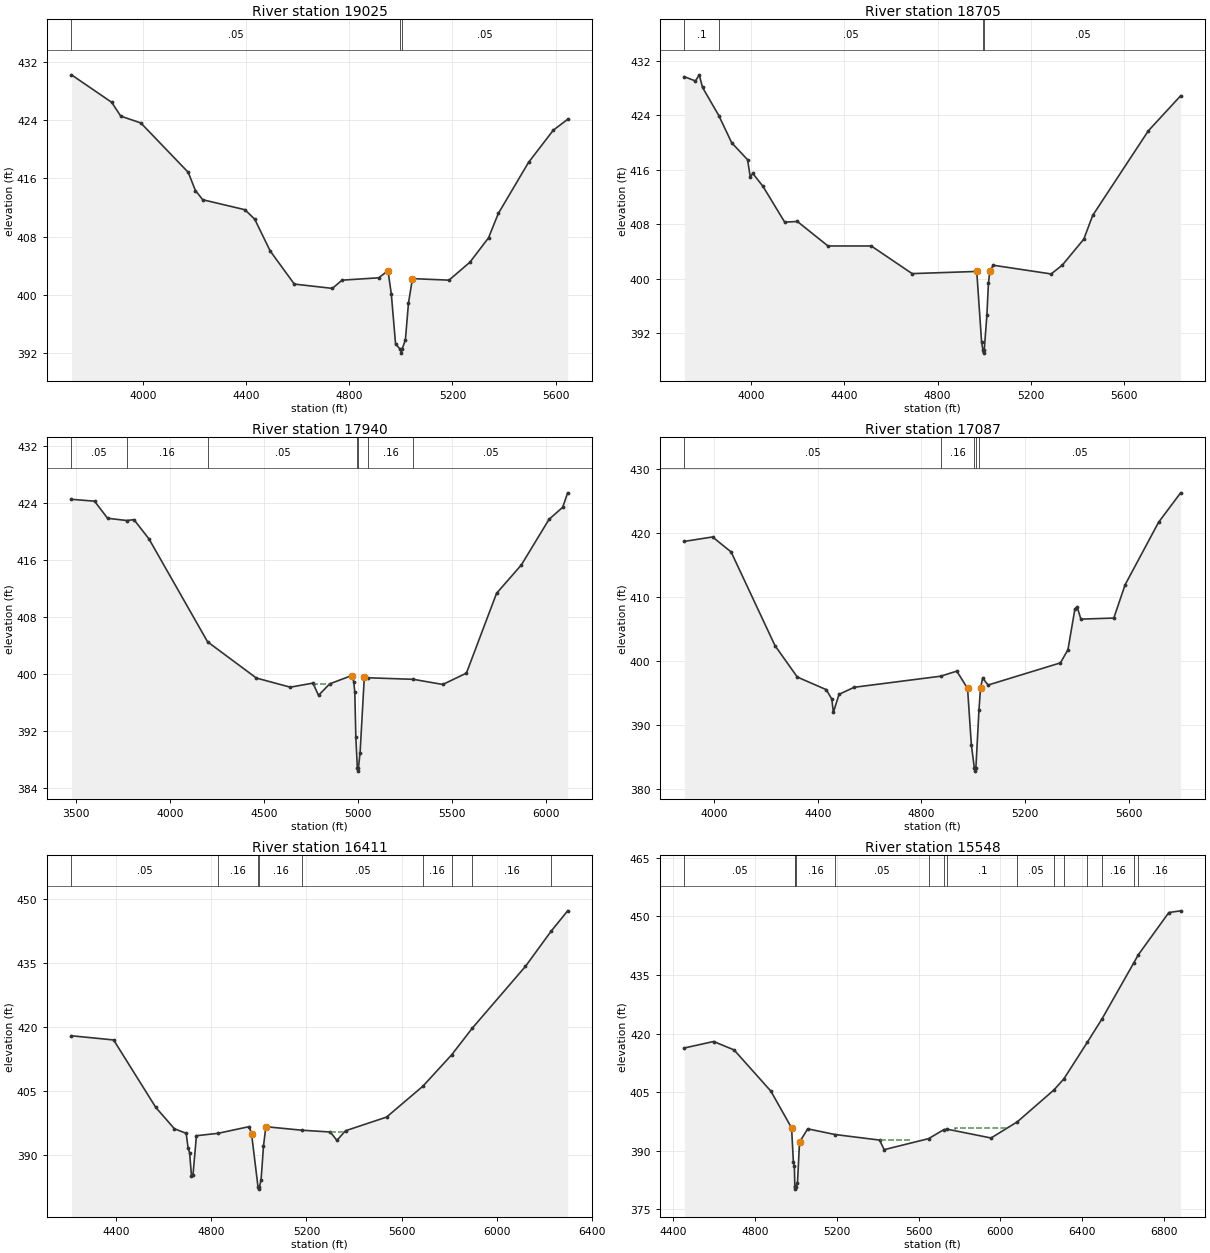
Type RM Length L Ch R = 1 ,19025   ,320,320,320
BEGIN DESCRIPTION:
MONTGOMERY CREEK 17.2
END DESCRIPTION:
XS GIS Cut Line= 3
      3492174.33     10524024.38      3492625.76     10523593.79
      3493243.79     10522447.99
#Sta/Elev= 30
  3721.2  430.21  3877.2  426.44  3912.4  424.54  3990.4   423.6  4174.2  416.83
  4202.4  414.32  4230.7  413.06  4394.3  411.69  4432.4  410.39  4492.4  406.03
  4586.1  401.48  4733.8  400.89  4771.4  402.02  4913.3  402.34  4949.7  403.31
  4962.7  400.07    4979  393.27  4997.8   392.5  5000.6     392  5003.8   392.5
  5017.1  393.79  5029.2  398.88  5044.6  402.23  5186.5  402.02  5267.8  404.49
  5339.8  407.83  5377.9  411.18    5495  418.18  5591.2  422.61  5646.9   424.1
#Mann= 3 ,-1 , 0
  3721.2     .05       0  4997.8     .03       0  5003.8     .05       0
Bank Sta=4949.7,5044.6
XS Rating Curve= 0 ,0
Exp/Cntr=0.3,0.1

Type RM Length L Ch R = 1 ,18705   ,765,765,765
BEGIN DESCRIPTION:
MONTGOMERY CREEK 16.0
END DESCRIPTION:
XS GIS Cut Line= 4
      3492485.63       10524380.       3493013.4     10523400.84
      3493176.59     10523178.62      3493339.77     10522456.47
#Sta/Elev= 30
  3714.4  429.68  3761.7  429.06  3777.9  429.96  3792.1   428.1    3862  423.97
    3917  419.99  3985.2  417.49  3996.9  414.93  4007.4  415.49  4051.2  413.58
  4144.5  408.32  4198.8  408.42  4330.2  404.82  4515.9  404.82  4691.1  400.76
  4968.3  401.08  4989.1  390.71  4994.6  389.58  4997.3  389.08  5000.6  389.58
  5011.8  394.66  5018.4  399.32  5024.6  401.16  5039.3  401.99  5287.6  400.71
  5335.9  402.03  5427.5  405.82  5465.5   409.3  5704.2  421.73  5842.8  426.88
#Mann= 4 ,-1 , 0
  3714.4      .1       0    3862     .05       0  4994.6     .03       0
  5000.6     .05       0
Bank Sta=4968.3,5024.6
XS Rating Curve= 0 ,0
Exp/Cntr=0.3,0.1

Type RM Length L Ch R = 1 ,17940   ,853,853,853
BEGIN DESCRIPTION:
MONTGOMERY CREEK 14.0
END DESCRIPTION:
XS GIS Cut Line= 4
      3493933.54     10524963.38      3493860.62     10523619.59
      3493699.35     10523306.13      3493427.21     10522406.36
#Sta/Elev= 30
  3477.3  424.51  3600.1  424.25  3669.3  421.85  3771.3  421.54  3809.5  421.66
  3889.6  418.95    4201  404.53  4460.5  399.45  4640.7  398.17  4760.9  398.74
    4791  397.03  4850.7  398.64  4967.2   399.8  4978.2  398.96  4983.8  397.46
  4989.4  391.13  4997.3   386.9  5000.1   386.4  5003.3   386.9  5011.9  388.97
  5034.4  399.58  5053.5  399.49  5295.3  399.27  5451.9  398.55  5577.3  400.14
  5737.6  411.33  5869.4  415.31  6016.8  421.71  6089.2  423.39  6115.6  425.42
#Mann= 7 ,-1 , 0
  3477.3     .05       0  3771.3     .16       0    4201     .05       0
  4997.3    .035       0  5003.3     .05       0  5053.5     .16       0
  5295.3     .05       0
#XS Ineff= 1 ,-1
 4771.34 4850.51  398.62
Permanent Ineff=
       F
Bank Sta=4967.2,5034.4
XS Rating Curve= 0 ,0
Exp/Cntr=0.3,0.1

Type RM Length L Ch R = 1 ,17087   ,676,676,676
BEGIN DESCRIPTION:
MONTGOMERY CREEK 12.0
END DESCRIPTION:
XS GIS Cut Line= 3
      3494957.81     10523452.91      3494079.37     10522942.51
      3493538.76     10522225.16
#Sta/Elev= 30
  3885.9  418.64  3994.4  419.33    4066  416.99  4235.2  402.37  4321.3  397.46
  4433.1  395.49  4454.6  394.01  4460.4  391.93  4482.3  394.76  4540.6  395.86
  4874.3  397.59  4936.5  398.38  4978.2  395.69  4992.8  386.89  5004.3  383.27
  5007.1  382.77  5010.3  383.27  5022.1  392.25  5028.2  395.76  5036.5   397.3
  5057.3  396.21  5336.3  399.67  5365.4  401.72  5392.5  408.12  5400.8  408.45
  5415.4   406.5  5542.4  406.67  5586.1  411.88  5715.2  421.63  5800.1  426.22
#Mann= 5 ,-1 , 0
  3885.9     .05       0  4874.3     .16       0  5004.3     .07       0
  5010.3     .16       0  5022.1     .05       0
Bank Sta=4978.2,5028.2
XS Rating Curve= 0 ,0
Exp/Cntr=0.3,0.1

Type RM Length L Ch R = 1 ,16411   ,863,863,863
BEGIN DESCRIPTION:
MONTGOMERY CREEK 11.0
END DESCRIPTION:
XS GIS Cut Line= 4
      3495027.29     10523366.13      3494594.63     10522832.61
      3494589.79     10522630.01      3493919.64     10521636.94
#Sta/Elev= 30
  4211.2     418  4388.5  417.02  4565.9  401.24  4644.2  396.24  4693.8  395.17
  4701.7  391.82  4708.2  390.63  4716.1  385.24  4722.5  385.46  4736.9  394.61
  4827.7  395.17  4959.1  396.74  4969.1  394.95  4996.1  382.61  4998.9  382.11
  5002.1  382.61  5009.1  384.35  5019.1   392.2  5029.1  396.72  5181.6  395.89
    5300  395.48    5328  393.52  5364.2  395.77  5536.9  398.97    5690  406.21
  5810.6  413.53  5898.4  419.83  6121.4  434.25  6228.8  442.44  6298.8  447.24
#Mann= 9 ,-1 , 0
  4211.2     .05       0  4827.7     .16       0  4996.1     .07       0
  5002.1     .16       0  5181.6     .05       0    5690     .16       0
  5810.6     .12       0  5898.4     .16       0  6228.8     .05       0
#XS Ineff= 1 ,-1
  5299.4 5359.18  395.46
Permanent Ineff=
       F
Bank Sta=4969.1,5029.1
XS Rating Curve= 0 ,0
Exp/Cntr=0.3,0.1

Type RM Length L Ch R = 1 ,15548   ,880,880,880
BEGIN DESCRIPTION:
MONTGOMERY CREEK 9.0
END DESCRIPTION:
XS GIS Cut Line= 3
      3495206.11      10523324.5      3495175.73     10522465.08
      3494429.68     10521085.77
#Sta/Elev= 30
  4454.1  416.31    4597  417.96  4697.1   415.8  4877.2  405.24 4978.46  395.83
  4987.1  387.22  4992.1  386.02  4994.2  380.89  4994.3  380.65    4997  380.15
  5000.3  380.65  5007.3  381.71  5017.3  392.18  5057.3  395.59  5190.8  394.14
  5408.9  392.71  5431.6  390.26  5648.9  393.08  5722.9  395.37  5741.1  395.49
  5954.6  393.25  6083.1  397.39  6262.3  405.55    6311   408.4    6425  417.71
  6497.3  423.73    6653   438.1  6675.8  440.22  6824.5  450.99  6882.2  451.43
#Mann= 15 ,-1 , 0
  4454.1     .05       0  4994.2     .16       0  4994.3     .07       0
  5000.3     .16       0  5190.8     .05       0  5648.9      .1       0
  5722.9     .05       0  5741.1      .1       0  6083.1     .05       0
  6262.3     .16       0    6311     .05       0    6425     .12       0
  6497.3     .16       0    6653     .12       0  6675.8     .16       0
#XS Ineff= 2 ,-1
 5409.04 5558.17  392.69 5776.09 6034.04  395.74
Permanent Ineff=
       F       F
Bank Sta=4978.46,5017.3
XS Rating Curve= 0 ,0
Exp/Cntr=0.3,0.1

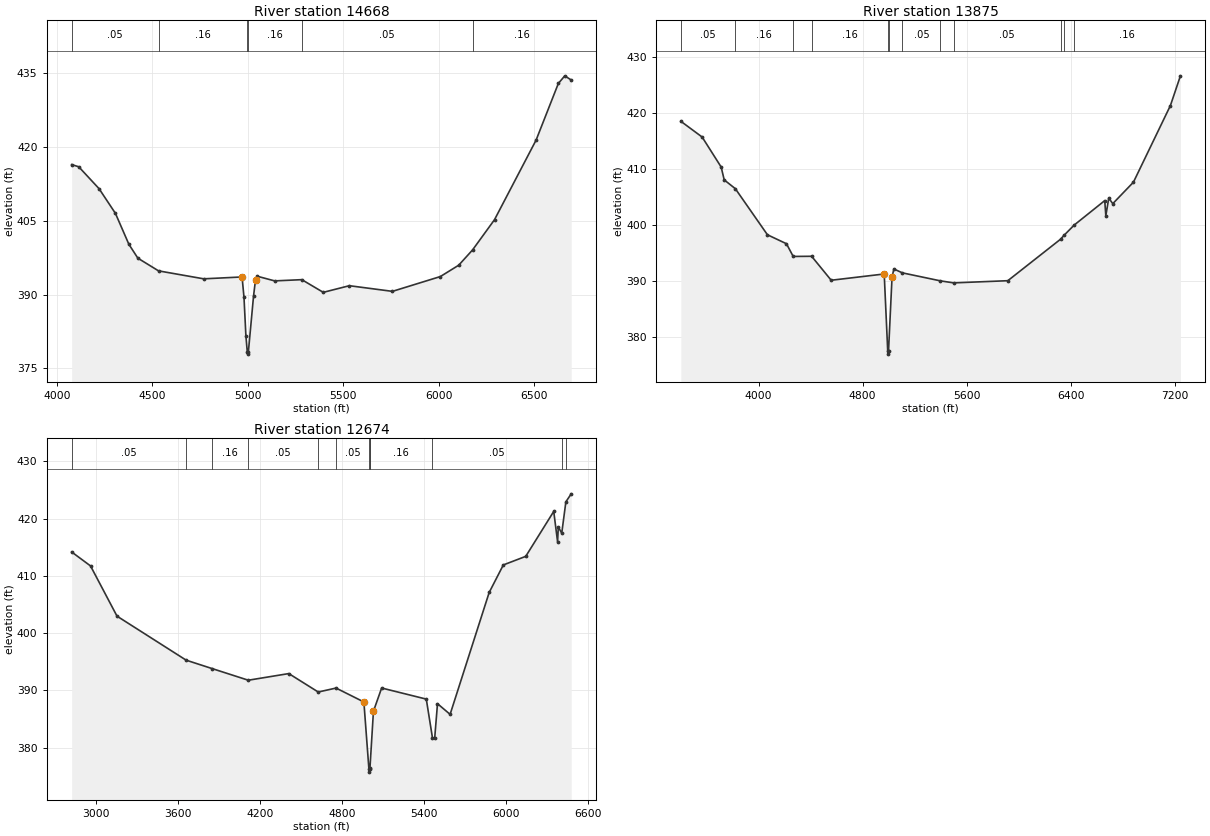
Type RM Length L Ch R = 1 ,14668   ,793,793,793
BEGIN DESCRIPTION:
MONTGOMERY CREEK 8.0
END DESCRIPTION:
XS GIS Cut Line= 4
      3495653.16     10523189.91      3495731.28     10522391.29
        3495766.     10522013.69      3495367.35     10520635.72
#Sta/Elev= 30
  4077.1  416.45  4114.1  416.01  4220.7  411.55  4306.5  406.52  4376.8  400.24
  4423.9  397.41  4532.1  394.83  4768.7  393.21  4969.6  393.59  4979.6  389.46
  4989.6  381.64  4996.7  378.39  4999.4  377.89  5002.7  378.39  5029.8  389.76
  5039.9  392.97  5048.6  393.74  5140.3  392.79  5282.5  393.04  5394.8  390.46
  5531.5  391.81  5756.9  390.66  6007.8  393.67  6104.1  395.98  6176.6  399.09
  6291.5  405.24  6509.5  421.45  6625.9  432.96  6659.5  434.51  6693.2  433.66
#Mann= 6 ,-1 , 0
  4077.1     .05       0  4532.1     .16       0  4996.7     .07       0
  5002.7     .16       0  5282.5     .05       0  6176.6     .16       0
Bank Sta=4969.6,5039.9
XS Rating Curve= 0 ,0
Exp/Cntr=0.3,0.1

Type RM Length L Ch R = 1 ,13875   ,1201,1201,1201
BEGIN DESCRIPTION:
MONTGOMERY CREEK 7.0
END DESCRIPTION:
XS GIS Cut Line= 4
      3495713.93     10523610.89       3496304.2      10522252.4
      3496364.96     10521527.58      3495822.42     10519991.11
#Sta/Elev= 30
  3403.5  418.52  3566.9  415.71    3713  410.36  3736.5  408.06  3821.9  406.49
  4068.6  398.26  4214.7  396.66  4266.6  394.39    4408  394.42  4558.4  390.14
  4965.7  391.26  4992.8  377.45  4995.6  376.95  4998.8  377.45  5025.9  390.75
  5040.1  392.15  5105.2  391.46  5397.8  390.03  5499.6  389.67  5915.3  390.06
  6320.1  397.46  6349.2  398.21  6425.6     400  6659.9  404.36  6668.3  401.66
  6690.8  404.81  6721.7  403.82  6880.4  407.65  7164.4  421.33  7241.5  426.64
#Mann= 12 ,-1 , 0
  3403.5     .05       0  3821.9     .16       0  4266.6     .12       0
    4408     .16       0  4992.8     .07       0  4998.8     .16       0
  5105.2     .05       0  5397.8     .16       0  5499.6     .05       0
  6320.1     .16       0  6349.2     .05       0  6425.6     .16       0
Bank Sta=4965.7,5025.9
XS Rating Curve= 0 ,0
Exp/Cntr=0.3,0.1

Type RM Length L Ch R = 1 ,12674   ,976,976,976
BEGIN DESCRIPTION:
MONTGOMERY CREEK 6.2
END DESCRIPTION:
XS GIS Cut Line= 4
      3495917.94     10523702.02      3497030.01     10522209.99
      3497033.36     10521753.27      3497328.49      10520446.9
#Sta/Elev= 30
  2820.6  414.17  2958.8  411.73  3152.7  402.96  3658.9  395.27  3849.2   393.8
  4113.8  391.77  4410.1  392.93  4625.6  389.71  4756.1   390.4  4959.8  387.97
  4996.8  376.22  4999.6  375.72  5002.8  376.22  5004.5  376.52  5029.8  386.35
  5089.8  390.41  5416.7  388.47  5461.5  381.76  5478.2  381.66  5498.7  387.67
    5591  385.81  5877.1   407.1  5980.5   411.9  6144.6   413.4  6349.6  421.25
  6377.8  415.94    6383  418.53  6408.2  417.45  6438.4  422.92  6477.5  424.32
#Mann= 12 ,-1 , 0
  2820.6     .05       0  3658.9     .12       0  3849.2     .16       0
  4113.8     .05       0  4625.6     .16       0  4756.1     .05       0
  4996.8    .035       0  5002.8     .05       0  5004.5     .16       0
  5461.5     .05       0  6408.2     .16       0  6438.4     .05       0
Bank Sta=4959.8,5029.8
XS Rating Curve= 0 ,0
Exp/Cntr=0.3,0.1