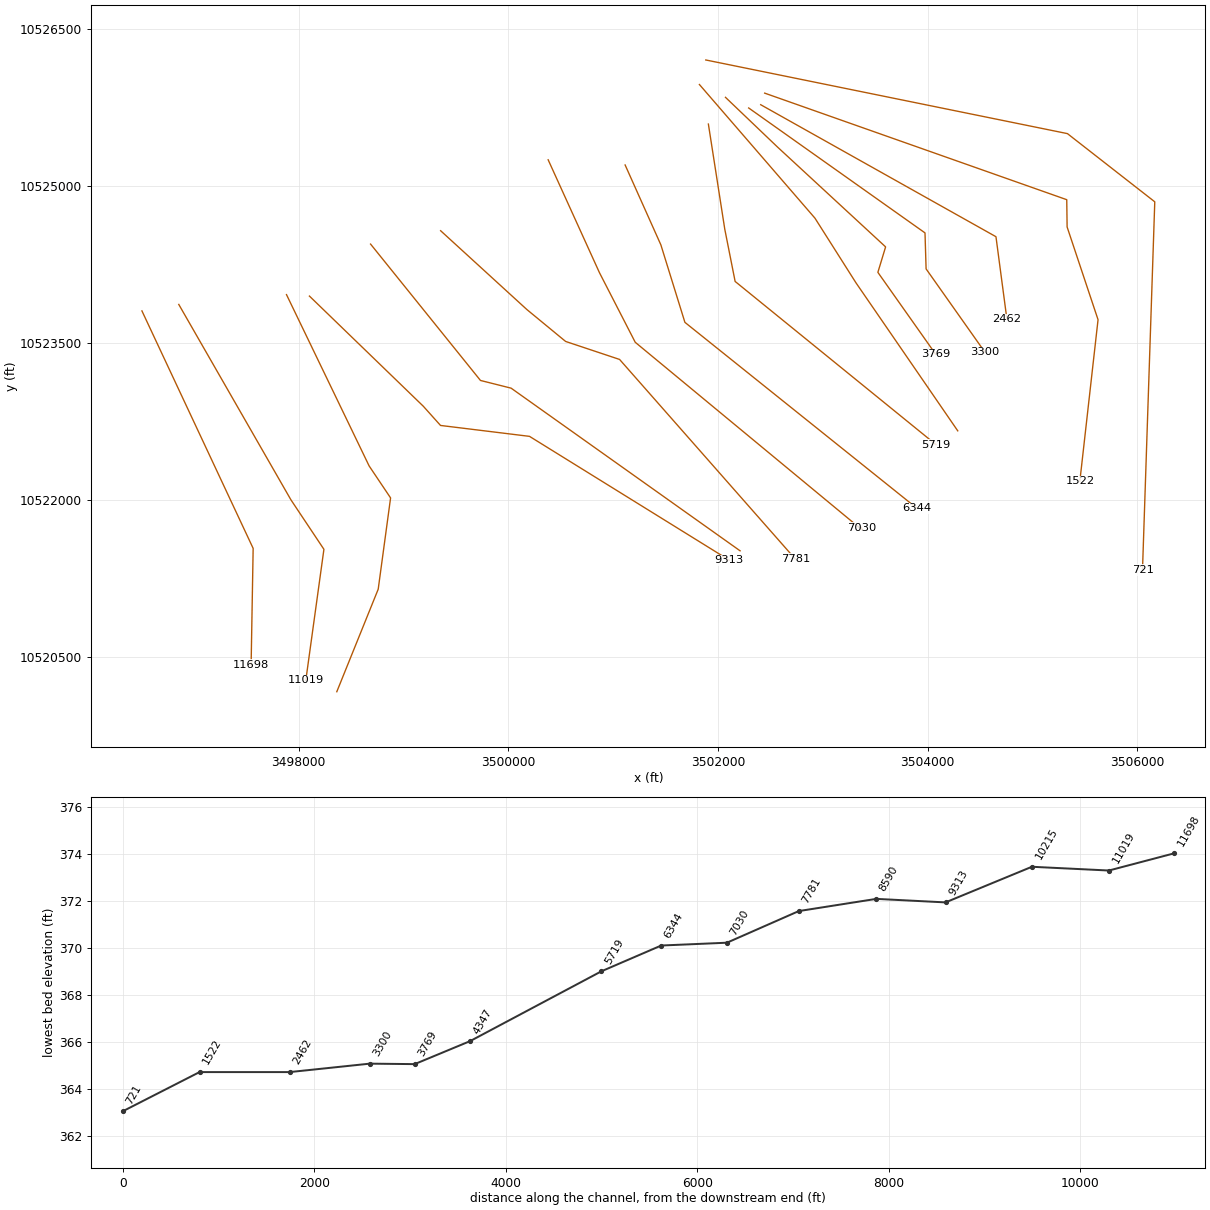
HEC-RAS study MONTGOMERY CREEK.prj: MONTGOMERY CREEK Base Level Engineering

--- MONTGOMERY CREEK.g01 (geometry) --- (continued)

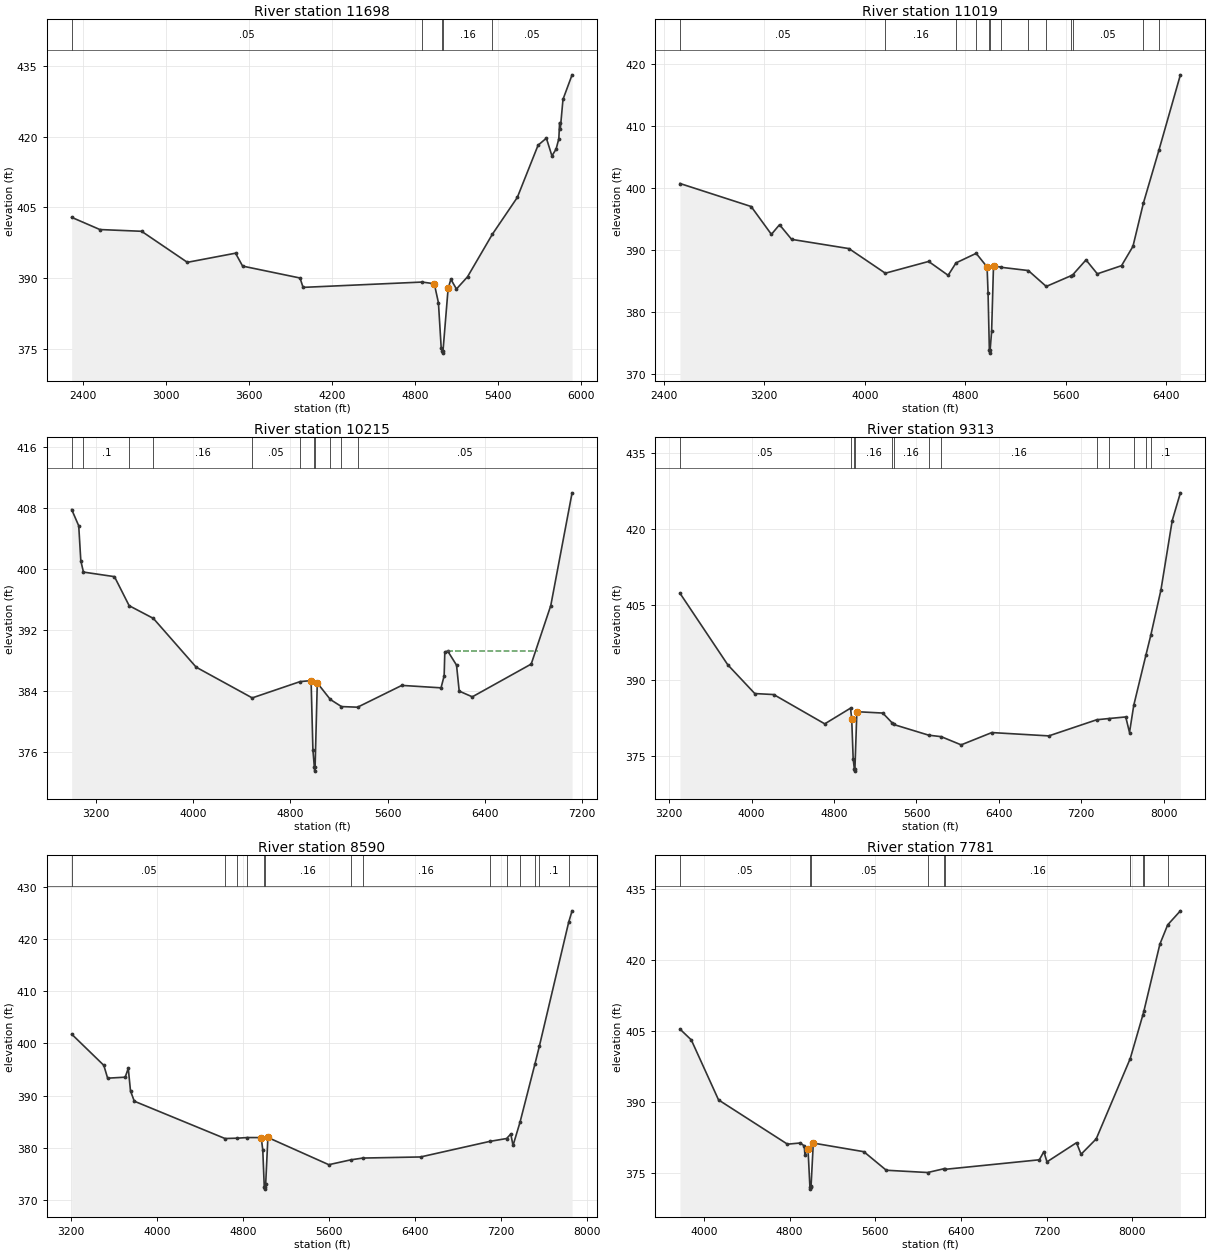
Type RM Length L Ch R = 1 ,11698   ,679,679,679
BEGIN DESCRIPTION:
MONTGOMERY CREEK 6.0
END DESCRIPTION:
XS GIS Cut Line= 3
      3496503.84     10523806.24      3497565.01      10521538.8
      3497545.53     10520425.94
#Sta/Elev= 30
  2320.2  402.87    2524  400.28  2825.5  399.91  3156.2  393.32  3504.3  395.26
  3555.5  392.52  3970.4  389.99  3992.5     388  4853.6  389.13  4940.8  388.77
  4970.8  384.74  4990.9   375.1  4997.9  374.54  5000.6  374.04  5003.9  374.54
  5040.9  387.81  5060.9  389.71  5100.9  387.65  5180.9  390.24  5360.1  399.26
  5540.9   407.1    5691  418.19    5751  419.68    5791  415.92    5821  417.35
    5841  419.57  5846.4  422.99  5851.4  421.57    5871  427.92  5936.7  433.13
#Mann= 5 ,-1 , 0
  2320.2     .05       0  4853.6     .16       0  4997.9     .07       0
  5003.9     .16       0  5360.1     .05       0
Bank Sta=4940.8,5040.9
XS Rating Curve= 0 ,0
Exp/Cntr=0.3,0.1

Type RM Length L Ch R = 1 ,11019   ,804,804,804
BEGIN DESCRIPTION:
MONTGOMERY CREEK 5.0
END DESCRIPTION:
XS GIS Cut Line= 4
       3496855.4     10523867.88      3497924.86     10522003.27
      3498240.17       10521530.      3498067.22     10520277.61
#Sta/Elev= 30
  2528.9  400.73  3095.2  397.01  3256.3  392.51    3321  394.07  3417.3   391.7
  3873.3  390.21    4163  386.23  4507.6  388.13  4662.9  385.89  4725.7   387.9
  4886.1  389.44  4972.9  387.24  4980.8  382.95    4991  373.81  4993.7  373.31
    4997  373.81    5009  376.81    5024  387.46    5087  387.18  5300.9  386.66
  5443.9  384.09  5643.1  385.84  5655.3  385.99  5760.3  388.38  5850.2  386.13
    6043  387.45  6133.8  390.57  6216.6  397.54  6340.2   406.1  6511.4   418.3
#Mann= 13 ,-1 , 0
  2528.9     .05       0    4163     .16       0  4725.7     .05       0
  4886.1     .16       0    4991     .07       0    4997     .16       0
    5087     .05       0  5300.9     .16       0  5443.9     .05       0
  5643.1     .16       0  5655.3     .05       0  6216.6     .16       0
  6340.2     .05       0
Bank Sta=4972.9,5024
XS Rating Curve= 0 ,0
Exp/Cntr=0.3,0.1

Type RM Length L Ch R = 1 ,10215   ,902,902,902
BEGIN DESCRIPTION:
MONTGOMERY CREEK 3.0
END DESCRIPTION:
XS GIS Cut Line= 5
       3497883.2     10523961.59      3498671.38     10522326.19
      3498876.25     10522020.63      3498758.19     10521149.11
      3498363.06     10520170.13
#Sta/Elev= 30
  2999.5   407.8  3057.5  405.66  3074.6  401.08  3096.2  399.59  3351.6  398.99
  3472.5  395.18    3672  393.51  4024.1  387.11  4485.5  383.08  4879.9  385.22
  4969.9  385.35  4984.9  376.28  4996.9  373.97  4999.6  373.47  5002.9  373.97
  5020.9  385.04  5128.5  382.87  5220.1  381.94  5352.5  381.86  5716.6  384.72
  6039.5   384.4  6065.1  385.98  6070.5  389.11  6094.6  389.22    6167  387.38
    6189  383.97  6296.8  383.22  6781.6  387.52  6942.7   395.2    7118  409.99
#Mann= 11 ,-1 , 0
  2999.5     .05       0  3096.2      .1       0  3472.5     .05       0
    3672     .16       0  4485.5     .05       0  4879.9     .16       0
  4996.9     .07       0  5002.9     .16       0  5128.5     .05       0
  5220.1     .16       0  5352.5     .05       0
#XS Ineff= 1 ,-1
 6091.74 6840.95  389.22
Permanent Ineff=
       F
Bank Sta=4969.9,5020.9
XS Rating Curve= 0 ,0
Exp/Cntr=0.3,0.1

Type RM Length L Ch R = 1 ,9313    ,723,723,723
BEGIN DESCRIPTION:
MONTGOMERY CREEK 6.1
END DESCRIPTION:
XS GIS Cut Line= 5
      3498101.93     10523947.73      3499188.75     10522895.63
      3499352.79     10522712.58      3500201.75     10522608.41
      3502107.16     10521426.64
#Sta/Elev= 30
  3305.5  407.23  3769.6  393.03  4031.2  387.34  4215.1  387.14  4710.3  381.33
  4960.1  384.44  4971.7  382.38  4985.9   374.4  4997.1  372.45  4999.9  371.95
  5003.1  372.45  5021.8  383.74  5273.3  383.47  5367.6  381.45  5377.8  381.21
  5719.2  379.08    5840  378.79    6034  377.16  6331.5   379.6  6884.5  378.94
  7349.5  382.14  7470.2  382.39    7631   382.7  7667.6  379.61  7708.8  385.01
  7828.1  395.08  7874.4  398.93  7972.4  407.87  8082.2  421.67  8161.4  427.16
#Mann= 13 ,-1 , 0
  3305.5     .05       0  4960.1     .16       0  4997.1     .07       0
  5003.1     .16       0  5367.6     .05       0  5377.8     .16       0
  5719.2      .1       0    5840     .16       0  7349.5     .12       0
  7470.2     .16       0  7708.8      .1       0  7828.1     .05       0
  7874.4      .1       0
Bank Sta=4971.7,5021.8
XS Rating Curve= 0 ,0
Exp/Cntr=0.3,0.1

Type RM Length L Ch R = 1 ,8590    ,809,809,809
BEGIN DESCRIPTION:
MONTGOMERY CREEK 4.1
END DESCRIPTION:
XS GIS Cut Line= 4
      3498685.26     10524444.27      3499733.88     10523142.16
      3500026.35     10523068.53      3502210.78     10521515.64
#Sta/Elev= 30
  3207.4  401.78  3506.1  395.81  3541.7  393.35  3704.8  393.54  3733.6  395.23
  3754.4  390.91  3789.6  388.94  4633.6  381.79  4748.8  381.86  4841.5  381.98
  4970.2  381.97  4984.7  379.54  4998.2   372.6  5000.9   372.1  5004.2   372.6
  5011.5  373.07  5032.1  381.99  5598.6  376.78  5802.9  377.71  5914.6  378.05
  6451.6  378.26  7095.1  381.24  7252.1  381.79  7290.9  382.65  7311.8  380.46
  7376.9  384.92  7515.1  396.03  7556.5  399.46  7829.1   423.2    7861   425.4
#Mann= 14 ,-1 , 0
  3207.4     .05       0  4633.6     .16       0  4748.8     .05       0
  4841.5     .16       0  4998.2     .07       0  5004.2     .16       0
  5802.9     .12       0  5914.6     .16       0  7095.1     .12       0
  7252.1     .16       0  7376.9      .1       0  7515.1     .05       0
  7556.5      .1       0  7829.1     .05       0
Bank Sta=4970.2,5032.1
XS Rating Curve= 0 ,0
Exp/Cntr=0.3,0.1

Type RM Length L Ch R = 1 ,7781    ,751,751,751
BEGIN DESCRIPTION:
MONTGOMERY CREEK 3.2
END DESCRIPTION:
XS GIS Cut Line= 5
      3499353.65     10524571.87      3500176.59     10523819.24
      3500546.38     10523514.56      3501061.12     10523342.79
      3502737.63     10521437.19
#Sta/Elev= 30
  3775.5  405.39    3881  403.11  4135.7  390.43  4779.5  381.08  4899.6  381.33
  4936.1  380.72  4942.6  378.84  4971.3  380.15  4989.1  372.08  4991.8  371.58
  4995.1  372.08    5000  372.23  5020.8  381.31 5493.15  379.49  5702.7  375.57
  6089.6  375.09  6243.4   375.9  6254.5  375.77  7132.7  377.78  7175.4  379.51
  7203.9  377.34    7480  381.39  7522.6  378.95    7664  382.19  7982.1  399.18
  8098.6  408.28  8109.7  409.21  8258.9  423.35  8331.9  427.43  8450.6  430.39
#Mann= 10 ,-1 , 0
  3775.5     .05       0  4989.1    .035       0  4995.1     .05       0
  6089.6     .16       0  6243.4     .05       0  6254.5     .16       0
  7982.1     .05       0  8098.6     .16       0  8109.7      .1       0
  8331.9     .05       0
Bank Sta=4971.3,5020.8
XS Rating Curve= 0 ,0
Exp/Cntr=0.3,0.1

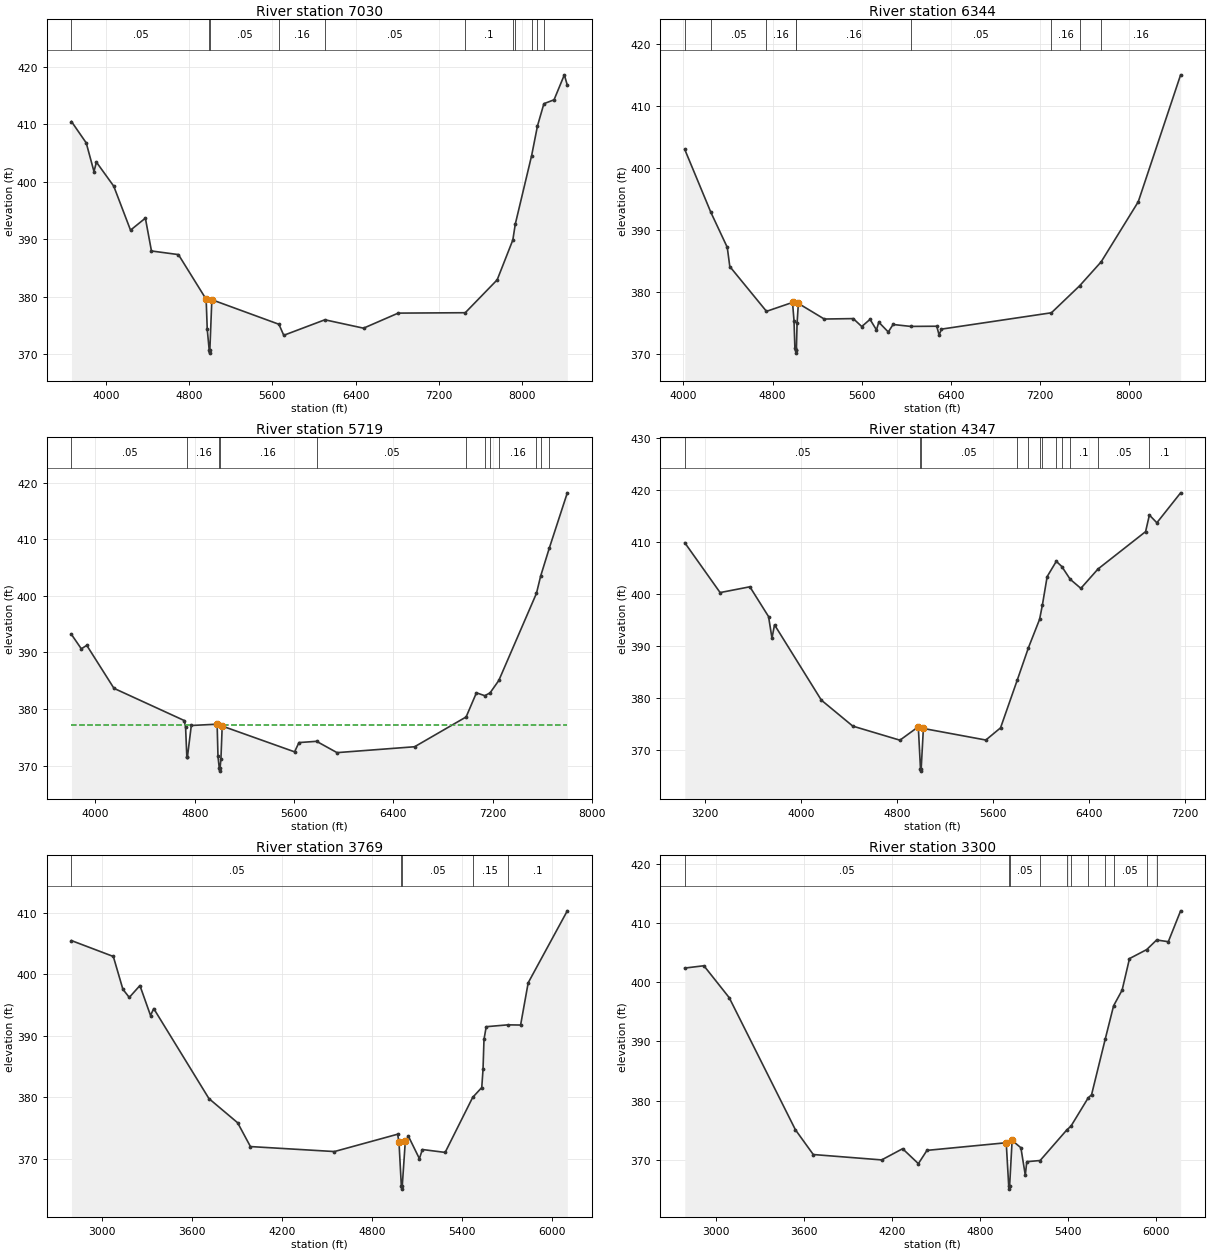
Type RM Length L Ch R = 1 ,7030    ,686,686,686
BEGIN DESCRIPTION:
MONTGOMERY CREEK 5.1
END DESCRIPTION:
XS GIS Cut Line= 5
      3500379.73     10525248.91       3500869.3     10524170.81
      3501210.45     10523506.74       3503377.1     10521713.45
      3503368.89     10521738.08
#Sta/Elev= 30
  3667.4  410.52  3809.4   406.8  3884.1  401.81  3907.2  403.46  4074.2  399.27
  4235.5  391.62  4378.3  393.71  4436.8     388  4696.2  387.37  4962.9   379.6
  4973.3  374.39  4992.4  370.73  4995.2  370.23  4998.4  370.73  5017.6  379.52
  5662.8  375.25  5709.2  373.33  6104.7  376.03  6476.4  374.57  6809.8  377.19
    7455  377.26    7762  382.98  7912.5  389.91  7936.2  392.68  8093.4   404.6
  8149.7  409.77  8211.3  413.62  8309.1   414.3    8408  418.64  8436.5  416.83
#Mann= 11 ,-1 , 0
  3667.4     .05       0  4992.4    .035       0  4998.4     .05       0
  5662.8     .16       0  6104.7     .05       0    7455      .1       0
  7912.5     .05       0  7936.2      .1       0  8093.4     .05       0
  8149.7      .1       0  8211.3     .05       0
Bank Sta=4962.9,5017.6
XS Rating Curve= 0 ,0
Exp/Cntr=0.3,0.1

Type RM Length L Ch R = 1 ,6344    ,625,625,625
BEGIN DESCRIPTION:
MONTGOMERY CREEK 4.0
END DESCRIPTION:
XS GIS Cut Line= 4
      3501114.09     10525199.46      3501455.24     10524436.43
      3501684.41     10523696.85      3503897.51     10521922.12
#Sta/Elev= 30
  4012.3  402.96  4246.3  392.82  4393.3  387.18  4416.2  384.08  4745.2  376.85
  4978.8  378.29    4992  375.34  4999.7  371.01  5007.2  370.61  5009.9  370.11
  5013.2  370.61  5019.4   374.9  5031.1  378.13  5263.3  375.61  5523.2  375.68
  5599.7   374.4  5673.9  375.56  5731.5  373.85  5752.3   375.1  5837.4  373.52
  5880.3  374.73  6038.2  374.42  6272.4  374.45  6293.2  373.02    6314  373.98
  7300.7  376.62    7554  380.98  7746.8  384.84  8079.2  394.52  8459.2     415
#Mann= 9 ,-1 , 0
  4012.3     .16       0  4246.3     .05       0  4745.2     .16       0
  5007.2     .07       0  5013.2     .16       0  6038.2     .05       0
  7300.7     .16       0    7554      .1       0  7746.8     .16       0
Bank Sta=4978.8,5031.1
XS Rating Curve= 0 ,0
Exp/Cntr=0.3,0.1

Type RM Length L Ch R = 1 ,5719    ,1372,1372,1372
BEGIN DESCRIPTION:
MONTGOMERY CREEK 3.1
END DESCRIPTION:
XS GIS Cut Line= 4
      3501908.37     10525590.05      3502064.61     10524587.47
      3502163.57     10524087.47      3504080.21     10522529.42
#Sta/Elev= 30
  3806.4  393.18  3885.8  390.64  3929.7  391.25  4148.9  383.65  4715.6  377.95
  4725.8  376.76  4735.9  371.48  4740.9  371.56  4771.8  377.08  4979.9  377.31
  4986.7  371.61  4997.3  369.51  5000.1  369.01  5003.3  369.51  5010.5  371.16
  5020.7  376.98  5603.8  372.42    5639  374.06  5780.9  374.28  5945.7  372.28
  6570.6  373.32  6985.6  378.59  7068.7  382.86  7135.9  382.35  7178.3  382.84
  7248.9  385.04  7552.3  400.45  7585.9  403.49  7655.5  408.43  7800.8  418.22
#Mann= 12 ,-1 , 0
  3806.4     .05       0  4740.9     .16       0  4997.3     .07       0
  5003.3     .16       0  5780.9     .05       0  6985.6      .1       0
  7135.9     .16       0  7178.3      .1       0  7248.9     .16       0
  7552.3     .05       0  7585.9     .16       0  7655.5      .1       0
#XS Ineff= 2 , 0
         4770.58  377.16 5043.52           377.2
Permanent Ineff=
       F       F
Bank Sta=4979.9,5020.7
XS Rating Curve= 0 ,0
Exp/Cntr=0.3,0.1

Type RM Length L Ch R = 1 ,4347    ,578,578,578
BEGIN DESCRIPTION:
MONTGOMERY CREEK 2.0
END DESCRIPTION:
XS GIS Cut Line= 4
      3501822.89      10525967.6      3502925.29      10524691.6
      3503315.92     10524075.28      3504287.63     10522661.09
#Sta/Elev= 30
  3030.4  409.88  3324.9  400.31  3572.9  401.42  3728.6   395.7  3757.1  391.55
  3778.3  394.12  4168.5  379.66  4430.6  374.67  4823.2  371.97  4976.4  374.54
  4994.5  366.53  4997.3  366.03  5000.5  366.53  5018.7  374.22  5539.2     372
  5661.7  374.34  5801.7  383.56  5894.5  389.75    5987  395.17  6010.4  397.93
  6050.1  403.38  6126.3  406.31  6172.3  405.31  6242.2  402.86  6330.9  401.12
  6473.9  404.84  6870.3  412.01  6901.9   415.2  6964.2  413.71  7162.2  419.46
#Mann= 12 ,-1 , 0
  3030.4     .05       0  4994.5     .03       0  5000.5     .05       0
  5801.7      .1       0  5894.5     .05       0    5987      .1       0
  6010.4     .05       0  6126.3      .1       0  6172.3     .05       0
  6242.2      .1       0  6473.9     .05       0  6901.9      .1       0
Bank Sta=4976.4,5018.7
XS Rating Curve= 0 ,0
Exp/Cntr=0.3,0.1

Type RM Length L Ch R = 1 ,3769    ,469,469,469
BEGIN DESCRIPTION:
MONTGOMERY CREEK 2.2
END DESCRIPTION:
XS GIS Cut Line= 5
      3502071.54      10525845.3      3502566.35      10525372.2
      3503599.34     10524417.33      3503525.55     10524174.28
      3504076.75     10523393.06
#Sta/Elev= 30
  2798.7  405.46  3077.4  402.88  3141.2  397.54  3183.7  396.22  3254.5  398.15
  3325.2  393.28  3346.3  394.41  3714.1  379.77  3905.2  375.84  3990.3  371.97
  4549.3  371.16  4970.4  373.98  4979.5  372.65  4995.1  365.55  4997.8  365.05
  5001.1  365.55  5021.4  372.81  5042.3  373.64  5115.4     370  5134.9  371.49
  5286.7  371.02  5470.1  379.97  5530.5  381.57  5538.9  384.52  5545.3  389.38
  5560.1  391.46  5703.7  391.76  5789.1  391.73  5839.6   398.6  6100.1   410.3
#Mann= 5 ,-1 , 0
  2798.7     .05       0  4995.1     .03       0  5001.1     .05       0
  5470.1     .15       0  5703.7      .1       0
Bank Sta=4979.5,5021.4
XS Rating Curve= 0 ,0
Exp/Cntr=0.3,0.1

Type RM Length L Ch R = 1 ,3300    ,838,838,838
BEGIN DESCRIPTION:
MONTGOMERY CREEK 2.1
END DESCRIPTION:
XS GIS Cut Line= 4
       3502292.9     10525743.73       3503975.2     10524551.02
      3503985.62     10524207.27      3504547.59     10523411.15
#Sta/Elev= 30
  2788.3  402.38  2918.8  402.77  3091.1  397.39  3542.6  375.09  3664.4  370.91
  4130.7     370  4273.5  371.89  4380.9  369.37  4439.6  371.61  4979.9   372.9
    4997  365.57  4999.7  365.07    5003  365.57    5020  373.29    5080  372.05
    5110  367.41    5120   369.7  5211.1   369.9  5392.8  375.06  5421.3   375.7
  5538.2  380.45  5561.8  381.01    5655   390.4    5712  396.02  5769.9  398.65
  5820.3  403.98  5937.8   405.5  6005.4  407.12    6085  406.83  6168.9  412.04
#Mann= 11 ,-1 , 0
  2788.3     .05       0    4997    .035       0    5003     .05       0
  5211.1      .1       0  5392.8     .16       0  5421.3      .1       0
  5538.2     .05       0    5655      .1       0    5712     .05       0
  5937.8     .16       0  6005.4      .1       0
Bank Sta=4979.9,5020
XS Rating Curve= 0 ,0
Exp/Cntr=0.3,0.1

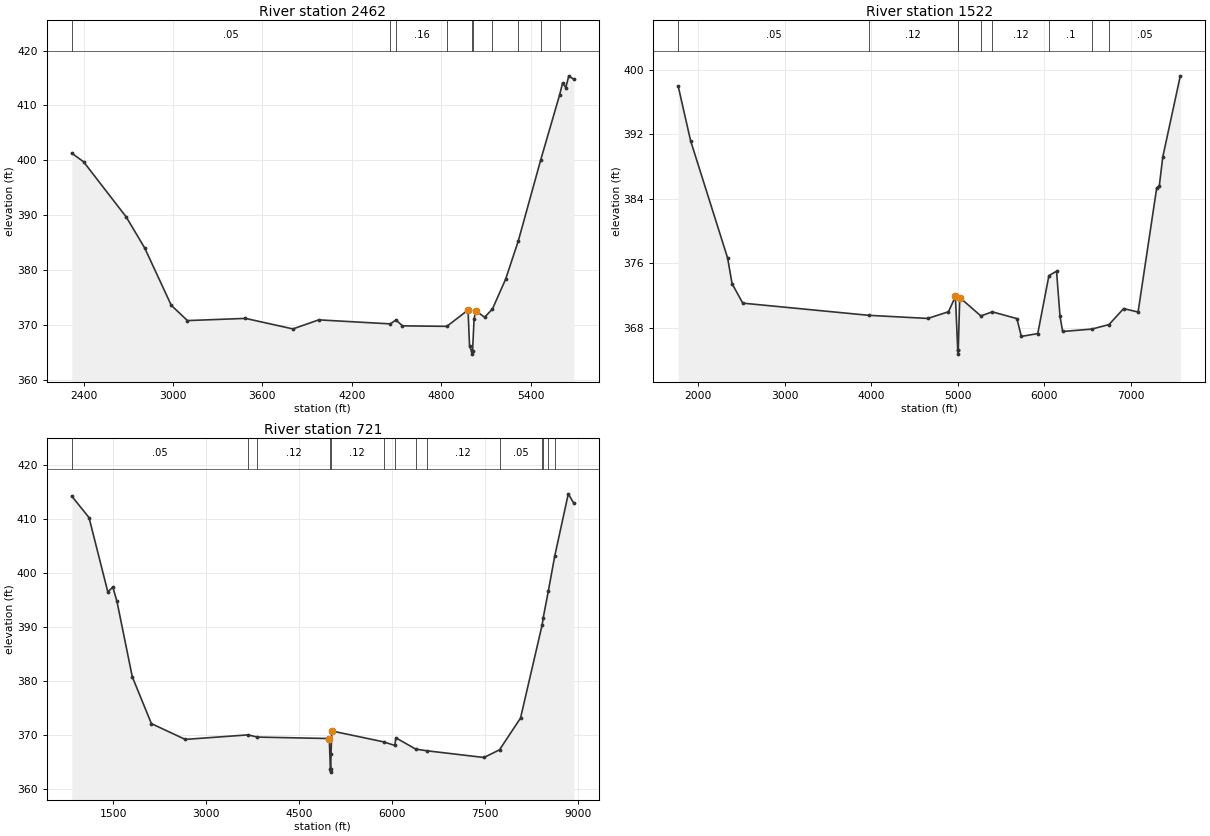
Type RM Length L Ch R = 1 ,2462    ,940,940,940
BEGIN DESCRIPTION:
MONTGOMERY CREEK 1.2
END DESCRIPTION:
XS GIS Cut Line= 3
      3502407.46     10525774.99      3504652.29     10524514.56
      3504756.45     10523728.11
#Sta/Elev= 30
  2321.2  401.31  2400.3  399.75  2686.6  389.69    2811  384.01  2988.9  373.59
  3097.3  370.82  3486.3  371.22  3804.6   369.3    3978  370.95    4458  370.22
  4495.7  370.94  4539.2  369.86  4837.1  369.77  4979.3  372.74  4989.4  366.19
  5003.5  365.21  5006.3  364.71  5009.5  365.21  5019.7  371.05  5029.8  372.65
  5090.3  371.43  5142.8  372.92  5231.5  378.37  5316.8  385.37  5467.2  400.13
  5593.9  411.96  5613.8  414.14    5635  413.25  5655.2   415.4    5689  414.76
#Mann= 10 ,-1 , 0
  2321.2     .05       0    4458     .12       0  4495.7     .16       0
  4837.1     .12       0  5003.5     .07       0  5009.5     .12       0
  5142.8     .05       0  5316.8      .1       0  5467.2     .05       0
  5593.9      .1       0
Bank Sta=4979.3,5029.8
XS Rating Curve= 0 ,0
Exp/Cntr=0.3,0.1

Type RM Length L Ch R = 1 ,1522    ,801,801,801
BEGIN DESCRIPTION:
MONTGOMERY CREEK 1.1
END DESCRIPTION:
XS GIS Cut Line= 5
      3502445.67      10525885.4      3505327.63     10524868.03
      3505331.11     10524607.61      3505626.25      10523722.2
      3505452.64     10522180.56
#Sta/Elev= 30
  1771.6  397.95  1914.5   391.2  2342.2  376.64  2393.5  373.46  2517.2  371.04
  3970.3  369.53  4654.7  369.14  4894.3  369.97  4974.3  371.87  5001.3  365.21
    5004  364.71  5007.3  365.21  5024.3  371.74  5268.6  369.45  5400.2  369.96
  5684.9  369.12    5736  366.91  5925.8  367.26  6054.9  374.46  6142.9     375
  6183.2  369.39  6213.4  367.52  6550.7  367.82  6749.1  368.38  6917.8  370.36
  7085.1  369.94  7300.2  385.34  7330.4  385.61  7370.6   389.2    7573  399.26
#Mann= 9 ,-1 , 0
  1771.6     .05       0  3970.3     .12       0  5001.3     .07       0
  5007.3     .12       0  5268.6     .05       0  5400.2     .12       0
  6054.9      .1       0  6550.7     .12       0  6749.1     .05       0
Bank Sta=4974.3,5024.3
XS Rating Curve= 0 ,0
Exp/Cntr=0.3,0.1

Type RM Length L Ch R = 1 ,721     ,0,0,0
BEGIN DESCRIPTION:
MONTGOMERY CREEK 1.0
END DESCRIPTION:
XS GIS Cut Line= 4
      3501883.64     10526202.01      3505334.15     10525498.89
      3506167.48     10524847.85      3506050.29     10521332.21
#Sta/Elev= 30
   834.1  414.15  1112.3  410.18  1415.6  396.41  1495.9  397.31  1562.2  394.69
  1809.9   380.7  2118.4  372.02  2664.2   369.1  3675.1  369.94  3828.4  369.53
  4986.9  369.26  5004.7  363.54  5007.4  363.04  5010.7  363.54    5014  366.34
  5028.5  370.66  5864.2  368.64  6043.5  367.98  6059.6   369.4  6379.7  367.31
    6557     367  7480.4  365.75  7731.8  367.17  8070.7  373.05  8419.9  390.33
    8435  391.54  8518.1  396.51    8623  403.09  8841.1  414.58  8930.6  412.82
#Mann= 14 ,-1 , 0
   834.1     .05       0  3675.1     .16       0  3828.4     .12       0
  5004.7     .07       0  5010.7     .12       0  5864.2     .07       0
  6043.5     .12       0  6379.7     .07       0    6557     .12       0
  7731.8     .05       0  8419.9      .1       0    8435     .05       0
  8518.1      .1       0    8623     .05       0
Bank Sta=4986.9,5028.5
XS Rating Curve= 0 ,0
Exp/Cntr=0.3,0.1

Chan Stop Cuts=-1
Use User Specified Reach Order=0
Composite Channel Slope=5