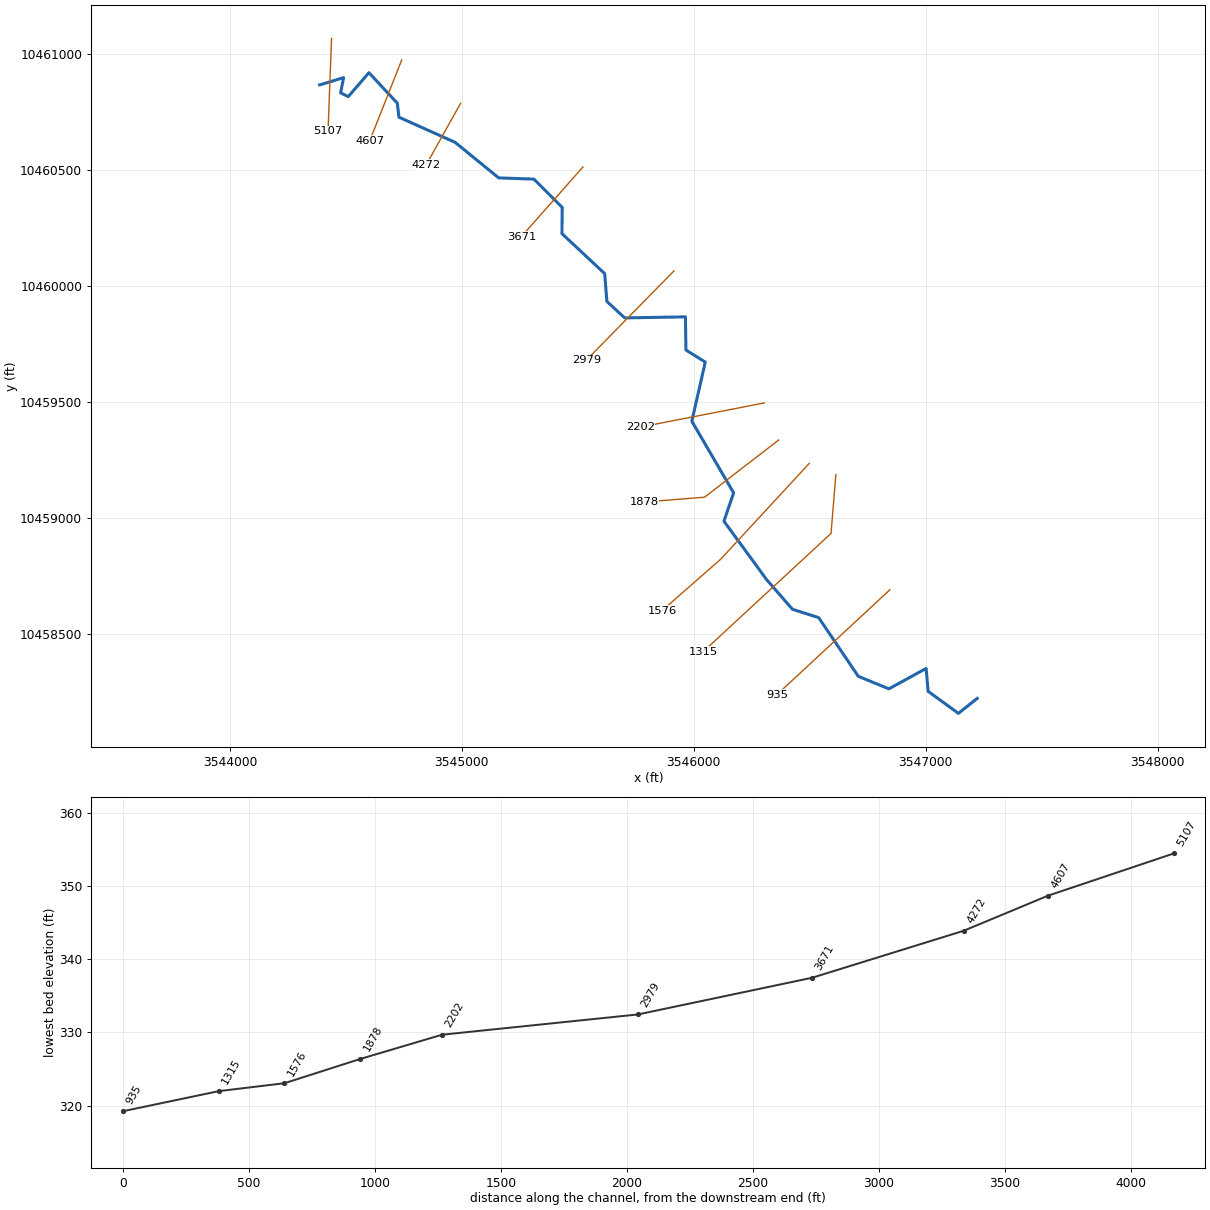
--- NAVASOTARIVTRIB10.prj (project) ---

Proj Title=NAVASOTA RIVER TRIBUTARY 10
Current Plan=p01
Default Exp/Contr=0.3,0.1
English Units
Geom File=g01
Flow File=f01
Plan File=p01
Y Axis Title=Elevation
X Axis Title(PF)=Main Channel Distance
X Axis Title(XS)=Station
BEGIN DESCRIPTION:
UNT02241 IN SAND CR
END DESCRIPTION:
DSS Export Rating Curves= 0
DSS Export Rating Curve Sorted= 0
DSS Export Volume Flow Curves= 0
DXF Filename=UNT02241 IN SAND CR.
DXF OffsetX= 0
DXF OffsetY= 0
DXF ScaleX= 1
DXF ScaleY= 10

--- NAVASOTARIVTRIB10.p01 (plan) ---

Plan Title=Multiple Run
Short Identifier=Multiple
Geom File=g01
Flow File=f01
Subcritical Flow
K Sum by GR= 0
Std Step Tol= 0.01
Critical Tol= 0.01
Num of Std Step Trials= 20
Max Error Tol= 0.3
Flow Tol Ratio= 0.001
Split Flow NTrial= 30
Split Flow Tol= 0.02
Split Flow Ratio= 0.02
Log Output Level= 0
Friction Slope Method= 1
Unsteady Friction Slope Method= 2
Unsteady Bridges Friction Slope Method= 1
Parabolic Critical Depth
Global Vel Dist=  1 , 1 , 1
Global Log Level= 0
CheckData=True
Encroach Param= -1, 0, 0, 0
BEGIN DESCRIPTION:
Multiple Run
END DESCRIPTION:

--- NAVASOTARIVTRIB10.f01 (steady flow) ---

Flow Title=Multiple
Program Version=4.10
Number of Profiles= 7
Profile Names=10-year,25-year,50-year,1pct_min,100-year,1pct_plu,500-year
River Rch & RM=UNT02241 IN SAND,Reach-1         ,5107
     530     704     843     739    1000    1352    1398
River Rch & RM=SOTA RIV TRIB 10,Reach-1         ,5107
     530     704     843     739    1000    1352    1398
River Rch & RM=NAVASOTARIVTRB10,Reach-1         ,5107
     530     704     843     739    1000    1352    1398
Boundary for River Rch & Prof#=NAVASOTARIVTRB10,Reach-1         , 1
Up Type= 0
Dn Type= 3
Dn Slope=0.005
Boundary for River Rch & Prof#=NAVASOTARIVTRB10,Reach-1         , 2
Up Type= 0
Dn Type= 3
Dn Slope=0.005
Boundary for River Rch & Prof#=NAVASOTARIVTRB10,Reach-1         , 3
Up Type= 0
Dn Type= 3
Dn Slope=0.005
Boundary for River Rch & Prof#=NAVASOTARIVTRB10,Reach-1         , 4
Up Type= 0
Dn Type= 3
Dn Slope=0.005
Boundary for River Rch & Prof#=NAVASOTARIVTRB10,Reach-1         , 5
Up Type= 0
Dn Type= 3
Dn Slope=0.005
Boundary for River Rch & Prof#=NAVASOTARIVTRB10,Reach-1         , 6
Up Type= 0
Dn Type= 3
Dn Slope=0.005
Boundary for River Rch & Prof#=NAVASOTARIVTRB10,Reach-1         , 7
Up Type= 0
Dn Type= 3
Dn Slope=0.005
DSS Import GetInterval= 0
DSS Import GetPeak= 0
DSS Import FillOption= 0

--- NAVASOTARIVTRIB10.g01 (geometry) ---

Geom Title=Existing Conditions
Program Version=4.10

River Reach=NAVASOTARIVTRB10,Reach-1
Reach XY= 30
      3544387.11     10460866.64      3544490.32     10460897.96
      3544477.67     10460832.62      3544510.38     10460816.05
      3544599.79     10460919.39      3544722.02     10460787.81
      3544729.17     10460727.47      3544971.29     10460619.03
      3545159.15     10460465.83      3545310.99     10460460.55
      3545433.05     10460338.56      3545431.79      10460225.6
      3545616.03     10460053.21      3545625.63     10459933.01
      3545702.33     10459862.24      3545964.18     10459866.68
       3545966.3     10459723.77      3546049.75     10459671.78
      3545991.82     10459416.64      3546171.96     10459108.04
       3546130.3     10458985.64      3546313.63      10458734.6
      3546425.61     10458605.95      3546538.63     10458570.02
       3546709.5     10458316.95      3546841.43     10458263.05
      3547001.92     10458350.93      3547010.54     10458252.29
      3547141.19     10458157.21      3547222.11     10458221.64

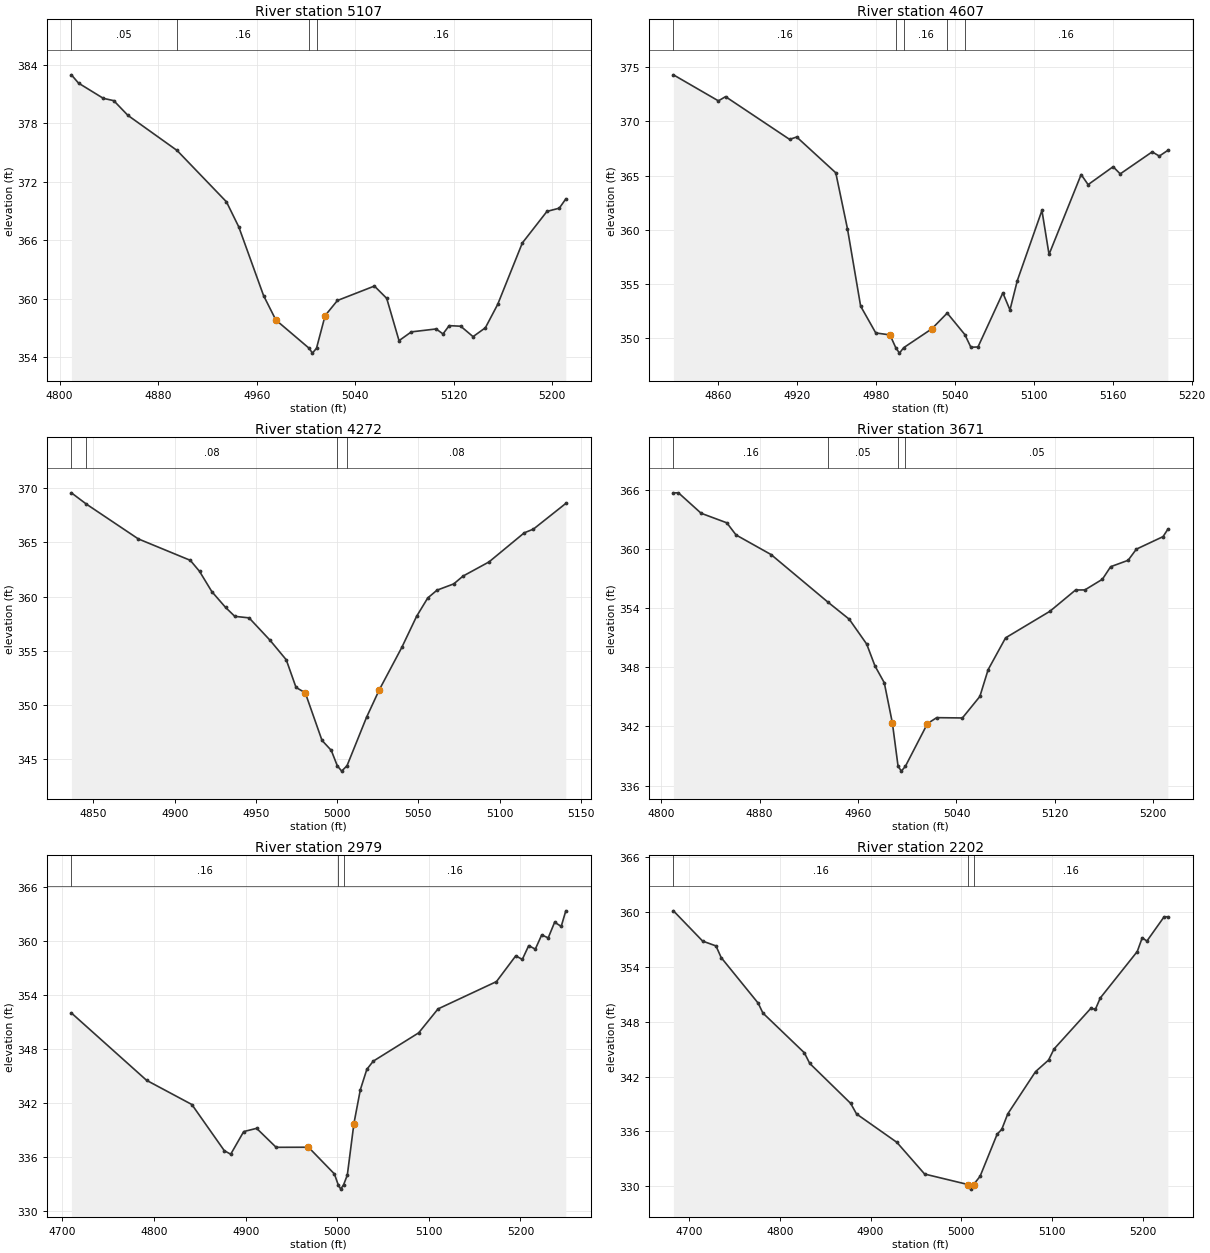
Type RM Length L Ch R = 1 ,5107    ,500,500,500
BEGIN DESCRIPTION:
UNT02241 IN SAND CR 11.0
END DESCRIPTION:
XS GIS Cut Line= 2
      3544438.54     10461067.48      3544423.36     10460666.37
#Sta/Elev= 30
  4809.6  382.97  4815.4  382.12  4835.5  380.56    4844  380.32  4855.5  378.81
  4895.4  375.21  4935.5  369.94  4945.5  367.37  4965.6  360.33  4975.6  357.82
  5002.6  354.92  5005.3  354.42  5008.6  354.92  5015.6  358.27  5025.6  359.82
  5055.6   361.3  5065.6  360.04  5075.6   355.7  5085.6   356.6  5105.7   356.9
  5111.3  356.39  5116.3  357.24  5125.7  357.18  5135.7  356.11  5145.7  357.02
  5155.7  359.42  5175.7  365.72  5195.7  368.96  5205.7  369.29    5211  370.24
#Mann= 4 ,-1 , 0
  4809.6     .05       0  4895.4     .16       0  5002.6     .07       0
  5008.6     .16       0
Bank Sta=4975.6,5015.6
XS Rating Curve= 0 ,0
Exp/Cntr=0.3,0.1

Type RM Length L Ch R = 1 ,4607    ,335,335,335
BEGIN DESCRIPTION:
UNT02241 IN SAND CR 10.0
END DESCRIPTION:
XS GIS Cut Line= 2
      3544741.22     10460974.66      3544602.85     10460625.27
#Sta/Elev= 30
    4826   374.3  4860.2   371.9  4865.6  372.29  4914.3  368.35  4919.7  368.57
  4949.4  365.27  4958.3   360.1  4968.3  352.98  4979.8  350.51  4990.6  350.33
    4995  349.15  4997.8  348.65    5001  349.15  5022.4  350.89  5034.1  352.34
  5047.5  350.36  5052.1  349.19  5057.5  349.22  5076.4   354.2  5081.8  352.63
  5087.4  355.34  5106.1   361.8  5111.5  357.75  5135.9  365.11  5141.2  364.18
  5160.2  365.83  5165.6  365.17  5189.9   367.2  5195.3  366.81  5201.8  367.34
#Mann= 5 ,-1 , 0
    4826     .16       0    4995     .07       0    5001     .16       0
  5034.1     .08       0  5047.5     .16       0
Bank Sta=4990.6,5022.4
XS Rating Curve= 0 ,0
Exp/Cntr=0.3,0.1

Type RM Length L Ch R = 1 ,4272    ,601,601,601
BEGIN DESCRIPTION:
UNT02241 IN SAND CR 9.0
END DESCRIPTION:
XS GIS Cut Line= 2
      3544994.69     10460787.14      3544846.27     10460521.38
#Sta/Elev= 30
  4836.4  369.59  4845.7  368.54  4877.6  365.33  4909.6  363.35  4915.3  362.33
  4922.9  360.45  4931.3     359    4937  358.17  4945.8  358.03  4958.7  355.96
  4968.7  354.15  4974.7   351.6  4980.4   351.1  4990.7   346.7  4996.4  345.78
  5000.1  344.36  5002.8  343.86  5006.1  344.36  5018.1  348.83    5026  351.39
  5039.8  355.29  5048.9  358.16  5055.8  359.87  5061.5  360.59  5071.8  361.17
  5077.5  361.89  5093.5   363.2  5115.2  365.89  5120.9  366.24  5140.8  368.61
#Mann= 4 ,-1 , 0
  4836.4      .1       0  4845.7     .08       0  5000.1     .07       0
  5006.1     .08       0
Bank Sta=4980.4,5026
XS Rating Curve= 0 ,0
Exp/Cntr=0.3,0.1

Type RM Length L Ch R = 1 ,3671    ,692,692,692
BEGIN DESCRIPTION:
UNT02241 IN SAND CR 7.0
END DESCRIPTION:
XS GIS Cut Line= 2
       3545522.5     10460512.89      3545256.14     10460211.94
#Sta/Elev= 30
  4809.9  365.67    4814  365.67  4832.4   363.6  4853.3  362.63  4860.8   361.4
  4889.3  359.41  4935.7  354.57  4952.8  352.86    4967  350.34  4973.7  348.13
  4981.3  346.42  4987.9  342.33  4992.5  337.96  4995.2  337.46  4998.5  337.96
  5016.4  342.28  5023.9  342.88  5044.8  342.85    5059  345.03  5065.7  347.74
  5079.9  350.97  5115.9  353.66  5136.8  355.82  5144.4  355.83  5158.6  356.91
  5165.3  358.18  5179.5  358.83  5186.2  359.96  5207.9  361.23  5211.8  361.98
#Mann= 4 ,-1 , 0
  4809.9     .16       0  4935.7     .05       0  4992.5     .03       0
  4998.5     .05       0
Bank Sta=4987.9,5016.4
XS Rating Curve= 0 ,0
Exp/Cntr=0.3,0.1

Type RM Length L Ch R = 1 ,2979    ,777,777,777
BEGIN DESCRIPTION:
UNT02241 IN SAND CR 6.0
END DESCRIPTION:
XS GIS Cut Line= 2
      3545914.84     10460064.95       3545536.7     10459679.87
#Sta/Elev= 30
  4709.8  352.04  4791.9  344.55  4841.3  341.86  4876.7  336.73  4883.7  336.33
  4897.9  338.85    4912  339.21  4933.3   337.1  4968.6  337.11  4996.9  334.14
    5001  332.95  5003.8  332.45    5007  332.95    5011  334.01  5018.2  339.74
  5025.2   343.5  5032.3  345.77  5039.3  346.68  5088.9  349.83    5110  352.49
  5173.8  355.53  5194.9   358.4    5202  357.99    5209  359.53  5216.2  359.14
  5223.2  360.72  5230.3  360.39  5237.3  362.13  5244.5  361.67  5249.5   363.4
#Mann= 3 ,-1 , 0
  4709.8     .16       0    5001     .07       0    5007     .16       0
Bank Sta=4968.6,5018.2
XS Rating Curve= 0 ,0
Exp/Cntr=0.3,0.1

Type RM Length L Ch R = 1 ,2202    ,324,324,324
BEGIN DESCRIPTION:
UNT02241 IN SAND CR 5.0
END DESCRIPTION:
XS GIS Cut Line= 2
      3546303.75     10459495.51      3545769.01     10459391.34
#Sta/Elev= 30
  4682.8  360.13    4715  356.82  4729.7  356.29  4735.4  355.02  4776.2  350.03
  4781.4  348.95  4827.1   344.6    4833  343.44  4878.1  339.07  4884.6  337.91
    4929  334.81  4959.6  331.34  5007.5  330.19  5010.2  329.69  5013.5  330.19
  5020.7  331.09  5039.5   335.7  5044.6  336.23  5051.2  337.92  5081.8  342.54
  5096.2  343.81  5102.2  345.02  5142.7  349.46  5147.8  349.36  5153.1  350.59
  5193.9  355.68  5199.4  357.19  5204.5  356.82  5223.5  359.48  5227.6  359.48
#Mann= 3 ,-1 , 0
  4682.8     .16       0  5007.5     .07       0  5013.5     .16       0
Bank Sta=5007.5,5013.5
XS Rating Curve= 0 ,0
Exp/Cntr=0.3,0.1

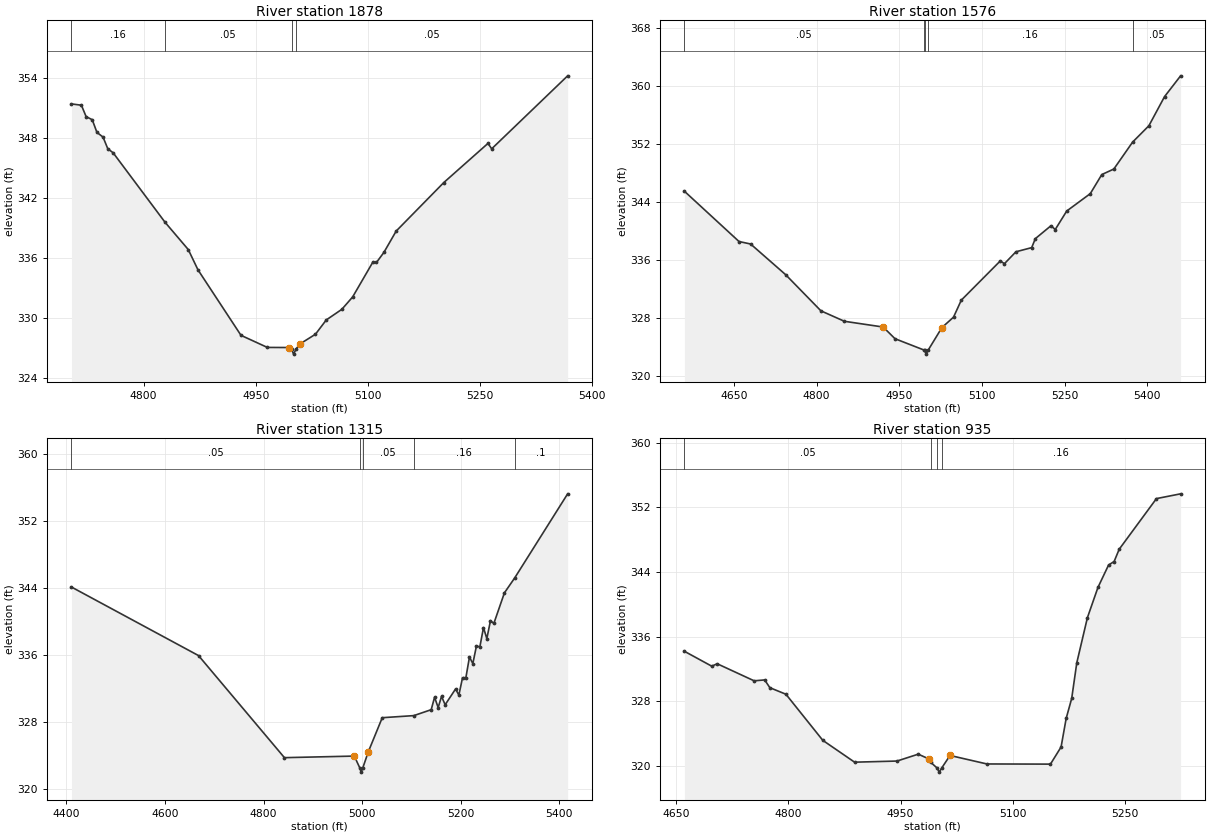
Type RM Length L Ch R = 1 ,1878    ,302,302,302
BEGIN DESCRIPTION:
UNT02241 IN SAND CR 4.0
END DESCRIPTION:
XS GIS Cut Line= 3
      3546366.25      10459335.8      3546046.78     10459089.25
      3545786.75     10459068.45
#Sta/Elev= 30
  4703.4  351.42  4716.7  351.29    4723  350.15  4731.2  349.84  4737.5  348.57
  4745.7   348.1    4752  346.94  4759.2  346.53  4828.7  339.58  4859.8  336.85
  4872.8  334.82  4930.4  328.27  4965.7  327.06  4994.7  327.05  4998.1  326.89
  5000.8  326.39  5004.1  326.89  5009.2   327.4  5030.1  328.38  5044.6  329.81
  5065.4  330.87  5079.9  332.11  5106.7  335.56  5111.8  335.56  5121.7  336.56
  5138.2   338.7  5201.9  343.55  5261.1  347.47  5266.1  346.93  5367.8  354.23
#Mann= 4 ,-1 , 0
  4703.4     .16       0  4828.7     .05       0  4998.1     .03       0
  5004.1     .05       0
Bank Sta=4994.7,5009.2
XS Rating Curve= 0 ,0
Exp/Cntr=0.3,0.1

Type RM Length L Ch R = 1 ,1576    ,261,261,261
BEGIN DESCRIPTION:
UNT02241 IN SAND CR 3.0
END DESCRIPTION:
XS GIS Cut Line= 3
       3546498.2     10459235.11      3546116.23     10458821.89
      3545862.76     10458599.68
#Sta/Elev= 30
  4560.5  345.49  4659.5  338.57  4680.5  338.23    4744  334.01    4808  329.03
  4850.6  327.59  4920.9   326.8  4942.4  325.19  4995.1  323.63  4996.1  323.57
  4998.9  323.07  5002.1  323.57  5027.5  326.73  5048.5  328.16  5062.6   330.5
  5133.3   335.9  5140.8  335.52  5161.7  337.16  5190.2  337.73  5196.9  338.97
  5225.3  340.75  5232.9  340.22  5253.8  342.77  5296.5  345.16  5317.4  347.79
  5339.2  348.55  5373.3  352.26  5402.8  354.51  5431.2  358.52  5460.3  361.38
#Mann= 5 ,-1 , 0
  4560.5     .05       0  4995.1     .16       0  4996.1     .07       0
  5002.1     .16       0  5373.3     .05       0
Bank Sta=4920.9,5027.5
XS Rating Curve= 0 ,0
Exp/Cntr=0.3,0.1

Type RM Length L Ch R = 1 ,1315    ,380,380,380
BEGIN DESCRIPTION:
UNT02241 IN SAND CR 2.0
END DESCRIPTION:
XS GIS Cut Line= 3
      3546612.76     10459186.52      3546591.92       10458933.
       3546039.8     10458422.55
#Sta/Elev= 30
  4410.5  344.13  4668.2  335.93  4842.4  323.72  4984.1  323.91  4995.3  322.49
  4998.1  321.99  5001.3  322.49  5012.5  324.42  5040.8   328.5  5104.8  328.75
  5140.1  329.46  5146.9  330.95  5154.2  329.71    5161  331.05  5168.4  330.05
  5189.4  331.93  5196.2  331.21  5203.6  333.28  5210.4  333.29  5217.7  335.76
  5224.5  334.97  5231.9   337.1  5238.7  336.95  5246.1  339.28  5252.9  337.96
  5260.3  340.11  5267.1  339.77  5288.6  343.44  5309.2   345.2  5416.8  355.28
#Mann= 5 ,-1 , 0
  4410.5     .05       0  4995.3     .03       0  5001.3     .05       0
  5104.8     .16       0  5309.2      .1       0
Bank Sta=4984.1,5012.5
XS Rating Curve= 0 ,0
Exp/Cntr=0.3,0.1

Type RM Length L Ch R = 1 ,935     ,0,0,0
BEGIN DESCRIPTION:
UNT02241 IN SAND CR 1.0
END DESCRIPTION:
XS GIS Cut Line= 2
      3546845.43     10458689.98      3546359.29     10458238.57
#Sta/Elev= 30
  4661.1  334.19  4697.6  332.35  4704.9  332.65  4754.3  330.54  4768.4  330.65
  4775.3  329.69  4796.8  328.88  4846.1  323.18  4888.6  320.48  4945.3  320.62
  4973.7  321.47  4987.8  320.89  4990.6  320.45    4999  319.75  5001.7  319.25
    5005  319.75  5016.2  321.31  5065.5  320.26  5150.5  320.24  5164.7  322.36
  5171.5  325.89  5178.9  328.37  5185.7  332.77  5199.9  338.35    5214  342.09
  5228.2  344.86  5235.6  345.29  5242.4  346.81  5292.2  353.07  5324.5  353.66
#Mann= 4 ,-1 , 0
  4661.1     .05       0  4990.6     .16       0    4999     .07       0
    5005     .16       0
Bank Sta=4987.8,5016.2
XS Rating Curve= 0 ,0
Exp/Cntr=0.3,0.1

Chan Stop Cuts=-1
Use User Specified Reach Order=0
Composite Channel Slope=5