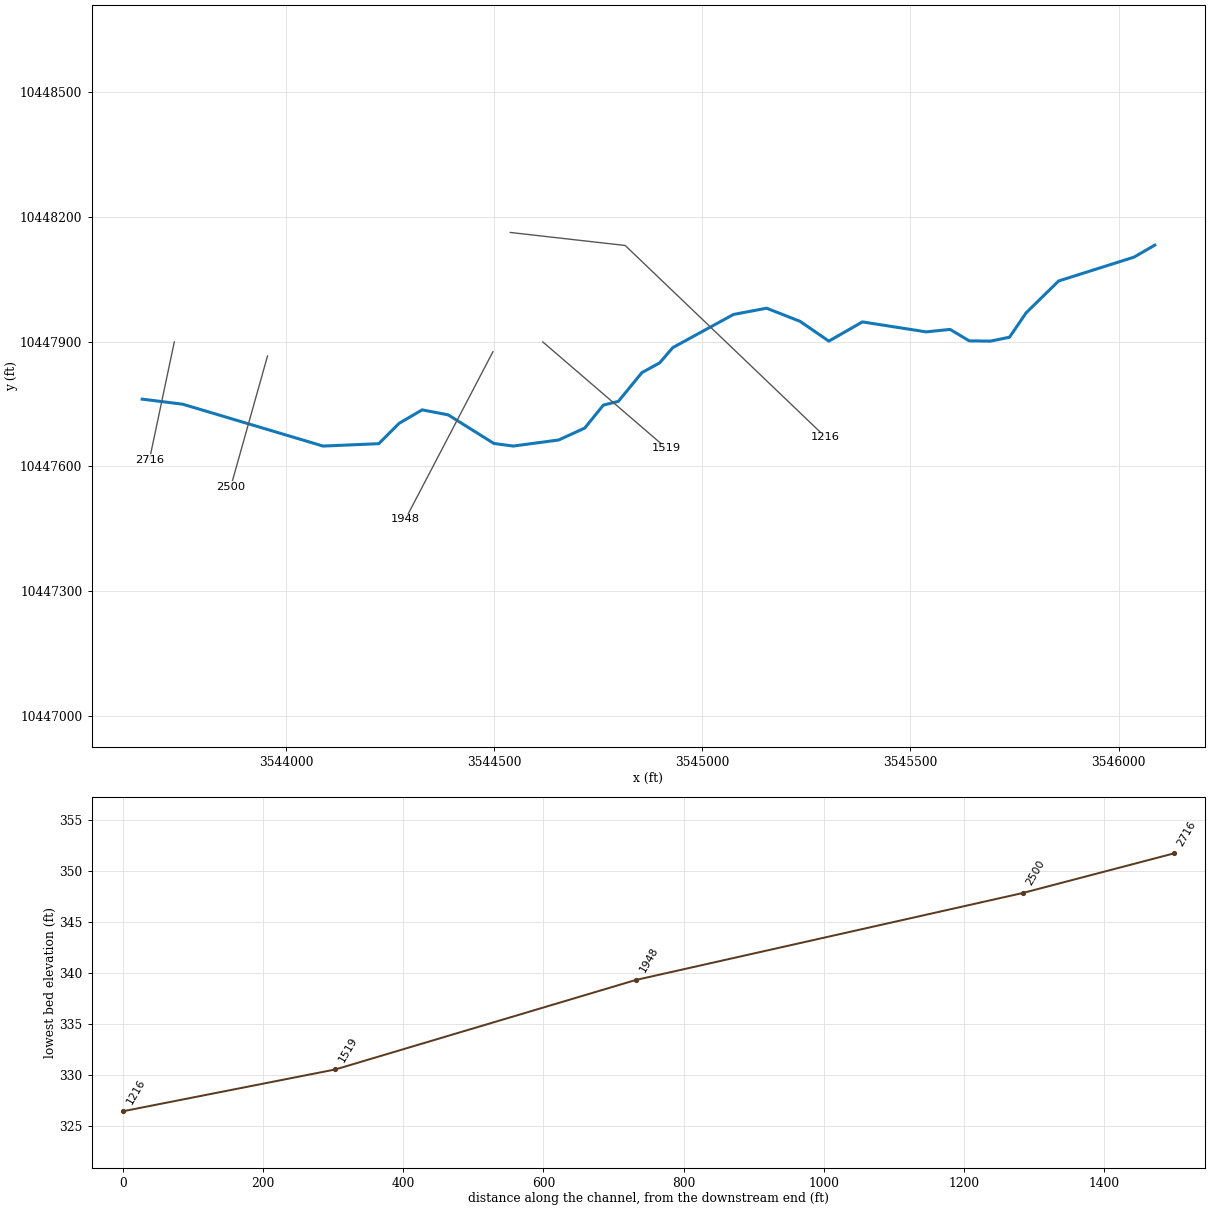
--- NAVASOTARIVTRB91.prj (project) ---

Proj Title=NAVASOTA RIVER TIRBUTARY 9 1
Current Plan=p01
Default Exp/Contr=0.3,0.1
English Units
Geom File=g01
Flow File=f01
Plan File=p01
Y Axis Title=Elevation
X Axis Title(PF)=Main Channel Distance
X Axis Title(XS)=Station
BEGIN DESCRIPTION:
UNT6764 IN SAND CR
END DESCRIPTION:
DSS Export Rating Curves= 0
DSS Export Rating Curve Sorted= 0
DSS Export Volume Flow Curves= 0
DXF OffsetX= 0
DXF OffsetY= 0
DXF ScaleX= 1
DXF ScaleY= 10

--- NAVASOTARIVTRB91.p01 (plan) ---

Plan Title=Multiple Run
Short Identifier=Multiple
Geom File=g01
Flow File=f01
Subcritical Flow
K Sum by GR= 0
Std Step Tol= 0.01
Critical Tol= 0.01
Num of Std Step Trials= 20
Max Error Tol= 0.3
Flow Tol Ratio= 0.001
Split Flow NTrial= 30
Split Flow Tol= 0.02
Split Flow Ratio= 0.02
Log Output Level= 0
Friction Slope Method= 1
Unsteady Friction Slope Method= 2
Unsteady Bridges Friction Slope Method= 1
Parabolic Critical Depth
Global Vel Dist=  1 , 1 , 1
Global Log Level= 0
CheckData=True
Encroach Param= -1, 0, 0, 0
BEGIN DESCRIPTION:
Multiple Run
END DESCRIPTION:

--- NAVASOTARIVTRB91.f01 (steady flow) ---

Flow Title=Multiple
Program Version=4.10
Number of Profiles= 7
Profile Names=10-year,25-year,50-year,1pct_min,100-year,1pct_plu,500-year
River Rch & RM=UNT6764 IN SAND,Reach-1         ,2716
     170     208     235     196     265     359     334
River Rch & RM=AVASOTARIVTRIB91,Reach-1         ,2716
     170     208     235     196     265     359     334
Boundary for River Rch & Prof#=AVASOTARIVTRIB91,Reach-1         , 1
Up Type= 0
Dn Type= 3
Dn Slope=0.005
Boundary for River Rch & Prof#=AVASOTARIVTRIB91,Reach-1         , 2
Up Type= 0
Dn Type= 3
Dn Slope=0.005
Boundary for River Rch & Prof#=AVASOTARIVTRIB91,Reach-1         , 3
Up Type= 0
Dn Type= 3
Dn Slope=0.005
Boundary for River Rch & Prof#=AVASOTARIVTRIB91,Reach-1         , 4
Up Type= 0
Dn Type= 3
Dn Slope=0.005
Boundary for River Rch & Prof#=AVASOTARIVTRIB91,Reach-1         , 5
Up Type= 0
Dn Type= 3
Dn Slope=0.005
Boundary for River Rch & Prof#=AVASOTARIVTRIB91,Reach-1         , 6
Up Type= 0
Dn Type= 3
Dn Slope=0.005
Boundary for River Rch & Prof#=AVASOTARIVTRIB91,Reach-1         , 7
Up Type= 0
Dn Type= 3
Dn Slope=0.005
DSS Import GetInterval= 0
DSS Import GetPeak= 0
DSS Import FillOption= 0

--- NAVASOTARIVTRB91.g01 (geometry) ---

Geom Title=Existing Conditions
Program Version=4.10

River Reach=AVASOTARIVTRIB91,Reach-1
Reach XY= 30
       3543654.1     10447761.54      3543751.76      10447749.3
      3544088.74     10447648.78      3544222.59     10447654.51
      3544271.55     10447703.46      3544326.76     10447735.76
      3544389.26     10447723.78      3544499.15     10447655.03
      3544545.51     10447648.78      3544654.88     10447663.36
      3544717.38     10447692.01      3544762.18     10447747.21
      3544798.11     10447756.07      3544854.88     10447825.34
      3544897.59     10447848.78      3544928.84     10447885.24
      3545074.68     10447964.92      3545154.36     10447980.03
      3545234.56     10447948.48        3545304.     10447900.91
      3545384.56     10447947.09      3545537.68     10447923.13
      3545595.32     10447929.03      3545641.15      10447901.6
      3545692.19     10447900.91      3545738.03     10447910.28
      3545777.96     10447968.97      3545856.13     10448045.48
      3546036.95      10448102.6      3546087.04     10448131.53

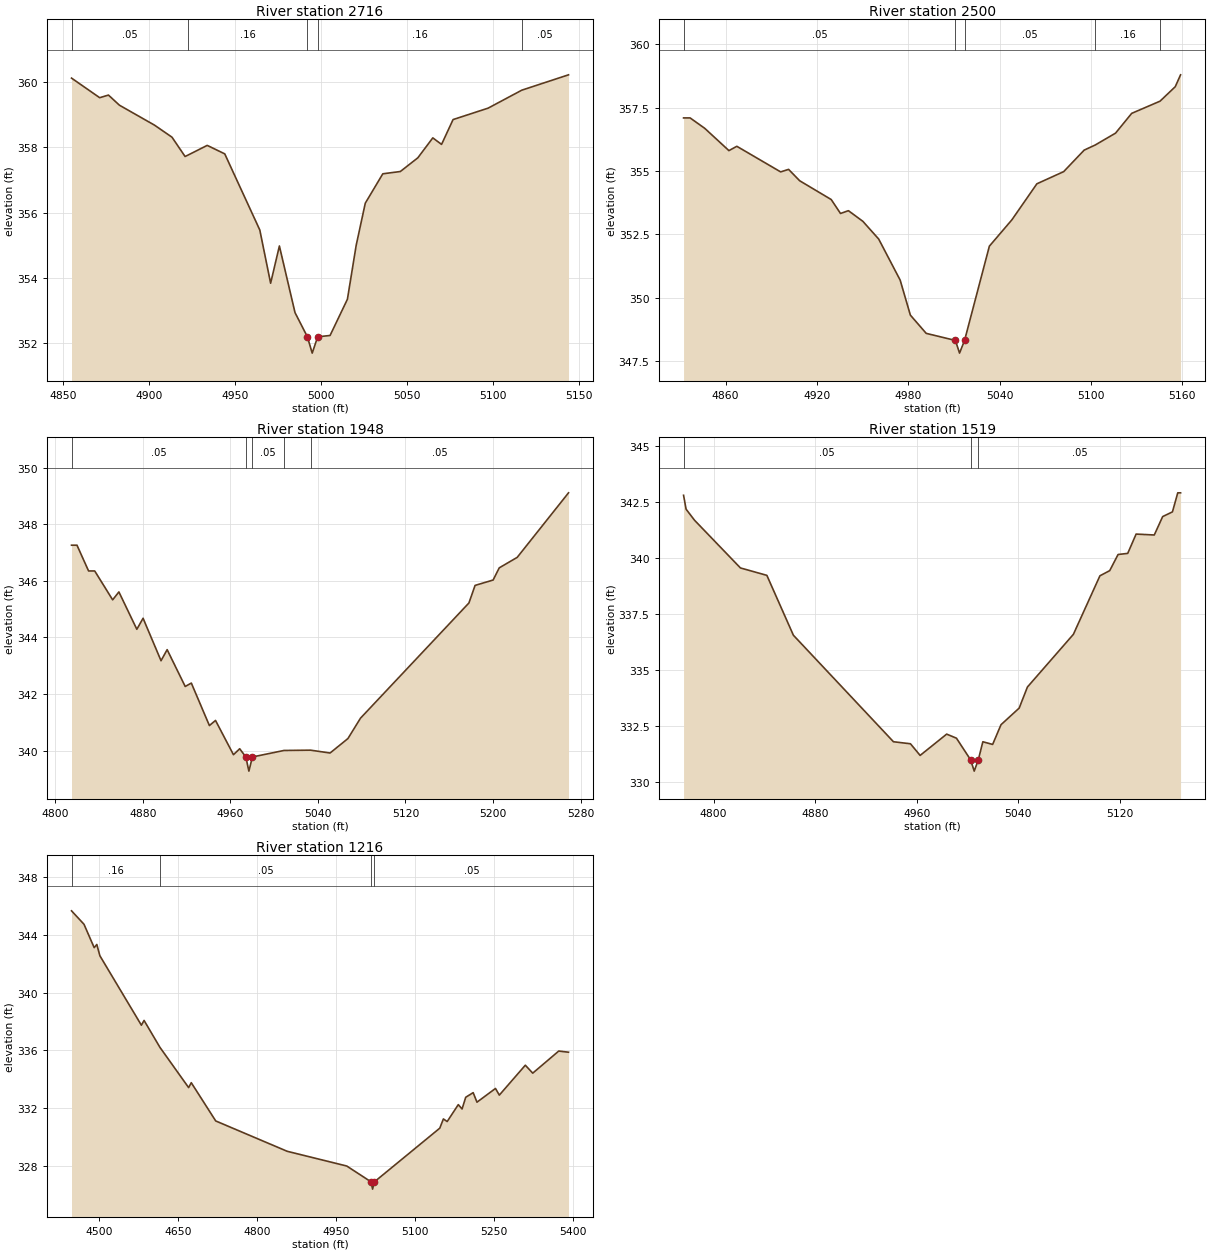
Type RM Length L Ch R = 1 ,2716    ,216,216,216
BEGIN DESCRIPTION:
UNT6764 IN SAND CR 4.1
END DESCRIPTION:
XS GIS Cut Line= 2
      3543731.27     10447898.92      3543671.54     10447615.86
#Sta/Elev= 30
  4854.8  360.12  4871.2  359.52  4876.3   359.6  4882.7  359.29  4903.1  358.68
  4913.3  358.31  4920.9  357.72  4922.5  357.76  4933.8  358.06    4944   357.8
  4964.4  355.47  4970.7  353.84  4975.8  354.98  4984.9  352.94  4992.1   352.2
  4994.9   351.7  4998.1   352.2  5005.3  352.24  5015.4  353.35  5020.5     355
  5025.8  356.29    5036  357.19  5046.2  357.26  5056.4  357.68  5065.1  358.29
  5070.2  358.09  5076.9  358.85  5097.3   359.2  5116.9  359.75  5144.1  360.22
#Mann= 5 ,-1 , 0
  4854.8     .05       0  4922.5     .16       0  4992.1     .07       0
  4998.1     .16       0  5116.9     .05       0
Bank Sta=4992.1,4998.1
XS Rating Curve= 0 ,0
Exp/Cntr=0.3,0.1

Type RM Length L Ch R = 1 ,2500    ,552,552,552
BEGIN DESCRIPTION:
UNT6764 IN SAND CR 4.0
END DESCRIPTION:
XS GIS Cut Line= 2
      3543955.22     10447865.05       3543866.9     10447550.73
#Sta/Elev= 30
  4832.4  357.09  4836.7  357.09  4846.3  356.68  4862.2   355.8  4867.4  355.97
  4896.2  354.96  4901.4  355.06  4908.7  354.61  4929.4  353.87  4935.5  353.32
  4940.7  353.43  4950.2  353.01  4960.6  352.31  4974.7  350.69  4981.4  349.31
  4991.8  348.59    5011  348.31  5013.7  347.81    5017  348.31  5033.3  352.03
  5048.1  353.07  5064.5  354.49  5082.1  354.97  5095.6  355.82  5102.8  356.02
  5116.2  356.49  5126.8  357.27  5145.4  357.75  5155.4  358.32  5158.9  358.79
#Mann= 5 ,-1 , 0
  4832.4     .05       0    5011     .03       0    5017     .05       0
  5102.8     .16       0  5145.4     .05       0
Bank Sta=5011,5017
XS Rating Curve= 0 ,0
Exp/Cntr=0.3,0.1

Type RM Length L Ch R = 1 ,1948    ,429,429,429
BEGIN DESCRIPTION:
UNT6764 IN SAND CR 3.0
END DESCRIPTION:
XS GIS Cut Line= 2
      3544496.89      10447875.5      3544286.53     10447472.95
#Sta/Elev= 30
  4814.8  347.26  4819.8  347.26  4830.4  346.35    4836  346.35  4852.4  345.33
  4858.1  345.61  4874.5  344.29  4880.2  344.68  4896.6  343.18  4902.2  343.57
  4918.7  342.27  4924.3  342.39  4940.8  340.89  4946.4  341.07  4962.8  339.86
  4968.5  340.07  4974.1  339.78  4976.9  339.28  4980.1  339.78    5009  340.01
  5033.3  340.02  5051.1  339.92  5067.4  340.43  5078.9  341.15    5178  345.22
  5183.6  345.84  5200.1  346.03  5205.7  346.46  5222.1  346.83    5269  349.11
#Mann= 5 ,-1 , 0
  4814.8     .05       0  4974.1     .03       0  4980.1     .05       0
    5009     .16       0  5033.3     .05       0
Bank Sta=4974.1,4980.1
XS Rating Curve= 0 ,0
Exp/Cntr=0.3,0.1

Type RM Length L Ch R = 1 ,1519    ,303,303,303
BEGIN DESCRIPTION:
UNT6764 IN SAND CR 2.0
END DESCRIPTION:
XS GIS Cut Line= 2
      3544616.73     10447898.92      3544913.53     10447643.77
#Sta/Elev= 30
  4776.3   342.8  4778.3  342.18  4784.9  341.69  4821.1  339.56  4841.9  339.23
  4862.8  336.56  4941.6  331.81    4955  331.72  4962.6   331.2  4983.5  332.15
  4991.2  331.97  5002.4     331  5005.2   330.5  5008.4     331    5012  331.81
  5019.7  331.69  5026.3  332.57  5040.6  333.31  5047.1  334.25  5083.3   336.6
  5104.2  339.21  5111.9  339.44  5118.5  340.16  5126.1  340.21  5132.7  341.07
    5147  341.03  5153.6  341.85  5161.3  342.06  5165.5  342.91  5167.7  342.91
#Mann= 3 ,-1 , 0
  4776.3     .05       0  5002.4     .03       0  5008.4     .05       0
Bank Sta=5002.4,5008.4
XS Rating Curve= 0 ,0
Exp/Cntr=0.3,0.1

Type RM Length L Ch R = 1 ,1216    ,0,0,0
BEGIN DESCRIPTION:
UNT6764 IN SAND CR 1.0
END DESCRIPTION:
XS GIS Cut Line= 3
      3544538.53     10448161.97      3544814.61     10448130.72
      3545296.38     10447669.78
#Sta/Elev= 30
  4447.3  345.67    4471  344.74  4490.4  343.12  4495.4  343.34  4501.2  342.56
  4580.1  337.75  4585.2  338.08  4615.3  336.22  4669.9  333.43  4674.9  333.77
  4721.4  331.12  4857.2  329.02  4970.4     328  5016.8   326.9  5019.5   326.4
  5022.8   326.9  5147.2  330.62  5154.1  331.26  5161.3  331.08  5182.4  332.25
  5189.6  331.95  5196.5  332.76  5210.7  333.08  5217.9  332.42  5253.1  333.37
  5260.4  332.91  5309.8  334.98  5323.9  334.43  5373.3  335.96  5391.9  335.88
#Mann= 4 ,-1 , 0
  4447.3     .16       0  4615.3     .05       0  5016.8     .03       0
  5022.8     .05       0
Bank Sta=5016.8,5022.8
XS Rating Curve= 0 ,0
Exp/Cntr=0.3,0.1

Chan Stop Cuts=-1
Use User Specified Reach Order=0
Composite Channel Slope=5