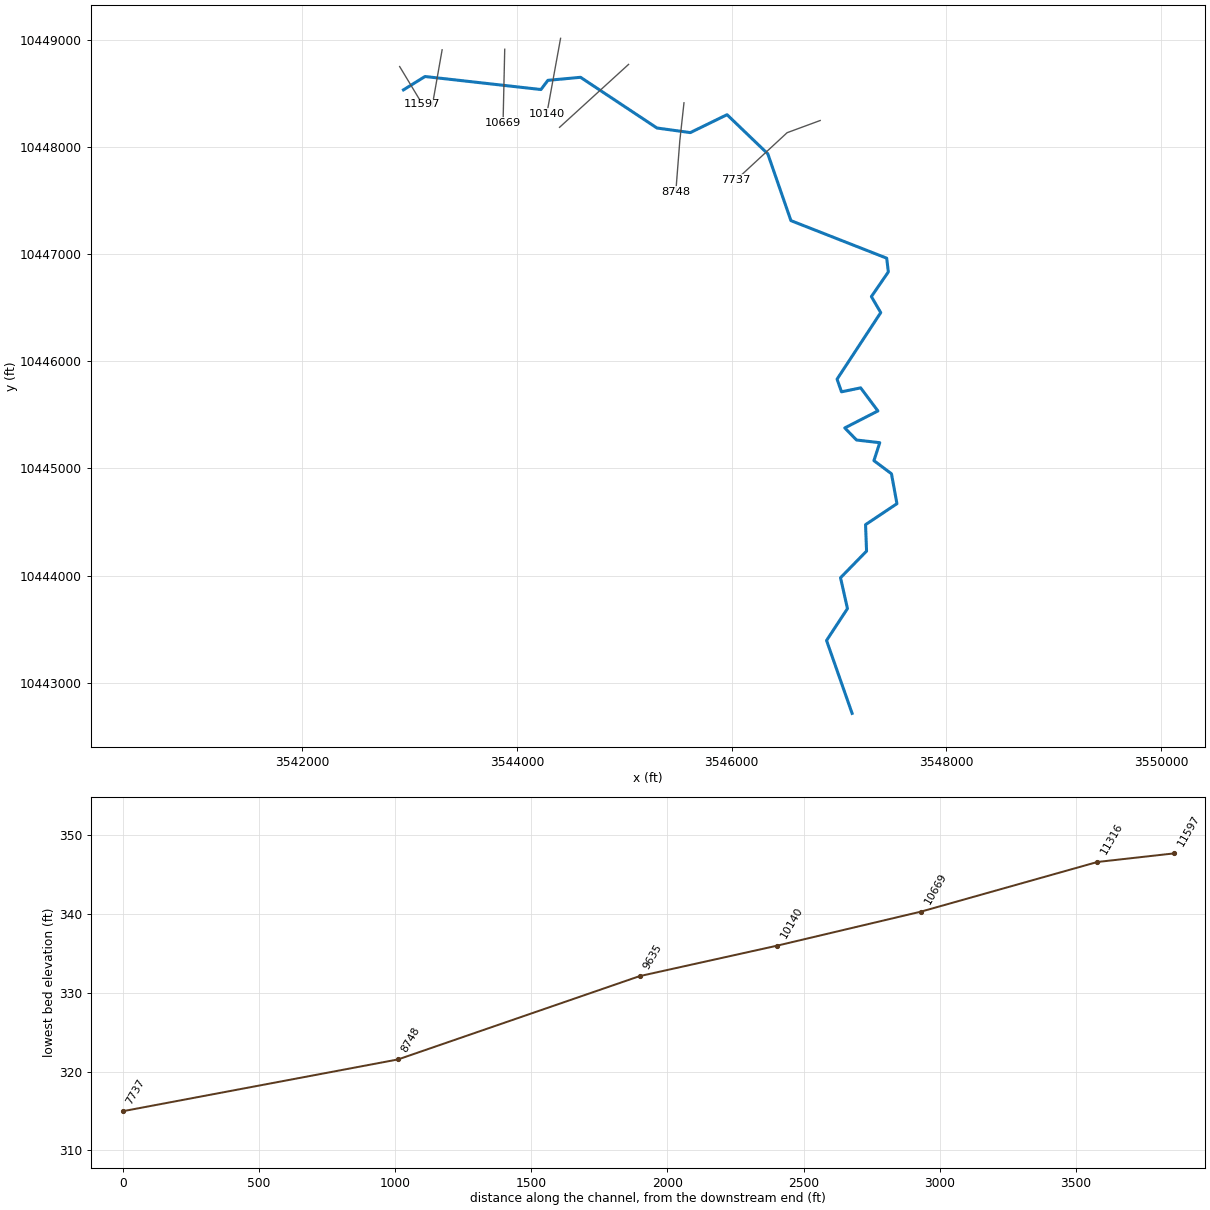
--- NAVRIVTRIB9.prj (project) ---

Proj Title=NAV RIV TRIB 9 Base Level Engineerin
Current Plan=p01
Default Exp/Contr=0.3,0.1
English Units
Geom File=g01
Flow File=f01
Plan File=p01
Y Axis Title=Elevation
X Axis Title(PF)=Main Channel Distance
X Axis Title(XS)=Station
BEGIN DESCRIPTION:
UNT0200 IN SAND CR
END DESCRIPTION:
DSS Export Rating Curves= 0
DSS Export Rating Curve Sorted= 0
DSS Export Volume Flow Curves= 0
DXF OffsetX= 0
DXF OffsetY= 0
DXF ScaleX= 1
DXF ScaleY= 10

--- NAVRIVTRIB9.p01 (plan) ---

Plan Title=Multiple Run
Short Identifier=Multiple
Geom File=g01
Flow File=f01
Subcritical Flow
K Sum by GR= 0
Std Step Tol= 0.01
Critical Tol= 0.01
Num of Std Step Trials= 20
Max Error Tol= 0.3
Flow Tol Ratio= 0.001
Split Flow NTrial= 30
Split Flow Tol= 0.02
Split Flow Ratio= 0.02
Log Output Level= 0
Friction Slope Method= 1
Unsteady Friction Slope Method= 2
Unsteady Bridges Friction Slope Method= 1
Parabolic Critical Depth
Global Vel Dist=  1 , 1 , 1
Global Log Level= 0
CheckData=True
Encroach Param= -1, 0, 0, 0
BEGIN DESCRIPTION:
Multiple Run
END DESCRIPTION:

--- NAVRIVTRIB9.f01 (steady flow) ---

Flow Title=Multiple
Program Version=4.10
Number of Profiles= 7
Profile Names=10-year,25-year,50-year,1pct_min,100-year,1pct_plu,500-year
River Rch & RM=UNT0200 IN SAND,Reach-1         ,11597
     515     682     816     714     965    1305    1346
River Rch & RM=UNT0200 IN SAND,Reach-1         ,7737
     962    1317    1608    1433    1938    2620    2805
River Rch & RM=IVER TRIBUTARY 9,Reach-1.        ,11597
     515     682     816     714     965    1305    1346
River Rch & RM=IVER TRIBUTARY 9,Reach-1.        ,7737
     962    1317    1608    1433    1938    2620    2805
River Rch & RM=NAVASOTA RIVER T,Reach-1.        ,11597
     515     682     816     714     965    1305    1346
River Rch & RM=NAVASOTA RIVER T,Reach-1.        ,7737
     962    1317    1608    1433    1938    2620    2805
Boundary for River Rch & Prof#=NAVASOTA RIVER T,Reach-1.        , 1
Up Type= 0
Dn Type= 3
Dn Slope=0.005
Boundary for River Rch & Prof#=NAVASOTA RIVER T,Reach-1.        , 2
Up Type= 0
Dn Type= 3
Dn Slope=0.005
Boundary for River Rch & Prof#=NAVASOTA RIVER T,Reach-1.        , 3
Up Type= 0
Dn Type= 3
Dn Slope=0.005
Boundary for River Rch & Prof#=NAVASOTA RIVER T,Reach-1.        , 4
Up Type= 0
Dn Type= 3
Dn Slope=0.005
Boundary for River Rch & Prof#=NAVASOTA RIVER T,Reach-1.        , 5
Up Type= 0
Dn Type= 3
Dn Slope=0.005
Boundary for River Rch & Prof#=NAVASOTA RIVER T,Reach-1.        , 6
Up Type= 0
Dn Type= 3
Dn Slope=0.005
Boundary for River Rch & Prof#=NAVASOTA RIVER T,Reach-1.        , 7
Up Type= 0
Dn Type= 3
Dn Slope=0.005
DSS Import GetInterval= 0
DSS Import GetPeak= 0
DSS Import FillOption= 0

--- NAVRIVTRIB9.g01 (geometry) ---

Geom Title=Existing Conditions
Program Version=4.10

River Reach=NAVASOTA RIVER T,Reach-1.
Reach XY= 30
      3542941.27     10448530.38      3543141.79     10448655.05
      3544222.34     10448533.64      3544287.31     10448619.61
      3544591.55     10448647.64      3545303.42     10448174.86
      3545614.38     10448131.96      3545956.83     10448299.06
      3546336.47     10447934.02      3546552.07     10447311.11
      3547444.51     10446960.81      3547459.91     10446832.82
      3547301.86     10446602.66      3547389.09     10446453.47
      3546981.95      10445832.5      3547023.32     10445714.69
      3547201.92     10445751.42      3547362.54     10445536.26
      3547053.85     10445377.79      3547163.57     10445265.13
      3547380.02     10445240.29      3547325.58     10445072.86
      3547488.93      10444950.5      3547539.93     10444671.37
      3547247.57     10444475.81      3547256.82     10444229.12
      3547014.37     10443980.76      3547078.82     10443692.99
      3546884.03     10443395.72      3547122.17      10442715.9

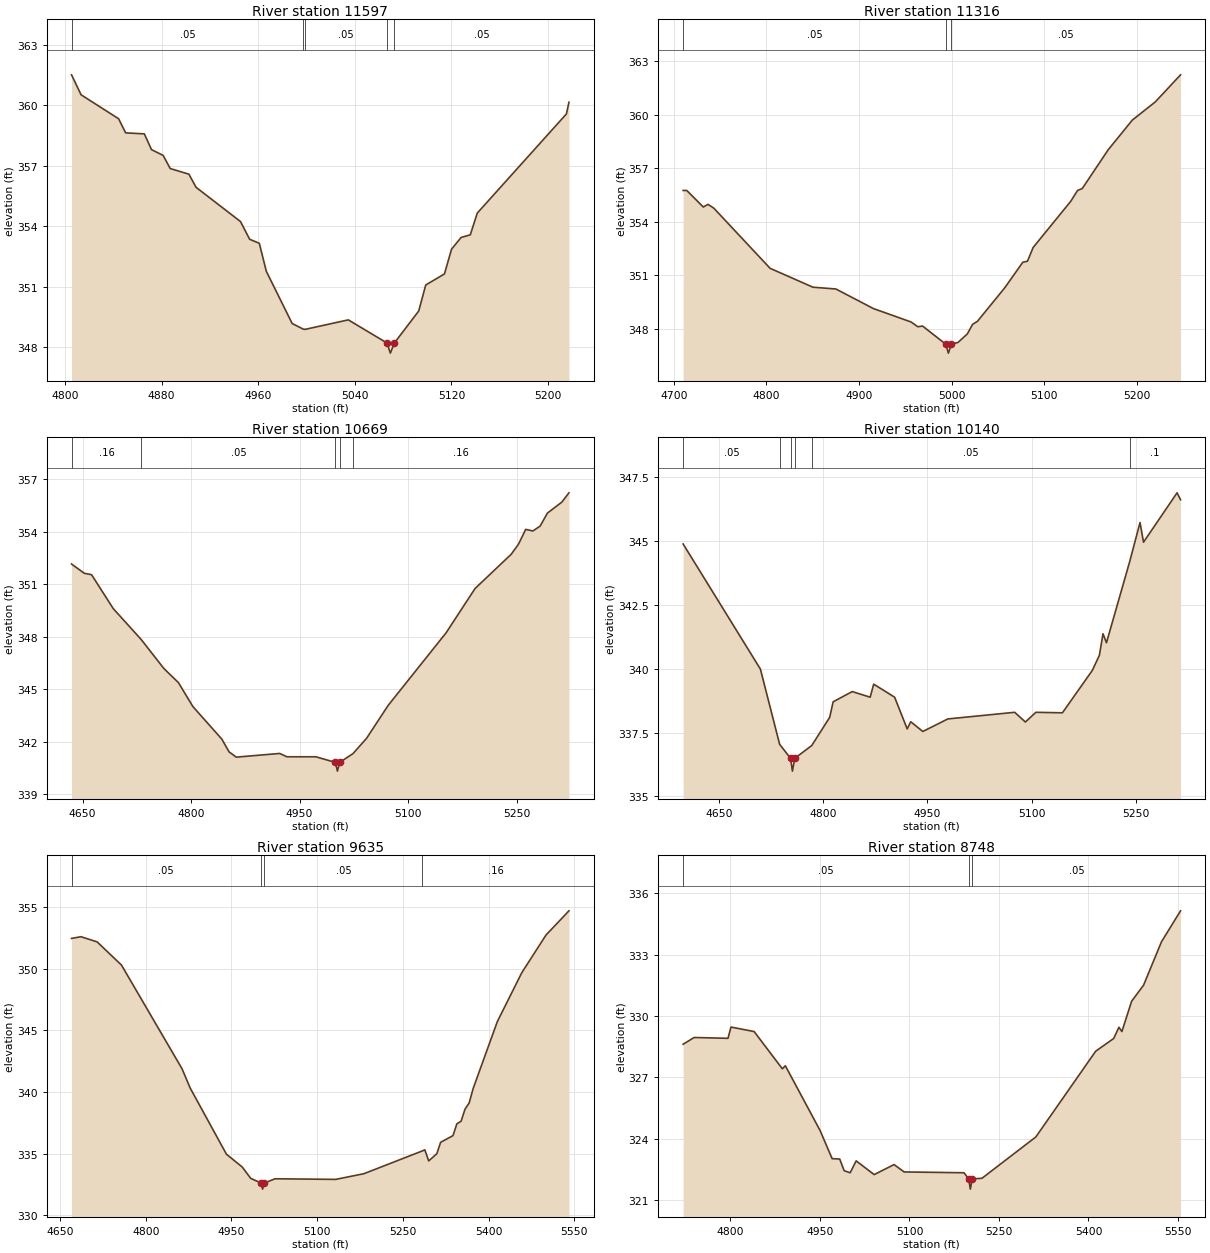
Type RM Length L Ch R = 1 ,11597   ,281,281,281
BEGIN DESCRIPTION:
UNT0200 IN SAND CR 13.0
END DESCRIPTION:
XS GIS Cut Line= 2
      3542905.73     10448747.94      3543118.41      10448395.2
#Sta/Elev= 30
  4805.4  361.52  4813.3  360.53  4844.4  359.34  4850.2  358.64  4865.7  358.59
  4871.6  357.81  4881.3  357.52  4887.1  356.87  4902.6  356.59  4908.5  355.94
  4945.3  354.24  4952.9  353.36  4960.9  353.16  4966.7  351.77  4988.1  349.18
  4997.3   348.9  4998.9  348.89  5034.6  349.36  5066.7  348.21  5069.4  347.71
  5072.7  348.21  5092.9   349.8  5098.7  351.09  5114.2  351.64  5120.1  352.87
    5128  353.45  5135.6  353.58  5141.4  354.66  5215.2  359.58  5217.3  360.16
#Mann= 5 ,-1 , 0
  4805.4     .05       0  4997.3      .1       0  4998.9     .05       0
  5066.7     .03       0  5072.7     .05       0
Bank Sta=5066.7,5072.7
XS Rating Curve= 0 ,0
Exp/Cntr=0.3,0.1

Type RM Length L Ch R = 1 ,11316   ,647,647,647
BEGIN DESCRIPTION:
UNT0200 IN SAND CR 13.1
END DESCRIPTION:
XS GIS Cut Line= 2
      3543301.59     10448904.19      3543208.17     10448374.77
#Sta/Elev= 30
  4709.9  355.75  4713.8  355.75  4731.7  354.82  4736.8  354.97    4743  354.76
  4803.9  351.38  4850.2  350.32    4875  350.22  4915.6  349.12  4956.2  348.37
  4963.6   348.1  4968.7  348.14  4993.8  347.12  4996.6  346.62  4999.8  347.12
    5007  347.22  5017.1   347.7  5022.8  348.24  5027.9   348.4  5057.7   350.3
    5077  351.72  5082.1  351.78  5088.2  352.55  5128.8  355.14  5136.2  355.75
  5141.3  355.86  5169.4  358.04  5195.4   359.7  5220.2  360.72  5247.5  362.24
#Mann= 3 ,-1 , 0
  4709.9     .05       0  4993.8     .03       0  4999.8     .05       0
Bank Sta=4993.8,4999.8
XS Rating Curve= 0 ,0
Exp/Cntr=0.3,0.1

Type RM Length L Ch R = 1 ,10669   ,529,529,529
BEGIN DESCRIPTION:
UNT0200 IN SAND CR 11.0
END DESCRIPTION:
XS GIS Cut Line= 2
      3543884.92     10448909.37      3543869.29     10448221.85
#Sta/Elev= 30
  4634.8  352.16  4652.5  351.63  4662.5  351.55  4692.5  349.61  4731.2  347.84
  4762.6  346.18  4782.6  345.38  4802.6  344.01  4842.6  342.15  4852.6  341.42
  4862.6  341.12  4922.6  341.33  4932.6  341.14  4972.6  341.14  4999.6  340.82
  5002.4  340.32  5005.6  340.82  5023.9  341.32  5042.6  342.19  5072.6  344.08
  5152.7  348.23  5192.7  350.76  5242.7  352.72  5252.7  353.29  5262.7  354.14
  5272.7  354.05  5282.7  354.33  5292.7  355.07  5312.7   355.7  5322.5  356.23
#Mann= 5 ,-1 , 0
  4634.8     .16       0  4731.2     .05       0  4999.6     .03       0
  5005.6     .05       0  5023.9     .16       0
Bank Sta=4999.6,5005.6
XS Rating Curve= 0 ,0
Exp/Cntr=0.3,0.1

Type RM Length L Ch R = 1 ,10140   ,505,505,505
BEGIN DESCRIPTION:
UNT0200 IN SAND CR 10.1
END DESCRIPTION:
XS GIS Cut Line= 2
      3544405.46     10449011.08       3544277.1     10448306.78
#Sta/Elev= 30
  4598.5  344.87  4709.7  339.98  4737.4  337.04  4753.1  336.49  4755.8  335.99
  4759.1  336.49  4783.6  336.99  4809.4  338.09  4814.4   338.7  4841.9   339.1
  4867.7  338.88  4872.8  339.39  4902.9  338.88    4921  337.64  4926.1  337.92
  4943.5  337.54  4979.4  338.03  5075.7  338.29  5091.1  337.91  5106.2  338.29
  5144.4  338.27  5187.5  339.93  5197.6  340.52  5202.8  341.36  5207.8  341.01
  5241.1  344.17  5256.1  345.71  5261.1  344.94  5309.4  346.87  5314.4   346.6
#Mann= 6 ,-1 , 0
  4598.5     .05       0  4737.4     .16       0  4753.1     .03       0
  4759.1     .16       0  4783.6     .05       0  5241.1      .1       0
Bank Sta=4753.1,4759.1
XS Rating Curve= 0 ,0
Exp/Cntr=0.3,0.1

Type RM Length L Ch R = 1 ,9635    ,887,887,887
BEGIN DESCRIPTION:
UNT0200 IN SAND CR 10.0
END DESCRIPTION:
XS GIS Cut Line= 2
      3545038.97       10448768.      3544395.78     10448181.12
#Sta/Elev= 30
    4670  352.46  4686.5   352.6  4714.8  352.18  4757.4   350.3  4863.5  341.88
  4877.6  340.33  4941.2  334.95  4968.7  333.92  4983.7  332.99  5001.7  332.62
  5004.4  332.12  5007.7  332.62  5026.3  332.96  5132.4  332.91  5181.7  333.37
  5284.1  335.22  5288.4  335.31  5295.2  334.41  5309.4  334.99  5316.1  335.92
  5337.7  336.46  5344.5  337.42  5351.9  337.63  5358.7   338.6  5366.1  339.12
  5372.9  340.27  5415.4  345.72    5458  349.67  5500.6  352.74  5540.7   354.7
#Mann= 4 ,-1 , 0
    4670     .05       0  5001.7     .03       0  5007.7     .05       0
  5284.1     .16       0
Bank Sta=5001.7,5007.7
XS Rating Curve= 0 ,0
Exp/Cntr=0.3,0.1

Type RM Length L Ch R = 1 ,8748    ,1011,1011,1011
BEGIN DESCRIPTION:
UNT0200 IN SAND CR 9.0
END DESCRIPTION:
XS GIS Cut Line= 3
      3545555.46      10448409.9      3545516.41     10448054.03
      3545479.35     10447579.88
#Sta/Elev= 30
  4720.7  328.62  4739.1  328.95  4795.9  328.91  4800.9  329.46  4839.7  329.24
    4887  327.42    4892  327.57  4950.3   324.4  4970.4  323.03  4983.1  323.01
  4990.6  322.44  5000.6  322.34  5010.7  322.92  5040.9  322.25  5074.2  322.74
  5091.1  322.38  5191.4  322.34  5199.3  322.04    5202  321.54  5205.3  322.04
  5221.5  322.07  5311.8  324.09  5412.1  328.28  5442.2   328.9    5451  329.45
    5456  329.24  5472.3  330.72  5492.4  331.51  5522.4  333.63  5554.3  335.14
#Mann= 3 ,-1 , 0
  4720.7     .05       0  5199.3     .03       0  5205.3     .05       0
Bank Sta=5199.3,5205.3
XS Rating Curve= 0 ,0
Exp/Cntr=0.3,0.1

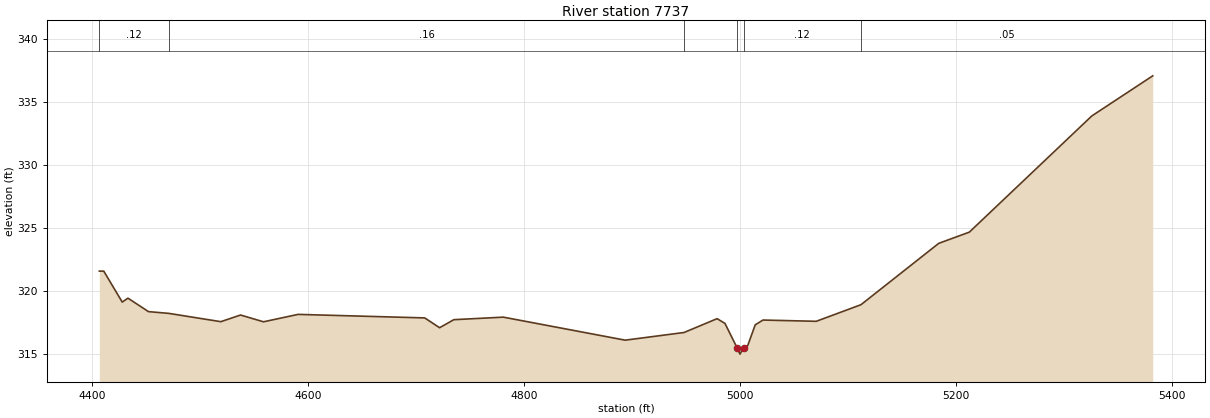
Type RM Length L Ch R = 1 ,7737    ,0,0,0
BEGIN DESCRIPTION:
UNT0200 IN SAND CR 1.0
END DESCRIPTION:
XS GIS Cut Line= 3
      3546824.77     10448244.79      3546516.57      10448131.2
      3546042.14     10447691.67
#Sta/Elev= 30
  4406.7  321.56  4410.8  321.56  4427.9   319.1  4433.2  319.41  4452.2  318.34
    4471   318.2  4519.2  317.54  4537.4  318.07  4558.7  317.53  4590.7  318.12
  4707.9  317.84  4721.7  317.06  4734.9   317.7  4780.7   317.9  4893.5  316.07
    4948  316.68  4978.6  317.78  4985.9   317.4  4997.1  315.46  4999.8  314.96
  5003.1  315.46  5006.9  315.63  5013.9  317.29  5021.1  317.67  5070.4  317.57
  5111.8  318.89  5183.8  323.77  5212.1  324.66  5325.5   333.9  5381.9  337.09
#Mann= 6 ,-1 , 0
  4406.7     .12       0    4471     .16       0    4948     .12       0
  4997.1     .07       0  5003.1     .12       0  5111.8     .05       0
Bank Sta=4997.1,5003.1
XS Rating Curve= 0 ,0
Exp/Cntr=0.3,0.1

Chan Stop Cuts=-1
Use User Specified Reach Order=0
Composite Channel Slope=5