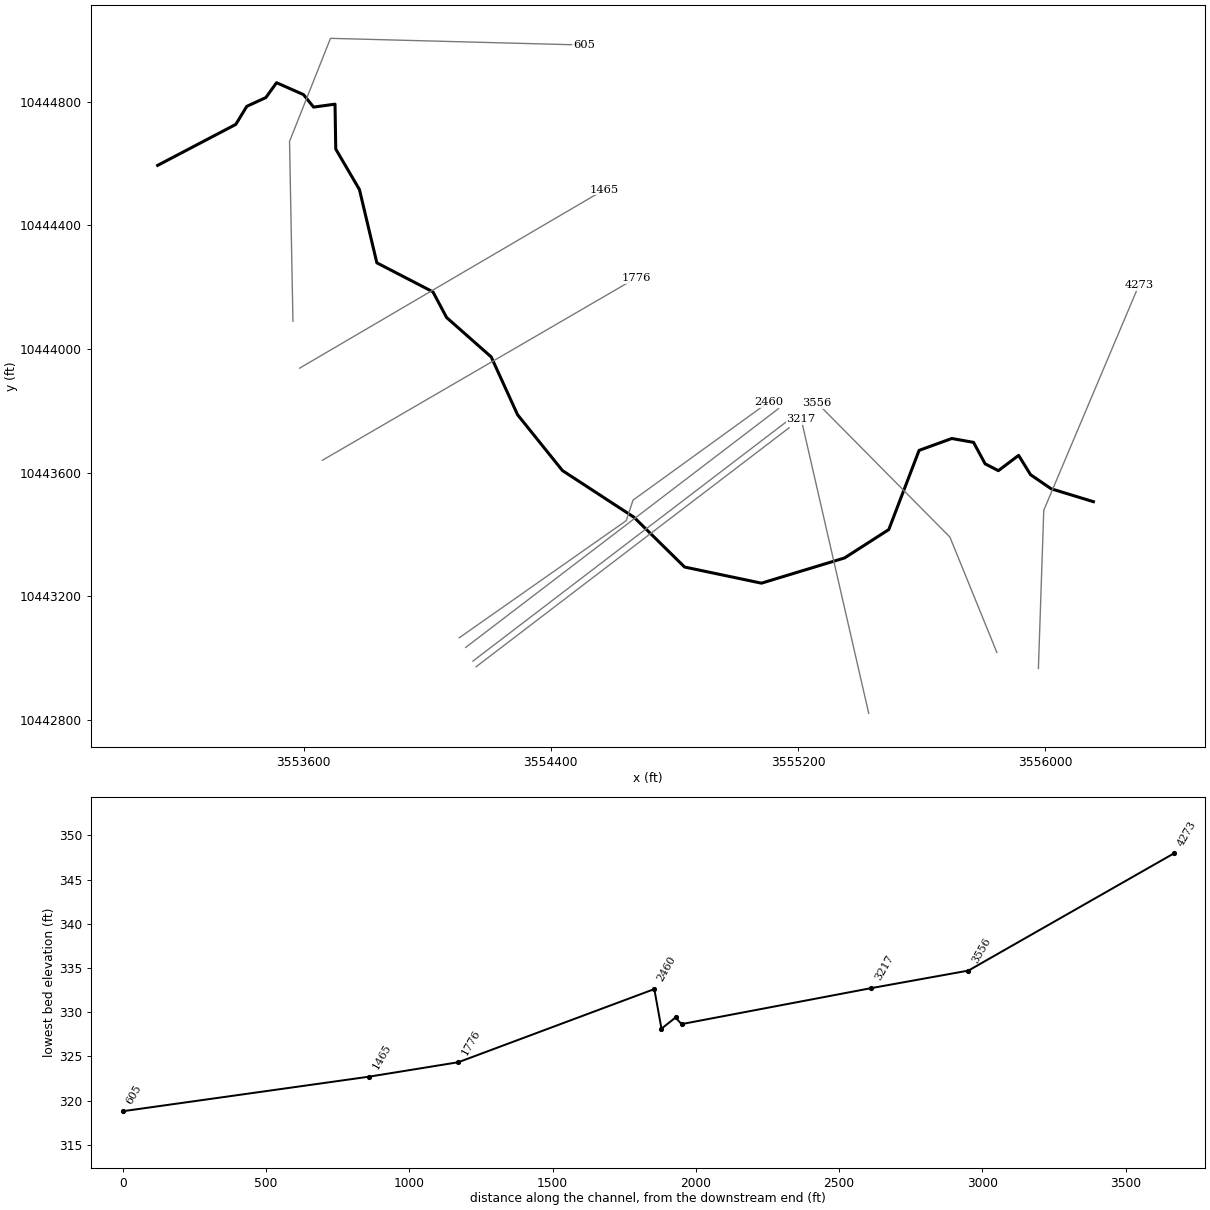
--- PADDY BRANCH.prj (project) ---

Proj Title=PADDY BRANCH Base Level Engineering
Current Plan=p01
Default Exp/Contr=0.3,0.1
English Units
Geom File=g01
Flow File=f01
Plan File=p01
Y Axis Title=Elevation
X Axis Title(PF)=Main Channel Distance
X Axis Title(XS)=Station
BEGIN DESCRIPTION:
PADDY BRANCH
END DESCRIPTION:
DSS Export Rating Curves= 0
DSS Export Rating Curve Sorted= 0
DSS Export Volume Flow Curves= 0
DXF OffsetX= 0
DXF OffsetY= 0
DXF ScaleX= 1
DXF ScaleY= 10

--- PADDY BRANCH.p01 (plan) ---

Plan Title=Multiple Run
Short Identifier=Multiple
Geom File=g01
Flow File=f01
Subcritical Flow
K Sum by GR= 0
Std Step Tol= 0.01
Critical Tol= 0.01
Num of Std Step Trials= 20
Max Error Tol= 0.3
Flow Tol Ratio= 0.001
Split Flow NTrial= 30
Split Flow Tol= 0.02
Split Flow Ratio= 0.02
Log Output Level= 0
Friction Slope Method= 1
Unsteady Friction Slope Method= 2
Unsteady Bridges Friction Slope Method= 1
Parabolic Critical Depth
Global Vel Dist=  1 , 1 , 1
Global Log Level= 0
CheckData=True
Encroach Param= -1, 0, 0, 0
BEGIN DESCRIPTION:
Multiple Run
END DESCRIPTION:

--- PADDY BRANCH.f01 (steady flow) ---

Flow Title=Multiple
Number of Profiles=7
Profile Names=10-year,25-year,50-year,1pct_min,100-year,1pct_plu,500-year
River Rch & RM= PADDY BRANCH,Reach-1,4273
    1263    1764    2183    1970    2665    3604    3960
Boundary for River Rch & Prof#=PADDY BRANCH,Reach-1,1
Up Type=0
Dn Type=3
Dn Slope=0.005
Boundary for River Rch & Prof#=PADDY BRANCH,Reach-1,2
Up Type=0
Dn Type=3
Dn Slope=0.005
Boundary for River Rch & Prof#=PADDY BRANCH,Reach-1,3
Up Type=0
Dn Type=3
Dn Slope=0.005
Boundary for River Rch & Prof#=PADDY BRANCH,Reach-1,4
Up Type=0
Dn Type=3
Dn Slope=0.005
Boundary for River Rch & Prof#=PADDY BRANCH,Reach-1,5
Up Type=0
Dn Type=3
Dn Slope=0.005
Boundary for River Rch & Prof#=PADDY BRANCH,Reach-1,6
Up Type=0
Dn Type=3
Dn Slope=0.005
Boundary for River Rch & Prof#=PADDY BRANCH,Reach-1,7
Up Type=0
Dn Type=3
Dn Slope=0.005

--- PADDY BRANCH.g01 (geometry) ---

Geom Title=Existing Conditions
Program Version=4.10

River Reach=PADDY BRANCH    ,Reach-1
Reach XY= 30
      3556156.58      10443505.6      3556019.76      10443547.4
      3555953.06     10443592.97       3555914.4     10443655.56
      3555848.84     10443606.01      3555806.02      10443628.2
      3555768.53     10443697.65      3555698.05     10443710.19
      3555592.23     10443671.68      3555494.12     10443415.37
      3555351.29     10443323.61      3555081.93     10443241.83
       3554833.1     10443294.07      3554669.21      10443455.3
       3554437.7     10443606.34      3554292.39     10443787.12
      3554207.07     10443974.28      3554062.63     10444101.85
      3554018.54     10444184.82      3553836.88      10444278.9
      3553780.55       10444516.      3553703.85      10444647.1
       3553701.5      10444792.5      3553632.05     10444782.95
       3553599.5     10444823.32      3553512.26     10444861.95
      3553477.54     10444813.77      3553415.72     10444785.33
      3553380.32     10444726.96      3553127.27     10444594.31

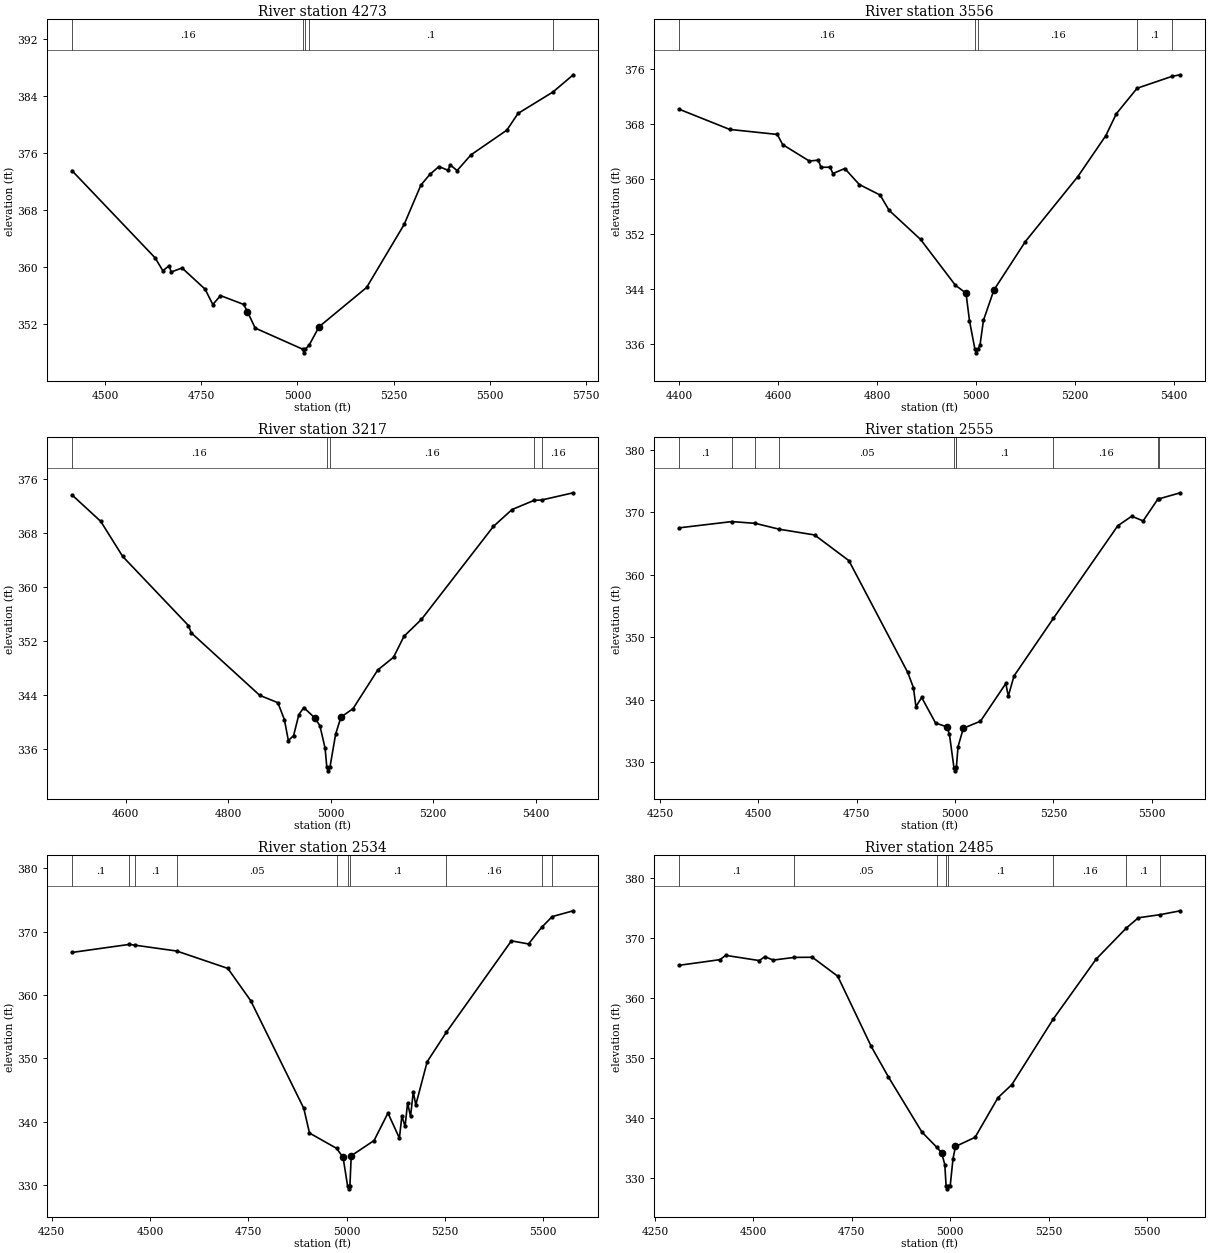
Type RM Length L Ch R = 1 ,4273    ,717,717,717
BEGIN DESCRIPTION:
PADDY BRANCH 9.0
END DESCRIPTION:
XS GIS Cut Line= 3
      3555978.48     10442965.62      3555995.84     10443477.79
      3556303.94      10444206.8
#Sta/Elev= 30
  4413.5  373.51  4629.6  361.28  4649.7  359.47  4666.3  360.18  4671.3  359.29
  4699.7  359.86  4759.7  356.88  4779.7  354.73  4799.7  355.98  4859.8  354.75
  4869.8  353.74  4889.8  351.43    5014  348.45  5016.7  347.95    5020  348.45
  5030.7  349.07  5056.3  351.62  5179.8  357.12  5277.5  365.97    5321  371.49
  5344.2  372.98  5367.9  374.09  5391.6  373.57    5397  374.33  5415.3  373.53
  5451.2  375.73  5544.6   379.2  5573.8  381.55  5664.5  384.55  5717.4  386.97
#Mann= 5 ,-1 , 0
  4413.5     .16       0    5014     .07       0    5020     .16       0
  5030.7      .1       0  5664.5     .05       0
Bank Sta=4869.8,5056.3
XS Rating Curve= 0 ,0
Exp/Cntr=0.3,0.1

Type RM Length L Ch R = 1 ,3556    ,339,339,339
BEGIN DESCRIPTION:
PADDY BRANCH 8.0
END DESCRIPTION:
XS GIS Cut Line= 3
      3555843.93     10443017.73      3555692.02     10443390.99
      3555262.36     10443824.99
#Sta/Elev= 30
  4399.7  370.15  4501.9  367.21  4598.2  366.48  4609.1     365    4663  362.61
  4681.2  362.74  4686.6   361.7  4705.2  361.71  4710.6  360.79  4734.7  361.52
  4764.1  359.19  4806.2  357.66  4824.3  355.44    4888   351.2  4958.6  344.52
  4979.9  343.39  4986.9  339.38    4998   335.2  5000.8   334.7    5004   335.2
  5008.2  335.82  5015.2  339.44  5036.4  343.85    5100   350.9  5206.1  360.35
  5262.7  366.31  5283.9  369.49  5325.9   373.2  5397.4  374.95  5413.4  375.16
#Mann= 5 ,-1 , 0
  4399.7     .16       0    4998     .07       0    5004     .16       0
  5325.9      .1       0  5397.4     .16       0
Bank Sta=4979.9,5036.4
XS Rating Curve= 0 ,0
Exp/Cntr=0.3,0.1

Type RM Length L Ch R = 1 ,3217    ,662,662,662
BEGIN DESCRIPTION:
PADDY BRANCH 6.0
END DESCRIPTION:
XS GIS Cut Line= 2
      3555429.22     10442820.33      3555210.47     10443773.45
#Sta/Elev= 30
  4495.6  373.64  4551.6  369.72  4594.4  364.52  4722.7  354.27  4728.2  353.19
  4861.9  343.91  4897.1  342.83  4909.9  340.33  4917.6  337.21  4927.9  337.95
  4938.1  341.05  4947.7   342.1  4968.9   340.6  4979.2  339.41  4989.4  336.04
  4992.7  333.22  4995.4  332.72  4998.7  333.22  5009.9  338.16  5020.2  340.69
  5043.7  341.93    5092  347.67  5122.8  349.56  5143.3  352.68  5177.4  355.19
  5317.7  368.97    5354  371.47  5396.8  372.83    5412  372.89  5473.5  373.96
#Mann= 5 ,-1 , 0
  4495.6     .16       0  4992.7     .07       0  4998.7     .16       0
  5396.8      .1       0    5412     .16       0
Bank Sta=4968.9,5020.2
XS Rating Curve= 0 ,0
Exp/Cntr=0.3,0.1

Type RM Length L Ch R = 1 ,2555    ,21,21,21
BEGIN DESCRIPTION:
PADDY BRANCH 4.2
END DESCRIPTION:
XS GIS Cut Line= 2
      3554158.35     10442971.32      3555171.43     10443744.81
#Sta/Elev= 30
  4298.3  367.53  4432.2  368.53  4491.8  368.25  4552.9  367.31  4642.8  366.39
    4730  362.28  4879.6   344.4  4894.2  341.95  4900.5  338.91    4915   340.4
  4950.4   336.3  4979.4  335.68  4985.7  334.47  4997.2  329.15    5000  328.65
  5003.2  329.15  5003.4   329.3  5007.6  332.53  5021.1  335.47  5064.6  336.59
  5129.1  342.63  5135.3   340.6  5149.9  343.83  5249.9  353.04  5413.8  367.86
  5449.2  369.39  5478.2  368.64  5515.7  372.12  5517.8  372.16  5572.9  373.14
#Mann= 10 ,-1 , 0
  4298.3      .1       0  4432.2     .05       0  4491.8      .1       0
  4552.9     .05       0  4997.2     .03       0  5003.2     .05       0
  5003.4      .1       0  5249.9     .16       0  5515.7      .1       0
  5517.8     .16       0
Bank Sta=4979.4,5021.1
XS Rating Curve= 0 ,0
Exp/Cntr=0.3,0.1

Type RM Length L Ch R = 1 ,2534    ,49,49,49
BEGIN DESCRIPTION:
PADDY BRANCH 4.0
END DESCRIPTION:
XS GIS Cut Line= 2
      3554147.99      10442989.6      3555160.99     10443763.02
#Sta/Elev= 30
  4301.7  366.74  4447.3  368.01  4462.7  367.88    4568  366.96  4697.8  364.22
  4755.9  359.13    4891  342.11  4905.5  338.21  4974.3   335.8  4990.8  334.38
  5002.3   329.9    5005   329.4  5008.3   329.9  5011.6  334.62  5069.7  337.03
    5105  341.37  5134.1  337.41  5140.4  340.89  5148.6  339.26  5154.9  342.96
  5162.4  340.85  5169.5  344.76  5175.7  342.65  5204.8  349.48  5253.4  354.12
  5418.9  368.57  5462.5  368.08  5495.5  370.68  5522.6   372.4  5576.2  373.32
#Mann= 10 ,-1 , 0
  4301.7      .1       0  4447.3     .05       0  4462.7      .1       0
    4568     .05       0  4974.3      .1       0  5002.3     .07       0
  5008.3      .1       0  5253.4     .16       0  5495.5      .1       0
  5522.6     .16       0
Bank Sta=4990.8,5011.6
XS Rating Curve= 0 ,0
Exp/Cntr=0.3,0.1

Type RM Length L Ch R = 1 ,2485    ,25,25,25
BEGIN DESCRIPTION:
PADDY BRANCH 4.1
END DESCRIPTION:
XS GIS Cut Line= 2
      3554124.52     10443033.85      3555136.89     10443806.78
#Sta/Elev= 30
  4311.2  365.44  4414.9  366.38  4429.4   367.1  4514.7  366.23  4529.2  366.88
    4550  366.31  4604.1  366.76  4649.8  366.78  4714.2  363.62  4799.4  351.89
    4843  346.81  4928.2   337.6  4966.2  335.05  4978.1  334.15  4986.3  332.18
  4989.6  328.63  4992.4  328.13  4995.6  328.63  5000.1  328.65  5007.2  333.19
  5013.5   335.2  5063.3  336.73  5121.5  343.35  5156.8  345.53  5261.8  356.46
  5370.9  366.47  5447.4  371.65  5478.2  373.37  5534.2   373.9  5584.9  374.54
#Mann= 8 ,-1 , 0
  4311.2      .1       0  4604.1     .05       0  4966.2      .1       0
  4989.6     .07       0  4995.6      .1       0  5261.8     .16       0
  5447.4      .1       0  5534.2     .16       0
Bank Sta=4978.1,5013.5
XS Rating Curve= 0 ,0
Exp/Cntr=0.3,0.1

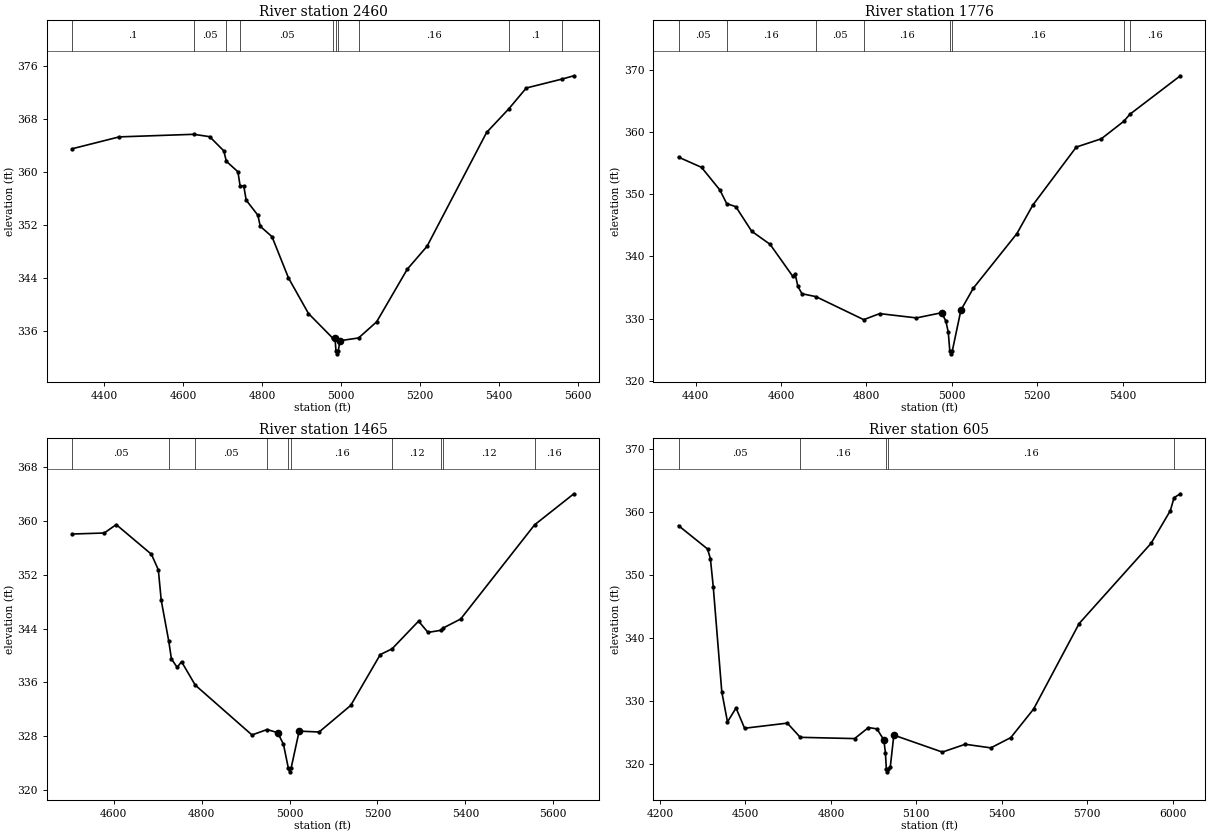
Type RM Length L Ch R = 1 ,2460    ,684,684,684
BEGIN DESCRIPTION:
PADDY BRANCH 4.3
END DESCRIPTION:
XS GIS Cut Line= 4
      3554103.66     10443065.08      3554644.39     10443444.33
      3554666.09     10443510.52      3555104.31     10443827.56
#Sta/Elev= 30
  4318.3  363.48  4437.7  365.27  4626.6  365.66  4666.9   365.3  4702.7  363.16
    4709   361.6  4738.4  360.02  4744.1  357.82  4753.2  357.89  4759.3  355.75
  4788.9  353.48    4795  351.81  4824.7  350.25  4866.5  344.03  4917.1  338.68
  4979.5  334.92  4984.3  335.04  4986.6  333.11  4989.4  332.61  4992.6  333.11
    4997  334.59    5044     335  5089.8  337.43  5167.2  345.34  5217.4   348.8
  5368.3  365.94  5424.6   369.5  5468.8  372.63  5559.7  373.98  5589.3  374.47
#Mann= 10 ,-1 , 0
  4318.3      .1       0  4626.6     .05       0    4709      .1       0
  4744.1     .05       0  4979.5      .1       0  4986.6     .07       0
  4992.6      .1       0    5044     .16       0  5424.6      .1       0
  5559.7     .16       0
Bank Sta=4984.3,4997
XS Rating Curve= 0 ,0
Exp/Cntr=0.3,0.1

Type RM Length L Ch R = 1 ,1776    ,311,311,311
BEGIN DESCRIPTION:
PADDY BRANCH 4.4
END DESCRIPTION:
XS GIS Cut Line= 2
      3553660.54     10443639.64      3554676.17     10444229.92
#Sta/Elev= 30
  4360.1  355.98  4413.9  354.34  4456.9   350.7  4472.8  348.51  4494.2  348.01
  4531.4  344.06  4574.5  341.95  4627.4  336.82  4633.2  337.15  4639.5  335.19
    4649  334.01  4681.8  333.54  4793.6  329.84    4831  330.81  4917.1  330.12
  4975.9  330.95  4985.8  329.64  4991.6   327.8  4995.1  324.84  4997.8  324.34
  5001.1  324.84  5021.2  331.39  5050.4  334.92  5152.2  343.68  5189.4  348.26
  5291.2   357.6    5350  358.94  5402.5  361.75  5416.9  362.89  5534.8  369.07
#Mann= 8 ,-1 , 0
  4360.1     .05       0  4472.8     .16       0  4681.8     .05       0
  4793.6     .16       0  4995.1     .07       0  5001.1     .16       0
  5402.5     .12       0  5416.9     .16       0
Bank Sta=4975.9,5021.2
XS Rating Curve= 0 ,0
Exp/Cntr=0.3,0.1

Type RM Length L Ch R = 1 ,1465    ,860,860,860
BEGIN DESCRIPTION:
PADDY BRANCH 3.0
END DESCRIPTION:
XS GIS Cut Line= 2
        3553587.     10443937.87      3554572.25     10444515.13
#Sta/Elev= 30
    4505  358.05  4578.2   358.2  4605.5  359.45  4685.6  355.04  4701.3  352.73
  4707.9   348.2    4725  342.14  4731.1  339.49  4744.2  338.24  4754.1  339.08
  4785.3   335.6  4914.4  328.19    4949     329    4973  328.52  4986.1  326.79
  4997.3  323.21    5000  322.71  5003.3  323.21  5021.8  328.76  5067.2  328.63
  5139.1  332.58  5206.3  340.13  5233.2  340.99  5293.5   345.1    5315  343.43
  5345.1  343.75  5349.4  344.08  5389.3  345.42  5557.6  359.42  5646.9  364.03
#Mann= 10 ,-1 , 0
    4505     .05       0    4725     .16       0  4785.3     .05       0
    4949     .16       0  4997.3     .07       0  5003.3     .16       0
  5233.2     .12       0  5345.1     .16       0  5349.4     .12       0
  5557.6     .16       0
Bank Sta=4973,5021.8
XS Rating Curve= 0 ,0
Exp/Cntr=0.3,0.1

Type RM Length L Ch R = 1 ,605     ,0,0,0
BEGIN DESCRIPTION:
PADDY BRANCH 1.0
END DESCRIPTION:
XS GIS Cut Line= 4
      3553565.29     10444089.75      3553554.24     10444671.82
      3553686.82     10445005.57      3554507.13     10444983.87
#Sta/Elev= 30
  4264.9  357.82  4366.8  354.12  4376.8  352.57  4386.8  348.14  4416.8  331.47
  4436.8  326.71  4466.8  328.92  4496.8  325.71  4646.9  326.52  4692.3  324.27
  4883.2  324.07  4931.8  325.82  4961.5  325.61  4985.8  323.86  4991.2  321.85
  4994.5   319.3  4997.3   318.8  5000.5   319.3  5008.3  319.53  5020.9  324.62
  5191.2  321.93  5271.5  323.17  5361.5   322.6  5431.6  324.23  5511.6  328.75
  5671.6  342.31  5924.3  355.03  5991.8   360.2  6004.7  362.25  6026.8  362.87
#Mann= 5 ,-1 , 0
  4264.9     .05       0  4692.3     .16       0  4994.5     .07       0
  5000.5     .16       0  6004.7      .1       0
Bank Sta=4985.8,5020.9
XS Rating Curve= 0 ,0
Exp/Cntr=0.3,0.1

Chan Stop Cuts=-1
Use User Specified Reach Order=0
Composite Channel Slope=5