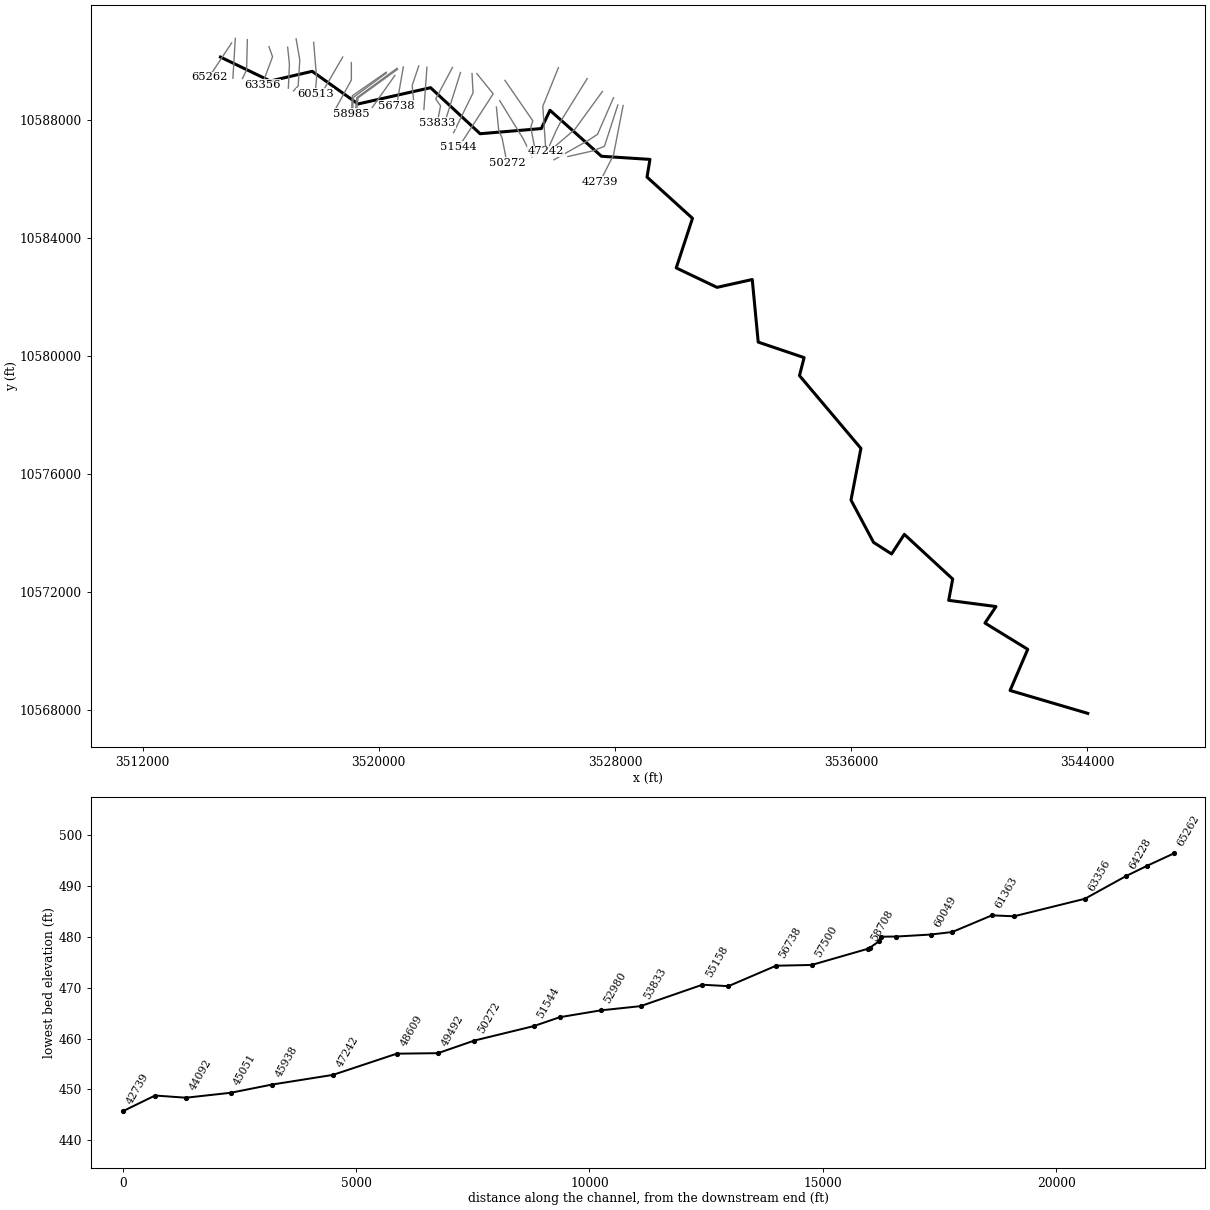
--- PATTON CREEK.prj (project) ---

Proj Title=PATTON CREEK Base Level Engineering
Current Plan=p01
Default Exp/Contr=0.3,0.1
English Units
Geom File=g01
Flow File=f01
Plan File=p01
Y Axis Title=Elevation
X Axis Title(PF)=Main Channel Distance
X Axis Title(XS)=Station
BEGIN DESCRIPTION:
PATTON CREEK
END DESCRIPTION:
DSS Export Rating Curves= 0
DSS Export Rating Curve Sorted= 0
DSS Export Volume Flow Curves= 0
DXF OffsetX= 0
DXF OffsetY= 0
DXF ScaleX= 1
DXF ScaleY= 10

--- PATTON CREEK.p01 (plan) ---

Plan Title=Multiple Run
Short Identifier=Multiple
Geom File=g01
Flow File=f01
Subcritical Flow
K Sum by GR= 0
Std Step Tol= 0.01
Critical Tol= 0.01
Num of Std Step Trials= 20
Max Error Tol= 0.3
Flow Tol Ratio= 0.001
Split Flow NTrial= 30
Split Flow Tol= 0.02
Split Flow Ratio= 0.02
Log Output Level= 0
Friction Slope Method= 1
Unsteady Friction Slope Method= 2
Unsteady Bridges Friction Slope Method= 1
Parabolic Critical Depth
Global Vel Dist=  1 , 1 , 1
Global Log Level= 0
CheckData=True
Encroach Param= -1, 0, 0, 0
BEGIN DESCRIPTION:
Multiple Run
END DESCRIPTION:

--- PATTON CREEK.f01 (steady flow) ---

Flow Title=Multiple
Number of Profiles=7
Profile Names=10-year,25-year,50-year,1pct_min,100-year,1pct_plu,500-year
River Rch & RM= PATTON CREEK,Reach-1,65262
     854    1156    1402    1240    1677    2268    2392
River Rch & RM= PATTON CREEK,Reach-1,63356
    1242    1715    2106    1883    2547    3445    3717
River Rch & RM= PATTON CREEK,Reach-1,60513
    1484    2066    2550    2292    3099    4191    4568
River Rch & RM= PATTON CREEK,Reach-1,58752
    1680    2345    2898    2606    3525    4767    5204
River Rch & RM= PATTON CREEK,Reach-1,50272
    1879    2632    3261    2938    3973    5373    5885
River Rch & RM= PATTON CREEK,Reach-1,47242
    2852    4066    5098    4641    6277    8489    9500
River Rch & RM= PATTON CREEK,Reach-1,42739
    3016    4312    5416    4940    6680    9034   10146
River Rch & RM= PATTON CREEK,Reach-1,40675
    3794    5474    6919    6346    8582   11606   13182
River Rch & RM= PATTON CREEK,Reach-1,38501
    4021    5783    7294    6673    9024   12204   13787
River Rch & RM= PATTON CREEK,Reach-1,30384
    4123    5937    7494    6860    9278   12547   14196
River Rch & RM= PATTON CREEK,Reach-1,29064
    4294    6181    7800    7136    9651   13052   14750
River Rch & RM= PATTON CREEK,Reach-1,22665
    4549    6560    8289    7593   10269   13888   15733
River Rch & RM= PATTON CREEK,Reach-1,19450
    5720    8298   10528    9678   13089   17701   20190
River Rch & RM= PATTON CREEK,Reach-1,12962
    5760    8351   10591    9731   13161   17798   20281
River Rch & RM= PATTON CREEK,Reach-1,5805
    5658    8173   10339    9474   12812   17327   19636
Boundary for River Rch & Prof#=PATTON CREEK,Reach-1,1
Up Type=0
Dn Type=3
Dn Slope=0.005
Boundary for River Rch & Prof#=PATTON CREEK,Reach-1,2
Up Type=0
Dn Type=3
Dn Slope=0.005
Boundary for River Rch & Prof#=PATTON CREEK,Reach-1,3
Up Type=0
Dn Type=3
Dn Slope=0.005
Boundary for River Rch & Prof#=PATTON CREEK,Reach-1,4
Up Type=0
Dn Type=3
Dn Slope=0.005
Boundary for River Rch & Prof#=PATTON CREEK,Reach-1,5
Up Type=0
Dn Type=3
Dn Slope=0.005
Boundary for River Rch & Prof#=PATTON CREEK,Reach-1,6
Up Type=0
Dn Type=3
Dn Slope=0.005
Boundary for River Rch & Prof#=PATTON CREEK,Reach-1,7
Up Type=0
Dn Type=3
Dn Slope=0.005

--- PATTON CREEK.g01 (geometry) ---

Geom Title=Existing Conditions
Program Version=4.10

River Reach=PATTON CREEK    ,Reach-1
Reach XY= 30
       3514634.9     10590143.74      3516322.11     10589331.64
      3517742.96     10589660.71      3519297.62     10588554.21
      3521754.63     10589105.39      3523433.36     10587544.34
      3525506.29     10587719.35       3525801.1     10588339.08
      3527545.69     10586780.23      3529188.89     10586673.86
      3529089.52      10586074.9      3530630.34     10584675.88
      3530078.96      10582994.4      3531461.25     10582334.51
      3532655.05     10582600.96      3532857.46     10580478.59
      3534412.66     10579952.37      3534255.42      10579342.6
      3536337.89     10576874.58       3536001.9     10575120.61
      3536765.38     10573688.32      3537376.51     10573293.89
      3537808.64     10573959.47      3539448.02     10572444.27
      3539312.12     10571721.77      3540915.96     10571511.13
      3540542.11     10570951.64      3541991.24     10570060.93
      3541392.83     10568665.14      3544025.43     10567888.78

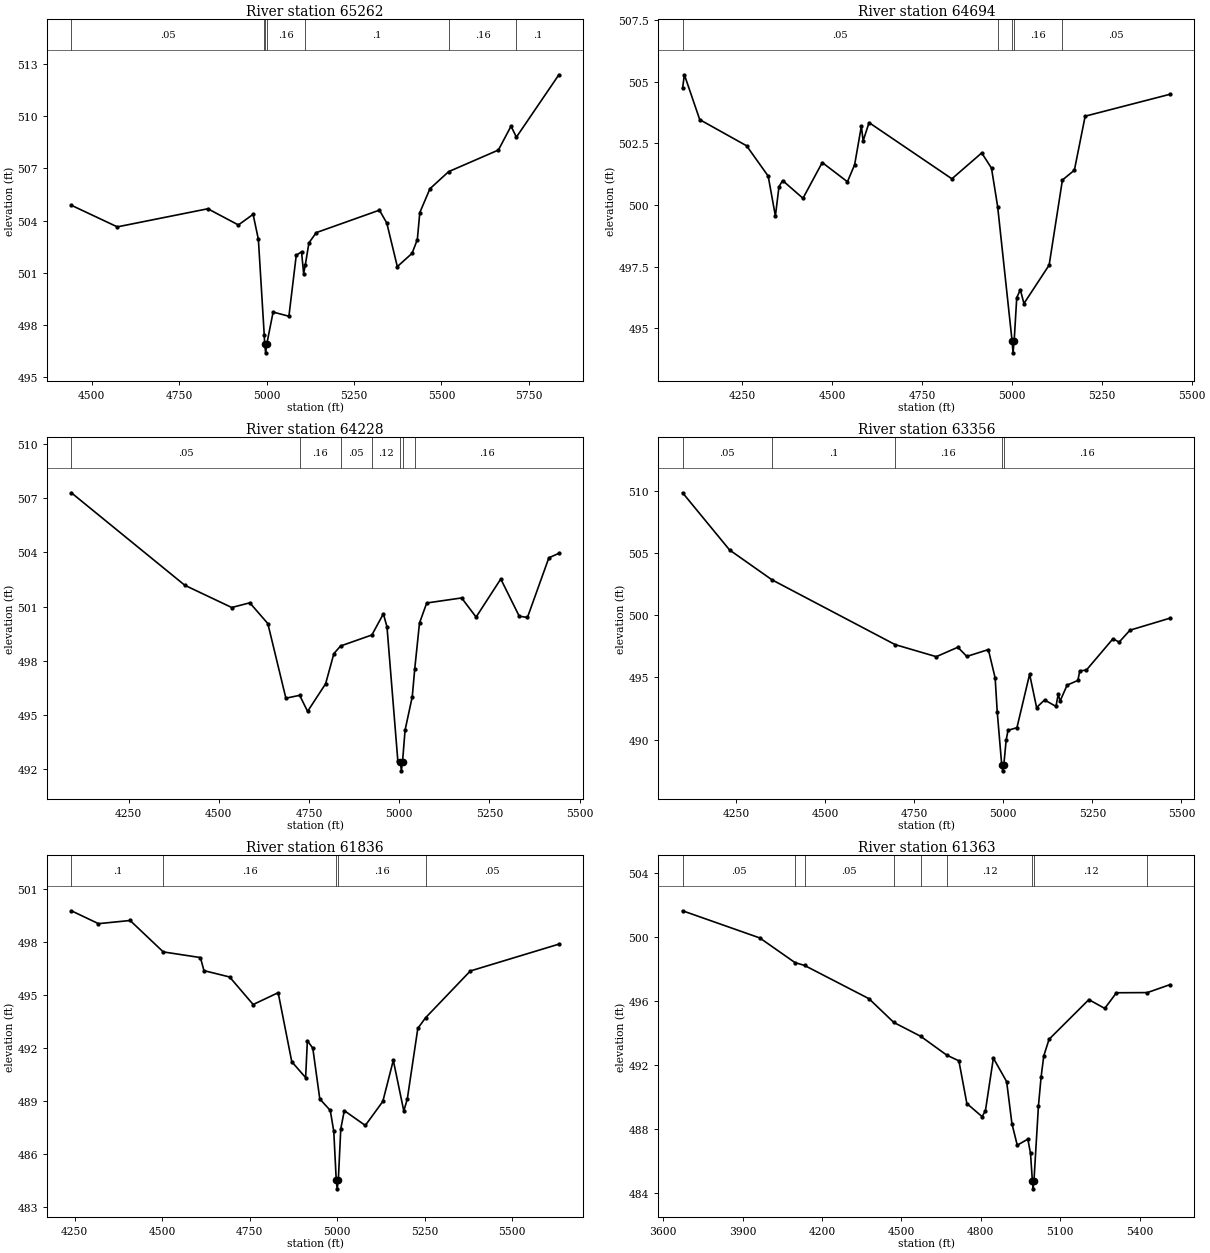
Type RM Length L Ch R = 1 ,65262   ,568,568,568
BEGIN DESCRIPTION:
PATTON CREEK 75.01
END DESCRIPTION:
XS GIS Cut Line= 2
       3515011.7     10590623.05      3514243.46     10589459.85
#Sta/Elev= 30
  4441.8  504.88  4573.2  503.64  4832.1  504.68  4919.4  503.75  4961.5  504.36
  4976.6  502.92  4993.4  497.42  4994.6  496.91  4997.4  496.41  5000.6  496.91
  5018.7  498.75  5063.9  498.51  5084.9  502.01    5100  502.21    5106  500.96
  5110.9  501.46  5121.1  502.72  5142.1  503.31  5322.7   504.6  5343.8  503.86
  5373.9  501.36    5416  502.12  5431.1  502.91  5438.2  504.46  5467.2  505.83
  5520.7  506.81  5662.9  508.05    5699  509.42  5714.4  508.79  5835.8  512.37
#Mann= 7 ,-1 , 0
  4441.8     .05       0  4993.4     .16       0  4994.6     .07       0
  5000.6     .16       0  5110.9      .1       0  5520.7     .16       0
  5714.4      .1       0
Bank Sta=4994.6,5000.6
XS Rating Curve= 0 ,0
Exp/Cntr=0.3,0.1

Type RM Length L Ch R = 1 ,64694   ,466,466,466
BEGIN DESCRIPTION:
PATTON CREEK 74.2
END DESCRIPTION:
XS GIS Cut Line= 2
      3515137.55     10590779.29      3515055.13     10589425.89
#Sta/Elev= 30
  4084.1  504.74  4089.1  505.28  4131.8  503.46  4262.1   502.4  4322.2  501.17
  4342.2  499.55  4352.2  500.74  4362.3  500.99  4418.9  500.27  4472.5  501.72
  4542.6  500.94  4562.6  501.63  4581.3  503.19  4586.3   502.6  4602.7  503.34
  4833.1  501.06  4916.1  502.11  4943.3  501.49  4960.4  499.93  5000.4   494.5
  5003.2     494  5006.4   494.5  5013.5  496.24  5023.5  496.56  5033.5     496
  5103.6  497.56  5140.5  501.01  5173.8  501.41  5203.8   503.6    5440  504.49
#Mann= 5 ,-1 , 0
  4084.1     .05       0  4960.4     .16       0  5000.4     .07       0
  5006.4     .16       0  5140.5     .05       0
Bank Sta=5000.4,5006.4
XS Rating Curve= 0 ,0
Exp/Cntr=0.3,0.1

Type RM Length L Ch R = 1 ,64228   ,872,872,872
BEGIN DESCRIPTION:
PATTON CREEK 82.0
END DESCRIPTION:
XS GIS Cut Line= 3
      3515545.54      10590735.9      3515519.49     10589711.57
      3515380.67     10589416.56
#Sta/Elev= 30
  4091.5   507.3  4405.9  502.18  4535.9  500.95  4585.9  501.21  4635.9  500.06
  4685.9  495.93  4724.1  496.09    4746   495.2    4796  496.73  4818.9   498.4
  4837.4  498.82  4924.2  499.43    4956   500.6    4966  499.88    4996  492.48
  5003.1  492.41  5005.8  491.91  5009.1  492.41  5016.1  494.16  5036.1  496.02
  5042.8  497.53  5056.1  500.09  5076.1   501.2  5172.8  501.48  5212.9  500.42
  5281.3  502.53  5332.4  500.47  5355.2   500.4  5414.5   503.7  5442.2  503.95
#Mann= 7 ,-1 , 0
  4091.5     .05       0  4724.1     .16       0  4837.4     .05       0
  4924.2     .12       0  5003.1     .07       0  5009.1     .12       0
  5042.8     .16       0
Bank Sta=5003.1,5009.1
XS Rating Curve= 0 ,0
Exp/Cntr=0.3,0.1

Type RM Length L Ch R = 1 ,63356   ,1520,1520,1520
BEGIN DESCRIPTION:
PATTON CREEK 70.0
END DESCRIPTION:
XS GIS Cut Line= 3
      3516277.56      10590496.1       3516399.1      10590153.2
      3516047.54     10589211.38
#Sta/Elev= 30
  4099.2  509.85  4231.2  505.25  4350.3  502.85  4696.1  497.64  4811.7  496.67
  4872.3  497.43  4897.3  496.69  4957.9  497.24    4977  494.96  4982.9  492.22
  4995.4  487.99  4998.1  487.49  5001.4  487.99  5007.9  489.96  5013.2  490.75
  5038.2  490.96  5073.8  495.26  5093.4  492.58  5115.8  493.19  5147.8  492.67
  5154.1  493.65  5159.4   493.1    5179  494.38  5209.3  494.76  5214.7  495.53
  5233.2  495.59  5307.9  498.11  5325.2  497.84  5355.6   498.8  5468.3  499.77
#Mann= 5 ,-1 , 0
  4099.2     .05       0  4350.3      .1       0  4696.1     .16       0
  4995.4     .07       0  5001.4     .16       0
Bank Sta=4995.4,5001.4
XS Rating Curve= 0 ,0
Exp/Cntr=0.3,0.1

Type RM Length L Ch R = 1 ,61836   ,473,473,473
BEGIN DESCRIPTION:
PATTON CREEK 78.0
END DESCRIPTION:
XS GIS Cut Line= 3
      3516911.25     10590478.75      3516971.04     10589894.38
      3516934.58     10589088.82
#Sta/Elev= 30
  4240.2  499.79  4317.7  499.06  4408.2  499.24    4503  497.46  4609.2  497.14
  4619.3   496.4  4692.7  496.04    4760  494.48  4831.5  495.15  4870.4  491.24
    4910  490.34    4915  492.43  4930.5  492.01  4950.5  489.13  4980.5  488.48
  4990.5  487.29  4997.5  484.54  5000.3  484.04  5003.5  484.54  5010.5  487.44
  5020.6  488.47  5080.6  487.63  5130.7  488.99  5160.7  491.32  5190.7  488.45
  5200.7  489.13  5230.8  493.13  5252.9  493.73  5380.9  496.38    5634   497.9
#Mann= 5 ,-1 , 0
  4240.2      .1       0    4503     .16       0  4997.5     .07       0
  5003.5     .16       0  5252.9     .05       0
Bank Sta=4997.5,5003.5
XS Rating Curve= 0 ,0
Exp/Cntr=0.3,0.1

Type RM Length L Ch R = 1 ,61363   ,850,850,850
BEGIN DESCRIPTION:
PATTON CREEK 69.1
END DESCRIPTION:
XS GIS Cut Line= 4
      3517197.15      10590764.1      3517322.16     10590045.34
      3517267.47     10589165.13      3517108.61     10588998.46
#Sta/Elev= 30
  3673.4  501.63    3965  499.93  4097.8  498.39  4134.1  498.21  4377.4  496.13
  4471.5  494.64  4572.5  493.78  4671.1   492.6  4717.2  492.24  4747.3  489.57
  4804.7  488.75  4817.4  489.11  4847.5  492.41  4897.6  490.94  4917.6  488.31
  4937.7  486.96  4977.7  487.34  4987.8  486.45  4994.8  484.73  4997.5  484.23
  5000.8  484.73  5017.8  489.43  5027.8  491.23  5037.9  492.55  5057.9  493.59
  5208.2  496.07  5268.3  495.52  5312.4   496.5  5429.1  496.51  5515.1  497.01
#Mann= 9 ,-1 , 0
  3673.4     .05       0  4097.8      .1       0  4134.1     .05       0
  4471.5      .1       0  4572.5     .16       0  4671.1     .12       0
  4994.8     .07       0  5000.8     .12       0  5429.1     .05       0
Bank Sta=4994.8,5000.8
XS Rating Curve= 0 ,0
Exp/Cntr=0.3,0.1

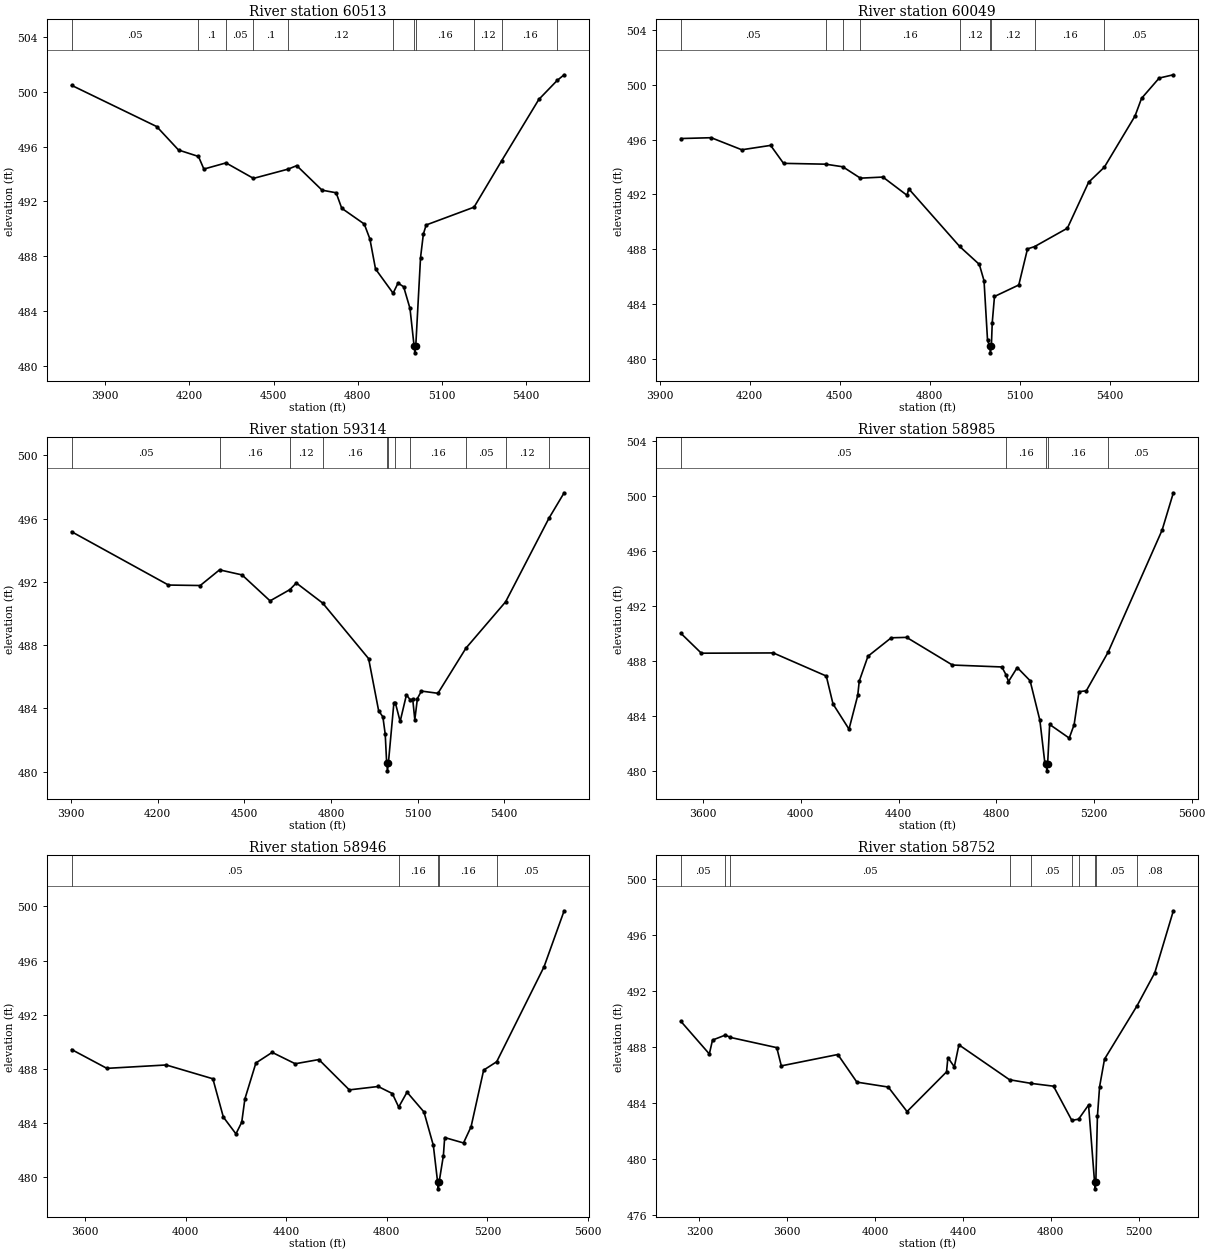
Type RM Length L Ch R = 1 ,60513   ,464,464,464
BEGIN DESCRIPTION:
PATTON CREEK 67.1
END DESCRIPTION:
XS GIS Cut Line= 3
       3517792.1     10590641.66      3517892.11     10589441.64
      3517842.11     10588891.69
#Sta/Elev= 30
  3779.9  500.47  4083.5  497.46  4161.2  495.75  4232.3  495.28  4251.6  494.36
  4330.4  494.81  4428.5  493.68  4552.8  494.36  4582.7  494.61    4673  492.82
  4723.2  492.63  4743.2   491.5  4823.5  490.35  4843.6  489.26  4863.7  487.07
  4926.4   485.3  4943.9  486.04    4964  485.77  4986.6  484.19  5001.2  481.45
  5003.9  480.95  5007.2  481.45  5024.2   487.9  5034.3  489.62  5044.3  490.28
    5215  491.58  5313.9  494.98    5446  499.44  5511.6  500.83  5536.3  501.24
#Mann= 11 ,-1 , 0
  3779.9     .05       0  4232.3      .1       0  4330.4     .05       0
  4428.5      .1       0  4552.8     .12       0  4926.4     .16       0
  5001.2     .07       0  5007.2     .16       0    5215     .12       0
  5313.9     .16       0  5511.6     .05       0
Bank Sta=5001.2,5007.2
XS Rating Curve= 0 ,0
Exp/Cntr=0.3,0.1

Type RM Length L Ch R = 1 ,60049   ,735,735,735
BEGIN DESCRIPTION:
PATTON CREEK 74.0
END DESCRIPTION:
XS GIS Cut Line= 2
      3518777.45     10590145.22      3517953.02     10588726.34
#Sta/Elev= 30
  3970.8  496.08  4072.1  496.14  4173.9  495.26    4270  495.58    4313  494.27
    4453  494.21  4510.4  494.02  4569.1  493.19  4644.1  493.27  4724.4  491.94
  4730.2  492.41  4899.7  488.21  4965.3   486.9    4981  485.71  4992.7  481.36
  4999.5  480.95  5002.3  480.45  5005.5  480.95  5008.3  482.63  5015.8  484.56
  5096.8   485.4  5125.8  488.03  5149.6   488.2  5258.7  489.54  5329.4  492.89
  5381.8  493.99  5484.2  497.73  5505.8  499.01  5564.5  500.49  5611.8  500.73
#Mann= 9 ,-1 , 0
  3970.8     .05       0    4453     .16       0  4510.4     .05       0
  4569.1     .16       0  4899.7     .12       0  4999.5     .07       0
  5005.5     .12       0  5149.6     .16       0  5381.8     .05       0
Bank Sta=4999.5,5005.5
XS Rating Curve= 0 ,0
Exp/Cntr=0.3,0.1

Type RM Length L Ch R = 1 ,59314   ,329,329,329
BEGIN DESCRIPTION:
PATTON CREEK 74.1
END DESCRIPTION:
XS GIS Cut Line= 3
      3519069.76     10589957.17      3519069.76     10589366.89
      3518535.06     10588387.75
#Sta/Elev= 30
  3901.5  495.17    4237   491.8    4347  491.77  4413.9  492.76  4491.8  492.44
  4588.9   490.8  4657.4  491.51  4679.7  491.93  4771.1  490.66  4930.2  487.15
  4964.9  483.86  4979.6  483.47  4987.7  482.38  4992.7  480.56  4995.5  480.06
  4998.7  480.56  5017.6  484.33  5023.3  484.32  5039.4  483.18  5061.2  484.86
  5074.2  484.55    5083  484.58  5090.2  483.29  5099.2  484.63    5113   485.1
  5170.3  484.96  5267.2  487.81  5404.7  490.74  5554.4  496.01  5607.4  497.63
#Mann= 11 ,-1 , 0
  3901.5     .05       0  4413.9     .16       0  4657.4     .12       0
  4771.1     .16       0  4992.7     .07       0  4998.7     .16       0
  5023.3     .12       0  5074.2     .16       0  5267.2     .05       0
  5404.7     .12       0  5554.4     .05       0
Bank Sta=4992.7,4998.7
XS Rating Curve= 0 ,0
Exp/Cntr=0.3,0.1

Type RM Length L Ch R = 1 ,58985   ,39,39,39
BEGIN DESCRIPTION:
PATTON CREEK 65.1
END DESCRIPTION:
XS GIS Cut Line= 3
      3520251.03     10589630.65      3519101.41     10588831.15
      3519075.41     10588215.69
#Sta/Elev= 30
  3508.8  490.03  3592.8  488.58  3887.4   488.6  4104.3  486.92  4131.8  484.89
  4197.3  483.06  4233.1  485.52  4239.2  486.55  4274.9  488.36  4370.1   489.7
  4433.2  489.73  4620.6  487.72    4823  487.58  4840.7  486.99  4850.2  486.52
    4886  487.54  4938.6  486.58  4978.7   483.7  4998.7  480.65  5004.4  480.53
  5007.2  480.03  5010.4  480.53  5018.7   483.4  5098.8  482.41  5118.8  483.38
  5138.8  485.78  5168.8  485.85  5257.9  488.65  5479.1  497.53  5525.1  500.24
#Mann= 5 ,-1 , 0
  3508.8     .05       0  4840.7     .16       0  5004.4     .07       0
  5010.4     .16       0  5257.9     .05       0
Bank Sta=5004.4,5010.4
XS Rating Curve= 0 ,0
Exp/Cntr=0.3,0.1

Type RM Length L Ch R = 1 ,58946   ,194,194,194
BEGIN DESCRIPTION:
PATTON CREEK 73.0
END DESCRIPTION:
XS GIS Cut Line= 5
      3520255.81     10589603.15      3519170.29     10588798.88
      3519129.93     10588768.93      3519119.51     10588464.24
      3519126.02     10588211.65
#Sta/Elev= 30
  3546.5  489.43  3686.8  488.04  3922.6  488.29  4108.3  487.27    4150  484.44
  4200.1   483.2  4223.1  484.06  4235.6  485.78  4279.5  488.44  4344.2  489.22
  4435.9  488.38  4529.9  488.69  4650.9  486.45  4765.7   486.7    4822  486.18
  4847.3  485.18  4880.5  486.28  4947.8  484.82  4985.1  482.35  5002.1  479.64
  5004.8  479.14  5008.1  479.64  5025.1   481.6  5030.2  482.93  5105.1  482.53
  5135.2  483.73  5185.2  487.91  5237.1  488.53  5425.3  495.54  5505.3  499.68
#Mann= 5 ,-1 , 0
  3546.5     .05       0  4847.3     .16       0  5002.1     .07       0
  5008.1     .16       0  5237.1     .05       0
Bank Sta=5002.1,5008.1
XS Rating Curve= 0 ,0
Exp/Cntr=0.3,0.1

Type RM Length L Ch R = 1 ,58752   ,44,44,44
BEGIN DESCRIPTION:
PATTON CREEK 73.1
END DESCRIPTION:
XS GIS Cut Line= 4
      3520618.95     10589765.42      3519252.47     10588763.94
      3519204.72     10588327.74      3519209.06     10588217.11
#Sta/Elev= 30
    3115  489.84  3244.8  487.51  3259.4   488.5  3318.5  488.86  3340.3  488.69
    3552  487.96  3572.8  486.66  3830.2  487.47    3917   485.5  4059.9  485.15
  4145.6   483.4  4325.4  486.23  4331.6  487.25  4360.9  486.59  4381.8  488.16
  4612.5  485.67  4711.1  485.41  4812.8  485.21  4896.2  482.77  4927.1  482.86
  4972.4  483.87  4999.6  478.39  5002.4  477.89  5005.6  478.39  5012.7  483.05
  5022.7  485.18  5045.1  487.14  5193.5  490.95  5274.1   493.3  5358.7  497.72
#Mann= 10 ,-1 , 0
    3115     .05       0  3318.5     .16       0  3340.3     .05       0
  4612.5     .12       0  4711.1     .05       0  4896.2     .12       0
  4927.1     .05       0  4999.6     .04       0  5005.6     .05       0
  5193.5     .08       0
Bank Sta=4999.6,5005.6
XS Rating Curve= 0 ,0
Exp/Cntr=0.3,0.1

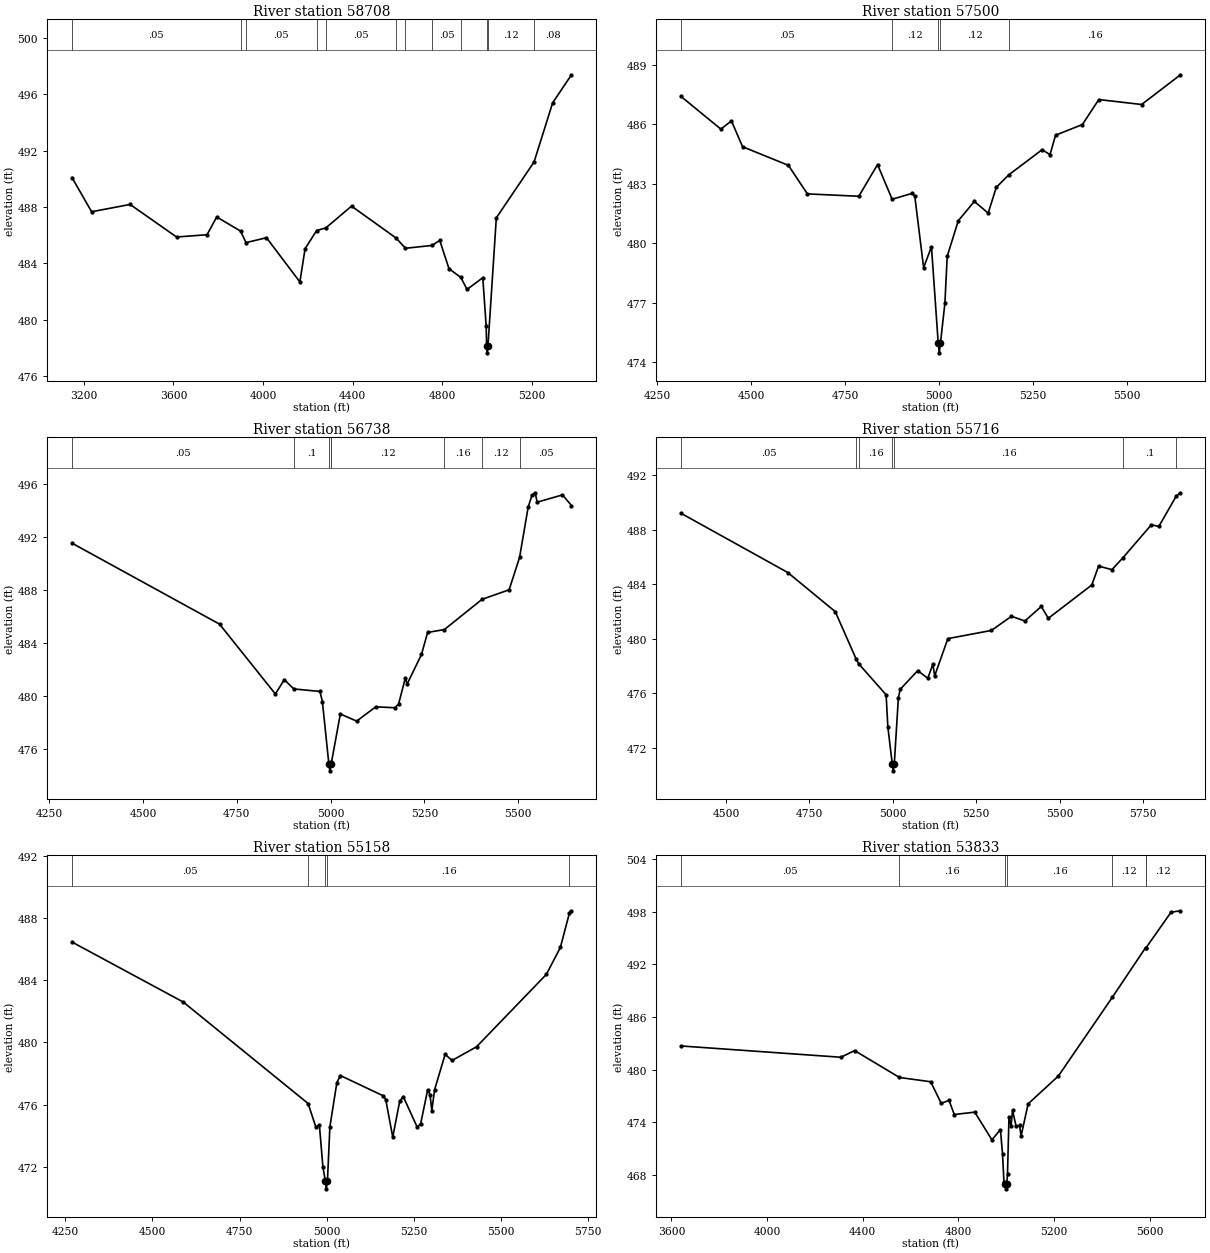
Type RM Length L Ch R = 1 ,58708   ,1208,1208,1208
BEGIN DESCRIPTION:
PATTON CREEK 72.0
END DESCRIPTION:
XS GIS Cut Line= 3
      3520635.91      10589729.8      3519295.61     10588761.03
      3519233.11      10588188.1
#Sta/Elev= 30
  3146.7   490.1  3234.5  487.67  3406.3  488.19  3613.6  485.88  3749.7  486.04
    3793   487.3  3899.3   486.3  3923.9  485.48  4015.1  485.83  4164.3  482.69
  4187.5  485.05  4239.2  486.34  4279.8  486.52  4394.9  488.07  4593.5  485.81
  4635.7  485.08  4754.4  485.28  4788.6  485.64    4830  483.63  4882.8  483.01
  4910.5  482.16  4980.9  482.99    4996  479.55    4998  478.16  5000.8  477.66
    5004  478.16  5041.3  487.24  5209.7   491.2  5292.8   495.4  5376.8  497.39
#Mann= 12 ,-1 , 0
  3146.7     .05       0  3899.3     .16       0  3923.9     .05       0
  4239.2     .16       0  4279.8     .05       0  4593.5     .16       0
  4635.7     .12       0  4754.4     .05       0  4882.8     .12       0
    4998     .07       0    5004     .12       0  5209.7     .08       0
Bank Sta=4998,5004
XS Rating Curve= 0 ,0
Exp/Cntr=0.3,0.1

Type RM Length L Ch R = 1 ,57500   ,762,762,762
BEGIN DESCRIPTION:
PATTON CREEK 62.0
END DESCRIPTION:
XS GIS Cut Line= 2
      3520543.37     10589518.21      3519776.12     10588434.52
#Sta/Elev= 30
  4313.5  487.41  4419.6  485.76  4447.8  486.17  4477.4  484.87  4599.2  483.93
  4649.7  482.49  4786.3  482.37  4836.2  483.97  4874.9  482.22    4929  482.52
  4935.2  482.37  4958.6  478.77  4979.5  479.82  4997.4  474.97  5000.2  474.47
  5003.4  474.97  5015.2  476.97  5021.3  479.34  5050.9  481.14  5093.5  482.11
  5130.2  481.52  5151.8  482.82  5184.9  483.45  5273.6  484.72  5294.6  484.47
  5309.3  485.45  5380.7  485.99  5424.3  487.25  5538.2     487  5641.3   488.5
#Mann= 5 ,-1 , 0
  4313.5     .05       0  4874.9     .12       0  4997.4     .07       0
  5003.4     .12       0  5184.9     .16       0
Bank Sta=4997.4,5003.4
XS Rating Curve= 0 ,0
Exp/Cntr=0.3,0.1

Type RM Length L Ch R = 1 ,56738   ,1022,1022,1022
BEGIN DESCRIPTION:
PATTON CREEK 69.0
END DESCRIPTION:
XS GIS Cut Line= 2
      3520831.07     10589808.78      3520601.03     10588498.02
#Sta/Elev= 30
  4310.9   491.5    4704  485.39  4852.8  480.12  4876.6   481.2    4902   480.5
  4971.6  480.31  4978.1  479.55  4995.4  474.82  4998.1  474.32  5001.4  474.82
  5002.3  474.96  5025.9  478.61  5069.5  478.07  5120.2  479.15    5171  479.08
  5181.1  479.36    5199  481.31  5204.1  480.88  5242.1   483.1  5258.4  484.76
  5303.1  484.98  5403.4  487.26  5475.6  487.98  5503.5  490.43  5526.3  494.22
  5536.5  495.12  5545.1   495.3  5550.2  494.59  5617.7  495.14  5641.7  494.34
#Mann= 8 ,-1 , 0
  4310.9     .05       0    4902      .1       0  4995.4     .07       0
  5001.4      .1       0  5002.3     .12       0  5303.1     .16       0
  5403.4     .12       0  5503.5     .05       0
Bank Sta=4995.4,5001.4
XS Rating Curve= 0 ,0
Exp/Cntr=0.3,0.1

Type RM Length L Ch R = 1 ,55716   ,558,558,558
BEGIN DESCRIPTION:
PATTON CREEK 58.1
END DESCRIPTION:
XS GIS Cut Line= 3
      3521354.13     10589845.45      3521131.92     10589182.28
      3521204.84     10588387.13
#Sta/Elev= 30
  4364.5   489.2  4684.9  484.85  4827.3  481.98  4890.5  478.47  4897.7  478.15
  4979.8  475.88  4985.1   473.5  4998.3   470.8  5001.1   470.3  5004.3   470.8
  5016.6  475.68  5022.4  476.29  5074.6  477.65  5104.7  477.09  5120.2  478.13
  5125.3  477.26    5165     480  5295.5   480.6  5355.8  481.64  5395.9  481.29
  5445.2  482.36  5466.2  481.49  5596.8  483.94  5616.9  485.32    5657  485.06
  5690.6  485.95  5775.1  488.35  5797.6  488.23  5849.9  490.46  5862.4   490.7
#Mann= 7 ,-1 , 0
  4364.5     .05       0  4890.5      .1       0  4897.7     .16       0
  4998.3     .07       0  5004.3     .16       0  5690.6      .1       0
  5849.9     .05       0
Bank Sta=4998.3,5004.3
XS Rating Curve= 0 ,0
Exp/Cntr=0.3,0.1

Type RM Length L Ch R = 1 ,55158   ,1325,1325,1325
BEGIN DESCRIPTION:
PATTON CREEK 67.0
END DESCRIPTION:
XS GIS Cut Line= 2
      3521631.92     10589800.31      3521527.75      10588369.8
#Sta/Elev= 30
  4268.8  486.46  4588.3   482.6  4946.9  476.07  4969.3  474.54  4979.3  474.67
  4989.4  471.99  4996.4  471.08  4999.1  470.58  5002.4  471.08  5009.4  474.57
  5029.5  477.42  5039.5  477.87    5163  476.56  5169.8  476.32  5189.9  473.91
    5210  476.23    5220  476.52  5260.1  474.55  5270.1  474.77  5290.2  476.96
    5297  476.63  5302.1  475.62  5310.2  476.97  5340.3  479.23  5360.3  478.84
  5430.5  479.72  5631.1  484.38  5671.2  486.11  5697.4  488.34  5703.1  488.47
#Mann= 5 ,-1 , 0
  4268.8     .05       0  4946.9     .16       0  4996.4     .07       0
  5002.4     .16       0  5697.4      .1       0
Bank Sta=4996.4,5002.4
XS Rating Curve= 0 ,0
Exp/Cntr=0.3,0.1

Type RM Length L Ch R = 1 ,53833   ,853,853,853
BEGIN DESCRIPTION:
PATTON CREEK 65.0
END DESCRIPTION:
XS GIS Cut Line= 4
      3522496.19      10589791.8       3521927.6     10588724.06
      3522092.11     10588489.69      3521979.69     10587908.09
#Sta/Elev= 30
  3639.6  482.69  4308.2   481.4  4365.8  482.16  4553.4  479.09    4684   478.6
  4727.9  476.13  4760.5  476.48  4782.5  474.86  4868.2  475.13  4939.7  471.97
  4975.4  473.13  4984.1  470.38  4990.2  467.11  4995.9  466.87  4998.6  466.37
  5001.9  466.87    5005  468.12  5011.1  474.54  5019.8  473.55    5026  475.33
  5040.8  473.53  5055.6  473.61  5061.7   472.4  5091.3  476.08  5217.5  479.25
  5442.8  488.23  5582.1  493.91  5583.5  493.88  5688.8  497.97    5728  498.13
#Mann= 7 ,-1 , 0
  3639.6     .05       0  4553.4     .16       0  4995.9     .07       0
  5001.9     .16       0  5442.8     .12       0  5582.1     .16       0
  5583.5     .12       0
Bank Sta=4995.9,5001.9
XS Rating Curve= 0 ,0
Exp/Cntr=0.3,0.1

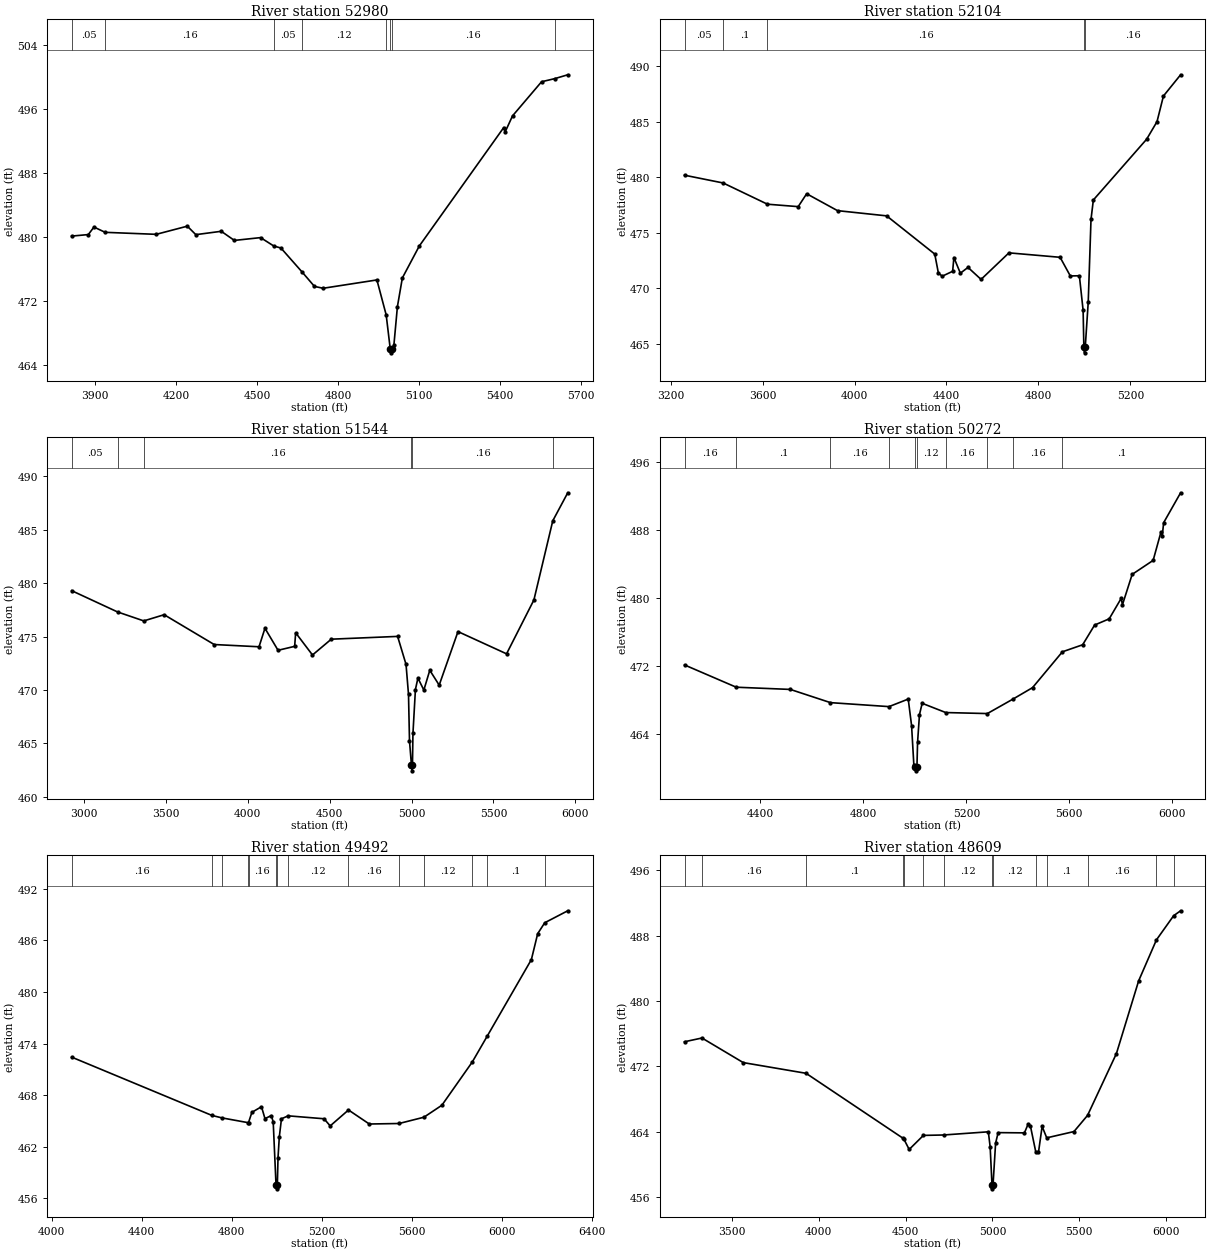
Type RM Length L Ch R = 1 ,52980   ,876,876,876
BEGIN DESCRIPTION:
PATTON CREEK 64.0
END DESCRIPTION:
XS GIS Cut Line= 2
      3522768.27     10589620.46      3522217.08     10587867.05
#Sta/Elev= 30
  3813.3  480.13    3875  480.32  3895.9  481.26  3937.5   480.6  4126.5  480.35
  4241.8  481.37  4273.3  480.31  4367.6  480.73  4416.1  479.59  4513.3  479.94
  4562.2  478.89  4588.6  478.64  4666.3  475.67  4712.9  473.84    4745  473.61
  4944.2  474.65  4978.6  470.28  4993.6  466.04  4996.3  465.54  4999.6  466.04
  5007.1  466.49  5020.2  471.32  5038.5   474.9  5101.4   478.9  5414.2   493.7
  5419.5  493.16  5446.6  495.15  5554.3  499.42  5603.3  499.81  5651.3  500.29
#Mann= 8 ,-1 , 0
  3813.3     .05       0  3937.5     .16       0  4562.2     .05       0
  4666.3     .12       0  4978.6     .16       0  4993.6     .07       0
  4999.6     .16       0  5603.3      .1       0
Bank Sta=4993.6,4999.6
XS Rating Curve= 0 ,0
Exp/Cntr=0.3,0.1

Type RM Length L Ch R = 1 ,52104   ,560,560,560
BEGIN DESCRIPTION:
PATTON CREEK 61.0
END DESCRIPTION:
XS GIS Cut Line= 3
      3523158.89     10589585.67      3523193.61     10588930.33
      3522533.88     10587580.48
#Sta/Elev= 30
  3260.1  480.19  3428.2  479.49  3620.9  477.58  3754.8  477.36  3791.6  478.52
  3925.8     477  4139.6  476.53    4349  473.09  4364.8  471.38  4381.7   471.1
  4426.8  471.54  4432.3  472.78  4460.4  471.37  4493.7  471.89  4550.5  470.81
  4671.8   473.2  4894.4   472.8  4938.9  471.12  4978.3  471.14  4994.6  468.02
  4997.8   464.7  5000.6   464.2  5003.8   464.7  5016.8  468.76  5028.9  476.21
  5039.1  477.96    5271  483.43  5316.1  485.01  5344.1  487.32  5418.8  489.23
#Mann= 5 ,-1 , 0
  3260.1     .05       0  3428.2      .1       0  3620.9     .16       0
  4997.8     .07       0  5003.8     .16       0
Bank Sta=4997.8,5003.8
XS Rating Curve= 0 ,0
Exp/Cntr=0.3,0.1

Type RM Length L Ch R = 1 ,51544   ,1272,1272,1272
BEGIN DESCRIPTION:
PATTON CREEK 61.1
END DESCRIPTION:
XS GIS Cut Line= 3
      3523321.23     10589584.36      3523876.77     10588896.88
      3522710.13      10587098.3
#Sta/Elev= 30
  2925.9   479.3  3205.8  477.31  3366.1  476.47  3490.4  477.05  3795.8  474.26
  4069.4  474.05  4105.6  475.78  4185.5  473.72  4286.9  474.09  4292.9  475.36
  4395.7  473.28  4510.4  474.76  4915.2  475.02  4966.6   472.4  4981.7  469.59
  4987.7  465.26  4999.8  462.94  5002.6  462.44  5005.8  462.94  5008.8  465.94
  5023.9  470.05  5039.1  471.12  5075.3     470  5111.6  471.85  5168.9  470.46
  5283.7  475.47  5580.1  473.39    5747  478.43  5862.2  485.84  5953.6  488.46
#Mann= 6 ,-1 , 0
  2925.9     .05       0  3205.8      .1       0  3366.1     .16       0
  4999.8     .07       0  5005.8     .16       0  5862.2     .12       0
Bank Sta=4999.8,5005.8
XS Rating Curve= 0 ,0
Exp/Cntr=0.3,0.1

Type RM Length L Ch R = 1 ,50272   ,780,780,780
BEGIN DESCRIPTION:
PATTON CREEK 60.0
END DESCRIPTION:
XS GIS Cut Line= 4
      3523984.89     10588450.67      3524063.02     10587660.69
      3524178.81     10587396.69      3524340.79     10586566.97
#Sta/Elev= 30
    4105   472.1    4306  469.47    4516  469.21  4672.1  467.65  4899.4  467.18
  4974.2  468.07  4987.2  464.95  4996.1  460.27  5002.1   460.1  5004.8   459.6
  5008.1   460.1  5010.5  462.96  5017.9  466.24  5028.4  467.57    5120  466.48
  5281.6  466.36  5380.7  468.06  5457.2  469.42  5573.2  473.65  5651.9  474.48
  5698.4  476.81    5755  477.54  5801.5  479.95  5806.6  479.21  5844.3  482.79
  5925.8  484.44  5956.2  487.79  5961.3  487.36  5966.6  488.89  6032.5  492.42
#Mann= 10 ,-1 , 0
    4105     .16       0    4306      .1       0  4672.1     .16       0
  4899.4     .12       0  5002.1     .07       0  5008.1     .12       0
    5120     .16       0  5281.6      .1       0  5380.7     .16       0
  5573.2      .1       0
Bank Sta=5002.1,5008.1
XS Rating Curve= 0 ,0
Exp/Cntr=0.3,0.1

Type RM Length L Ch R = 1 ,49492   ,883,883,883
BEGIN DESCRIPTION:
PATTON CREEK 58.0
END DESCRIPTION:
XS GIS Cut Line= 3
       3524096.4     10588667.73      3524895.04     10587369.94
      3525197.98     10586759.73
#Sta/Elev= 30
  4088.7  472.42  4711.9  465.65    4757  465.36  4870.3  464.82  4874.8  464.82
  4889.9  466.01  4932.5  466.66  4947.9  465.28  4976.5  465.63  4984.6  464.87
    4997  457.62  4999.7  457.12    5003  457.62  5005.9  460.72  5011.7  463.16
  5021.3  465.26  5051.1   465.6  5210.6  465.26  5237.8  464.43  5319.2  466.28
  5411.7  464.65  5544.1  464.71  5654.5  465.44  5734.3  466.83  5869.3  471.85
  5935.4  474.84  6132.1  483.75  6160.1  486.76  6191.5  488.03  6293.8  489.42
#Mann= 14 ,-1 , 0
  4088.7     .16       0  4711.9      .1       0    4757     .16       0
  4870.3     .12       0  4874.8     .16       0    4997     .07       0
    5003     .16       0  5051.1     .12       0  5319.2     .16       0
  5544.1      .1       0  5654.5     .12       0  5869.3     .16       0
  5935.4      .1       0  6191.5     .05       0
Bank Sta=4997,5003
XS Rating Curve= 0 ,0
Exp/Cntr=0.3,0.1

Type RM Length L Ch R = 1 ,48609   ,1367,1367,1367
BEGIN DESCRIPTION:
PATTON CREEK 56.0
END DESCRIPTION:
XS GIS Cut Line= 4
      3524274.31      10589353.7      3525218.79     10587982.13
      3525149.34      10587759.9      3525333.37     10586818.95
#Sta/Elev= 30
  3226.6  475.02  3327.1  475.48  3564.8  472.47  3926.5  471.16  4486.4  463.19
  4488.1  463.18  4520.4  461.84  4602.3  463.56  4718.2  463.61  4976.2     464
  4986.7  462.16  4997.3  457.52    5000  457.02  5003.3  457.52  5018.1  462.61
  5032.7   463.9  5184.1  463.87  5204.5   464.9  5218.5  464.72  5250.1  461.47
  5264.9  461.47    5286  464.66  5312.5  463.26  5469.4  464.03  5547.6  466.01
  5713.9  473.58  5841.9  482.48  5944.3  487.49  6043.5  490.45  6083.5  491.05
#Mann= 14 ,-1 , 0
  3226.6      .1       0  3327.1     .16       0  3926.5      .1       0
  4486.4     .16       0  4488.1     .12       0  4602.3     .16       0
  4718.2     .12       0  4997.3     .07       0  5003.3     .12       0
  5250.1     .16       0  5312.5      .1       0  5547.6     .16       0
  5944.3      .1       0  6043.5     .05       0
Bank Sta=4997.3,5003.3
XS Rating Curve= 0 ,0
Exp/Cntr=0.3,0.1

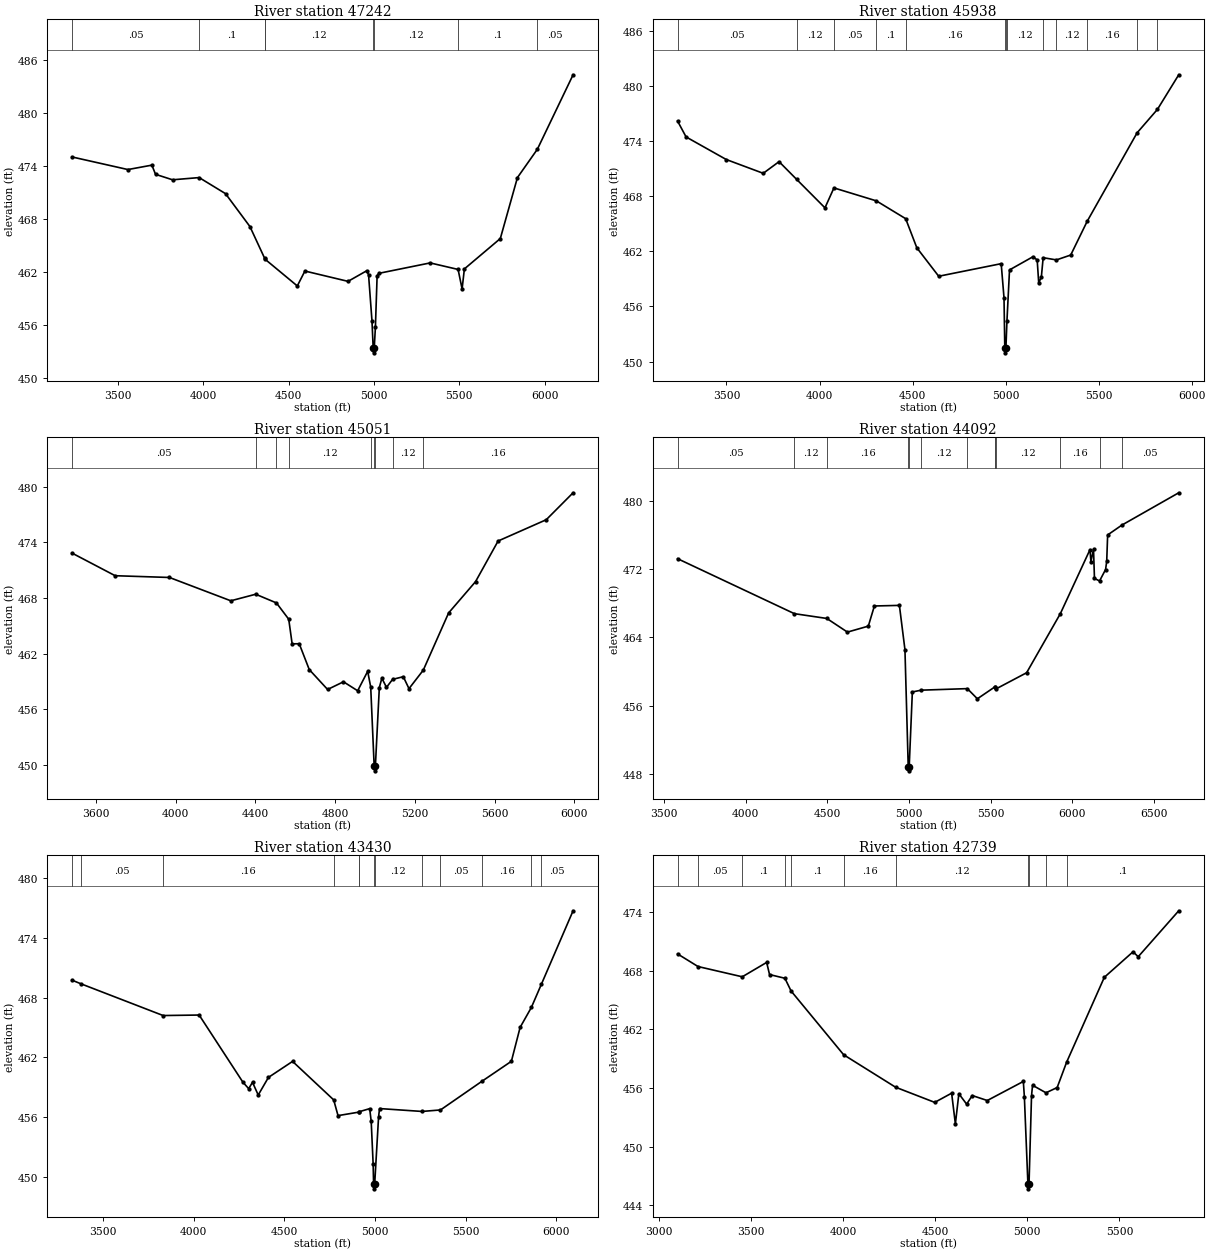
Type RM Length L Ch R = 1 ,47242   ,1304,1304,1304
BEGIN DESCRIPTION:
PATTON CREEK 46.2
END DESCRIPTION:
XS GIS Cut Line= 3
      3526086.82      10589785.9      3525557.33     10588475.18
      3525661.47     10586956.38
#Sta/Elev= 30
  3230.7  475.05  3558.8  473.62  3699.1  474.12  3720.6  473.08  3820.2  472.46
  3976.2  472.71  4130.5  470.89  4273.6  467.16  4359.1  463.59    4364  463.43
  4551.1  460.43  4595.6  462.12  4848.3  460.95  4958.6  462.16  4968.6  461.68
  4988.7  456.44  4995.7  453.35  4998.5  452.85  5001.7  453.35  5008.7  455.78
  5018.7  461.59  5028.8  461.86  5329.5  463.04  5493.1   462.3  5516.5  460.09
  5529.9  462.36  5740.4   465.8  5840.7  472.71  5957.4  475.92  6166.7  484.36
#Mann= 8 ,-1 , 0
  3230.7     .05       0  3976.2      .1       0  4359.1     .05       0
    4364     .12       0  4995.7     .07       0  5001.7     .12       0
  5493.1      .1       0  5957.4     .05       0
Bank Sta=4995.7,5001.7
XS Rating Curve= 0 ,0
Exp/Cntr=0.3,0.1

Type RM Length L Ch R = 1 ,45938   ,887,887,887
BEGIN DESCRIPTION:
PATTON CREEK 54.0
END DESCRIPTION:
XS GIS Cut Line= 4
      3527062.13     10589414.14      3526202.78     10588029.62
      3526007.46     10587643.33      3525751.51     10587066.35
#Sta/Elev= 30
  3237.1  476.19  3282.9  474.46    3499     472  3697.5   470.5  3782.5  471.77
    3877  469.84  4029.3  466.74  4077.5  468.91  4305.4   467.5    4463  465.56
    4523  462.39  4640.6  459.29  4976.4  460.66  4991.6  456.94  4995.8  451.45
  4998.6  450.95  5001.8  451.45  5007.3  454.39  5021.2  459.98  5147.6  461.42
  5169.9  461.06  5178.1  458.57  5192.2  459.19    5202  461.31  5273.5  461.07
  5350.1   461.6    5439  465.29  5706.9  474.91  5816.1  477.46  5930.7  481.23
#Mann= 13 ,-1 , 0
  3237.1     .05       0    3877     .12       0  4077.5     .05       0
  4305.4      .1       0    4463     .16       0  4995.8     .07       0
  5001.8     .16       0  5007.3     .12       0    5202     .16       0
  5273.5     .12       0    5439     .16       0  5706.9      .1       0
  5816.1     .05       0
Bank Sta=4995.8,5001.8
XS Rating Curve= 0 ,0
Exp/Cntr=0.3,0.1

Type RM Length L Ch R = 1 ,45051   ,959,959,959
BEGIN DESCRIPTION:
PATTON CREEK 53.0
END DESCRIPTION:
XS GIS Cut Line= 3
      3527577.66     10588978.03      3526642.11     10587691.64
      3525942.08     10587091.62
#Sta/Elev= 30
  3480.5  472.86  3697.4  470.41  3969.5  470.22  4277.1   467.7  4401.9  468.41
  4505.9  467.47  4567.5  465.71  4584.6  463.05  4620.2  463.06  4670.4  460.27
  4762.4  458.12    4842  458.95  4913.1  457.98  4963.3  460.08  4978.5  458.39
  4995.9  449.83  4998.6  449.33  5001.9  449.83  5021.7  458.32  5034.4  459.34
  5057.6  458.35  5088.2  459.21  5141.9   459.5  5170.4  458.21  5242.1  460.21
  5369.1  466.39  5504.1  469.77  5617.2  474.16  5858.6  476.46  5993.1  479.37
#Mann= 9 ,-1 , 0
  3480.5     .05       0  4401.9      .1       0  4505.9     .05       0
  4567.5     .12       0  4978.5     .16       0  4995.9     .07       0
  5001.9     .16       0  5088.2     .12       0  5242.1     .16       0
Bank Sta=4995.9,5001.9
XS Rating Curve= 0 ,0
Exp/Cntr=0.3,0.1

Type RM Length L Ch R = 1 ,44092   ,662,662,662
BEGIN DESCRIPTION:
PATTON CREEK 42.0
END DESCRIPTION:
XS GIS Cut Line= 4
      3527954.46     10588767.36      3527412.77     10587524.29
      3527098.87     10587319.46       3525931.7     10586660.16
#Sta/Elev= 30
  3581.5  473.21  4297.4  466.77    4496  466.21  4622.4  464.61  4750.4  465.31
  4787.6  467.67  4940.9  467.74  4974.9  462.56    4995  448.86  4997.7  448.36
    5001  448.86  5020.3   457.6  5075.1  457.81  5357.2  457.99  5418.7   456.8
  5524.2  458.17  5526.2  458.15  5533.3  457.96  5720.5  459.85  5927.2  466.77
  6108.9  474.27  6114.6  472.86  6130.5  474.33  6136.3   470.9  6167.5   470.6
  6204.4  471.94  6211.4   472.9  6217.1  475.99    6304  477.14  6652.8  480.93
#Mann= 13 ,-1 , 0
  3581.5     .05       0  4297.4     .12       0    4496     .16       0
    4995     .07       0    5001     .16       0  5075.1     .12       0
  5357.2     .16       0  5524.2      .1       0  5526.2     .16       0
  5533.3     .12       0  5927.2     .16       0  6167.5      .1       0
    6304     .05       0
Bank Sta=4995,5001
XS Rating Curve= 0 ,0
Exp/Cntr=0.3,0.1

Type RM Length L Ch R = 1 ,43430   ,691,691,691
BEGIN DESCRIPTION:
PATTON CREEK 50.0
END DESCRIPTION:
XS GIS Cut Line= 4
      3528100.54      10588519.3      3527646.22      10587116.3
      3527248.78     10586961.91      3526406.95     10586770.98
#Sta/Elev= 30
    3329  469.77  3380.2  469.39  3832.1  466.21  4030.8  466.26  4272.5   459.5
  4304.1  458.86  4325.1   459.5  4356.6  458.22  4412.9  459.99  4546.1   461.6
  4772.9  457.73  4796.8  456.15  4911.5   456.5  4913.1  456.54  4971.4  456.85
  4979.8  455.57  4990.5  451.28    4993  449.29  4995.7  448.79    4999  449.29
  5020.5  456.04  5025.9  456.86    5260  456.57    5362  456.72  5588.8  459.58
    5753  461.61  5801.2  465.02  5863.1  467.02  5918.8  469.37  6093.3  476.74
#Mann= 13 ,-1 , 0
    3329      .1       0  3380.2     .05       0  3832.1     .16       0
  4772.9     .12       0  4911.5     .16       0  4913.1     .12       0
    4993     .07       0    4999     .12       0    5260      .1       0
    5362     .05       0  5588.8     .16       0  5863.1      .1       0
  5918.8     .05       0
Bank Sta=4993,4999
XS Rating Curve= 0 ,0
Exp/Cntr=0.3,0.1

Type RM Length L Ch R = 1 ,42739   ,545,545,545
BEGIN DESCRIPTION:
PATTON CREEK 49.0
END DESCRIPTION:
XS GIS Cut Line= 3
      3528279.36     10588501.64      3527952.11     10586819.67
      3527496.75     10585921.97
#Sta/Elev= 30
    3102  469.72  3212.9  468.43  3453.1  467.38  3585.5  468.85  3601.2  467.61
  3684.5  467.23    3718  465.93  4003.3  459.41  4285.3  456.09  4497.7  454.54
  4589.4  455.48  4609.8  452.34  4628.7  455.42  4670.9  454.36  4701.4  455.24
  4782.9  454.73  4978.6  456.68  4984.2  455.13  5003.5   446.2  5006.2   445.7
  5009.5   446.2  5023.1  455.22  5028.7  456.29  5101.6  455.52  5162.3  456.06
  5213.8  458.66  5418.3  467.33  5574.2  469.94    5602  469.43  5822.1  474.13
#Mann= 11 ,-1 , 0
    3102      .1       0  3212.9     .05       0  3453.1      .1       0
  3684.5     .16       0    3718      .1       0  4003.3     .16       0
  4285.3     .12       0  5003.5     .07       0  5009.5     .12       0
  5101.6     .16       0  5213.8      .1       0
Bank Sta=5003.5,5009.5
XS Rating Curve= 0 ,0
Exp/Cntr=0.3,0.1