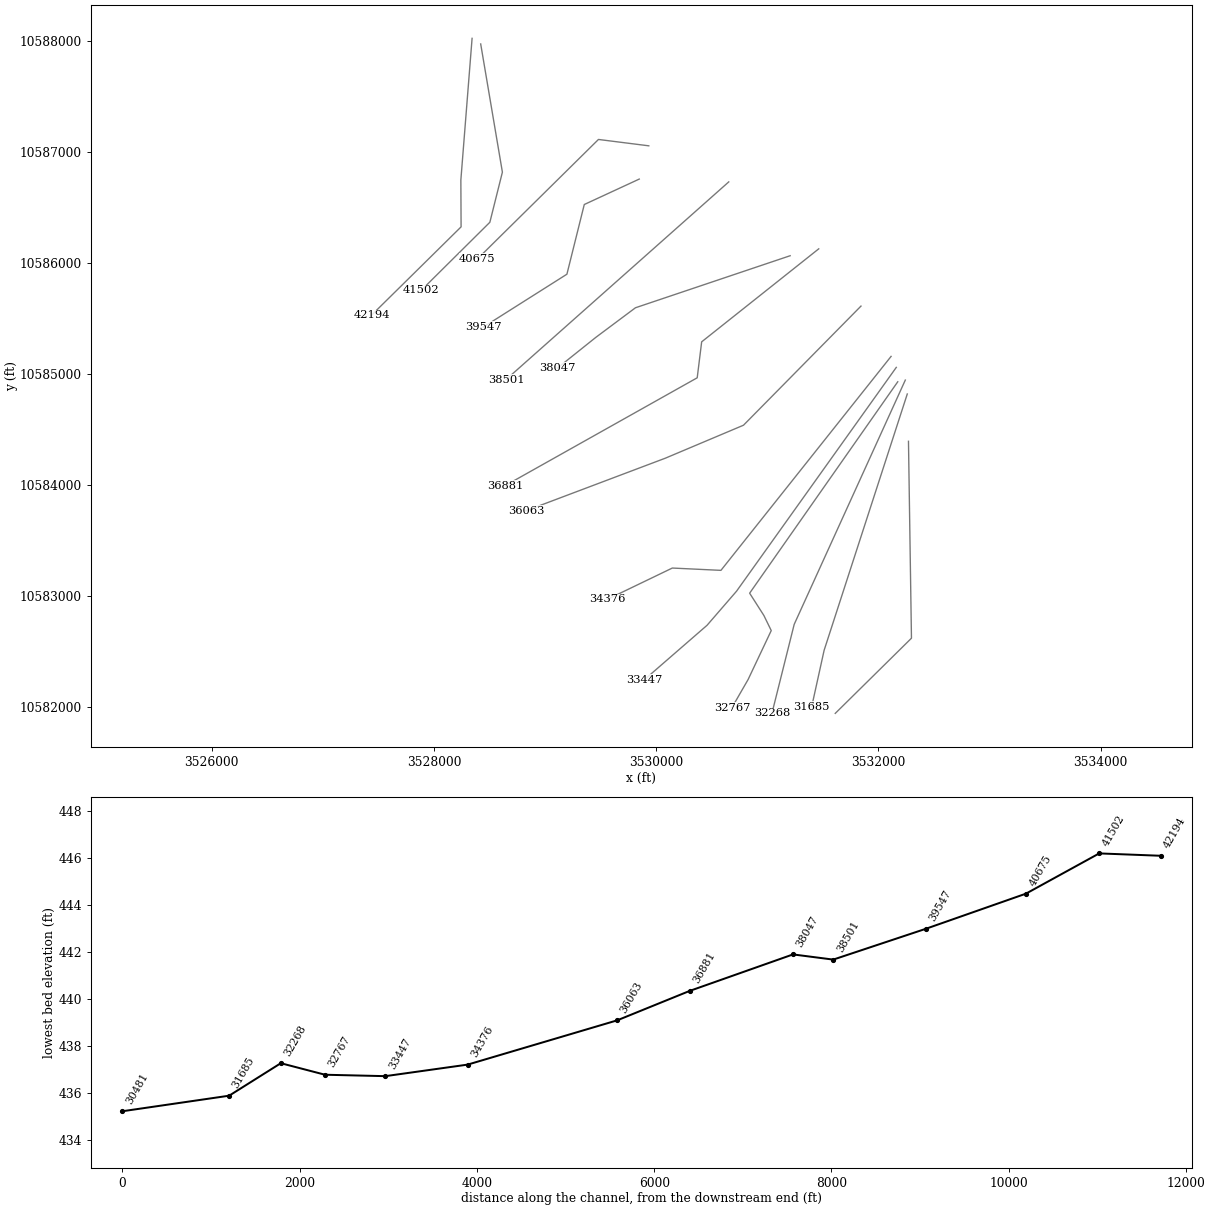
HEC-RAS study PATTON CREEK.prj: PATTON CREEK Base Level Engineering

--- PATTON CREEK.g01 (geometry) --- (continued)

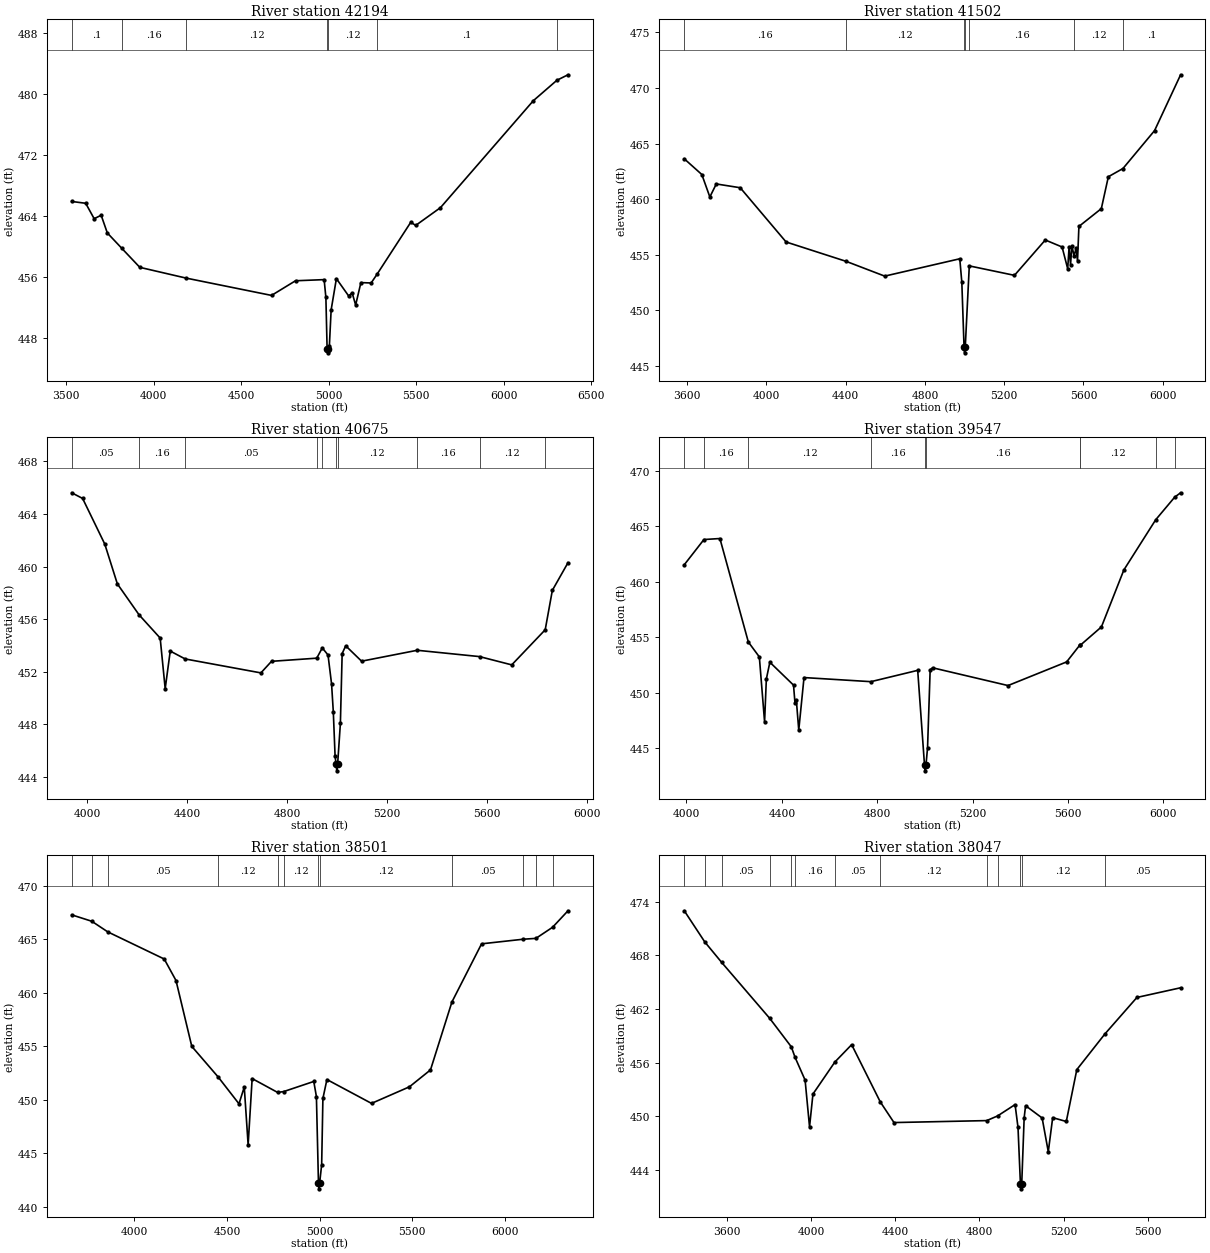
Type RM Length L Ch R = 1 ,42194   ,692,692,692
BEGIN DESCRIPTION:
PATTON CREEK 39.1
END DESCRIPTION:
XS GIS Cut Line= 4
      3528343.19      10588019.6      3528242.11     10586743.51
      3528244.23     10586321.63      3527438.01     10585525.82
#Sta/Elev= 30
  3531.8  465.93  3611.9  465.69  3660.2  463.67  3700.3  464.12  3735.4   461.8
  3817.5   459.8    3921  457.29  4185.4  455.88  4673.3  453.61  4810.3  455.53
  4973.8  455.68  4983.8  453.34  4990.8  446.58  4993.5  446.08  4996.8  446.58
  5003.8  447.04  5013.8  451.71  5043.8  455.81  5113.8  453.54  5133.8  453.94
  5153.8  452.35  5183.8  455.29  5242.3  455.24  5276.4   456.4  5468.6   463.2
  5496.9  462.79  5638.3  465.12  6168.6  479.14  6303.3  481.82  6366.6  482.54
#Mann= 7 ,-1 , 0
  3531.8      .1       0  3817.5     .16       0  4185.4     .12       0
  4990.8     .07       0  4996.8     .12       0  5276.4      .1       0
  6303.3     .05       0
Bank Sta=4990.8,4996.8
XS Rating Curve= 0 ,0
Exp/Cntr=0.3,0.1

Type RM Length L Ch R = 1 ,41502   ,827,827,827
BEGIN DESCRIPTION:
PATTON CREEK 48.0
END DESCRIPTION:
XS GIS Cut Line= 4
      3528420.66     10587968.86      3528615.97     10586814.34
      3528503.12     10586362.95      3527886.98     10585751.15
#Sta/Elev= 30
  3585.7  463.63  3674.2  462.22  3714.7   460.2  3747.2  461.37    3868  461.03
  4099.5  456.15  4403.8   454.4  4597.1  453.08  4975.9  454.64  4986.2  452.53
  4997.5  446.68  5000.2  446.18  5003.5  446.68  5023.9     454  5251.8  453.15
  5407.4  456.33  5492.2   455.7  5520.5  453.74  5527.6  455.74  5534.7  454.11
  5541.8  455.81  5552.6  454.88  5562.9  455.61    5570  454.46  5577.1  457.55
  5690.2  459.15  5725.6  462.02  5799.4  462.76  5958.9  466.17  6090.2  471.19
#Mann= 7 ,-1 , 0
  3585.7     .16       0  4403.8     .12       0  4997.5     .07       0
  5003.5     .12       0  5023.9     .16       0  5552.6     .12       0
  5799.4      .1       0
Bank Sta=4997.5,5003.5
XS Rating Curve= 0 ,0
Exp/Cntr=0.3,0.1

Type RM Length L Ch R = 1 ,40675   ,1128,1128,1128
BEGIN DESCRIPTION:
PATTON CREEK 46.1
END DESCRIPTION:
XS GIS Cut Line= 3
      3529933.58     10587051.53      3529480.48     10587108.82
      3528391.91     10586033.26
#Sta/Elev= 30
    3938  465.62  3981.8  465.19  4070.5  461.72  4120.9  458.69  4208.1  456.33
  4292.3  454.57  4312.4  450.72  4332.6  453.58  4392.4  452.98  4695.6  451.92
  4738.1   452.8  4919.1  453.04  4941.4  453.82  4964.3  453.28  4978.5  451.08
  4985.5  448.95  4992.6  445.58  4996.7  444.97  4999.4  444.47  5002.7  444.97
  5013.8  448.08  5020.9  453.39  5035.1  453.98  5098.7  452.81  5321.4  453.64
  5570.8  453.16  5699.8  452.53  5833.8   455.2  5862.4   458.2    5925   460.3
#Mann= 10 ,-1 , 0
    3938     .05       0  4208.1     .16       0  4392.4     .05       0
  4919.1     .16       0  4941.4     .12       0  4996.7     .07       0
  5002.7     .12       0  5321.4     .16       0  5570.8     .12       0
  5833.8     .16       0
Bank Sta=4996.7,5002.7
XS Rating Curve= 0 ,0
Exp/Cntr=0.3,0.1

Type RM Length L Ch R = 1 ,39547   ,1046,1046,1046
BEGIN DESCRIPTION:
PATTON CREEK 38.2
END DESCRIPTION:
XS GIS Cut Line= 4
      3529847.66     10586752.04      3529352.88     10586522.88
      3529196.63     10585895.28      3528445.58      10585419.7
#Sta/Elev= 30
    3991  461.54  4073.4  463.81  4140.4   463.9  4259.6  454.58  4305.7  453.24
  4327.7  447.39  4335.1  451.25  4349.8  452.76    4449   450.7  4455.2  449.08
  4460.7  449.38    4471  446.65    4493  451.38  4773.6  451.01  4969.7  452.03
  4998.3  443.48    5001  442.98  5004.3  443.48    5011  445.06  5021.9  452.07
  5032.2  452.26  5348.4  450.66  5594.2  452.79  5648.5  454.28    5652   454.3
    5740  455.94  5834.1  461.07  5967.6  465.59  6047.4  467.63    6072  468.02
#Mann= 10 ,-1 , 0
    3991     .05       0  4073.4     .16       0  4259.6     .12       0
  4773.6     .16       0  4998.3     .07       0  5004.3     .16       0
  5648.5     .16       0    5652     .12       0  5967.6     .16       0
  6047.4     .12       0
Bank Sta=4998.3,5004.3
XS Rating Curve= 0 ,0
Exp/Cntr=0.3,0.1

Type RM Length L Ch R = 1 ,38501   ,454,454,454
BEGIN DESCRIPTION:
PATTON CREEK 37.1
END DESCRIPTION:
XS GIS Cut Line= 2
      3530653.23      10586726.7       3528648.7     10584946.05
#Sta/Elev= 30
  3660.8  467.29  3769.4  466.69  3855.5   465.7  4160.8  463.16  4224.4  461.15
  4309.7  454.99  4452.1  452.13  4564.7  449.62  4593.2  451.19  4614.1  445.79
  4635.8  451.98  4773.9  450.68    4807  450.77  4968.7  451.71  4982.9   450.3
  4994.1  442.17  4996.8  441.67  5000.1  442.17  5011.3  443.93    5018  450.12
  5039.7  451.89  5280.6  449.66  5485.5  451.21  5599.2  452.79  5714.9  459.14
  5875.2  464.58  6100.1  465.01  6168.7  465.09  6258.9  466.13    6342  467.67
#Mann= 12 ,-1 , 0
  3660.8     .05       0  3769.4     .12       0  3855.5     .05       0
  4452.1     .12       0  4773.9     .16       0    4807     .12       0
  4994.1     .07       0  5000.1     .12       0  5714.9     .05       0
  6100.1      .1       0  6168.7     .16       0  6258.9     .05       0
Bank Sta=4994.1,5000.1
XS Rating Curve= 0 ,0
Exp/Cntr=0.3,0.1

Type RM Length L Ch R = 1 ,38047   ,1166,1166,1166
BEGIN DESCRIPTION:
PATTON CREEK 44.0
END DESCRIPTION:
XS GIS Cut Line= 4
      3531205.86     10586061.72      3529813.54     10585592.98
       3529455.9     10585325.62      3529111.42     10585050.02
#Sta/Elev= 30
  3398.2  472.98  3495.4   469.5    3576   467.2  3804.3  460.94  3906.4  457.77
  3924.3  456.59  3971.9  454.05    3993  448.82  4009.2  452.49  4113.3  456.07
    4193  458.01  4328.9  451.61    4394   449.3  4834.3  449.52  4885.8  450.04
    4969  451.31  4982.9  448.76  4994.5  442.39  4997.3  441.89  5000.5  442.39
  5012.1  449.82  5018.9  451.19  5097.5  449.81  5126.7  446.04  5147.6  449.85
  5212.2  449.42  5262.2  455.22  5395.6  459.21  5547.6  463.29    5755  464.37
#Mann= 13 ,-1 , 0
  3398.2     .12       0  3495.4     .16       0    3576     .05       0
  3804.3     .16       0  3906.4     .12       0  3924.3     .16       0
  4113.3     .05       0  4328.9     .12       0  4834.3     .16       0
  4885.8     .12       0  4994.5     .07       0  5000.5     .12       0
  5395.6     .05       0
Bank Sta=4994.5,5000.5
XS Rating Curve= 0 ,0
Exp/Cntr=0.3,0.1

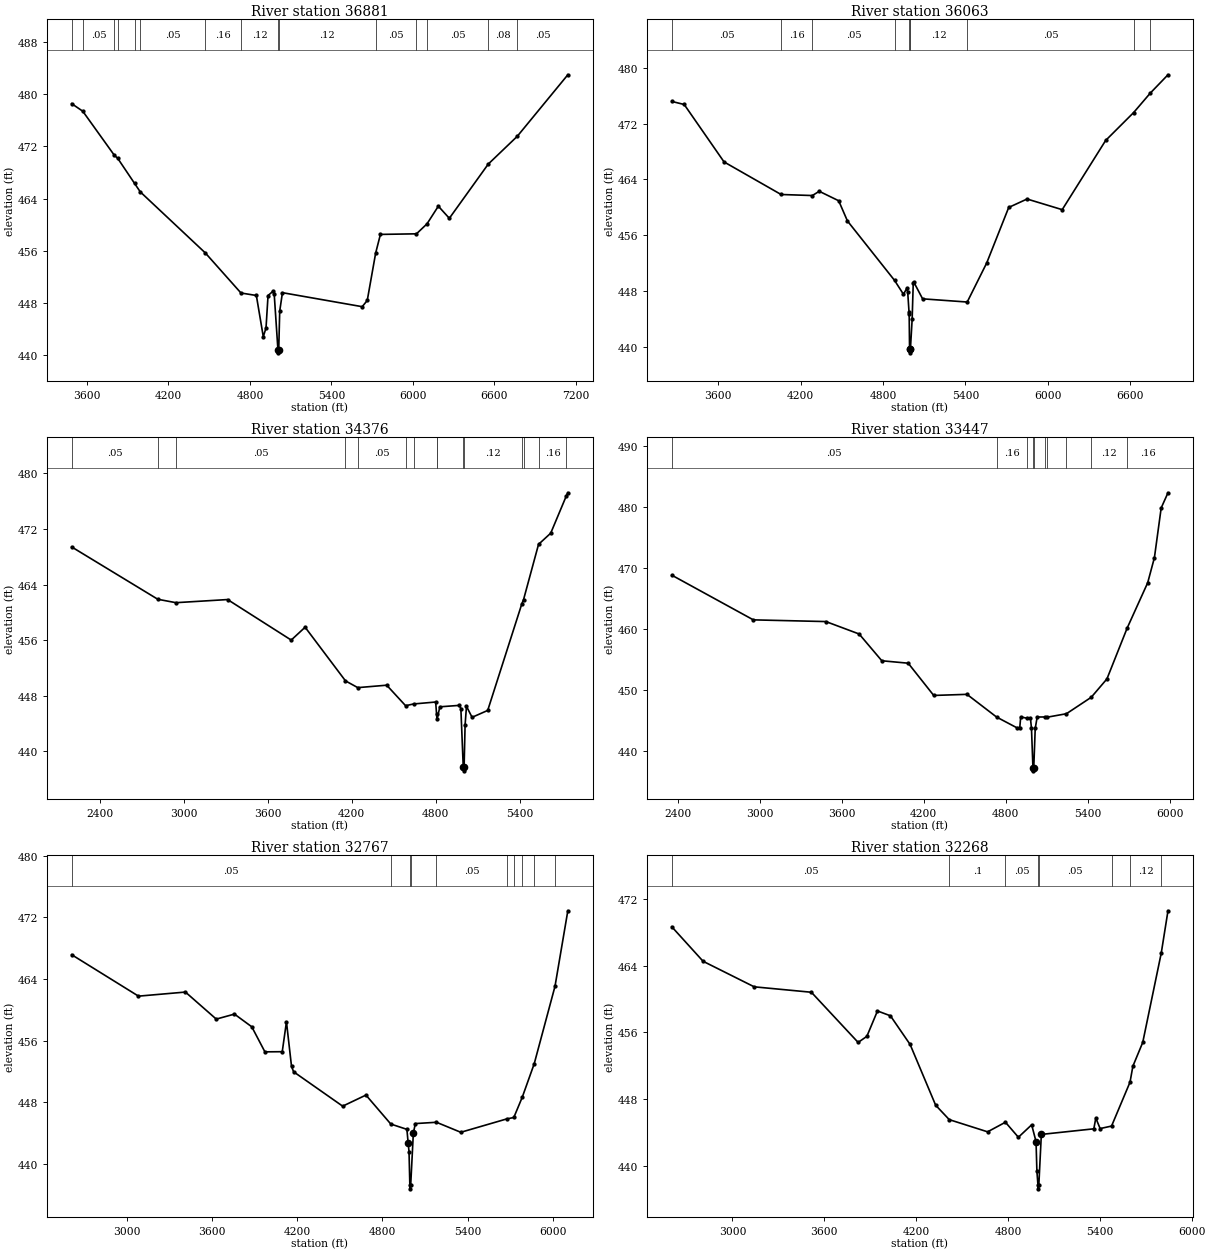
Type RM Length L Ch R = 1 ,36881   ,818,818,818
BEGIN DESCRIPTION:
PATTON CREEK 35.2
END DESCRIPTION:
XS GIS Cut Line= 4
      3531463.01     10586123.74      3530409.38     10585286.11
      3530369.23     10584962.26      3528642.12     10583991.65
#Sta/Elev= 30
  3487.1  478.57  3568.8  477.41  3801.7  470.64  3825.3  470.21  3950.1  466.34
  3992.2  465.04  4471.2  455.67  4733.8  449.52  4847.1  449.14  4898.1  442.82
  4918.2  444.15  4933.1  449.13  4968.6  449.77  4978.7   449.3  5005.9  440.84
  5008.7  440.34  5011.9  440.84  5019.1  446.74  5039.1  449.57  5626.5  447.42
  5663.7  448.38  5725.6  455.65  5760.6  458.51  6026.2   458.6  6103.7  460.13
  6187.1  462.84  6268.1  460.98  6554.7   469.3  6768.3  473.56  7140.6     483
#Mann= 15 ,-1 , 0
  3487.1     .16       0  3568.8     .05       0  3801.7     .16       0
  3825.3     .05       0  3950.1     .16       0  3992.2     .05       0
  4471.2     .16       0  4733.8     .12       0  5005.9     .07       0
  5011.9     .12       0  5725.6     .05       0  6026.2     .12       0
  6103.7     .05       0  6554.7     .08       0  6768.3     .05       0
Bank Sta=5005.9,5011.9
XS Rating Curve= 0 ,0
Exp/Cntr=0.3,0.1

Type RM Length L Ch R = 1 ,36063   ,1687,1687,1687
BEGIN DESCRIPTION:
PATTON CREEK 34.1
END DESCRIPTION:
XS GIS Cut Line= 4
      3531843.17     10585608.08      3530785.89     10584535.17
      3530082.77      10584238.3       3528827.6     10583764.36
#Sta/Elev= 30
  3262.7  475.21  3352.9  474.77  3642.8  466.52  4057.9  461.84  4285.4  461.69
  4335.8   462.3  4477.2  460.94  4540.8  458.04  4883.8   449.5  4948.7   447.5
  4972.4  448.34  4979.4  447.86  4989.4  444.89  4990.2  444.65  4993.1  439.59
  4995.9  439.09  4999.1  439.59  5011.9  443.91  5019.8  449.09  5025.3   449.2
  5087.9  446.85  5412.7  446.39  5554.3  451.99  5714.7  459.98  5848.3  461.19
    6104  459.66  6420.1   469.6  6624.3  473.62  6745.3  476.41  6873.9  479.04
#Mann= 10 ,-1 , 0
  3262.7     .05       0  4057.9     .16       0  4285.4     .05       0
  4883.8     .16       0  4989.4     .12       0  4993.1     .07       0
  4999.1     .12       0  5412.7     .05       0  6624.3     .08       0
  6745.3     .05       0
Bank Sta=4993.1,4999.1
XS Rating Curve= 0 ,0
Exp/Cntr=0.3,0.1

Type RM Length L Ch R = 1 ,34376   ,929,929,929
BEGIN DESCRIPTION:
PATTON CREEK 32.1
END DESCRIPTION:
XS GIS Cut Line= 4
      3532114.04     10585154.99      3530582.77     10583227.88
      3530145.27     10583248.72      3529561.93     10582967.46
#Sta/Elev= 30
  2198.1  469.42    2814  461.89  2943.3   461.4  3312.8  461.85  3767.7  456.02
    3867  457.87  4155.7  450.15  4243.5  449.18  4450.3  449.53  4585.3  446.58
  4642.6  446.83  4800.3  447.11  4806.5  445.45  4809.7   444.6  4830.4  446.42
  4970.5  446.63  4980.5  446.16  4997.6  437.71  5000.3  437.21  5003.6  437.71
  5010.6   443.8  5020.6  446.49  5060.6  444.91  5172.3   445.9  5416.4  461.24
  5428.4  461.83  5535.7  469.79  5622.8   471.4  5735.4  476.81  5745.1  477.21
#Mann= 15 ,-1 , 0
  2198.1     .05       0    2814     .12       0  2943.3     .05       0
  4155.7     .12       0  4243.5     .05       0  4585.3     .16       0
  4642.6     .05       0  4806.5     .16       0  4809.7     .12       0
  4997.6     .07       0  5003.6     .12       0  5416.4     .16       0
  5428.4     .12       0  5535.7     .16       0  5735.4     .12       0
Bank Sta=4997.6,5003.6
XS Rating Curve= 0 ,0
Exp/Cntr=0.3,0.1

Type RM Length L Ch R = 1 ,33447   ,680,680,680
BEGIN DESCRIPTION:
PATTON CREEK 31.1
END DESCRIPTION:
XS GIS Cut Line= 4
       3532160.9     10585056.01      3530723.39     10583040.38
      3530457.77     10582733.09      3529892.13     10582241.66
#Sta/Elev= 30
  2356.7  468.82  2953.3  461.49  3484.3  461.21  3727.7  459.17  3893.6  454.78
  4086.6  454.38  4273.5  449.09  4516.8  449.27  4733.2  445.55  4882.5  443.78
  4903.3  443.83  4910.1  445.57  4956.3  445.35  4981.2  445.37  4988.9  443.68
  4999.6  437.22  5002.3  436.72  5005.6  437.22  5016.3  443.67  5030.6  445.55
  5087.6  445.56    5101  445.51  5244.7  446.09  5426.4  448.79  5541.1   451.8
  5689.1  460.14  5839.3  467.57  5888.7  471.71  5938.1  479.85  5987.9  482.34
#Mann= 10 ,-1 , 0
  2356.7     .05       0  4733.2     .16       0  4956.3     .12       0
  4999.6     .07       0  5005.6     .12       0  5087.6     .16       0
    5101     .05       0  5244.7     .16       0  5426.4     .12       0
  5689.1     .16       0
Bank Sta=4999.6,5005.6
XS Rating Curve= 0 ,0
Exp/Cntr=0.3,0.1

Type RM Length L Ch R = 1 ,32767   ,499,499,499
BEGIN DESCRIPTION:
PATTON CREEK 40.1
END DESCRIPTION:
XS GIS Cut Line= 6
      3532174.08     10584926.38      3530841.09     10583022.31
      3530969.57     10582820.92      3531035.54      10582685.5
      3530827.21     10582244.53       3530681.4      10581991.1
#Sta/Elev= 30
  2611.2  467.17  3081.8  461.79  3412.3  462.32  3629.4  458.81  3757.5  459.46
  3879.6  457.81    3972  454.56  4094.1  454.58  4123.7  458.46  4159.5  452.66
  4174.3  451.97  4519.6  447.51  4683.5  448.95  4858.5  445.19  4971.9   444.5
  4980.8  442.71  4986.8  441.62  4992.6  437.28  4995.3  436.78  4998.6  437.28
  5017.2  443.99  5031.2  445.25    5180  445.42  5351.4  444.12    5674  445.85
  5724.7  446.04  5784.6  448.69  5868.5  453.02  6014.8  463.07  6105.1  472.87
#Mann= 10 ,-1 , 0
  2611.2     .05       0  4858.5     .16       0  4992.6     .07       0
  4998.6     .16       0    5180     .05       0    5674     .16       0
  5724.7     .05       0  5784.6     .16       0  5868.5     .12       0
  6014.8     .05       0
Bank Sta=4980.8,5017.2
XS Rating Curve= 0 ,0
Exp/Cntr=0.3,0.1

Type RM Length L Ch R = 1 ,32268   ,583,583,583
BEGIN DESCRIPTION:
PATTON CREEK 39.0
END DESCRIPTION:
XS GIS Cut Line= 3
      3532242.11     10584941.65      3531242.11     10582741.64
      3531042.11     10581941.68
#Sta/Elev= 30
  2604.1  468.66  2808.4  464.53  3142.4  461.47  3515.8  460.82  3821.2  454.81
  3878.3  455.54  3947.5  458.58  4032.1     458  4160.6  454.57  4327.6  447.29
  4416.5  445.56    4667   444.1  4783.5  445.25    4868  443.45  4954.8  444.94
  4983.4  442.93  4988.9  439.42  4995.7  437.77  4998.5  437.27  5001.7  437.77
    5018  443.79  5360.9  444.46  5373.8  445.75  5402.1  444.49  5476.7  444.79
  5597.3  450.05    5616  451.96  5680.4  454.81  5801.5  465.53  5845.3  470.58
#Mann= 8 ,-1 , 0
  2604.1     .05       0  4416.5      .1       0  4783.5     .05       0
  4995.7     .03       0  5001.7     .05       0  5476.7     .16       0
  5597.3     .12       0  5801.5     .05       0
Bank Sta=4983.4,5018
XS Rating Curve= 0 ,0
Exp/Cntr=0.3,0.1

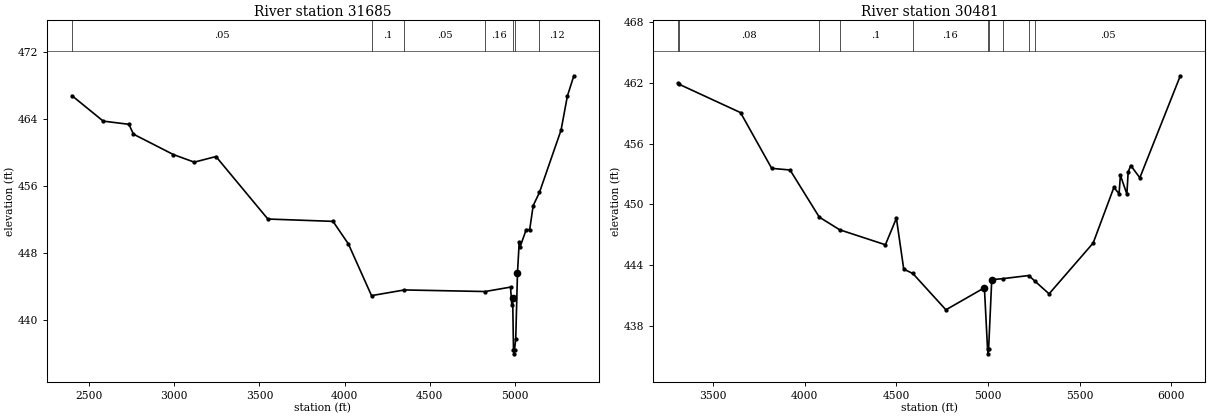
Type RM Length L Ch R = 1 ,31685   ,1204,1204,1204
BEGIN DESCRIPTION:
PATTON CREEK 30.1
END DESCRIPTION:
XS GIS Cut Line= 3
      3532259.87     10584816.46      3531511.44     10582508.04
      3531399.19     10581998.27
#Sta/Elev= 30
  2398.5   466.8  2582.3  463.75  2733.2  463.37  2759.9  462.19  2994.3  459.75
    3117  458.84  3244.6  459.51  3549.4  452.03  3932.3  451.75  4022.5  449.05
  4158.5  442.86  4351.9  443.54  4825.9  443.35  4975.1  443.88  4982.6  441.76
  4987.7  442.59  4992.6  436.39  4995.4  435.89  4998.6  436.39  5005.8  437.71
  5016.1  445.62  5026.3  449.31  5031.4   448.7  5067.3  450.76  5087.8  450.77
  5108.2  453.63    5145  455.21  5272.1  462.68  5309.1  466.75  5347.2  469.18
#Mann= 7 ,-1 , 0
  2398.5     .05       0  4158.5      .1       0  4351.9     .05       0
  4825.9     .16       0  4992.6     .07       0  4998.6     .16       0
    5145     .12       0
Bank Sta=4987.7,5016.1
XS Rating Curve= 0 ,0
Exp/Cntr=0.3,0.1

Type RM Length L Ch R = 1 ,30481   ,97,97,97
BEGIN DESCRIPTION:
PATTON CREEK 37.3
END DESCRIPTION:
XS GIS Cut Line= 3
      3532270.58     10584390.36      3532297.49     10582616.89
      3531611.71     10581939.79
#Sta/Elev= 30
  3311.6  462.01  3315.7  461.87  3650.4  459.07  3820.4  453.56  3920.4   453.4
    4080  448.74  4191.2  447.49  4440.5  446.01  4500.5  448.63  4540.5   443.6
  4590.2  443.17  4770.5  439.58  4980.5  441.76  4997.5  435.73  5000.3  435.23
  5003.5  435.73  5020.5  442.56  5080.4  442.66  5222.8  442.97  5257.3  442.39
  5333.2  441.16  5573.6  446.18  5686.8  451.68    5715  451.05  5722.2  452.88
  5757.5  451.02  5764.6  453.21  5778.7  453.84  5828.2  452.63    6049  462.71
#Mann= 10 ,-1 , 0
  3311.6     .05       0  3315.7     .08       0    4080     .05       0
  4191.2      .1       0  4590.2     .16       0  4997.5     .07       0
  5003.5     .16       0  5080.4     .05       0  5222.8     .16       0
  5257.3     .05       0
Bank Sta=4980.5,5020.5
XS Rating Curve= 0 ,0
Exp/Cntr=0.3,0.1