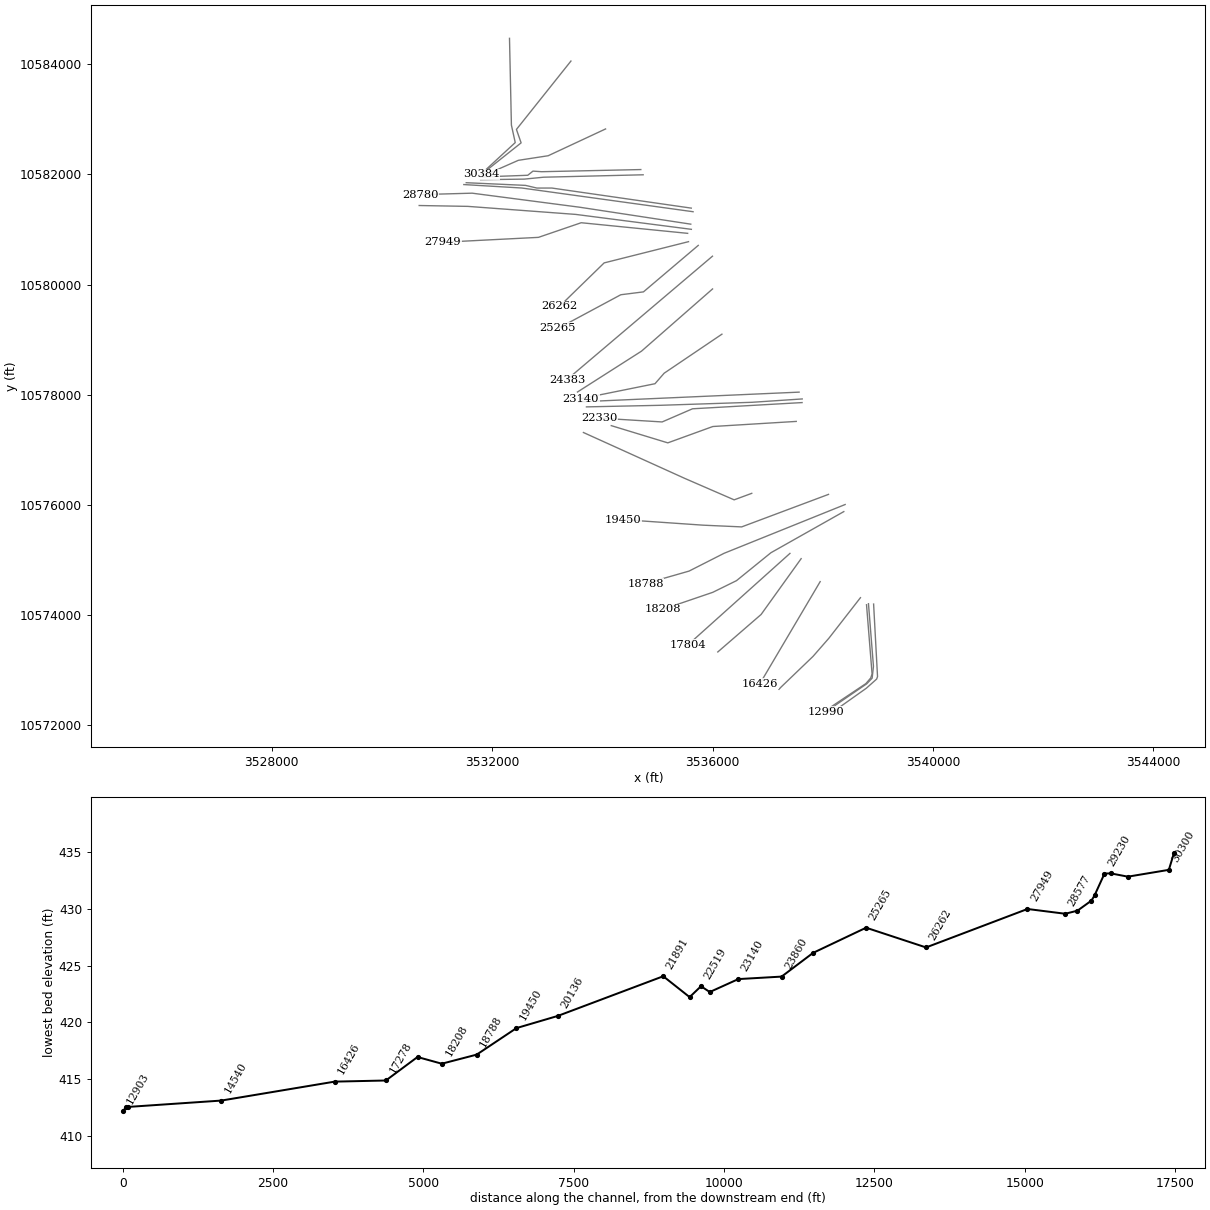
HEC-RAS study PATTON CREEK.prj: PATTON CREEK Base Level Engineering

--- PATTON CREEK.g01 (geometry) --- (continued)

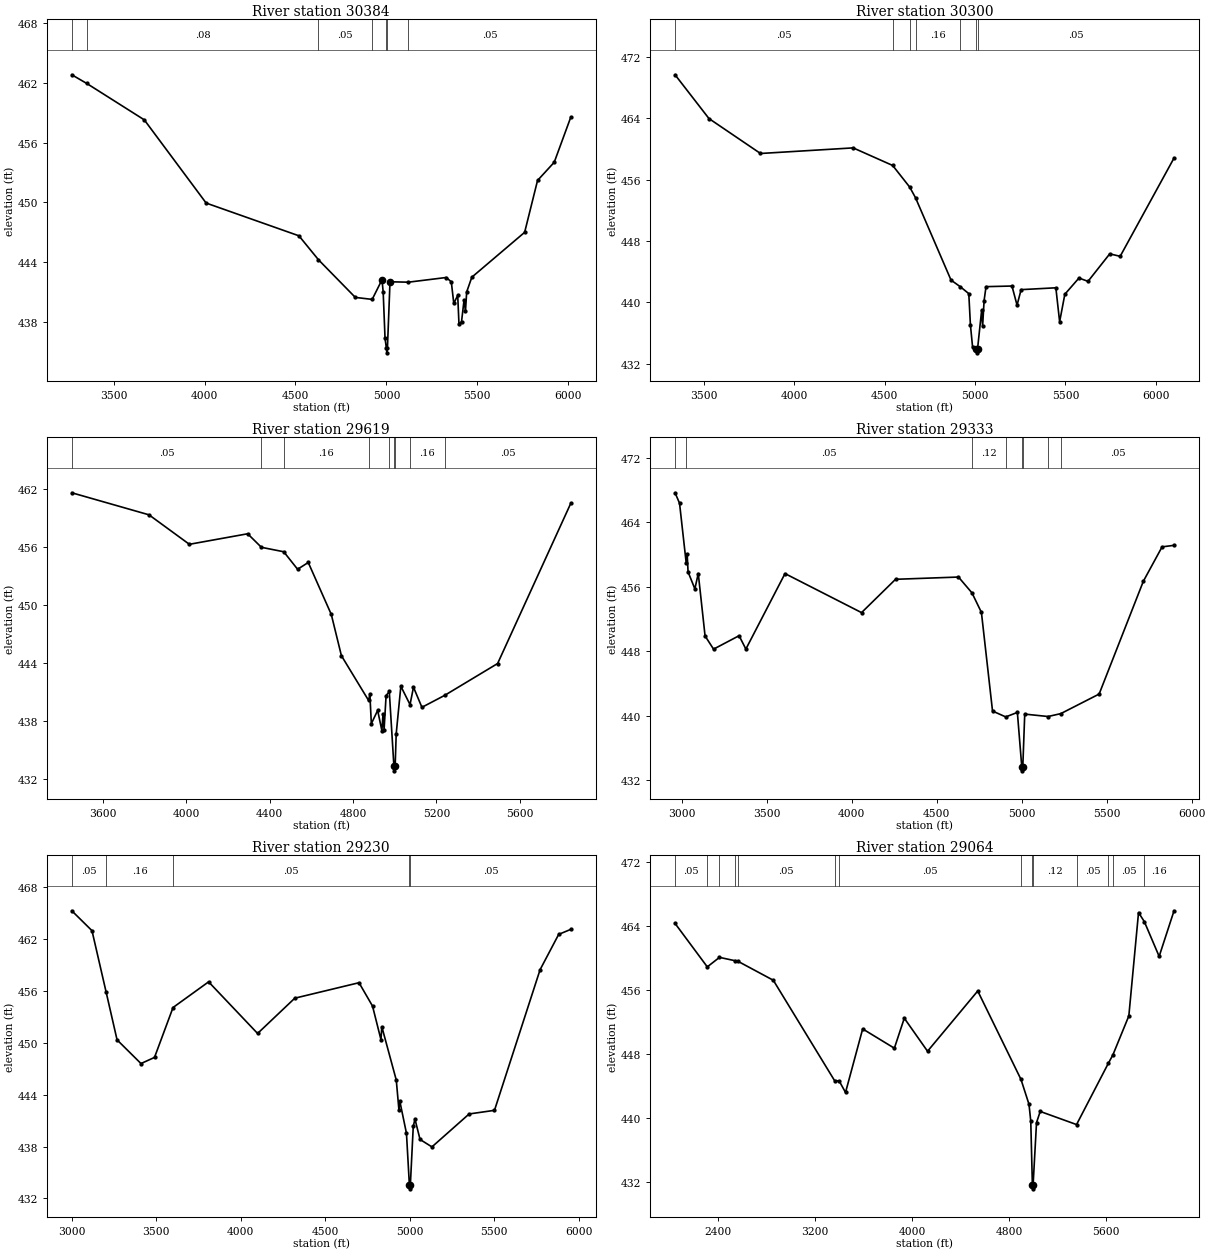
Type RM Length L Ch R = 1 ,30384   ,84,84,84
BEGIN DESCRIPTION:
PATTON CREEK 37.0
END DESCRIPTION:
XS GIS Cut Line= 4
      3532314.85     10584470.17      3532349.57     10582894.66
      3532419.01     10582577.82      3531799.31     10582005.79
#Sta/Elev= 30
  3270.2  462.83  3352.3  461.96  3668.8   458.3  4008.9  449.94    4519  446.65
  4626.6  444.24  4829.1  440.46  4921.8  440.26  4975.9  442.24  4982.3  440.99
  4992.5  436.35  4999.7  435.39  5002.5  434.89  5005.7  435.39  5019.8  442.03
  5120.9  441.99  5328.6  442.46  5356.8  442.03  5370.5  439.86  5392.1  440.66
  5398.9  437.83    5413  438.01  5427.2  440.22  5434.6  439.05  5441.4  441.01
  5469.7  442.49  5760.1     447    5831  452.21  5922.8  454.04  6013.8  458.57
#Mann= 7 ,-1 , 0
  3270.2     .05       0  3352.3     .08       0  4626.6     .05       0
  4921.8     .16       0  4999.7     .07       0  5005.7     .16       0
  5120.9     .05       0
Bank Sta=4975.9,5019.8
XS Rating Curve= 0 ,0
Exp/Cntr=0.3,0.1

Type RM Length L Ch R = 1 ,30300   ,681,681,681
BEGIN DESCRIPTION:
PATTON CREEK 37.2
END DESCRIPTION:
XS GIS Cut Line= 4
       3533430.3     10584057.86      3532440.72     10582816.54
      3532525.78     10582572.62      3531810.47     10582004.01
#Sta/Elev= 30
  3340.7  469.65  3528.2  463.95  3813.2   459.4  4325.7  460.13  4544.2  457.84
  4638.5  455.02  4670.5  453.64    4867  442.91  4918.8  442.04  4965.2  441.15
  4974.2  437.08  4986.3  434.16  5007.6  433.94  5010.3  433.44  5013.6  433.94
  5036.3  438.99  5041.6  436.89  5049.9  440.25  5060.5  442.06    5204  442.14
  5232.1  439.65  5254.6  441.67  5446.7  441.91  5467.6  437.49  5496.4  441.07
  5574.5  443.18  5624.6  442.75  5744.7  446.33  5802.4  446.01  6100.3  458.81
#Mann= 7 ,-1 , 0
  3340.7     .05       0  4544.2     .16       0  4638.5     .05       0
  4670.5     .16       0  4918.8     .05       0  5007.6     .04       0
  5013.6     .05       0
Bank Sta=5007.6,5013.6
XS Rating Curve= 0 ,0
Exp/Cntr=0.3,0.1

Type RM Length L Ch R = 1 ,29619   ,286,286,286
BEGIN DESCRIPTION:
PATTON CREEK 29.0
END DESCRIPTION:
XS GIS Cut Line= 4
      3534058.79     10582825.23       3533017.1     10582339.11
      3532475.44     10582255.78      3531836.84     10581974.65
#Sta/Elev= 30
    3450   461.6  3820.5  459.32  4014.4  456.27  4294.2  457.36  4360.1  455.96
  4467.3   455.5  4533.9  453.69  4585.1  454.39  4695.6  449.02  4744.2  444.75
  4874.7  440.12  4880.8  440.77  4887.9  437.72  4918.2  439.09  4938.5     437
    4944  438.73  4949.1  437.11  4958.7  440.62  4974.1  441.05  4996.2  433.34
  4998.9  432.84  5002.2  433.34  5007.3  436.68  5029.5  441.59  5073.6  439.69
  5090.2  441.49  5130.7  439.41  5240.3  440.65  5494.1  443.94  5845.3  460.51
#Mann= 9 ,-1 , 0
    3450     .05       0  4360.1     .12       0  4467.3     .16       0
  4874.7     .12       0  4974.1     .05       0  4996.2     .04       0
  5002.2     .05       0  5073.6     .16       0  5240.3     .05       0
Bank Sta=4996.2,5002.2
XS Rating Curve= 0 ,0
Exp/Cntr=0.3,0.1

Type RM Length L Ch R = 1 ,29333   ,103,103,103
BEGIN DESCRIPTION:
PATTON CREEK 36.0
END DESCRIPTION:
XS GIS Cut Line= 5
      3534698.55     10582088.18      3532897.33     10582049.12
      3532741.08     10582059.97      3532646.03     10581984.45
      3531791.87      10581953.2
#Sta/Elev= 30
    2962  467.68  2988.4  466.38  3027.8  458.91  3033.3  460.07  3038.5  457.85
  3078.5  455.74  3098.5  457.65  3138.5  449.89  3188.5  448.25  3338.5  449.92
  3378.5  448.26  3608.6  457.64  4058.7  452.79  4258.7  456.93  4628.8  457.21
  4708.2  455.24  4763.6  452.82    4829  440.56  4906.7  439.83  4975.1  440.39
    5001  433.63  5003.7  433.13    5007  433.63  5018.4  440.18  5155.5  439.88
  5230.5  440.24  5455.9  442.67    5716  456.69  5826.1  460.96  5896.4  461.15
#Mann= 8 ,-1 , 0
    2962     .16       0  3027.8     .05       0  4708.2     .12       0
  4906.7     .05       0    5001     .04       0    5007     .05       0
  5155.5     .16       0  5230.5     .05       0
Bank Sta=5001,5007
XS Rating Curve= 0 ,0
Exp/Cntr=0.3,0.1

Type RM Length L Ch R = 1 ,29230   ,166,166,166
BEGIN DESCRIPTION:
PATTON CREEK 36.1
END DESCRIPTION:
XS GIS Cut Line= 4
      3534741.42     10581993.24      3532934.23     10581949.29
      3532582.66     10581914.57      3531790.54     10581903.72
#Sta/Elev= 30
  2999.7  465.27  3119.1  462.97  3203.4  455.82  3267.6  450.34  3409.1   447.6
  3489.2  448.31  3598.8  454.08  3809.3  457.05  4099.3  451.08  4319.4  455.16
  4699.5  456.95  4779.5  454.25  4829.5  450.36  4834.5  451.86  4920.1  445.69
  4935.7  442.26  4940.7  443.28  4980.4  439.53  4997.5  433.61  5000.2  433.11
  5003.5  433.61  5020.6  440.33  5030.6  441.18  5060.8  438.82  5131.1  437.96
  5351.3  441.77  5501.3  442.19  5771.3  458.46  5881.3  462.54  5952.9  463.12
#Mann= 5 ,-1 , 0
  2999.7     .05       0  3203.4     .16       0  3598.8     .05       0
  4997.5     .04       0  5003.5     .05       0
Bank Sta=4997.5,5003.5
XS Rating Curve= 0 ,0
Exp/Cntr=0.3,0.1

Type RM Length L Ch R = 1 ,29064   ,51,51,51
BEGIN DESCRIPTION:
PATTON CREEK 35.0
END DESCRIPTION:
XS GIS Cut Line= 5
      3535614.66     10581388.03      3533083.38     10581752.61
      3532812.37     10581752.27      3532605.78     10581800.88
      3531529.42     10581849.49
#Sta/Elev= 30
  2043.8  464.34  2309.9  458.91  2410.4   460.1  2539.2  459.68  2562.7  459.61
  2854.6  457.24  3360.3   444.7  3398.3  444.66  3450.7  443.22  3592.2  451.16
  3853.8  448.75  3935.7   452.5  4127.6  448.37  4541.9   455.9  4898.8  444.85
  4964.9  441.74  4979.5  439.64  4992.8  431.68  4995.5  431.18  4998.8  431.68
    5027  439.45  5057.4  440.85  5357.4  439.21  5619.3  446.85  5657.2  447.91
  5788.8  452.78  5868.9   465.7  5916.9  464.56  6039.1  460.22  6161.9  465.92
#Mann= 14 ,-1 , 0
  2043.8     .05       0  2309.9     .16       0  2410.4     .05       0
  2539.2     .16       0  2562.7     .05       0  3360.3     .16       0
  3398.3     .05       0  4898.8     .12       0  4992.8     .07       0
  4998.8     .12       0  5357.4     .05       0  5619.3     .16       0
  5657.2     .05       0  5916.9     .16       0
Bank Sta=4992.8,4998.8
XS Rating Curve= 0 ,0
Exp/Cntr=0.3,0.1

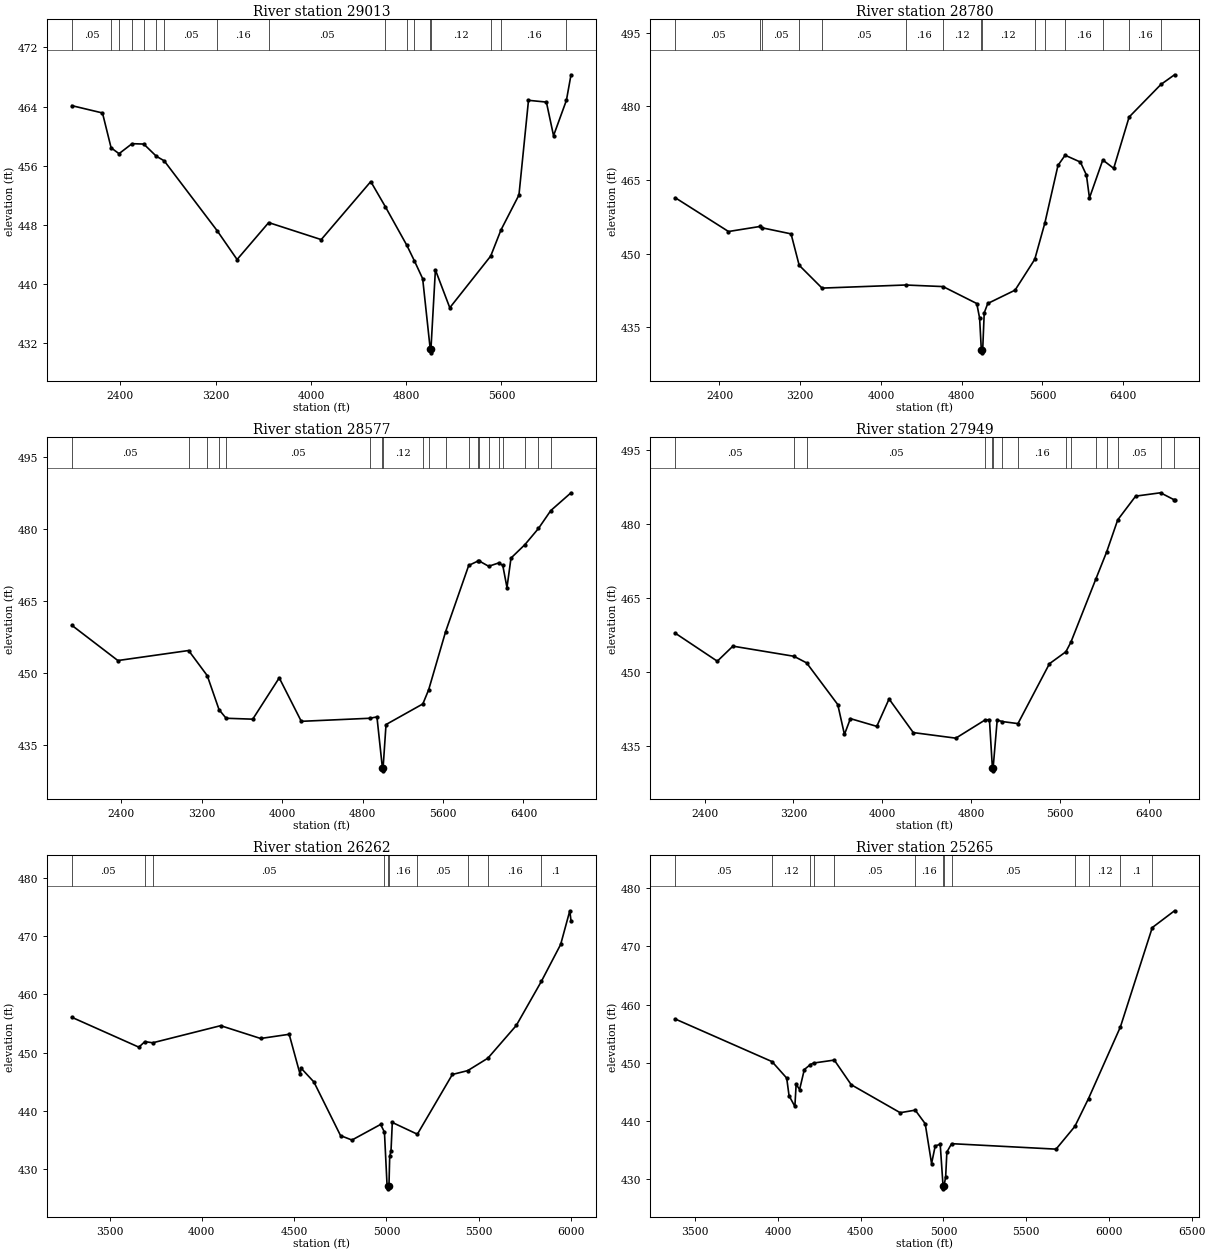
Type RM Length L Ch R = 1 ,29013   ,233,233,233
BEGIN DESCRIPTION:
PATTON CREEK 35.1
END DESCRIPTION:
XS GIS Cut Line= 3
      3535647.25     10581322.76      3532536.16     10581753.31
      3531485.55     10581815.72
#Sta/Elev= 30
  1991.6  464.13  2249.2  463.14  2321.7  458.43  2388.3  457.64  2497.6  458.99
    2596  458.94  2701.7  457.29  2767.3  456.68  3211.6  447.25  3379.8  443.34
  3645.3  448.33  4086.5  446.03  4502.8  453.87    4625  450.48  4805.7  445.26
  4869.5  443.15  4938.7  440.75  5002.2  431.23  5004.9  430.73  5008.2  431.23
  5045.6  441.94  5166.5  436.82  5510.3  443.81  5596.1  447.32  5747.5  452.06
  5827.6  464.85  5977.9  464.61    6038  460.07  6146.1  464.85  6184.8   468.3
#Mann= 17 ,-1 , 0
  1991.6     .05       0  2321.7     .16       0  2388.3     .05       0
  2497.6     .16       0    2596     .05       0  2701.7     .16       0
  2767.3     .05       0  3211.6     .16       0  3645.3     .05       0
    4625     .12       0  4805.7     .05       0  4869.5     .12       0
  5002.2     .07       0  5008.2     .12       0  5510.3     .05       0
  5596.1     .16       0  6146.1     .05       0
Bank Sta=5002.2,5008.2
XS Rating Curve= 0 ,0
Exp/Cntr=0.3,0.1

Type RM Length L Ch R = 1 ,28780   ,203,203,203
BEGIN DESCRIPTION:
PATTON CREEK 26.1
END DESCRIPTION:
XS GIS Cut Line= 4
      3535605.93     10581096.92      3533590.29     10581404.21
      3531637.17     10581659.42      3530699.68     10581633.38
#Sta/Elev= 30
  1962.4  461.41  2489.3  454.54  2802.1  455.57  2825.8  455.28  3109.3  454.06
  3189.7  447.67  3416.2  443.02  4243.3  443.65  4615.6  443.33  4949.4  439.88
  4977.7   436.9  4994.9  430.34  4997.7  429.84  5000.9  430.34    5008  430.36
  5023.3  437.98  5058.4  439.89  5328.9   442.6  5524.1  448.88  5624.4  456.29
  5754.3     468  5824.9  470.07  5976.1  468.68  6036.1  466.04  6066.1  461.37
  6198.3   469.1  6306.2   467.4  6459.1  477.85  6774.2  484.48  6908.9  486.45
#Mann= 15 ,-1 , 0
  1962.4     .05       0  2802.1     .16       0  2825.8     .05       0
  3189.7     .16       0  3416.2     .05       0  4243.3     .16       0
  4615.6     .12       0  4994.9     .07       0  5000.9     .12       0
  5524.1     .16       0  5624.4      .1       0  5824.9     .16       0
  6198.3     .05       0  6459.1     .16       0  6774.2     .05       0
Bank Sta=4994.9,5000.9
XS Rating Curve= 0 ,0
Exp/Cntr=0.3,0.1

Type RM Length L Ch R = 1 ,28577   ,628,628,628
BEGIN DESCRIPTION:
PATTON CREEK 25.1
END DESCRIPTION:
XS GIS Cut Line= 4
       3535616.3     10581003.17      3533517.38       10581274.
      3531559.04     10581419.84      3530675.36     10581435.43
#Sta/Elev= 30
  1909.1  459.91  2367.1  452.56  3070.5  454.65  3255.9  449.41  3373.3  442.31
  3443.6  440.53  3708.1  440.34  3971.6  448.95  4190.9  439.89  4872.3  440.53
  4943.2  440.81    4998  430.07  5000.7  429.57    5004  430.07  5033.5  439.22
  5399.6  443.52  5457.7  446.48  5625.7  458.56  5855.6  472.38  5952.2  473.35
  5955.1  473.37  6054.2  472.21  6153.2   472.9  6194.4  472.39  6236.2  467.78
  6276.2  473.92  6414.8  476.73  6549.2  480.09  6671.6  483.82    6873  487.53
#Mann= 20 ,-1 , 0
  1909.1     .05       0  3070.5     .16       0  3255.9     .05       0
  3373.3     .16       0  3443.6     .05       0  4872.3     .12       0
    4998     .07       0    5004     .12       0  5399.6     .16       0
  5457.7     .12       0  5625.7     .16       0  5855.6     .05       0
  5952.2      .1       0  5955.1     .05       0  6054.2     .16       0
  6153.2     .05       0  6194.4     .16       0  6414.8     .05       0
  6549.2     .16       0  6671.6     .05       0
Bank Sta=4998,5004
XS Rating Curve= 0 ,0
Exp/Cntr=0.3,0.1

Type RM Length L Ch R = 1 ,27949   ,1687,1687,1687
BEGIN DESCRIPTION:
PATTON CREEK 24.0
END DESCRIPTION:
XS GIS Cut Line= 4
      3535548.59     10580930.26      3533616.33     10581122.96
      3532840.29     10580857.34      3531106.53     10580768.83
#Sta/Elev= 30
  2136.2  457.87  2514.6   452.2  2655.2  455.25  3204.7   453.2  3319.3  451.86
  3599.9  443.42  3660.2  437.36  3713.8  440.57  3951.6     439  4062.2  444.55
  4280.4  437.74  4663.8  436.61  4926.1  440.28  4966.6  440.37  4993.6  430.49
  4996.3  429.99  4999.6  430.49  5036.6  440.28  5084.2  439.97  5223.6  439.56
  5507.3  451.69  5655.4  454.11  5700.2  456.03  5924.8  468.81  6023.6  474.38
  6122.5  480.83  6284.1  485.64  6508.2  486.32  6626.7  484.95  6634.3  484.79
#Mann= 15 ,-1 , 0
  2136.2     .05       0  3204.7     .16       0  3319.3     .05       0
  4926.1     .16       0  4993.6     .07       0  4999.6     .16       0
  5084.2      .1       0  5223.6     .16       0  5655.4     .05       0
  5700.2     .16       0  5924.8     .12       0  6023.6     .16       0
  6122.5     .05       0  6508.2      .1       0  6626.7     .05       0
Bank Sta=4993.6,4999.6
XS Rating Curve= 0 ,0
Exp/Cntr=0.3,0.1

Type RM Length L Ch R = 1 ,26262   ,997,997,997
BEGIN DESCRIPTION:
PATTON CREEK 31.0
END DESCRIPTION:
XS GIS Cut Line= 3
      3535564.29     10580779.22        3534033.     10580393.79
      3533226.42     10579608.03
#Sta/Elev= 30
  3295.3  456.06  3658.5  450.93  3691.3  451.88  3733.6  451.68  4101.9  454.62
  4318.4  452.42  4473.1  453.14  4532.4  446.26  4537.5  447.33  4607.2  444.95
  4751.5  435.74  4813.4  434.98  4968.5  437.66  4989.4  436.34  5003.7  427.11
  5007.9   427.1  5010.7   426.6  5013.9   427.1  5017.9  432.18    5025  433.14
    5032     438  5167.8  435.98  5357.4  446.24  5440.7   446.9    5550  449.04
  5703.9  454.66  5839.6  462.22  5944.3  468.57  5993.8  474.35  6000.4  472.61
#Mann= 10 ,-1 , 0
  3295.3     .05       0  3691.3     .16       0  3733.6     .05       0
  4989.4     .16       0  5007.9     .07       0  5013.9     .16       0
  5167.8     .05       0  5440.7     .12       0    5550     .16       0
  5839.6      .1       0
Bank Sta=5007.9,5013.9
XS Rating Curve= 0 ,0
Exp/Cntr=0.3,0.1

Type RM Length L Ch R = 1 ,25265   ,882,882,882
BEGIN DESCRIPTION:
PATTON CREEK 30.0
END DESCRIPTION:
XS GIS Cut Line= 5
      3535741.34     10580711.51      3534746.54     10579867.75
      3534335.08     10579815.67      3533210.08      10579211.5
      3533189.37     10579216.68
#Sta/Elev= 30
  3378.9  457.51  3963.4   450.2  4052.2  447.37  4066.5  444.33  4101.6  442.49
  4109.3   446.3  4130.2   445.4  4158.8  448.84    4196   449.7  4214.4  449.95
  4339.9  450.46  4442.1  446.23  4738.2  441.42  4829.2  441.86  4889.4  439.53
  4927.9  432.68  4949.9  435.71  4980.1     436  4997.3  428.84    5000  428.34
  5003.3  428.84  5013.1  430.43  5020.4  434.66    5049   436.1  5680.4  435.16
  5793.9  439.06  5876.7  443.86  6069.2  456.15  6261.9  473.22  6396.4  476.11
#Mann= 13 ,-1 , 0
  3378.9     .05       0  3963.4     .12       0    4196     .05       0
  4214.4     .16       0  4339.9     .05       0  4829.2     .16       0
  4997.3     .07       0  5003.3     .16       0    5049     .05       0
  5793.9     .16       0  5876.7     .12       0  6069.2      .1       0
  6261.9     .05       0
Bank Sta=4997.3,5003.3
XS Rating Curve= 0 ,0
Exp/Cntr=0.3,0.1

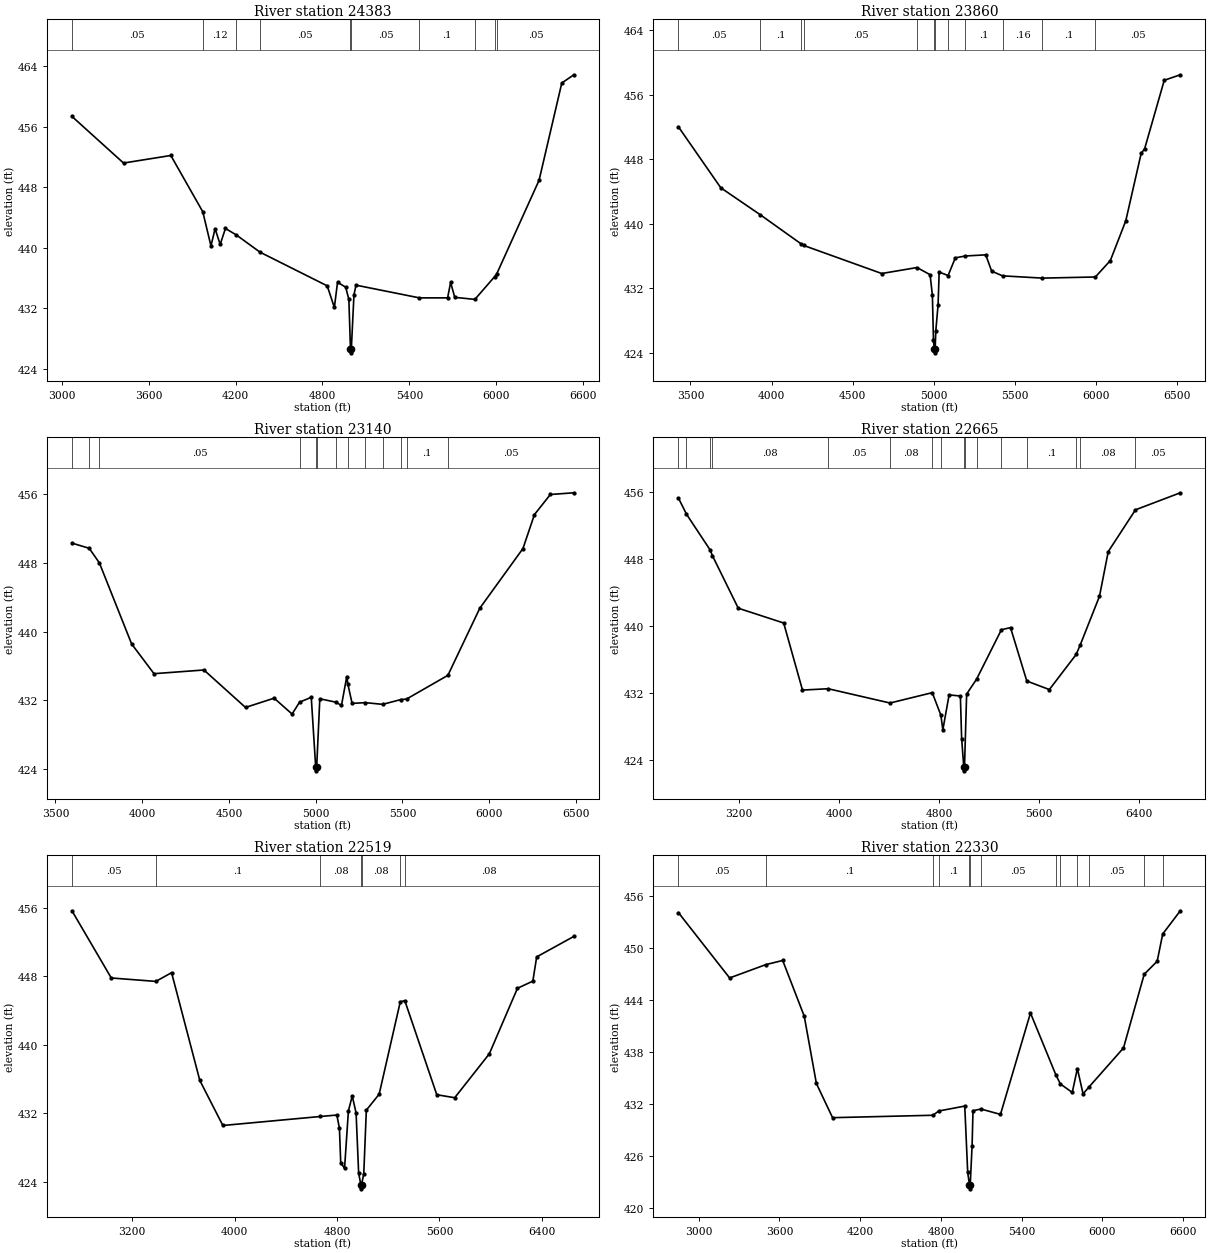
Type RM Length L Ch R = 1 ,24383   ,523,523,523
BEGIN DESCRIPTION:
PATTON CREEK 20.0
END DESCRIPTION:
XS GIS Cut Line= 2
      3535999.59     10580515.76      3533359.24     10578276.41
#Sta/Elev= 30
  3071.8  457.35  3427.6  451.19  3753.8  452.19  3974.1  444.76  4030.6  440.25
  4059.2  442.51  4094.3  440.44  4130.6  442.55  4204.3  441.71  4369.7  439.41
  4832.5  434.97  4881.9  432.11  4903.9  435.44  4959.9  434.79  4981.9  433.18
    4993  426.62  4995.8  426.12    4999  426.62  5017.1  433.79  5031.3  435.06
  5468.8  433.38    5663  433.38  5683.8  435.42  5712.4  433.45  5851.2  433.18
  5987.3  436.18  6003.1   436.6  6294.1  448.92  6450.6  461.76  6533.9  462.85
#Mann= 10 ,-1 , 0
  3071.8     .05       0  3974.1     .12       0  4204.3     .16       0
  4369.7     .05       0    4993     .03       0    4999     .05       0
  5468.8      .1       0  5851.2     .05       0  5987.3      .1       0
  6003.1     .05       0
Bank Sta=4993,4999
XS Rating Curve= 0 ,0
Exp/Cntr=0.3,0.1

Type RM Length L Ch R = 1 ,23860   ,720,720,720
BEGIN DESCRIPTION:
PATTON CREEK 28.0
END DESCRIPTION:
XS GIS Cut Line= 3
      3536000.86     10579921.12      3534711.82      10578792.3
      3533548.66     10578050.14
#Sta/Elev= 30
  3426.2  452.01  3687.4  444.46  3930.2  441.13  4184.3  437.49  4198.6  437.32
  4679.2  433.85  4896.8  434.59  4977.2   433.7  4991.4  431.17  4998.1  425.58
  5002.6  424.53  5005.4  424.03  5008.6  424.53  5012.3  426.72  5026.5  429.98
  5033.2  434.03  5088.2   433.6  5132.8  435.79  5194.8  436.02  5320.3  436.16
  5356.7  434.14  5423.7  433.56  5669.9  433.28  5995.9  433.42  6088.3  435.46
  6183.2  440.37  6278.1  448.72  6299.3  449.28  6420.4  457.77  6519.4  458.45
#Mann= 12 ,-1 , 0
  3426.2     .05       0  3930.2      .1       0  4184.3     .08       0
  4198.6     .05       0  4896.8     .16       0  5002.6     .07       0
  5008.6     .16       0  5088.2     .05       0  5194.8      .1       0
  5423.7     .16       0  5669.9      .1       0  5995.9     .05       0
Bank Sta=5002.6,5008.6
XS Rating Curve= 0 ,0
Exp/Cntr=0.3,0.1

Type RM Length L Ch R = 1 ,23140   ,475,475,475
BEGIN DESCRIPTION:
PATTON CREEK 27.0
END DESCRIPTION:
XS GIS Cut Line= 4
      3536171.14     10579099.91      3535122.57      10578391.6
       3534955.9     10578200.62      3533609.37     10577928.59
#Sta/Elev= 30
  3595.2  450.32  3694.6  449.72  3753.2  448.02  3939.2  438.58  4068.1  435.12
  4355.8  435.55  4595.5  431.19  4760.4  432.27  4863.9  430.42  4906.8   431.8
  4974.4  432.37  4999.8  424.31  5002.6  423.81  5005.8  424.31  5023.7   432.2
  5116.8   431.8  5148.5  431.42  5179.1  434.79  5185.5  433.89  5209.8  431.66
  5285.6  431.75  5385.7  431.55  5489.6   432.1  5523.9  432.17  5761.9  434.93
  5945.8  442.74  6194.4  449.69  6260.6  453.64  6352.4  455.98  6487.8  456.18
#Mann= 13 ,-1 , 0
  3595.2     .05       0  3694.6     .08       0  3753.2     .05       0
  4906.8     .16       0  4999.8     .07       0  5005.8     .16       0
  5116.8     .05       0  5185.5     .16       0  5285.6      .1       0
  5385.7     .05       0  5489.6     .16       0  5523.9      .1       0
  5761.9     .05       0
Bank Sta=4999.8,5005.8
XS Rating Curve= 0 ,0
Exp/Cntr=0.3,0.1

Type RM Length L Ch R = 1 ,22665   ,146,146,146
BEGIN DESCRIPTION:
PATTON CREEK 19.1
END DESCRIPTION:
XS GIS Cut Line= 2
       3537572.1     10578047.88      3533567.01      10577870.8
#Sta/Elev= 30
  2717.9  455.33  2782.3   453.4  2971.9   449.1  2989.2  448.44    3196  442.14
  3558.7  440.37  3708.9  432.34  3914.1   432.5  4408.2  430.79  4745.5  432.03
  4814.5  429.32    4830  427.58    4880  431.76  4970.1  431.63  4980.1  426.54
  4997.1  423.17  4999.9  422.67  5003.1  423.17  5020.1  431.86    5100  433.66
  5297.7  439.56  5370.5  439.82  5500.8  433.42  5680.8   432.4  5895.2  436.61
  5926.8  437.72  6081.2  443.57  6151.2  448.92  6368.7  453.92  6726.9  455.96
#Mann= 16 ,-1 , 0
  2717.9     .05       0  2782.3     .08       0  2971.9     .05       0
  2989.2     .08       0  3914.1     .05       0  4408.2     .08       0
  4745.5     .05       0  4814.5     .16       0  4997.1     .07       0
  5003.1     .16       0    5100     .05       0  5297.7     .16       0
  5500.8      .1       0  5895.2     .05       0  5926.8     .08       0
  6368.7     .05       0
Bank Sta=4997.1,5003.1
XS Rating Curve= 0 ,0
Exp/Cntr=0.3,0.1

Type RM Length L Ch R = 1 ,22519   ,189,189,189
BEGIN DESCRIPTION:
PATTON CREEK 26.0
END DESCRIPTION:
XS GIS Cut Line= 4
      3537628.49     10577924.25      3536719.63     10577863.48
      3535052.97      10577808.8      3533711.83     10577780.15
#Sta/Elev= 30
  2729.8  455.62  3036.9  447.78  3384.7  447.38  3507.9   448.4  3728.3  435.83
  3908.4  430.57  4669.6  431.62  4798.8  431.79  4818.9  430.24  4828.9  426.23
  4858.9  425.57  4888.9  432.27  4918.9  434.01  4948.9  432.04  4968.9  425.01
  4985.9  423.68  4988.7  423.18  4991.9  423.68    5009  424.95    5029  432.36
    5129  434.22  5294.2  445.01  5329.6  445.13  5579.2  434.16  5719.2  433.81
  5989.3  438.93  6209.3  446.58  6329.3  447.41  6359.4  450.24  6649.7  452.63
#Mann= 7 ,-1 , 0
  2729.8     .05       0  3384.7      .1       0  4669.6     .08       0
  4985.9     .07       0  4991.9     .08       0  5294.2     .05       0
  5329.6     .08       0
Bank Sta=4985.9,4991.9
XS Rating Curve= 0 ,0
Exp/Cntr=0.3,0.1

Type RM Length L Ch R = 1 ,22330   ,439,439,439
BEGIN DESCRIPTION:
PATTON CREEK 17.0
END DESCRIPTION:
XS GIS Cut Line= 4
      3537625.84     10577858.27      3535636.73     10577745.43
      3535085.52     10577506.71      3533950.53     10577576.16
#Sta/Elev= 30
  2849.4  454.13    3230  446.58  3498.9  448.12  3624.4   448.6  3784.6  442.16
  3874.8  434.39    3995  430.44  4740.8  430.72  4783.9  431.21  4977.5  431.78
  4999.3  424.12  5012.2  422.72    5015  422.22  5018.2  422.72    5032  427.22
  5038.7  431.24    5097  431.44  5242.9  430.82  5465.8  442.53  5653.9  435.41
  5687.9  434.34  5776.4  433.35  5814.5  436.12  5856.6  433.19  5898.3  433.94
  6157.1  438.49  6311.2  447.01  6407.6  448.51  6448.6  451.66  6579.5  454.34
#Mann= 13 ,-1 , 0
  2849.4     .05       0  3498.9      .1       0  4740.8     .05       0
  4783.9      .1       0  5012.2     .07       0  5018.2      .1       0
    5097     .05       0  5653.9      .1       0  5687.9     .05       0
  5814.5      .1       0  5898.3     .05       0  6311.2     .08       0
  6448.6     .05       0
Bank Sta=5012.2,5018.2
XS Rating Curve= 0 ,0
Exp/Cntr=0.3,0.1

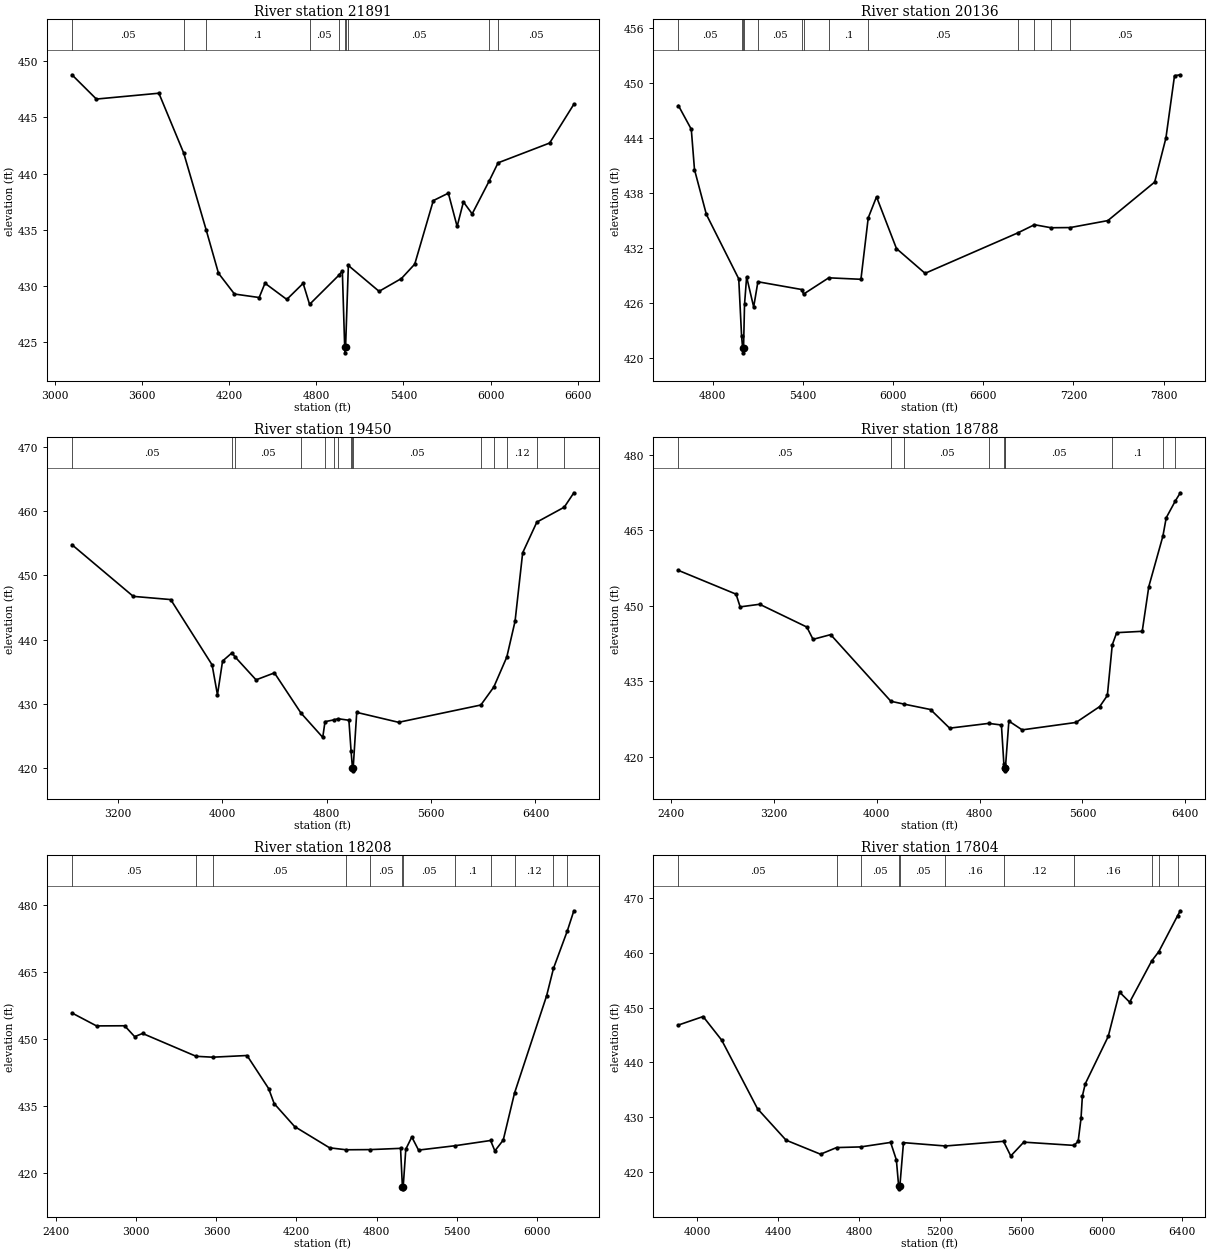
Type RM Length L Ch R = 1 ,21891   ,1755,1755,1755
BEGIN DESCRIPTION:
PATTON CREEK 23.0
END DESCRIPTION:
XS GIS Cut Line= 4
       3537520.1     10577516.34      3536006.25      10577423.9
      3535188.54     10577127.02      3534162.48     10577439.53
#Sta/Elev= 30
    3115  448.79  3283.3  446.63  3714.1  447.15  3885.5  441.82  4040.8  434.96
  4124.9  431.14  4235.1  429.29  4405.4  428.98  4445.5  430.25  4595.7  428.81
  4708.4  430.24  4752.7  428.37  4954.5  430.96  4978.5  431.35  4994.8  424.56
  4997.5  424.06  5000.8  424.56  5020.1  431.83  5231.8  429.53  5385.8  430.67
  5477.6  431.95  5605.5   437.6  5709.2  438.26  5769.7   435.3    5813  437.48
  5873.4  436.42  5989.7  439.32    6052  440.96  6407.3  442.72  6574.2  446.17
#Mann= 10 ,-1 , 0
    3115     .05       0  3885.5     .16       0  4040.8      .1       0
  4752.7     .05       0  4954.5     .16       0  4994.8     .07       0
  5000.8     .16       0  5020.1     .05       0  5989.7      .1       0
    6052     .05       0
Bank Sta=4994.8,5000.8
XS Rating Curve= 0 ,0
Exp/Cntr=0.3,0.1

Type RM Length L Ch R = 1 ,20136   ,686,686,686
BEGIN DESCRIPTION:
PATTON CREEK 21.0
END DESCRIPTION:
XS GIS Cut Line= 4
      3536712.41     10576210.76      3536392.95      10576092.7
      3535497.12     10576481.59      3533656.97     10577314.86
#Sta/Elev= 30
  4573.1  447.52  4658.7  444.94    4680  440.54    4759  435.65  4974.2  428.63
  4993.2  422.36  5000.1  421.06  5002.8  420.56  5006.1  421.06  5012.7  425.84
  5026.6  428.84  5073.5  425.56  5101.6  428.31  5394.5  427.46  5404.8  426.96
  5572.7  428.74  5786.7  428.58  5835.2  435.28  5890.3  437.57  6022.9  431.93
  6213.2  429.23  6829.8  433.64  6940.3  434.53  7050.9   434.2  7178.2  434.22
  7428.5  434.98  7739.7  439.18  7814.5  443.98  7871.7  450.78  7910.3  450.88
#Mann= 13 ,-1 , 0
  4573.1     .05       0  4993.2     .16       0  5000.1     .07       0
  5006.1     .16       0  5101.6     .05       0  5394.5      .1       0
  5404.8     .05       0  5572.7      .1       0  5835.2     .05       0
  6829.8     .12       0  6940.3     .05       0  7050.9     .12       0
  7178.2     .05       0
Bank Sta=5000.1,5006.1
XS Rating Curve= 0 ,0
Exp/Cntr=0.3,0.1

Type RM Length L Ch R = 1 ,19450   ,662,662,662
BEGIN DESCRIPTION:
PATTON CREEK 15.0
END DESCRIPTION:
XS GIS Cut Line= 4
      3538105.66     10576191.76       3536529.3     10575601.49
      3535831.38     10575632.74      3534373.02     10575733.44
#Sta/Elev= 30
  2850.3  454.81  3319.9  446.74  3606.6  446.24  3923.6  436.04  3964.6  431.37
  4003.8  436.64  4076.3  437.93  4097.2  437.34  4260.2   433.7  4400.9  434.79
  4604.5  428.51    4771  424.72  4788.3  427.17    4856  427.45  4888.8  427.63
  4971.2  427.39    4988  422.56  4998.2  419.99    5001  419.49  5004.2  419.99
  5031.2  428.62  5351.7  427.07  5981.6  429.77    6081  432.58  6180.4  437.26
  6243.8  442.86    6302  453.55  6410.6  458.34  6620.5  460.67    6694  462.92
#Mann= 15 ,-1 , 0
  2850.3     .05       0  4076.3     .16       0  4097.2     .05       0
  4604.5     .16       0  4788.3     .05       0    4856      .1       0
  4888.8     .16       0    4988     .05       0  4998.2     .03       0
  5004.2     .05       0  5981.6     .12       0    6081      .1       0
  6180.4     .12       0  6410.6     .05       0  6620.5      .1       0
Bank Sta=4998.2,5004.2
XS Rating Curve= 0 ,0
Exp/Cntr=0.3,0.1

Type RM Length L Ch R = 1 ,18788   ,580,580,580
BEGIN DESCRIPTION:
PATTON CREEK 14.1
END DESCRIPTION:
XS GIS Cut Line= 4
      3538407.76     10576007.74      3536209.85     10575122.33
      3535574.44     10574799.41      3534786.71     10574573.85
#Sta/Elev= 30
  2458.8  457.03  2906.9   452.3  2938.7  449.77  3090.2  450.29    3457  445.76
  3505.4  443.31  3642.3  444.25  4110.5  430.99  4215.5  430.41  4418.5  429.35
  4567.2  425.64  4870.6  426.59  4969.7  426.27  4988.9  418.47  4994.5  417.65
  4997.3  417.15  5000.5  417.65  5027.7  427.05  5131.1   425.3    5550  426.78
  5734.4  429.95  5793.2  432.14  5831.5  442.23    5866  444.64  6064.3  444.91
  6115.6  453.82    6225  463.84  6250.9   467.5  6322.9   470.9  6360.5  472.47
#Mann= 10 ,-1 , 0
  2458.8     .05       0  4110.5      .1       0  4215.5     .05       0
  4870.6     .16       0  4988.9     .05       0  4994.5     .03       0
  5000.5     .05       0  5831.5      .1       0    6225     .12       0
  6322.9     .16       0
Bank Sta=4994.5,5000.5
XS Rating Curve= 0 ,0
Exp/Cntr=0.3,0.1

Type RM Length L Ch R = 1 ,18208   ,404,404,404
BEGIN DESCRIPTION:
PATTON CREEK 14.0
END DESCRIPTION:
XS GIS Cut Line= 5
      3538383.51      10575879.3      3537060.55     10575132.74
      3536435.55      10574625.8      3536004.99     10574413.99
      3535098.78     10574104.98
#Sta/Elev= 30
  2517.6  455.75  2701.7  452.85  2912.5  452.88  2987.6  450.44  3046.8  451.16
  3448.1  446.04  3572.2  445.84  3829.6  446.22  3991.4  438.82  4032.9  435.45
    4186  430.31  4448.2  425.54  4572.8   425.1  4753.6  425.14    4980  425.42
  4993.9  416.85  4996.6  416.35  4999.9  416.85  5019.4  425.23  5064.3  427.97
  5114.8  425.03  5386.6     426  5654.8  427.18  5686.8  424.85  5749.5  427.27
  5834.1   437.8  6074.4  459.58  6126.1  465.74  6229.2  474.09  6278.7  478.64
#Mann= 12 ,-1 , 0
  2517.6     .05       0  3448.1     .12       0  3572.2     .05       0
  4572.8      .1       0  4753.6     .05       0  4993.9     .03       0
  4999.9     .05       0  5386.6      .1       0  5654.8     .16       0
  5834.1     .12       0  6126.1     .16       0  6229.2      .1       0
Bank Sta=4993.9,4999.9
XS Rating Curve= 0 ,0
Exp/Cntr=0.3,0.1

Type RM Length L Ch R = 1 ,17804   ,526,526,526
BEGIN DESCRIPTION:
PATTON CREEK 19.0
END DESCRIPTION:
XS GIS Cut Line= 2
      3537405.73     10575120.36      3535556.96     10573462.55
#Sta/Elev= 30
  3906.4  446.83  4028.6  448.38  4120.6  444.07  4297.7  431.56    4439  425.82
  4609.5  423.26  4688.8  424.47    4808  424.59  4956.4  425.41  4984.8  422.21
    4996  417.44  4998.7  416.94    5002  417.44  5019.9  425.37  5227.7  424.76
  5514.8  425.61  5550.7  422.94    5615  425.46    5863  424.87  5884.1  425.59
  5898.3  429.79    5905  433.87  5919.2   436.1  6032.9  444.75  6088.9  452.84
    6139     451  6247.9  458.52  6283.3  460.23  6376.2  466.79  6389.6  467.68
#Mann= 11 ,-1 , 0
  3906.4     .05       0  4688.8      .1       0    4808     .05       0
    4996     .03       0    5002     .05       0  5227.7     .16       0
  5514.8     .12       0    5863     .16       0  6247.9      .1       0
  6283.3     .16       0  6376.2      .1       0
Bank Sta=4996,5002
XS Rating Curve= 0 ,0
Exp/Cntr=0.3,0.1

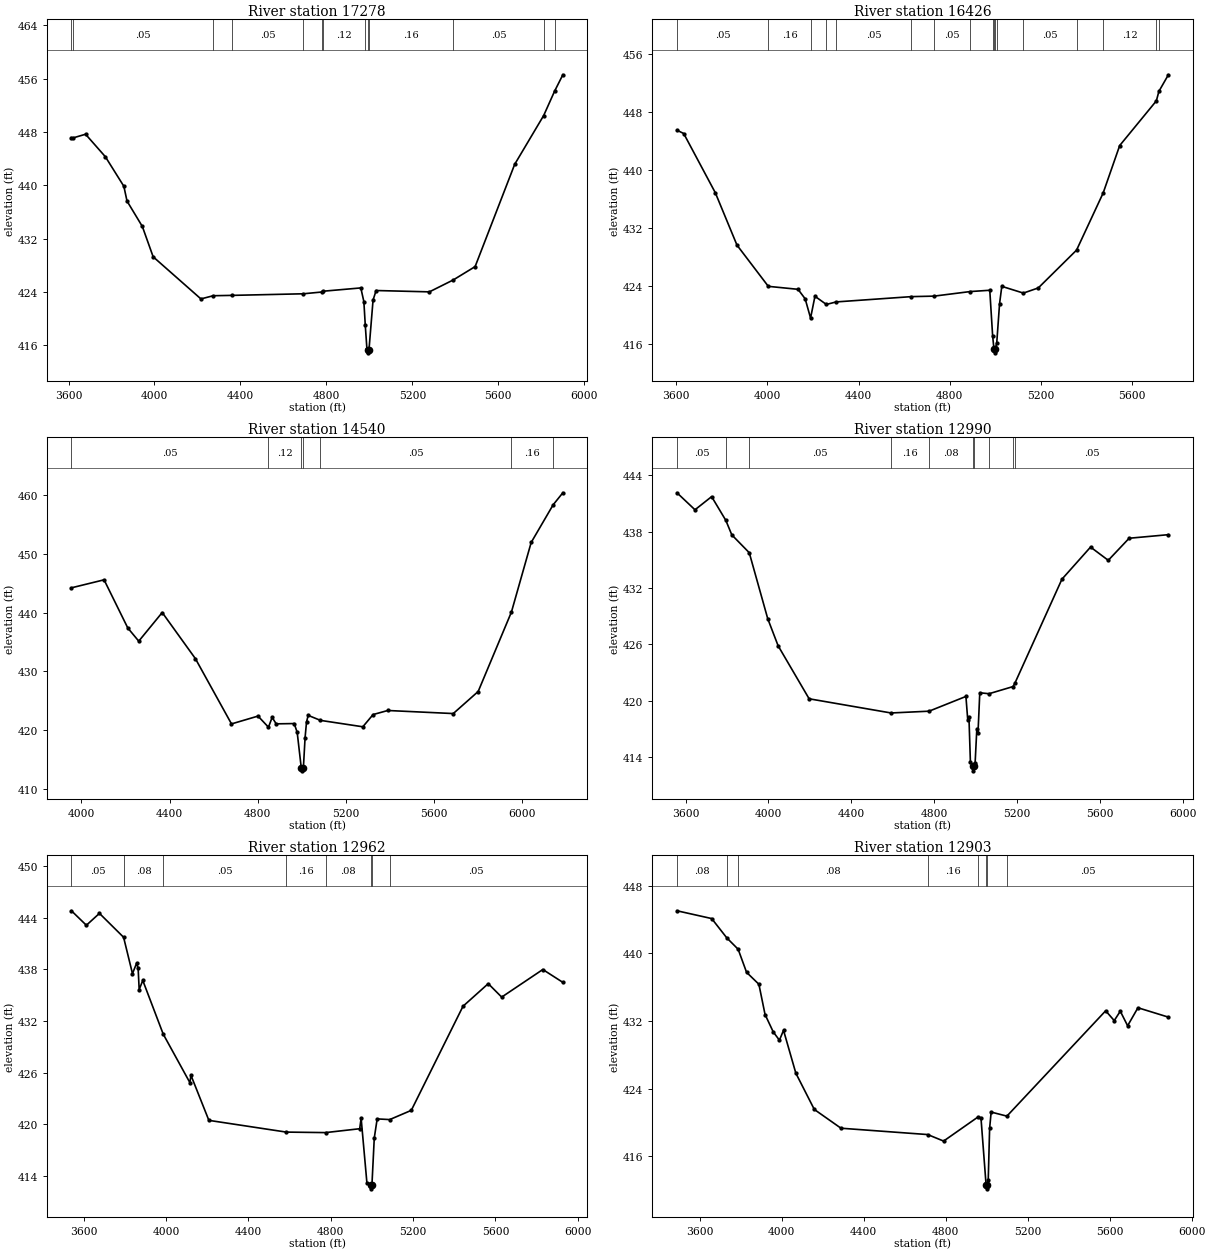
Type RM Length L Ch R = 1 ,17278   ,852,852,852
BEGIN DESCRIPTION:
PATTON CREEK 13.0
END DESCRIPTION:
XS GIS Cut Line= 3
      3537609.17     10575025.13      3536882.11     10574011.67
      3536096.18     10573331.45
#Sta/Elev= 30
  3613.6  447.15  3620.4  447.11  3679.4  447.67  3771.6  444.29  3857.6  439.86
  3872.3  437.64  3943.6  433.83  3993.9  429.28  4216.2  422.96  4273.6  423.44
  4359.7  423.49  4692.4  423.73  4779.8     424    4783  424.11  4960.2  424.61
  4974.4  422.56    4981  418.99  4988.7  415.41  4992.3  415.37    4995  414.87
  4998.3  415.37  5017.2  422.79  5031.4  424.22  5279.3  424.02  5390.6  425.81
  5492.1  427.81  5676.3  443.16  5811.2  450.48  5861.8  454.12  5900.3  456.59
#Mann= 13 ,-1 , 0
  3613.6     .12       0  3620.4     .05       0  4273.6      .1       0
  4359.7     .05       0  4692.4     .16       0  4779.8     .05       0
    4783     .12       0    4981     .16       0  4992.3     .07       0
  4998.3     .16       0  5390.6     .05       0  5811.2     .16       0
  5861.8     .05       0
Bank Sta=4992.3,4998.3
XS Rating Curve= 0 ,0
Exp/Cntr=0.3,0.1

Type RM Length L Ch R = 1 ,16426   ,1886,1886,1886
BEGIN DESCRIPTION:
PATTON CREEK 11.0
END DESCRIPTION:
XS GIS Cut Line= 2
      3537954.48     10574608.23      3536858.53     10572752.72
#Sta/Elev= 30
  3603.5  445.51  3633.1  445.05  3771.6  436.88  3866.7  429.64  4004.1  423.95
  4134.4  423.54  4165.7  422.23  4189.4  419.57  4208.6  422.58  4258.7  421.45
  4301.6   421.8  4631.3  422.53  4731.1   422.6  4889.3  423.23  4975.3  423.41
  4987.8  417.12  4993.7  415.27  4996.5  414.77  4999.7  415.27  5005.9  416.17
  5018.2  421.56    5028  423.95  5122.6  423.02    5188  423.73  5355.8  428.95
  5472.5  436.84    5545  443.39  5705.8  449.56  5716.9  450.87  5758.5  453.16
#Mann= 17 ,-1 , 0
  3603.5     .05       0  4004.1     .16       0  4189.4     .12       0
  4258.7     .16       0  4301.6     .05       0  4631.3      .1       0
  4731.1     .05       0  4889.3      .1       0  4987.8     .05       0
  4993.7     .03       0  4999.7     .05       0  5005.9     .16       0
  5122.6     .05       0  5355.8     .16       0  5472.5     .12       0
  5705.8     .16       0  5716.9     .12       0
Bank Sta=4993.7,4999.7
XS Rating Curve= 0 ,0
Exp/Cntr=0.3,0.1

Type RM Length L Ch R = 1 ,14540   ,1550,1550,1550
BEGIN DESCRIPTION:
PATTON CREEK 10.0
END DESCRIPTION:
XS GIS Cut Line= 5
      3538685.53     10574316.75      3538112.63     10573580.66
      3537824.44      10573250.8      3537242.11     10572691.64
      3537206.72     10572653.94
#Sta/Elev= 30
  3954.9  444.22    4103  445.58  4210.7  437.39  4260.4  435.15  4366.9  440.02
  4517.4  432.18  4681.2  421.08  4801.5  422.41    4849  420.52  4865.7  422.19
    4884  421.09  4965.7  421.14  4979.3  419.65  4997.8   413.6  5000.6   413.1
  5003.8   413.6  5007.5  413.65  5015.1  418.74  5021.7  421.43  5029.3  422.53
  5084.9  421.68  5277.1  420.59  5323.7  422.67  5390.4  423.36  5687.5  422.84
  5800.5  426.59  5951.4   440.1    6041  451.93  6140.8  458.34  6184.7  460.38
#Mann= 7 ,-1 , 0
  3954.9     .05       0    4849     .12       0  4997.8     .07       0
  5003.8     .12       0  5084.9     .05       0  5951.4     .16       0
  6140.8     .05       0
Bank Sta=4997.8,5003.8
XS Rating Curve= 0 ,0
Exp/Cntr=0.3,0.1

Type RM Length L Ch R = 1 ,12990   ,28,28,28
BEGIN DESCRIPTION:
PATTON CREEK 8.0
END DESCRIPTION:
XS GIS Cut Line= 6
      3538795.76     10574188.38      3538896.57       10572932.
      3538872.26     10572859.08      3538783.72     10572756.65
      3538141.36     10572327.83      3538056.71     10572241.46
#Sta/Elev= 30
  3558.6  442.14  3645.6  440.33  3725.9  441.73  3794.5   439.2  3823.3  437.66
  3907.5  435.76  3996.7  428.74  4046.9  425.85  4196.5  420.21    4592   418.7
  4775.4  418.89  4953.3  420.46  4962.1  417.96  4967.8  418.32  4974.9  413.51
  4986.7  413.04  4989.5  412.54  4992.7  413.04  4997.6  413.33    5006  417.03
  5011.7  416.61  5020.2  420.85  5064.9  420.75  5180.7  421.51  5189.9  421.88
  5416.7  432.94  5554.9  436.36  5640.3  434.95  5741.1   437.3  5930.5  437.68
#Mann= 10 ,-1 , 0
  3558.6     .05       0  3794.5     .08       0  3907.5     .05       0
    4592     .16       0  4775.4     .08       0  4986.7     .07       0
  4992.7     .08       0  5064.9     .05       0  5180.7     .16       0
  5189.9     .05       0
Bank Sta=4986.7,4992.7
XS Rating Curve= 0 ,0
Exp/Cntr=0.3,0.1

Type RM Length L Ch R = 1 ,12962   ,59,59,59
BEGIN DESCRIPTION:
PATTON CREEK 7.0
END DESCRIPTION:
XS GIS Cut Line= 6
       3538831.2     10574207.28      3538921.63     10573070.85
      3538897.76     10572856.01       3538800.1     10572754.01
      3538238.03      10572369.9       3538086.6     10572229.41
#Sta/Elev= 30
  3540.3  444.78  3612.9   443.1  3676.4  444.48  3793.7  441.71  3836.9  437.49
  3856.9   438.7  3864.4  438.11  3869.4  435.65    3887   436.7  3986.2  430.48
  4115.9  424.85  4120.9  425.71    4208  420.48  4583.9  419.12  4774.6  419.06
  4940.7  419.51  4947.7  420.72    4976  413.17  4994.3  413.04  4997.1  412.54
  5000.3  413.04  5011.5  418.43  5025.6  420.65  5086.5  420.57  5191.4  421.64
  5442.6  433.71  5565.2  436.33  5630.5  434.77  5830.3  437.97  5927.6  436.48
#Mann= 8 ,-1 , 0
  3540.3     .05       0  3793.7     .08       0  3986.2     .05       0
  4583.9     .16       0  4774.6     .08       0  4994.3     .07       0
  5000.3     .08       0  5086.5     .05       0
Bank Sta=4994.3,5000.3
XS Rating Curve= 0 ,0
Exp/Cntr=0.3,0.1

Type RM Length L Ch R = 1 ,12903   ,32,32,32
BEGIN DESCRIPTION:
PATTON CREEK 6.0
END DESCRIPTION:
XS GIS Cut Line= 6
      3538924.35     10574200.78      3538995.53     10572884.78
       3538979.9     10572839.64       3538792.4     10572672.97
      3538226.43     10572271.93      3538158.87      10572216.5
#Sta/Elev= 30
  3488.8  445.05  3658.2  444.13  3731.8  441.85  3787.3   440.5  3828.4  437.77
  3888.5  436.36  3918.6  432.78  3958.6  430.72  3988.7  429.74  4008.7  430.91
  4068.8  425.84  4158.9  421.55  4289.1  419.33    4712  418.58  4789.8  417.81
  4956.5  420.64    4972  420.57  4996.9  412.66  4999.7  412.16  5002.9  412.66
  5007.5  413.22  5014.2   419.3  5021.7  421.24  5098.6  420.76  5580.4  433.22
  5622.2  432.06  5651.8  433.17  5687.5  431.45  5737.9  433.58  5886.4  432.47
#Mann= 8 ,-1 , 0
  3488.8     .08       0  3731.8     .05       0  3787.3     .08       0
    4712     .16       0  4956.5     .08       0  4996.9     .07       0
  5002.9     .08       0  5098.6     .05       0
Bank Sta=4996.9,5002.9
XS Rating Curve= 0 ,0
Exp/Cntr=0.3,0.1