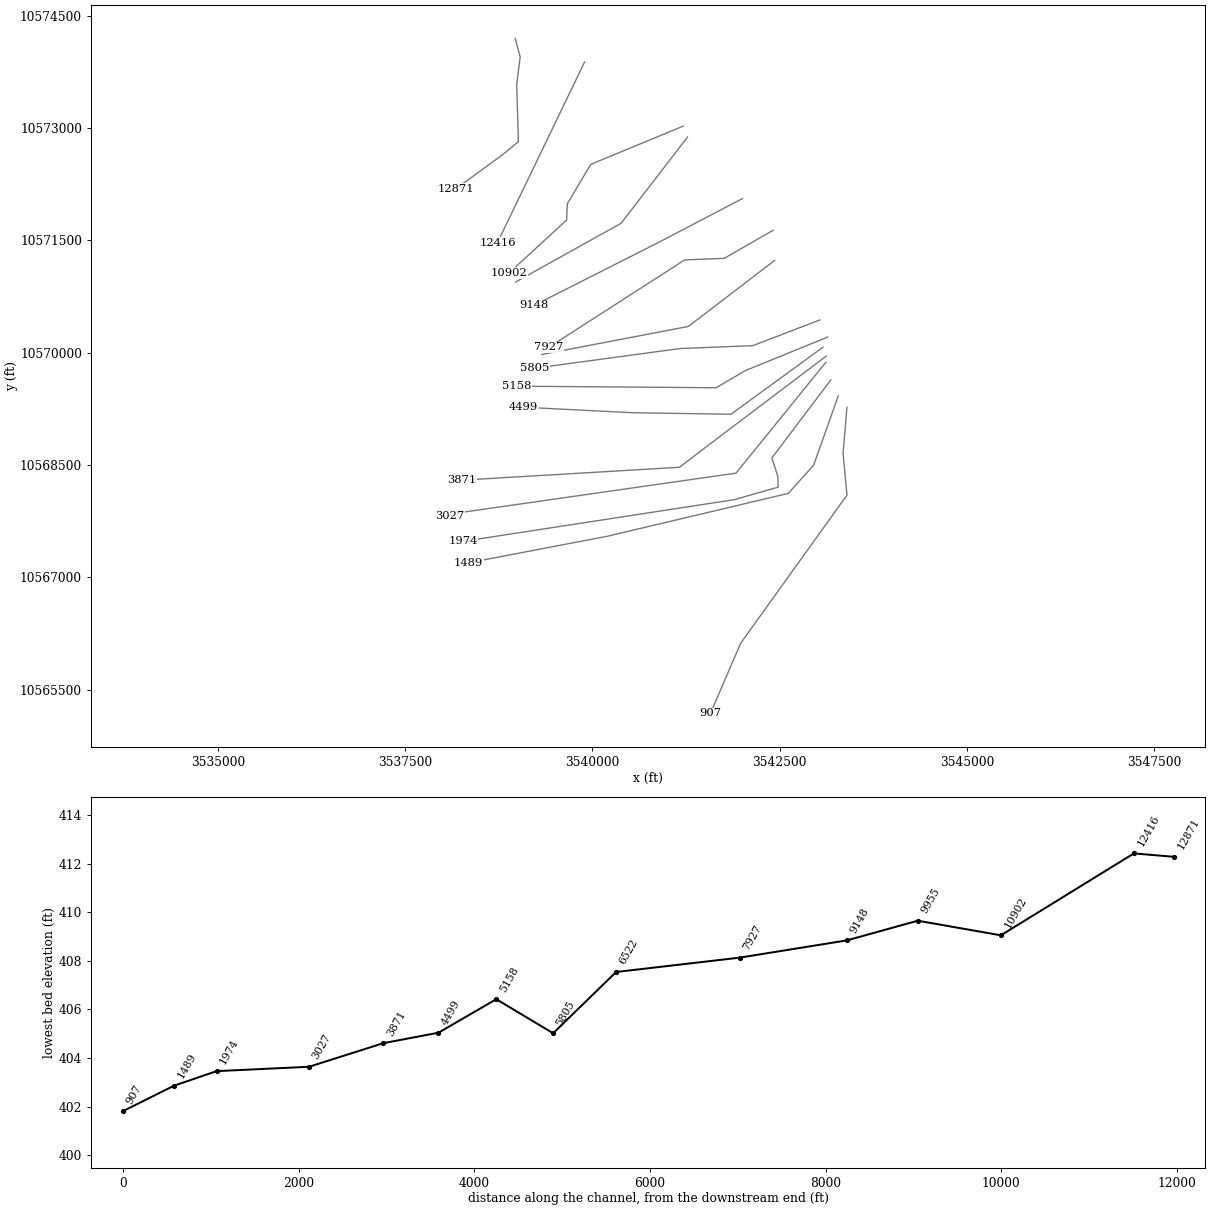
HEC-RAS study PATTON CREEK.prj: PATTON CREEK Base Level Engineering

--- PATTON CREEK.g01 (geometry) --- (continued)

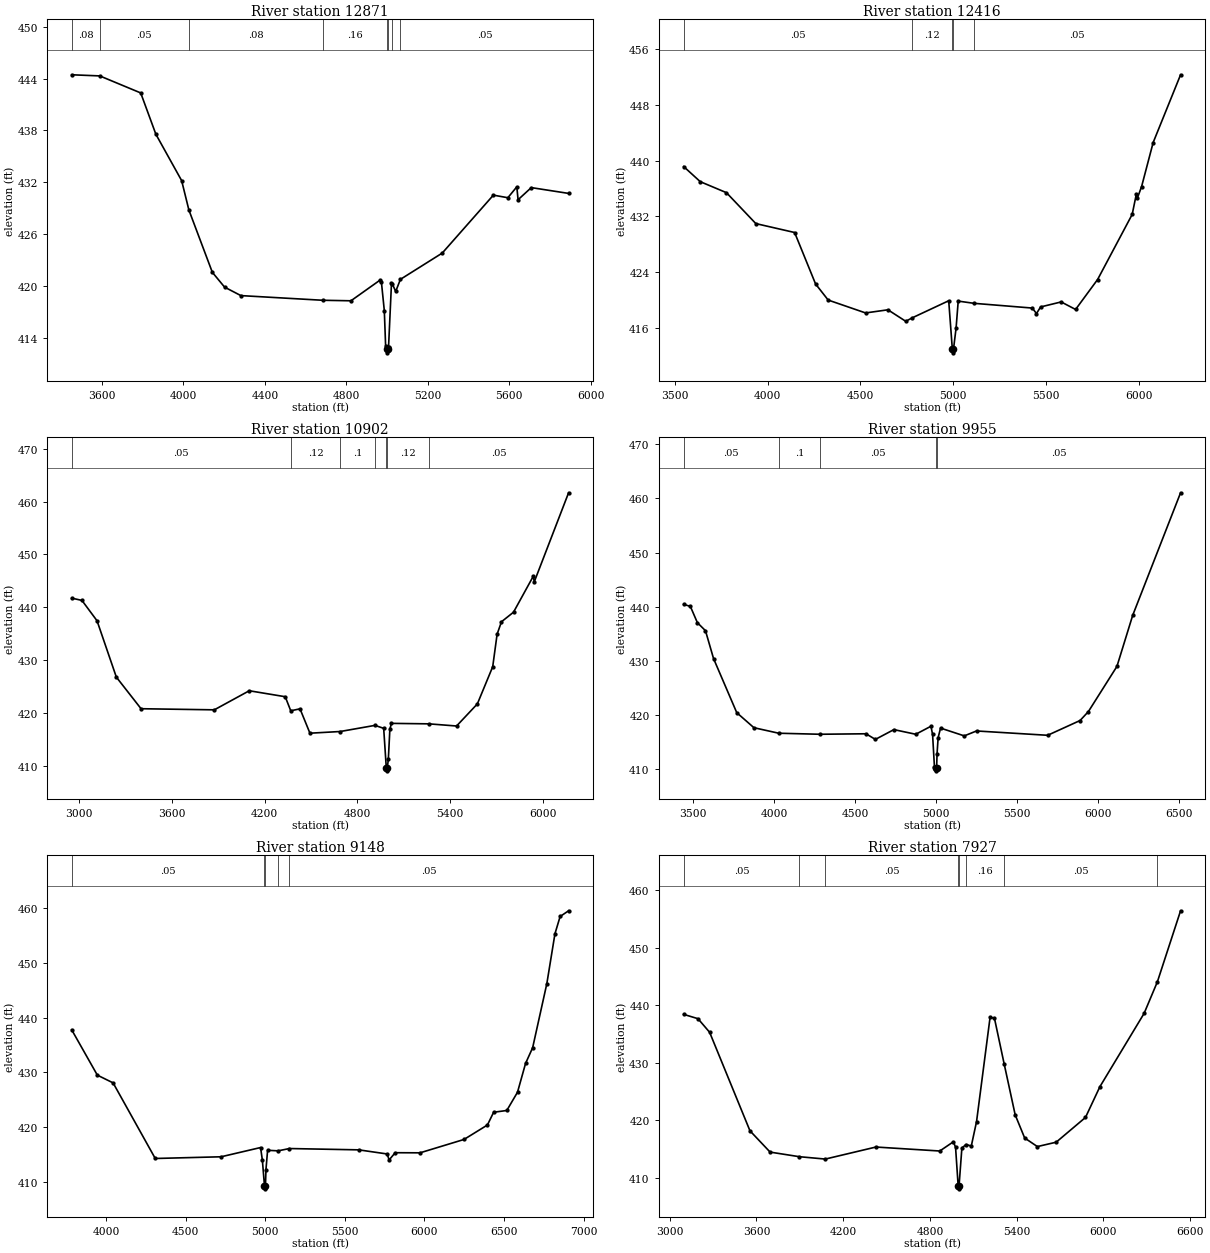
Type RM Length L Ch R = 1 ,12871   ,455,455,455
BEGIN DESCRIPTION:
PATTON CREEK 6.2
END DESCRIPTION:
XS GIS Cut Line= 6
      3538969.02     10574200.29      3539036.73     10573950.29
      3538989.86      10573585.7      3539013.29     10572820.08
      3538804.96      10572648.2      3538177.36     10572189.88
#Sta/Elev= 30
  3451.2  444.44  3588.9  444.31  3790.1  442.34  3864.6  437.56  3991.1   432.2
  4026.7   428.8  4141.9  421.59    4202  419.88    4282   418.9  4683.7  418.36
  4822.6   418.3  4964.2  420.67  4972.1  420.48  4986.4  417.17  4992.9  413.05
  4997.8  412.78  5000.5  412.28  5003.8  412.78  5007.2  412.93  5021.6  420.31
  5025.9  420.24  5042.4  419.38  5065.5  420.78    5271  423.82    5522  430.52
  5593.1  430.22  5637.1  431.48  5643.3  429.99  5708.2  431.39  5891.4  430.72
#Mann= 8 ,-1 , 0
  3451.2     .08       0  3588.9     .05       0  4026.7     .08       0
  4683.7     .16       0  4997.8     .07       0  5003.8     .16       0
  5025.9     .08       0  5065.5     .05       0
Bank Sta=4997.8,5003.8
XS Rating Curve= 0 ,0
Exp/Cntr=0.3,0.1

Type RM Length L Ch R = 1 ,12416   ,1514,1514,1514
BEGIN DESCRIPTION:
PATTON CREEK 5.1
END DESCRIPTION:
XS GIS Cut Line= 2
      3539896.98     10573884.98      3538733.79     10571471.79
#Sta/Elev= 30
  3546.9  439.17  3636.3     437  3777.5  435.42  3935.9  430.98    4145   429.7
    4258  422.31  4325.9     420  4527.5  418.15  4648.1   418.6  4744.1  416.95
  4780.1  417.46  4975.8   419.9  4995.4  412.92  4998.2  412.42  5001.4  412.92
  5015.5  415.97    5027  419.85  5112.4  419.53  5426.7  418.85  5448.9  418.06
  5471.1  419.01  5582.1  419.73  5659.8  418.65  5778.5  422.95    5965   432.3
  5987.6  435.25  5993.1  434.66  6015.7   436.3    6078  442.62  6225.8  452.35
#Mann= 5 ,-1 , 0
  3546.9     .05       0  4780.1     .12       0  4995.4     .07       0
  5001.4     .12       0  5112.4     .05       0
Bank Sta=4995.4,5001.4
XS Rating Curve= 0 ,0
Exp/Cntr=0.3,0.1

Type RM Length L Ch R = 1 ,10902   ,947,947,947
BEGIN DESCRIPTION:
PATTON CREEK 5.0
END DESCRIPTION:
XS GIS Cut Line= 5
      3541213.28     10573027.16      3539978.89     10572516.74
      3539666.39      10571990.7      3539655.97     10571771.95
      3538886.16     10571064.55
#Sta/Elev= 30
  2953.4  441.72  3019.6  441.29  3117.1  437.44    3242  426.78  3401.7   420.8
  3875.3  420.59  4101.3   424.2  4333.8  423.07  4369.4  420.41  4429.3  420.78
  4493.5  416.17  4689.3  416.49  4913.8  417.65  4970.2  417.09  4987.2  409.55
  4989.9  409.05  4993.2  409.55  5000.2  411.21  5010.2  416.93  5020.2  418.03
  5262.1  417.94  5441.3  417.53  5575.7  421.71    5675  428.75  5703.4   434.9
  5731.7  437.25  5809.4  439.06    5937  445.85  5943.8  444.82  6165.5  461.65
#Mann= 7 ,-1 , 0
  2953.4     .05       0  4369.4     .12       0  4689.3      .1       0
  4913.8     .12       0  4987.2     .07       0  4993.2     .12       0
  5262.1     .05       0
Bank Sta=4987.2,4993.2
XS Rating Curve= 0 ,0
Exp/Cntr=0.3,0.1

Type RM Length L Ch R = 1 ,9955    ,807,807,807
BEGIN DESCRIPTION:
PATTON CREEK 8.01
END DESCRIPTION:
XS GIS Cut Line= 3
      3541270.54     10572881.31      3540385.14     10571730.28
      3538975.38     10570944.77
#Sta/Elev= 30
  3442.7  440.41  3483.8  440.05  3527.3  437.03  3577.2  435.55    3627   430.4
  3770.2   420.4  3876.2  417.62  4029.6   416.6  4283.6  416.41  4567.5   416.5
  4625.6  415.46  4739.7  417.27  4874.7  416.41  4968.4  417.89  4978.5  416.39
  4990.1  410.31  4997.4  410.15  5000.1  409.65  5003.4  410.15  5006.1  412.79
  5012.8  415.79  5027.8  417.55  5174.1  416.11  5249.6  417.02  5688.5  416.22
  5888.5  418.95  5940.1  420.61    6116  428.95  6213.2  438.38  6508.7  461.04
#Mann= 5 ,-1 , 0
  3442.7     .05       0  4029.6      .1       0  4283.6     .05       0
  4997.4     .03       0  5003.4     .05       0
Bank Sta=4997.4,5003.4
XS Rating Curve= 0 ,0
Exp/Cntr=0.3,0.1

Type RM Length L Ch R = 1 ,9148    ,1221,1221,1221
BEGIN DESCRIPTION:
PATTON CREEK 7.1
END DESCRIPTION:
XS GIS Cut Line= 3
      3542003.66     10572059.29      3540856.93     10571459.45
      3539225.61     10570634.69
#Sta/Elev= 30
  3783.9  437.76    3945  429.52    4044  428.11  4308.9  414.36  4722.7  414.67
  4970.6  416.35  4981.9  414.07  4995.3  409.34  4998.1  408.84  5001.3  409.34
  5004.5  412.34  5014.8  415.85  5080.7  415.75  5152.2  416.17  5587.7  415.93
  5766.4  415.18  5778.2  414.09  5816.5  415.41  5972.5  415.39  6248.8  417.82
    6396  420.45    6435  422.77  6517.7  423.09    6585  426.41  6635.6  431.65
  6680.1   434.5  6769.3  446.16  6820.3  455.23  6852.8  458.37    6906  459.41
#Mann= 5 ,-1 , 0
  3783.9     .05       0  4995.3     .03       0  5001.3     .05       0
  5080.7     .16       0  5152.2     .05       0
Bank Sta=4995.3,5001.3
XS Rating Curve= 0 ,0
Exp/Cntr=0.3,0.1

Type RM Length L Ch R = 1 ,7927    ,1405,1405,1405
BEGIN DESCRIPTION:
PATTON CREEK 6.1
END DESCRIPTION:
XS GIS Cut Line= 4
      3542413.34     10571635.66      3541760.57     10571260.67
      3541232.79     10571239.83      3539420.31     10570073.18
#Sta/Elev= 30
  3096.6  438.43  3195.5  437.68    3276  435.32    3555  418.21  3694.4  414.51
    3897  413.71    4076   413.3  4426.2  415.39  4867.9   414.7  4961.7   416.3
  4976.9  415.36    4995  408.63  4997.7  408.13    5001  408.63  5020.6  415.21
  5048.9  415.83  5085.8  415.57  5122.1  419.81  5215.9  437.96  5246.2  437.72
  5312.7  429.87  5389.3  420.98  5454.9  416.96  5542.7  415.47  5672.8  416.23
  5875.5  420.53  5975.2  425.87  6280.9   438.6  6372.8  444.09  6533.1  456.42
#Mann= 8 ,-1 , 0
  3096.6     .05       0    3897      .1       0    4076     .05       0
    4995     .03       0    5001     .05       0  5048.9     .16       0
  5312.7     .05       0  6372.8     .16       0
Bank Sta=4995,5001
XS Rating Curve= 0 ,0
Exp/Cntr=0.3,0.1

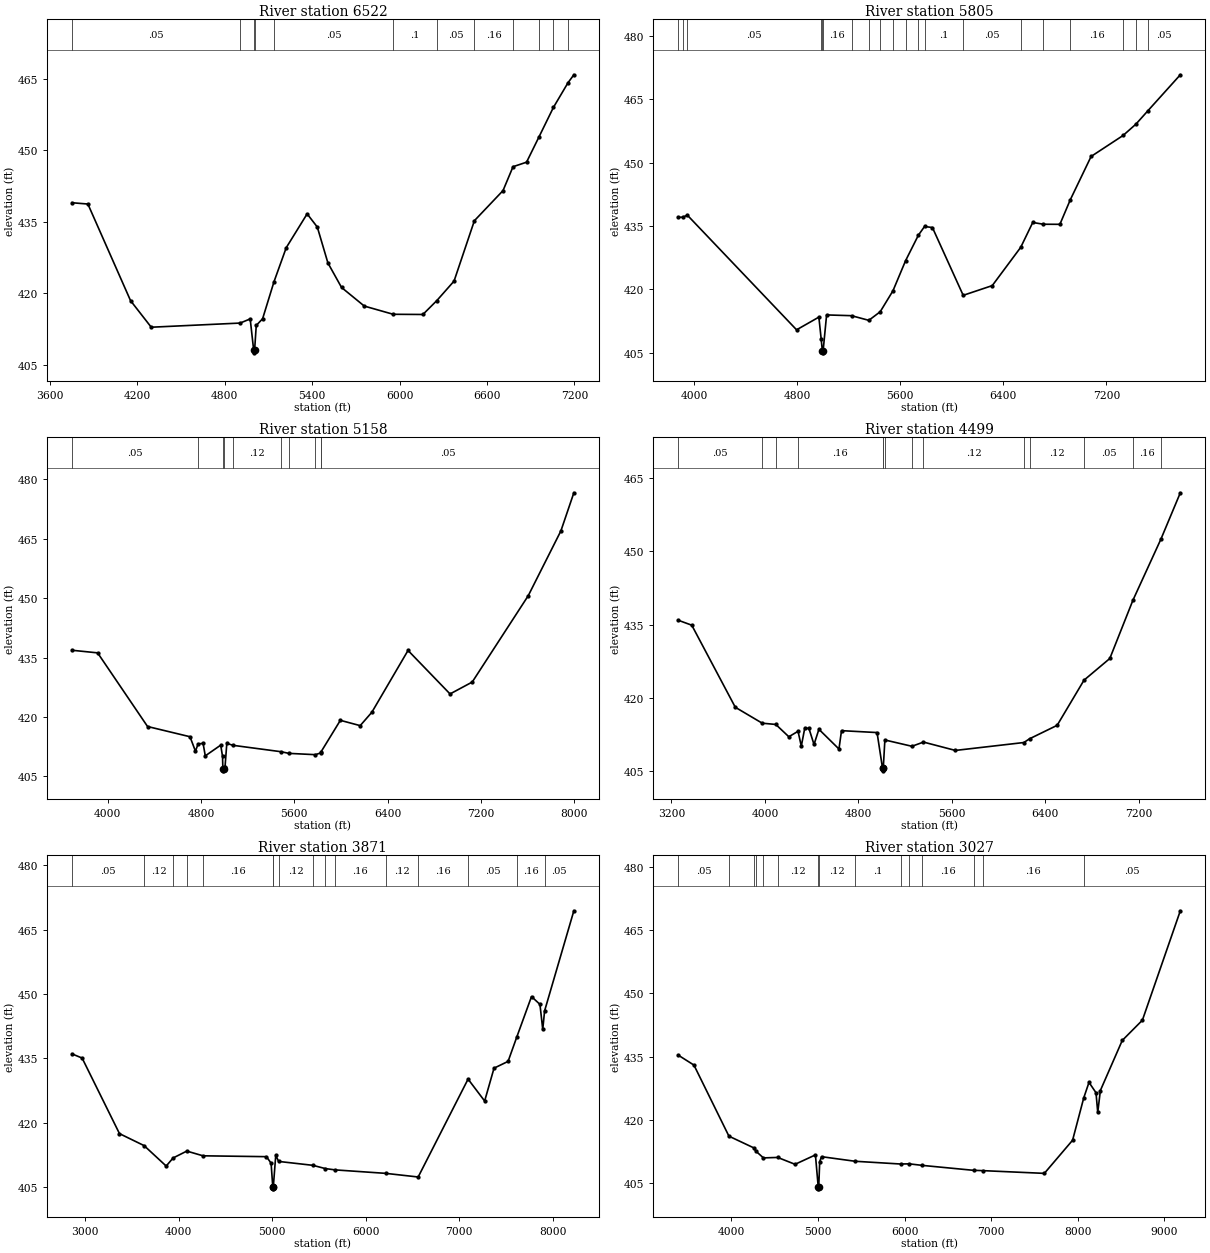
Type RM Length L Ch R = 1 ,6522    ,717,717,717
BEGIN DESCRIPTION:
PATTON CREEK 5.2
END DESCRIPTION:
XS GIS Cut Line= 3
      3542434.17     10571232.88       3541281.4     10570350.94
      3539324.89     10569976.29
#Sta/Elev= 30
  3752.7     439    3862  438.73  4154.9  418.47  4296.7  412.91  4906.6  413.78
  4975.6  414.65  4999.7  408.04  5002.4  407.54  5005.7  408.04  5017.2  413.28
  5060.8  414.69  5139.2  422.47  5222.9  429.58  5366.3  436.67  5436.1   433.9
  5508.9  426.37  5602.4  421.24  5758.5  417.34  5956.8  415.62  6160.5  415.58
  6256.6  418.51  6374.3  422.58  6513.7  435.23  6710.3  441.55  6778.8  446.55
  6871.7   447.5  6956.2  452.75  7056.2  458.99  7156.1  464.15  7196.2  465.82
#Mann= 12 ,-1 , 0
  3752.7     .05       0  4906.6     .16       0  4999.7     .07       0
  5005.7     .16       0  5139.2     .05       0  5956.8      .1       0
  6256.6     .05       0  6513.7     .16       0  6778.8     .05       0
  6956.2     .16       0  7056.2     .05       0  7156.1     .16       0
Bank Sta=4999.7,5005.7
XS Rating Curve= 0 ,0
Exp/Cntr=0.3,0.1

Type RM Length L Ch R = 1 ,5805    ,647,647,647
BEGIN DESCRIPTION:
PATTON CREEK 4.0
END DESCRIPTION:
XS GIS Cut Line= 4
      3543037.98      10570438.3      3542142.14     10570094.55
      3541171.47     10570055.86      3539226.27     10569792.57
#Sta/Elev= 30
  3879.7  437.04  3913.8  437.07  3948.8  437.56  4796.4  410.46  4969.4  413.46
    4987  408.37  4996.4  405.52  4999.1  405.02  5002.4  405.52  5029.4  413.98
  5222.7   413.8  5356.9   412.7  5445.2  414.73    5544  419.67  5642.8  426.84
  5741.6  432.83  5789.3  434.88  5850.4  434.63  6089.1  418.61  6314.6  420.91
  6535.5  429.96  6628.7  435.83    6711  435.41  6839.3  435.39  6920.4  441.22
  7081.5  451.43  7329.7  456.39    7429  459.06  7521.5  462.21  7773.6  470.73
#Mann= 20 ,-1 , 0
  3879.7     .05       0  3913.8     .08       0  3948.8     .05       0
    4987     .16       0  4996.4     .07       0  5002.4     .16       0
  5222.7     .12       0  5356.9     .16       0  5445.2     .05       0
    5544     .12       0  5642.8     .16       0  5741.6     .05       0
  5789.3      .1       0  6089.1     .05       0  6535.5     .16       0
    6711     .05       0  6920.4     .16       0  7329.7     .05       0
    7429     .12       0  7521.5     .05       0
Bank Sta=4996.4,5002.4
XS Rating Curve= 0 ,0
Exp/Cntr=0.3,0.1

Type RM Length L Ch R = 1 ,5158    ,659,659,659
BEGIN DESCRIPTION:
PATTON CREEK 3.1
END DESCRIPTION:
XS GIS Cut Line= 4
      3543142.12     10570209.12      3542043.19     10569761.22
      3541652.56     10569532.05      3538991.14     10569552.88
#Sta/Elev= 30
  3694.5  436.86  3914.5   436.2  4342.4  417.61    4706  415.03  4752.8  411.38
  4775.9  413.23  4818.4  413.34  4837.1   410.2  4969.4  412.91    4985  410.04
  4987.8  406.92  4990.6  406.42  4993.8  406.92  5006.5  407.48  5021.6  413.35
    5075  412.86  5488.3  411.24  5553.2  410.83  5780.4   410.5  5824.5  410.93
  5829.1  411.21  5994.6  419.17  6164.6  417.83  6264.6  421.21  6574.6  436.81
  6934.6  425.83  7124.6  428.83  7604.6  450.62  7884.6  466.99  7995.6  476.61
#Mann= 10 ,-1 , 0
  3694.5     .05       0  4775.9      .1       0  4987.8     .07       0
  4993.8      .1       0    5075     .12       0  5488.3     .16       0
  5553.2     .12       0  5780.4     .16       0  5824.5      .1       0
  5829.1     .05       0
Bank Sta=4987.8,4993.8
XS Rating Curve= 0 ,0
Exp/Cntr=0.3,0.1

Type RM Length L Ch R = 1 ,4499    ,628,628,628
BEGIN DESCRIPTION:
PATTON CREEK 2.3
END DESCRIPTION:
XS GIS Cut Line= 4
      3543079.64     10570073.71      3541850.48     10569177.88
      3540532.77     10569198.72      3539079.64     10569271.63
#Sta/Elev= 30
  3260.2  435.87  3374.4  434.87  3746.8  418.06  3977.1   414.8  4093.5  414.54
  4204.9  412.02  4283.5  413.14  4311.5   410.1  4340.9  413.76  4376.4  413.75
  4420.3  410.44  4462.2  413.55  4633.7  409.51  4655.4  413.27  4959.6  412.88
  5006.6  405.54  5009.3  405.04  5012.6  405.54  5026.5  411.36  5257.9  410.07
  5356.8  410.93  5629.6  409.22  6215.7  410.84  6263.8   411.6  6500.2  414.36
  6730.1  423.61  6950.8  428.05  7148.3  439.97  7388.8  452.54    7554  461.99
#Mann= 14 ,-1 , 0
  3260.2     .05       0  3977.1     .16       0  4093.5     .12       0
  4283.5     .16       0  5006.6     .07       0  5012.6     .16       0
  5026.5     .12       0  5257.9     .16       0  5356.8     .12       0
  6215.7     .05       0  6263.8     .12       0  6730.1     .05       0
  7148.3     .16       0  7388.8     .05       0
Bank Sta=5006.6,5012.6
XS Rating Curve= 0 ,0
Exp/Cntr=0.3,0.1

Type RM Length L Ch R = 1 ,3871    ,844,844,844
BEGIN DESCRIPTION:
PATTON CREEK 3.0
END DESCRIPTION:
XS GIS Cut Line= 4
      3543121.33     10569953.94      3541537.98     10568756.01
      3541162.98     10568469.55      3538260.22     10568297.58
#Sta/Elev= 30
  2858.8  436.07  2967.4   435.1  3366.9  417.48  3629.8  414.69  3866.3  409.92
  3939.7   411.8  4086.5  413.41  4259.9  412.31  4937.7  412.11  4987.6  410.59
  5005.4  405.11  5008.2  404.61  5011.4  405.11  5037.5  412.45    5068     411
  5434.7  410.09    5566  409.34  5670.2  409.03  6212.1  408.22  6559.8  407.37
  7093.2  430.19  7270.4  425.08  7370.6  432.74  7520.9  434.32  7615.3  440.08
  7771.3  449.43  7861.5  447.61  7891.5  441.78  7911.3   446.1    8224  469.43
#Mann= 16 ,-1 , 0
  2858.8     .05       0  3629.8     .12       0  3939.7     .16       0
  4086.5     .12       0  4259.9     .16       0  5005.4     .07       0
  5011.4     .16       0    5068     .12       0  5434.7     .16       0
    5566     .12       0  5670.2     .16       0  6212.1     .12       0
  6559.8     .16       0  7093.2     .05       0  7615.3     .16       0
  7911.3     .05       0
Bank Sta=5005.4,5011.4
XS Rating Curve= 0 ,0
Exp/Cntr=0.3,0.1

Type RM Length L Ch R = 1 ,3027    ,1053,1053,1053
BEGIN DESCRIPTION:
PATTON CREEK 2.0
END DESCRIPTION:
XS GIS Cut Line= 5
      3543116.09     10569870.58      3541918.19     10568391.42
      3538209.85     10567860.17      3538220.27     10567854.97
      3538096.21     10567813.61
#Sta/Elev= 30
  3390.7  435.33  3569.9     433  3973.5  416.14  4257.5  413.39    4286  412.56
  4371.7  410.98  4536.4  411.09  4736.9  409.46  4971.8  411.69    5004  404.14
  5006.8  403.64    5010  404.14  5021.4  410.11  5042.2  411.27  5430.2  410.18
  5954.4  409.53  6054.3  409.57  6206.8   409.2  6797.3  408.03  6902.2  407.96
  7613.6  407.31  7939.4  415.17  8068.4  425.23  8128.8   428.9  8209.6  426.44
  8229.8  421.77  8260.1  426.97  8512.7  438.85    8745  443.65  9182.7  469.61
#Mann= 15 ,-1 , 0
  3390.7     .05       0  3973.5     .12       0  4257.5     .16       0
    4286     .12       0  4371.7     .16       0  4536.4     .12       0
    5004     .07       0    5010     .12       0  5430.2      .1       0
  5954.4     .16       0  6054.3      .1       0  6206.8     .16       0
  6797.3      .1       0  6902.2     .16       0  8068.4     .05       0
Bank Sta=5004,5010
XS Rating Curve= 0 ,0
Exp/Cntr=0.3,0.1

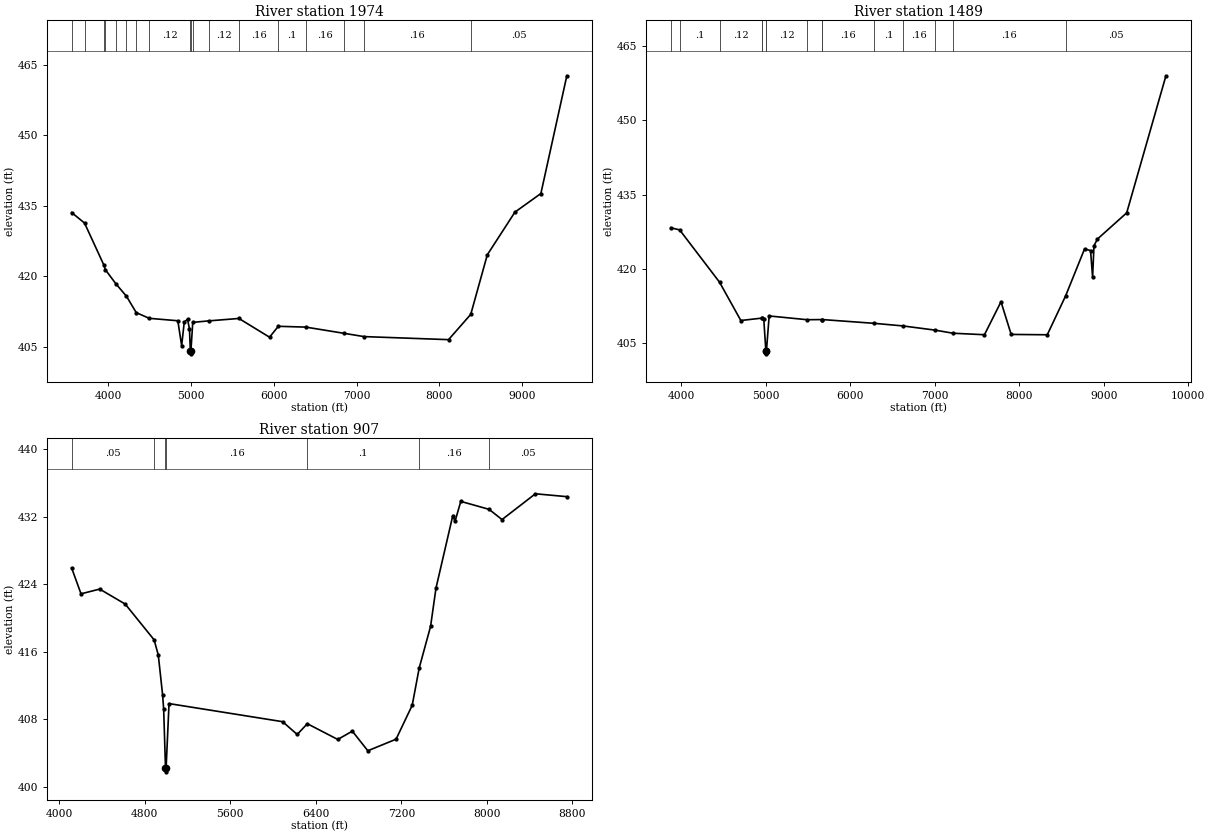
Type RM Length L Ch R = 1 ,1974    ,485,485,485
BEGIN DESCRIPTION:
PATTON CREEK 2.2
END DESCRIPTION:
XS GIS Cut Line= 6
      3543183.78     10569636.18      3542397.35     10568594.55
      3542475.48     10568349.76      3542480.69     10568203.92
      3541897.35     10568037.26      3538272.37     10567479.97
#Sta/Elev= 30
  3558.1  433.54    3714   431.3    3945  422.46  3967.4  421.33    4094  418.34
  4220.7  415.72  4338.9  412.23  4495.7  411.02  4841.3   410.5  4887.3   405.2
  4918.8  410.21  4958.3  410.82  4981.8  408.76  4992.8  403.96  4995.5  403.46
  4998.8  403.96  5021.6  410.16  5217.9  410.48  5579.1  410.99    5949     407
  6055.3  409.32  6387.6  409.15    6851  407.82  7090.8  407.13  8111.7  406.48
  8379.7  411.86  8579.8  424.54  8913.4  433.62    9227  437.58  9540.4  462.64
#Mann= 18 ,-1 , 0
  3558.1     .05       0    3714      .1       0    3945     .05       0
  3967.4      .1       0    4094     .16       0  4220.7     .12       0
  4338.9     .16       0  4495.7     .12       0  4992.8     .07       0
  4998.8     .12       0  5021.6     .16       0  5217.9     .12       0
  5579.1     .16       0  6055.3      .1       0  6387.6     .16       0
    6851      .1       0  7090.8     .16       0  8379.7     .05       0
Bank Sta=4992.8,4998.8
XS Rating Curve= 0 ,0
Exp/Cntr=0.3,0.1

Type RM Length L Ch R = 1 ,1489    ,582,582,582
BEGIN DESCRIPTION:
PATTON CREEK 2.1
END DESCRIPTION:
XS GIS Cut Line= 5
      3543282.78     10569422.71      3542955.63     10568499.95
       3542616.1     10568120.59      3540199.44     10567547.67
      3538346.14     10567193.67
#Sta/Elev= 30
  3877.6  428.32  3983.1  427.89  4455.1  417.33  4707.1  409.59  4957.8  410.08
  4958.5   410.1  4978.1  409.99  5003.5  403.36  5006.3  402.86  5009.5  403.36
  5042.3  410.51    5491  409.75  5672.5  409.78  5672.6  409.78  6285.6  409.02
  6622.7   408.5  7004.8  407.65  7218.1  407.02  7589.2  406.72    7785  413.37
  7905.4  406.78  8332.4  406.71  8549.4  414.56  8773.1  424.03  8844.4  423.72
  8868.7  418.33  8885.1  424.69  8925.9  426.04    9272  431.33  9736.2  459.01
#Mann= 15 ,-1 , 0
  3877.6     .05       0  3983.1      .1       0  4455.1     .12       0
  4957.8     .16       0  4958.5     .12       0  5003.5     .07       0
  5009.5     .12       0    5491     .16       0  5672.5      .1       0
  5672.6     .16       0  6285.6      .1       0  6622.7     .16       0
  7004.8      .1       0  7218.1     .16       0  8549.4     .05       0
Bank Sta=5003.5,5009.5
XS Rating Curve= 0 ,0
Exp/Cntr=0.3,0.1

Type RM Length L Ch R = 1 ,907     ,0,0,0
BEGIN DESCRIPTION:
PATTON CREEK 1.0
END DESCRIPTION:
XS GIS Cut Line= 5
      3543399.31     10569269.24      3543347.23     10568657.29
      3543399.31      10568097.4      3541980.04     10566118.23
      3541576.76     10565181.58
#Sta/Elev= 30
  4115.6  425.93  4203.5  422.86  4378.3  423.42  4616.7  421.65  4887.2  417.42
  4926.3  415.62  4966.4  410.94  4976.5  409.24  4993.6  402.31  4996.3  401.81
  4999.6  402.31  5026.7  409.88    6089  407.74  6225.4  406.23  6320.3   407.5
  6604.8  405.64  6741.2  406.62  6886.1   404.3  7150.1  405.67  7301.2  409.68
  7366.4  414.08  7473.1  419.02  7523.5  423.53  7680.7  432.11  7701.6  431.43
  7755.6  433.79  8020.2  432.85  8141.3  431.64  8453.3  434.69  8747.3  434.35
#Mann= 7 ,-1 , 0
  4115.6     .05       0  4887.2     .16       0  4993.6     .07       0
  4999.6     .16       0  6320.3      .1       0  7366.4     .16       0
  8020.2     .05       0
Bank Sta=4993.6,4999.6
XS Rating Curve= 0 ,0
Exp/Cntr=0.3,0.1

Chan Stop Cuts=-1
Use User Specified Reach Order=0
Composite Channel Slope=5