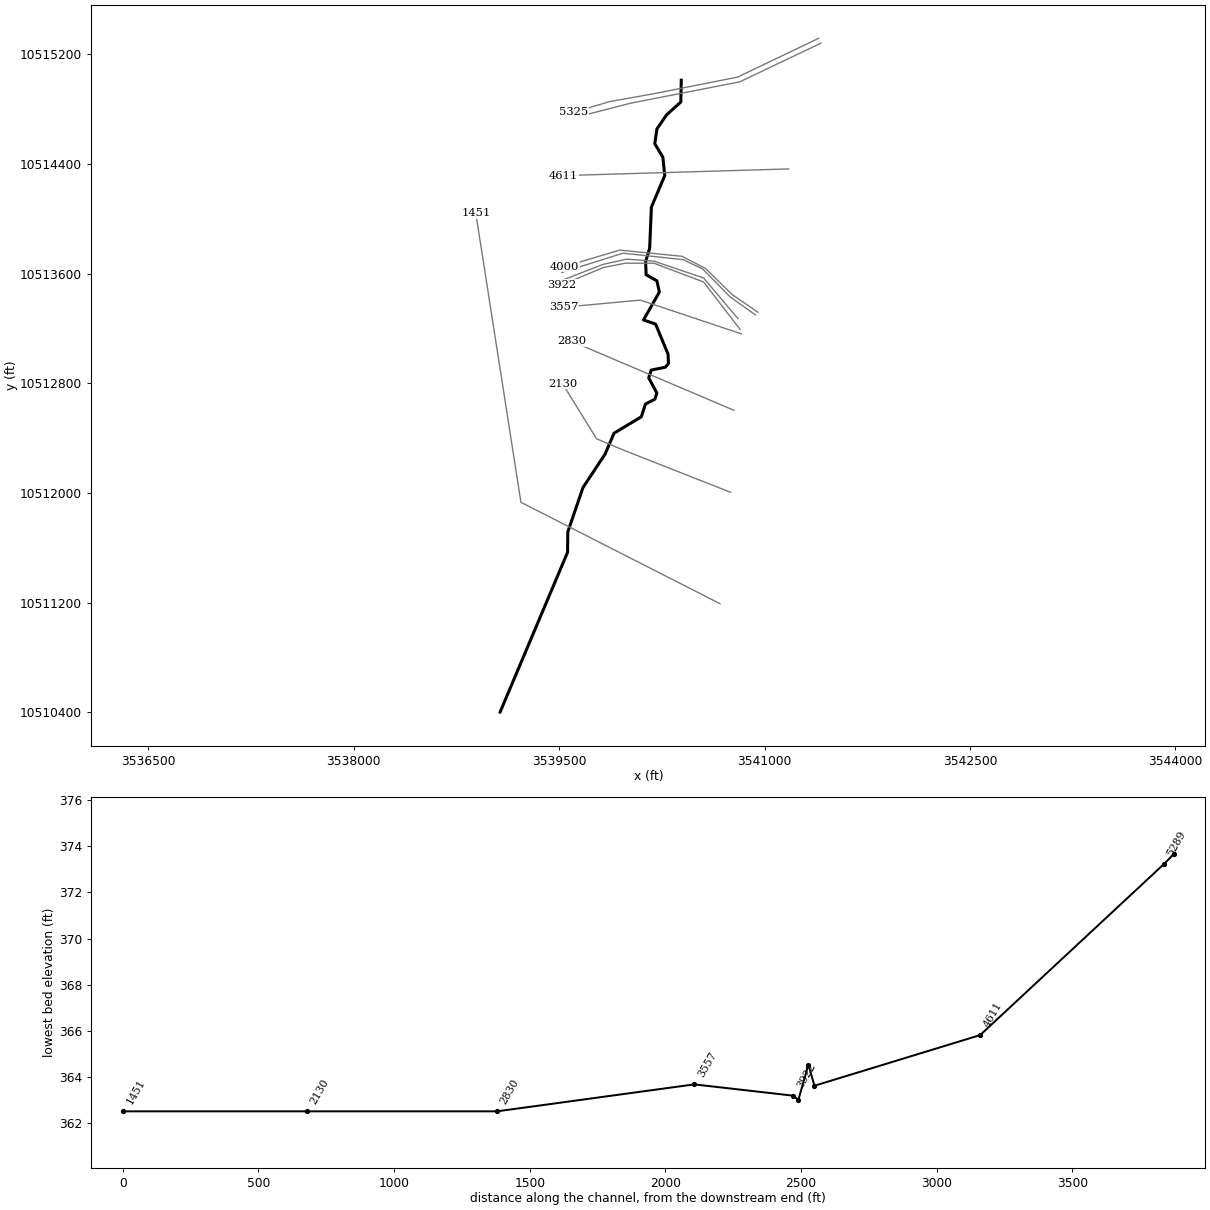
--- PEAR BRANCH.prj (project) ---

Proj Title=PEAR BRANCH Base Level Engineering
Current Plan=p01
Default Exp/Contr=0.3,0.1
English Units
Geom File=g01
Flow File=f01
Plan File=p01
BEGIN DESCRIPTION:
PEAR BRANCH
END DESCRIPTION:

--- PEAR BRANCH.p01 (plan) ---

Plan Title=Multiple Run
Short Identifier=Multiple
Geom File=g01
Flow File=f01
Subcritical Flow
K Sum by GR= 0
Std Step Tol= 0.01
Critical Tol= 0.01
Num of Std Step Trials= 20
Max Error Tol= 0.3
Flow Tol Ratio= 0.001
Split Flow NTrial= 30
Split Flow Tol= 0.02
Split Flow Ratio= 0.02
Log Output Level= 0
Friction Slope Method= 1
Unsteady Friction Slope Method= 2
Unsteady Bridges Friction Slope Method= 1
Parabolic Critical Depth
Global Vel Dist=  1 , 1 , 1
Global Log Level= 0
CheckData=True
Encroach Param= -1, 0, 0, 0
BEGIN DESCRIPTION:
Multiple Run
END DESCRIPTION:

--- PEAR BRANCH.f01 (steady flow) ---

Flow Title=Multiple
Number of Profiles=7
Profile Names=10-year,25-year,50-year,1pct_min,100-year,1pct_plu,500-year
River Rch & RM= PEAR BRANCH,Reach-1,5325
     986    1349    1646    1465    1981    2679    2862
River Rch & RM= PEAR BRANCH,Reach-1,3941
    1029    1404    1710    1518    2052    2776    2950
Boundary for River Rch & Prof#=PEAR BRANCH,Reach-1,1
Up Type=0
Dn Type=3
Dn Slope=0.005
Boundary for River Rch & Prof#=PEAR BRANCH,Reach-1,2
Up Type=0
Dn Type=3
Dn Slope=0.005
Boundary for River Rch & Prof#=PEAR BRANCH,Reach-1,3
Up Type=0
Dn Type=3
Dn Slope=0.005
Boundary for River Rch & Prof#=PEAR BRANCH,Reach-1,4
Up Type=0
Dn Type=3
Dn Slope=0.005
Boundary for River Rch & Prof#=PEAR BRANCH,Reach-1,5
Up Type=0
Dn Type=3
Dn Slope=0.005
Boundary for River Rch & Prof#=PEAR BRANCH,Reach-1,6
Up Type=0
Dn Type=3
Dn Slope=0.005
Boundary for River Rch & Prof#=PEAR BRANCH,Reach-1,7
Up Type=0
Dn Type=3
Dn Slope=0.005

--- PEAR BRANCH.g01 (geometry) ---

Geom Title=Existing Conditions

River Reach=PEAR BRANCH,Reach-1
Reach XY= 30
      3540392.11     10515011.64      3540389.01     10514852.92
      3540285.32     10514759.51      3540214.60     10514656.32
      3540198.85     10514548.33      3540258.05     10514450.04
      3540271.73     10514315.98      3540174.09     10514085.82
      3540161.46     10513786.31      3540132.04     10513687.56
      3540135.61     10513593.00      3540214.27     10513548.00
      3540232.50     10513466.70      3540116.58     10513262.45
      3540204.66     10513232.51      3540295.81     10513013.32
      3540298.84     10512944.31      3540275.84     10512917.84
      3540172.54     10512896.57      3540154.75     10512840.14
      3540214.21     10512728.60      3540199.89     10512684.76
      3540130.88     10512649.17      3540100.93     10512556.29
      3539901.27     10512436.06      3539836.17     10512284.15
      3539674.56     10512039.28      3539563.95     10511715.90
      3539562.10     10511567.17      3539069.69     10510401.66

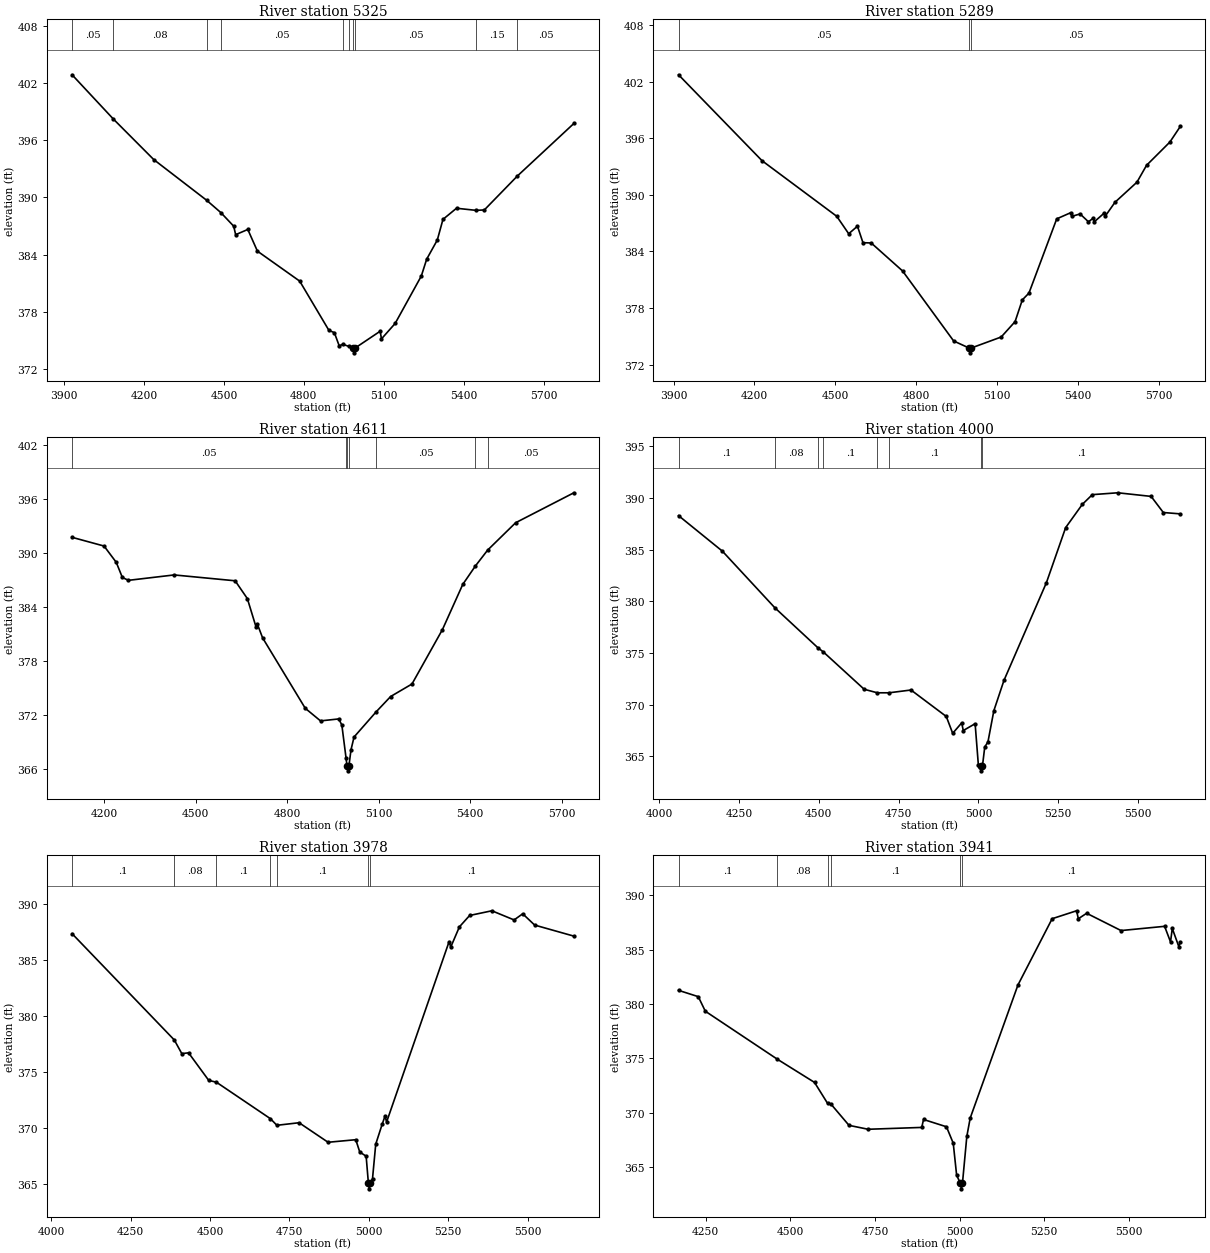
Type RM Length L Ch R = 1,5325,36,36,36
BEGIN DESCRIPTION:
PEAR BRANCH 9.0
END DESCRIPTION:
XS GIS Cut Line= 5
      3541395.62     10515317.86      3540804.21     10515034.74
      3540203.08     10514915.38      3539864.54     10514854.61
      3539605.83     10514777.00
#Sta/Elev= 30
  3930.4  402.90  4085.2  398.25  4236.7  393.99  4435.2  389.71  4488.7  388.41
  4536.9  386.98  4544.1  386.09  4589.7  386.64  4625.8  384.36  4784.4  381.21
  4894.1  376.03  4914.5  375.79  4932.7  374.40  4945.9  374.57  4967.6  374.36
  4986.0  374.17  4988.8  373.67  4992.0  374.17  5086.2  375.94  5091.3  375.14
  5142.5  376.76  5240.6  381.74  5260.9  383.52  5300.7  385.53  5321.9  387.70
  5372.7  388.87  5445.3  388.65  5477.1  388.69  5601.5  392.27  5813.0  397.78
#Mann=10,-1,0
  3930.4    0.05       0  4085.2    0.08       0  4435.2     0.1       0
  4488.7    0.05       0  4945.9    0.08       0  4967.6    0.05       0
  4986.0    0.03       0  4992.0    0.05       0  5445.3    0.15       0
  5601.5    0.05       0
Bank Sta=4986,4992
Exp/Cntr=0.3,0.1

Type RM Length L Ch R = 1,5289,678,678,678
BEGIN DESCRIPTION:
PEAR BRANCH 9.1
END DESCRIPTION:
XS GIS Cut Line= 4
      3541411.86     10515282.14      3540819.40     10515000.01
      3540020.79     10514843.76      3539642.07     10514746.38
#Sta/Elev= 30
  3918.5  402.75  4228.2  393.63  4505.3  387.73  4549.6  385.88  4582.1  386.68
  4602.5  384.93  4633.1  384.90  4749.4  381.93  4938.8  374.50  4996.9  373.74
  4999.7  373.24  5002.9  373.74  5115.1  374.92  5166.6  376.55  5193.5  378.86
  5218.1  379.58  5321.1  387.46  5372.7  388.11  5377.7  387.73  5407.8  387.98
  5438.7  387.15  5455.7  387.51  5460.9  387.16  5496.4  388.05  5501.6  387.77
  5537.2  389.22  5618.6  391.35  5654.2  393.14  5740.8  395.61  5779.5  397.27
#Mann=3,-1,0
  3918.5    0.05       0  4996.9    0.03       0  5002.9    0.05       0
Bank Sta=4996.9,5002.9
Exp/Cntr=0.3,0.1

Type RM Length L Ch R = 1,4611,611,611,611
BEGIN DESCRIPTION:
PEAR BRANCH 8.0
END DESCRIPTION:
XS GIS Cut Line= 2
      3541177.02     10514364.54      3539531.13     10514315.93
#Sta/Elev= 30
  4093.9  391.76  4198.9  390.79  4238.9  388.98  4258.9  387.30  4278.9  386.98
  4429.0  387.58  4629.0  386.93  4669.1  384.95  4697.1  381.85  4702.1  382.10
  4719.1  380.59  4859.1  372.76  4909.2  371.36  4969.2  371.58  4979.2  370.89
  4993.0  367.22  4996.2  366.31  4999.0  365.81  5002.2  366.31  5009.2  368.15
  5019.2  369.57  5091.8  372.37  5139.3  374.07  5209.3  375.46  5309.3  381.51
  5376.0  386.53  5417.5  388.58  5457.6  390.34  5549.4  393.38  5740.5  396.71
#Mann=7,-1,0
  4093.9    0.05       0  4993.0    0.16       0  4996.2    0.07       0
  5002.2    0.16       0  5091.8    0.05       0  5417.5     0.1       0
  5457.6    0.05       0
Bank Sta=4996.2,5002.2
Exp/Cntr=0.3,0.1

Type RM Length L Ch R = 1,4000,22,22,22
BEGIN DESCRIPTION:
PEAR BRANCH 6.0
END DESCRIPTION:
XS GIS Cut Line= 6
      3540951.14     10513319.18      3540761.93     10513449.38
      3540569.22     10513638.61      3540397.35     10513727.16
      3539942.49     10513772.29      3539537.95     10513650.76
#Sta/Elev= 30
  4060.3  388.30  4197.8  384.86  4362.0  379.39  4496.6  375.53  4514.2  375.11
  4642.1  371.50  4683.4  371.16  4720.1  371.16  4788.8  371.43  4899.4  368.87
  4919.5  367.24  4947.7  368.25  4952.7  367.51  4989.8  368.17  4999.9  364.20
  5006.9  364.11  5009.7  363.61  5012.9  364.11  5020.0  365.92  5030.0  366.41
  5048.5  369.43  5080.2  372.36  5213.3  381.82  5273.5  387.14  5325.8  389.39
  5357.1  390.33  5437.0  390.51  5541.4  390.16  5579.6  388.60  5632.9  388.47
#Mann=8,-1,0
  4060.3     0.1       0  4362.0    0.08       0  4496.6    0.05       0
  4514.2     0.1       0  4683.4    0.05       0  4720.1     0.1       0
  5006.9    0.07       0  5012.9     0.1       0
Bank Sta=5006.9,5012.9
Exp/Cntr=0.3,0.1

Type RM Length L Ch R = 1,3978,37,37,37
BEGIN DESCRIPTION:
PEAR BRANCH 6.1
END DESCRIPTION:
XS GIS Cut Line= 6
      3540933.99     10513299.20      3540749.78     10513430.28
      3540548.39     10513635.14      3540404.29     10513702.85
      3539966.79     10513749.72      3539520.60     10513609.10
#Sta/Elev= 30
  4065.5  387.38  4387.5  377.86  4411.1  376.64  4432.4  376.71  4496.0  374.24
  4520.0  374.08  4690.3  370.81  4710.6  370.22  4780.5  370.45  4871.8  368.70
  4959.0  368.93  4971.6  367.83  4991.7  367.45  4998.8  365.03  5001.5  364.53
  5004.8  365.03  5011.8  365.45  5021.9  368.53  5042.0  370.30  5051.1  371.04
  5056.2  370.52  5253.0  386.67  5258.2  386.18  5285.4  387.99  5317.7  389.01
  5387.7  389.43  5457.7  388.61  5484.8  389.16  5522.4  388.15  5645.9  387.16
#Mann=7,-1,0
  4065.5     0.1       0  4387.5    0.08       0  4520.0     0.1       0
  4690.3    0.05       0  4710.6     0.1       0  4998.8    0.07       0
  5004.8     0.1       0
Bank Sta=4998.8,5004.8
Exp/Cntr=0.3,0.1

Type RM Length L Ch R = 1,3941,19,19,19
BEGIN DESCRIPTION:
PEAR BRANCH 5.0
END DESCRIPTION:
XS GIS Cut Line= 6
      3540805.51     10513273.02      3540555.51     10513569.02
      3540190.92     10513692.29      3539993.01     10513706.18
      3539821.13     10513667.98      3539508.89     10513546.56
#Sta/Elev= 30
  4169.9  381.26  4228.2  380.68  4249.0  379.34  4461.9  374.92  4571.5  372.79
  4609.9  370.87  4621.0  370.76  4673.3  368.84  4729.8  368.48  4888.1  368.65
  4893.4  369.38  4961.1  368.71  4981.1  367.20  4991.1  364.26  5002.3  363.50
  5005.0  363.00  5008.3  363.50  5021.2  367.82  5031.2  369.51  5172.3  381.76
  5273.2  387.85  5345.2  388.58  5350.6  387.85  5375.1  388.35  5476.6  386.76
  5605.3  387.15  5622.7  385.72  5628.0  386.95  5647.2  385.29  5651.7  385.71
#Mann=6,-1,0
  4169.9     0.1       0  4461.9    0.08       0  4609.9    0.05       0
  4621.0     0.1       0  5002.3    0.07       0  5008.3     0.1       0
Bank Sta=5002.3,5008.3
Exp/Cntr=0.3,0.1

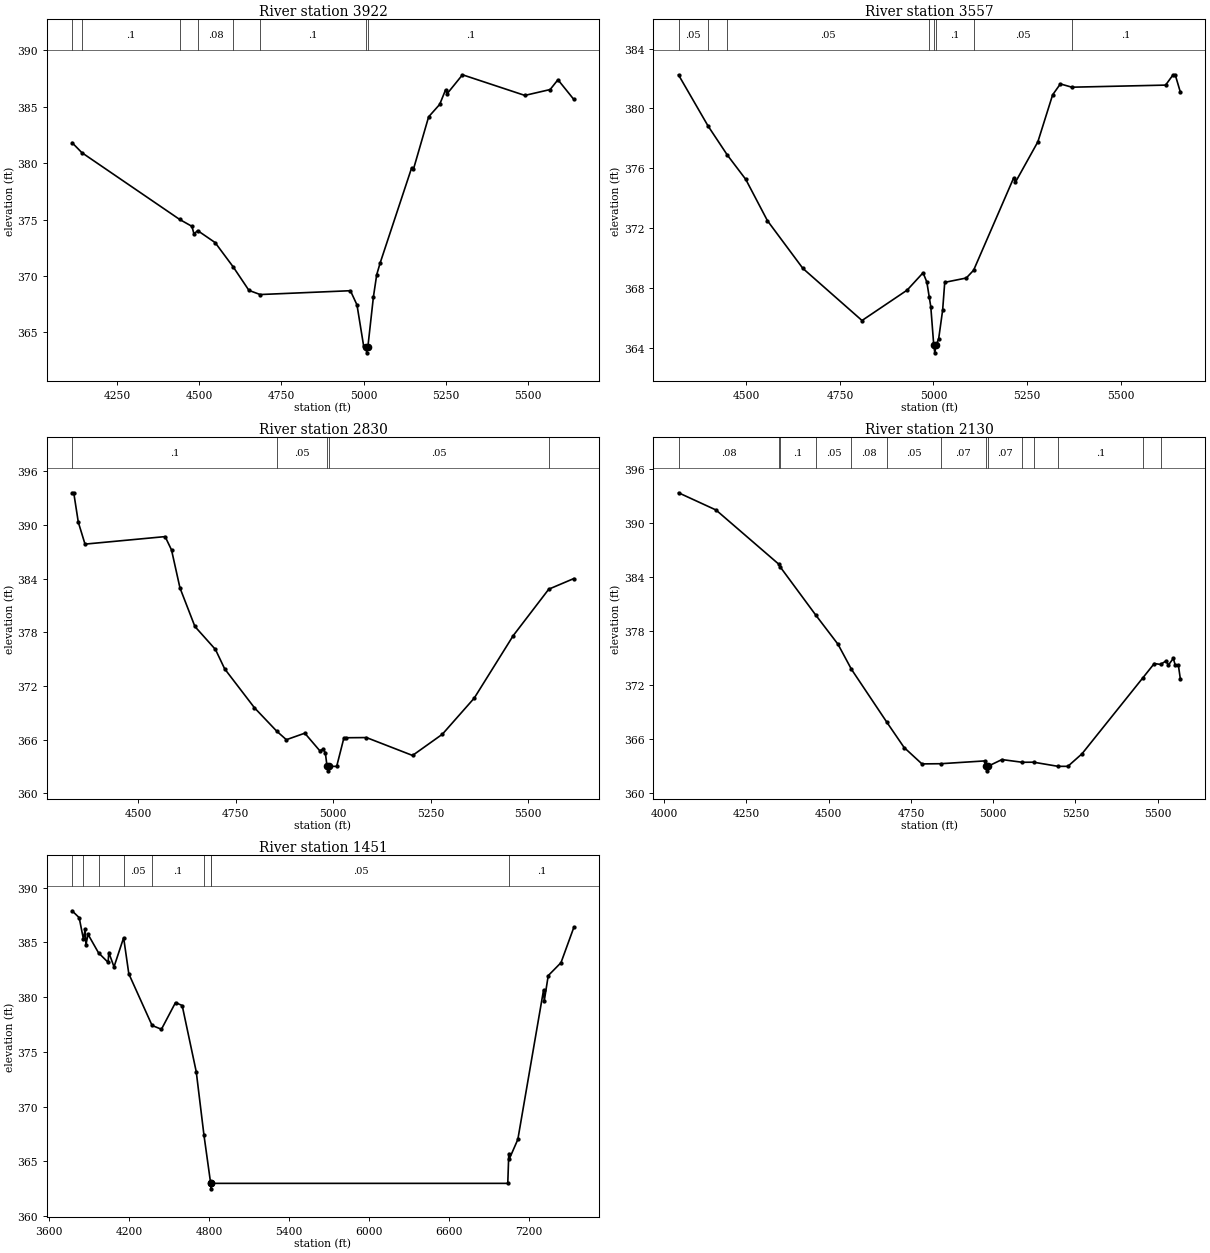
Type RM Length L Ch R = 1,3922,365,365,365
BEGIN DESCRIPTION:
PEAR BRANCH 5.1
END DESCRIPTION:
XS GIS Cut Line= 6
      3540822.87     10513192.29      3540555.51     10513539.51
      3540192.66     10513676.66      3539984.33     10513676.66
      3539824.60     10513645.41      3539520.79     10513518.68
#Sta/Elev= 30
  4113.2  381.82  4143.1  380.93  4440.5  375.01  4477.7  374.40  4484.0  373.73
  4495.3  374.02  4548.3  372.96  4603.4  370.80  4651.2  368.72  4685.3  368.35
  4959.9  368.69  4979.9  367.43  4999.9  363.83  5006.9  363.68  5009.6  363.18
  5012.9  363.68  5029.9  368.15  5039.9  370.11  5049.9  371.11  5146.3  379.60
  5151.4  379.44  5197.8  384.11  5231.4  385.21  5249.3  386.50  5254.4  386.17
  5300.8  387.84  5490.5  386.01  5567.4  386.53  5591.2  387.40  5639.6  385.65
#Mann=8,-1,0
  4113.2    0.05       0  4143.1     0.1       0  4440.5    0.05       0
  4495.3    0.08       0  4603.4    0.05       0  4685.3     0.1       0
  5006.9    0.07       0  5012.9     0.1       0
Bank Sta=5006.9,5012.9
Exp/Cntr=0.3,0.1

Type RM Length L Ch R = 1,3557,727,727,727
BEGIN DESCRIPTION:
PEAR BRANCH 5.2
END DESCRIPTION:
XS GIS Cut Line= 3
      3540831.58     10513161.03      3540093.70     10513407.57
      3539532.89     10513355.48
#Sta/Elev= 30
  4318.7  382.24  4397.8  378.82  4449.3  376.88  4498.4  375.26  4556.3  372.50
  4651.1  369.31  4809.1  365.83  4929.7  367.86  4972.3  369.02  4982.4  368.40
  4988.9  367.38  4992.9  366.76  5000.9  364.17  5003.7  363.67  5006.9  364.17
  5014.0  364.61  5024.6  366.52  5030.2  368.38  5087.8  368.67  5107.4  369.19
  5214.3  375.35  5219.3  375.08  5279.1  377.77  5318.6  380.91  5339.3  381.64
  5369.9  381.42  5620.5  381.56  5640.6  382.25  5646.5  382.23  5659.9  381.10
#Mann=8,-1,0
  4318.7    0.05       0  4397.8     0.1       0  4449.3    0.05       0
  4988.9     0.1       0  5000.9    0.07       0  5006.9     0.1       0
  5107.4    0.05       0  5369.9     0.1       0
Bank Sta=5000.9,5006.9
Exp/Cntr=0.3,0.1

Type RM Length L Ch R = 1,2830,700,700,700
BEGIN DESCRIPTION:
PEAR BRANCH 4.0
END DESCRIPTION:
XS GIS Cut Line= 2
      3540776.87     10512603.31      3539592.18     10513106.69
#Sta/Elev= 30
  4329.9  393.59  4334.2  393.59  4345.9  390.30  4363.1  387.85  4568.6  388.69
  4585.0  387.20  4606.7  382.95  4645.0  378.64  4697.7  376.07  4721.4  373.90
  4797.8  369.55  4854.8  366.94  4879.6  365.98  4926.9  366.71  4965.3  364.75
  4974.2  364.93  4979.6  364.50  4984.0  363.00  4986.7  362.50  4990.0  363.00
  5008.7  363.00  5026.9  366.13  5032.4  366.20  5085.1  366.22  5203.3  364.22
  5279.7  366.59  5361.5  370.63  5461.6  377.62  5552.7  382.81  5617.1  384.00
#Mann=5,-1,0
  4329.9     0.1       0  4854.8    0.05       0  4984.0   0.035       0
  4990.0    0.05       0  5552.7     0.1       0
Bank Sta=4984,4990
Exp/Cntr=0.3,0.1

Type RM Length L Ch R = 1,2130,679,679,679
BEGIN DESCRIPTION:
PEAR BRANCH 2.0
END DESCRIPTION:
XS GIS Cut Line= 4
      3540753.00     10512005.01      3539971.73     10512312.31
      3539773.81     10512395.64      3539526.64     10512795.89
#Sta/Elev= 30
  4044.0  393.36  4157.8  391.45  4349.1  385.42  4353.6  385.10  4461.5  379.76
  4528.5  376.55  4569.4  373.77  4677.4  367.87  4729.4  365.09  4783.6  363.27
  4840.3  363.29  4973.7  363.60  4977.8  363.00  4980.5  362.50  4983.8  363.00
  5026.6  363.75  5088.7  363.45  5122.7  363.46  5197.0  363.00  5227.0  363.00
  5269.9  364.39  5454.8  372.82  5489.5  374.41  5508.5  374.31  5526.2  374.72
  5532.0  374.21  5547.4  374.99  5553.3  374.22  5562.8  374.21  5568.7  372.72
#Mann=14,-1,0
  4044.0    0.08       0  4349.1    0.05       0  4353.6     0.1       0
  4461.5    0.05       0  4569.4    0.08       0  4677.4    0.05       0
  4840.3    0.07       0  4977.8    0.07       0  4983.8    0.07       0
  5088.7    0.05       0  5122.7    0.07       0  5197.0     0.1       0
  5454.8    0.08       0  5508.5     0.1       0
Bank Sta=4977.8,4983.8
Exp/Cntr=0.3,0.1

Type RM Length L Ch R = 1,1451,0,0,0
BEGIN DESCRIPTION:
PEAR BRANCH 1.0
END DESCRIPTION:
XS GIS Cut Line= 3
      3540674.84     10511192.53      3539221.73     10511932.10
      3538892.11     10514041.61
#Sta/Elev= 30
  3771.6  387.89  3825.0  387.26  3856.9  385.30  3869.5  386.19  3875.7  384.80
  3891.7  385.73  3970.1  384.05  4041.8  383.18  4047.4  384.08  4086.3  382.77
  4158.6  385.43  4197.5  382.13  4372.0  377.42  4442.2  377.07  4547.8  379.51
  4597.9  379.24  4703.5  373.19  4761.3  367.41  4811.7  363.00  4814.5  362.50
  4817.7  363.00  7041.3  363.00  7048.9  365.72  7053.8  365.26  7116.7  367.01
  7310.0  380.67  7315.1  379.66  7344.9  381.97  7440.6  383.15  7537.2  386.38
#Mann=9,-1,0
  3771.6    0.05       0  3856.9    0.08       0  3970.1     0.1       0
  4158.6    0.05       0  4372.0     0.1       0  4761.3    0.05       0
  4811.7   0.033       0  4817.7    0.05       0  7053.8     0.1       0
Bank Sta=4811.7,4817.7
Exp/Cntr=0.3,0.1

Chan Stop Cuts=-1