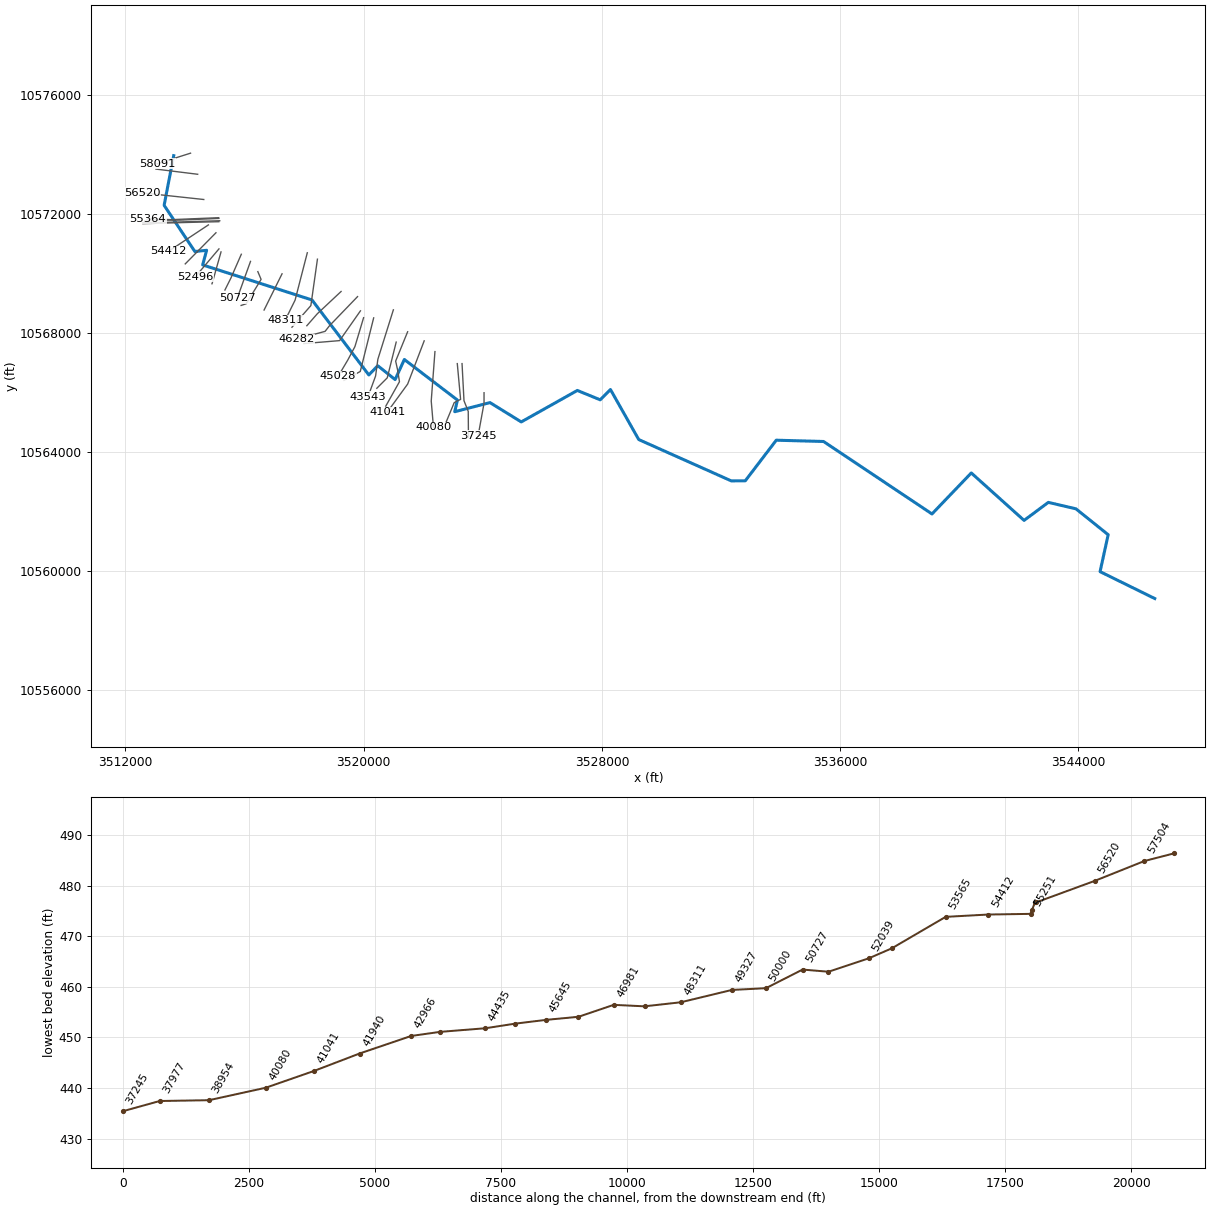
--- PERRY CREEK.prj (project) ---

Proj Title=PERRY CREEK Base Level Engineering
Current Plan=p01
Default Exp/Contr=0.3,0.1
English Units
Geom File=g01
Flow File=f01
Plan File=p01
Y Axis Title=Elevation
X Axis Title(PF)=Main Channel Distance
X Axis Title(XS)=Station
BEGIN DESCRIPTION:
PERRY CREEK
END DESCRIPTION:
DSS Export Rating Curves= 0
DSS Export Rating Curve Sorted= 0
DSS Export Volume Flow Curves= 0
DXF OffsetX= 0
DXF OffsetY= 0
DXF ScaleX= 1
DXF ScaleY= 10

--- PERRY CREEK.p01 (plan) ---

Plan Title=Multiple Run
Short Identifier=Multiple
Geom File=g01
Flow File=f01
Subcritical Flow
K Sum by GR= 0
Std Step Tol= 0.01
Critical Tol= 0.01
Num of Std Step Trials= 20
Max Error Tol= 0.3
Flow Tol Ratio= 0.001
Split Flow NTrial= 30
Split Flow Tol= 0.02
Split Flow Ratio= 0.02
Log Output Level= 0
Friction Slope Method= 1
Unsteady Friction Slope Method= 2
Unsteady Bridges Friction Slope Method= 1
Parabolic Critical Depth
Global Vel Dist=  1 , 1 , 1
Global Log Level= 0
CheckData=True
Encroach Param= -1, 0, 0, 0
BEGIN DESCRIPTION:
Multiple Run
END DESCRIPTION:

--- PERRY CREEK.f01 (steady flow) ---

Flow Title=Multiple
Program Version=4.10
Number of Profiles= 7
Profile Names=10-year,25-year,50-year,1pct_min,100-year,1pct_plu,500-year
River Rch & RM=PERRY CREEK,Reach-1         ,58091
     923    1258    1532    1361    1840    2489    2649
River Rch & RM=PERRY CREEK,Reach-1         ,57504
    1380    1921    2372    2133    2885    3901    4258
River Rch & RM=PERRY CREEK,Reach-1         ,55251
    1609    2255    2795    2523    3412    4614    5072
River Rch & RM=PERRY CREEK,Reach-1         ,49327
    2077    2942    3674    3337    4513    6104    6797
River Rch & RM=PERRY CREEK,Reach-1         ,46282
    2589    3695    4638    4229    5719    7734    8683
River Rch & RM=PERRY CREEK,Reach-1         ,43543
    3014    4321    5439    4972    6724    9093   10260
River Rch & RM=PERRY CREEK,Reach-1         ,37977
    3365    4844    6115    5603    7578   10248   11620
River Rch & RM=PERRY CREEK,Reach-1         ,34894
    3690    5328    6739    6185    8365   11312   12869
River Rch & RM=PERRY CREEK,Reach-1         ,32483
    3829    5520    6975    6394    8647   11694   13268
River Rch & RM=PERRY CREEK,Reach-1         ,28165
    4074    5884    7443    6829    9236   12490   14199
River Rch & RM=PERRY CREEK,Reach-1         ,21561
    4075    5875    7421    6799    9195   12436   14094
River Rch & RM=PERRY CREEK,Reach-1         ,19175
    4399    6349    8026    7357    9950   13456   15265
River Rch & RM=PERRY CREEK,Reach-1         ,13094
    4865    7021    8876    8133   10998   14874   16858
Boundary for River Rch & Prof#=PERRY CREEK,Reach-1         , 1
Up Type= 0
Dn Type= 3
Dn Slope=0.001
Boundary for River Rch & Prof#=PERRY CREEK,Reach-1         , 2
Up Type= 0
Dn Type= 3
Dn Slope=0.001
Boundary for River Rch & Prof#=PERRY CREEK,Reach-1         , 3
Up Type= 0
Dn Type= 3
Dn Slope=0.001
Boundary for River Rch & Prof#=PERRY CREEK,Reach-1         , 4
Up Type= 0
Dn Type= 3
Dn Slope=0.001
Boundary for River Rch & Prof#=PERRY CREEK,Reach-1         , 5
Up Type= 0
Dn Type= 3
Dn Slope=0.001
Boundary for River Rch & Prof#=PERRY CREEK,Reach-1         , 6
Up Type= 0
Dn Type= 3
Dn Slope=0.001
Boundary for River Rch & Prof#=PERRY CREEK,Reach-1         , 7
Up Type= 0
Dn Type= 3
Dn Slope=0.001
DSS Import GetInterval= 0
DSS Import GetPeak= 0
DSS Import FillOption= 0

--- PERRY CREEK.g01 (geometry) ---

Geom Title=Existing Conditions
Program Version=4.10

River Reach=PERRY CREEK     ,Reach-1
Reach XY= 30
      3513622.11     10573951.64      3513300.35     10572284.63
      3514332.71      10570732.6      3514726.95     10570774.21
      3514594.35     10570283.31      3518264.96     10569106.47
      3520173.06     10566589.38      3520473.41     10566898.06
      3521056.91     10566433.43      3521365.09     10567108.05
      3523148.22     10565746.28      3523058.38       10565355.
      3524241.43     10565660.43      3525291.59     10565011.85
      3527173.69     10566068.39      3527942.15     10565753.85
      3528286.32     10566099.47      3529235.92      10564419.3
      3532342.45     10563032.39      3532811.64     10563033.91
      3533853.79     10564397.77      3535441.18     10564354.86
      3539082.11     10561921.64      3540400.85     10563298.51
      3542173.86     10561704.88      3542987.97     10562310.32
       3543915.4       10562094.      3544997.87     10561224.54
      3544725.14     10559984.88      3546562.11     10559081.64

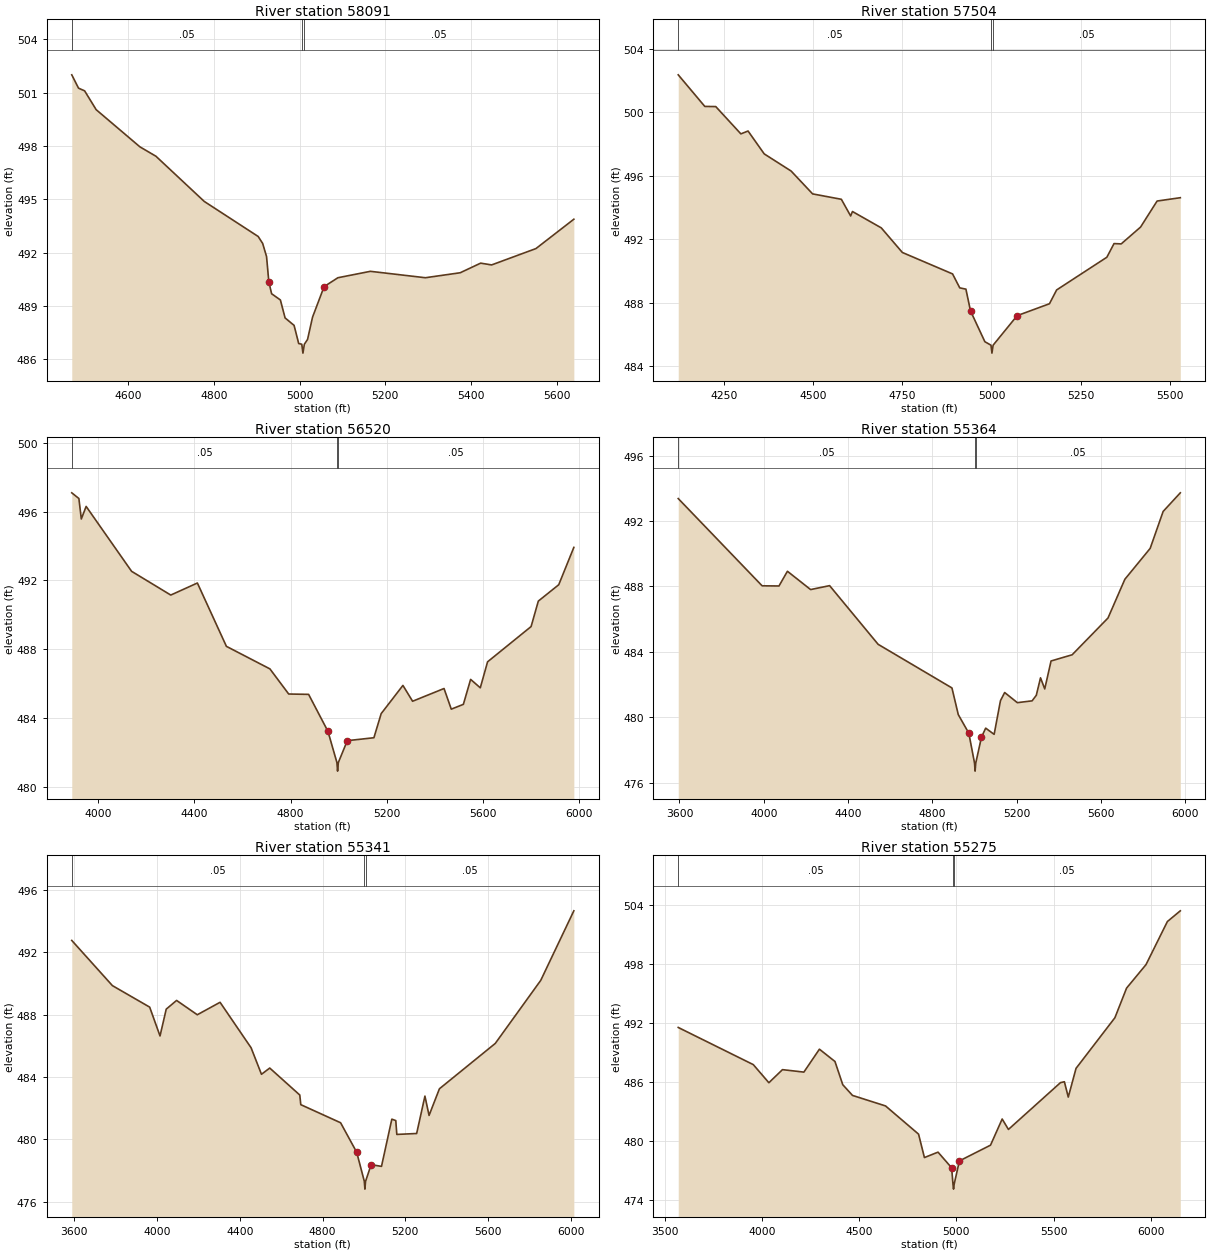
Type RM Length L Ch R = 1 ,58091   ,587,587,587
BEGIN DESCRIPTION:
PERRY CREEK 84.0
END DESCRIPTION:
XS GIS Cut Line= 2
      3514187.16     10574035.23      3513069.11     10573681.07
#Sta/Elev= 30
  4467.6     502  4483.4  501.25  4497.6   501.1  4524.6  500.04  4626.8  497.95
  4664.3  497.42  4777.1  494.88    4903  492.91  4913.5  492.52  4922.6  491.78
  4927.9  490.36  4934.4  489.69  4954.9  489.34  4965.9  488.33  4986.9  487.91
  4997.7  486.89  5004.9  486.85  5007.6  486.35  5010.9  486.85  5018.4  487.12
    5030  488.37    5057  490.09  5089.3  490.59  5165.2  490.95  5293.6  490.59
    5375  490.87  5422.7  491.41  5448.4  491.31  5551.9  492.23  5640.4  493.88
#Mann= 3 ,-1 , 0
  4467.6     .05       0  5004.9    .035       0  5010.9     .05       0
Bank Sta=4927.9,5057
XS Rating Curve= 0 ,0
Exp/Cntr=0.3,0.1

Type RM Length L Ch R = 1 ,57504   ,984,984,984
BEGIN DESCRIPTION:
PERRY CREEK 84.1
END DESCRIPTION:
XS GIS Cut Line= 2
      3514426.68      10573326.9      3513027.41      10573500.5
#Sta/Elev= 30
  4120.3  502.37  4194.9  500.38  4225.7  500.37  4296.2  498.65  4316.4  498.83
  4361.8  497.39  4437.3  496.31  4497.7  494.87  4578.4  494.53  4604.5  493.48
  4609.6  493.76  4690.5  492.73  4749.7  491.18  4890.7  489.83  4910.9  488.95
  4928.2  488.87  4941.1   487.5  4981.4  485.56  4998.6  485.34  5001.3  484.84
  5004.6  485.34  5072.1   487.2  5162.8  487.95    5183  488.82    5324  490.88
  5344.2  491.74  5364.3  491.72  5418.7  492.78  5465.1  494.42  5530.3  494.63
#Mann= 3 ,-1 , 0
  4120.3     .05       0  4998.6     .03       0  5004.6     .05       0
Bank Sta=4941.1,5072.1
XS Rating Curve= 0 ,0
Exp/Cntr=0.3,0.1

Type RM Length L Ch R = 1 ,56520   ,1156,1156,1156
BEGIN DESCRIPTION:
PERRY CREEK 83.1
END DESCRIPTION:
XS GIS Cut Line= 2
      3514631.56     10572479.67      3512555.28     10572703.43
#Sta/Elev= 30
  3889.8  497.09  3919.4  496.76  3929.5  495.57  3949.6   496.3  4138.6  492.53
  4301.6  491.15  4412.3  491.85    4533  488.17    4714  486.86  4792.1   485.4
  4874.9  485.38  4955.4  483.23  4992.6  481.42  4995.4  480.92  4998.6  481.42
  5035.9  482.69  5146.5  482.86  5176.7  484.26  5267.2   485.9  5307.4  484.98
  5438.2  485.72  5468.3  484.52  5518.6   484.8  5548.8  486.25    5589  485.76
  5619.2  487.27  5800.3  489.32  5830.4   490.8  5915.3  491.75  5978.1  493.92
#Mann= 3 ,-1 , 0
  3889.8     .05       0  4992.6     .03       0  4998.6     .05       0
Bank Sta=4955.4,5035.9
XS Rating Curve= 0 ,0
Exp/Cntr=0.3,0.1

Type RM Length L Ch R = 1 ,55364   ,23,23,23
BEGIN DESCRIPTION:
PERRY CREEK 83.0
END DESCRIPTION:
XS GIS Cut Line= 3
      3515129.81     10571868.49      3513545.56     10571803.38
      3512749.17     10571829.42
#Sta/Elev= 30
  3594.3  493.38  3992.3  488.04  4072.4  488.03  4112.4  488.93  4222.5  487.81
  4312.6  488.05  4542.8  484.46  4893.1  481.79  4923.1  480.16  4973.2  479.02
  5000.2   477.2  5002.9   476.7  5006.2   477.2  5033.2  478.78  5053.2  479.33
  5093.3  478.95  5123.3  481.01  5143.3  481.51  5203.4  480.89  5273.4     481
  5293.4  481.34  5313.4  482.41  5333.4  481.73  5363.4  483.44  5463.5  483.82
  5633.6  486.07  5713.6  488.44  5833.7  490.33  5895.2  492.59  5976.7  493.73
#Mann= 3 ,-1 , 0
  3594.3     .05       0  5000.2     .04       0  5006.2     .05       0
Bank Sta=4973.2,5033.2
XS Rating Curve= 0 ,0
Exp/Cntr=0.3,0.1

Type RM Length L Ch R = 1 ,55341   ,66,66,66
BEGIN DESCRIPTION:
PERRY CREEK 82.0
END DESCRIPTION:
XS GIS Cut Line= 4
      3515138.42     10571844.61      3513842.87     10571788.19
      3513458.76     10571786.02       3512712.2      10571794.7
#Sta/Elev= 30
  3587.7  492.76  3784.2  489.86  3964.4  488.48  4014.4  486.63  4044.4  488.35
  4094.5  488.91  4194.6  487.99  4304.7  488.79  4454.8  485.87  4504.9  484.17
  4544.9  484.57  4690.1  482.84  4695.1  482.22  4887.4  481.06  4965.2  479.17
  5002.2   477.3    5005   476.8  5008.2   477.3  5035.2  478.37  5085.2  478.26
  5135.2  481.29  5154.3   481.2  5159.3  480.31  5255.2  480.37  5295.2  482.77
  5315.2  481.53  5365.3  483.24  5635.3  486.15  5855.3   490.2  6015.2  494.66
#Mann= 3 ,-1 , 0
  3587.7     .05       0  5002.2     .04       0  5008.2     .05       0
Bank Sta=4965.2,5035.2
XS Rating Curve= 0 ,0
Exp/Cntr=0.3,0.1

Type RM Length L Ch R = 1 ,55275   ,24,24,24
BEGIN DESCRIPTION:
PERRY CREEK 81.0
END DESCRIPTION:
XS GIS Cut Line= 4
      3515168.27     10571767.21      3513803.81     10571725.26
      3513220.04     10571710.07      3512585.63     10571705.73
#Sta/Elev= 30
  3568.6  491.57  3954.9  487.79    4035  485.95    4105  487.28  4215.1  487.03
  4295.1  489.36  4375.1  488.11  4415.2  485.75  4465.2  484.66  4635.3  483.59
  4805.3  480.72  4835.4  478.34  4905.4  478.89  4975.4   477.3  4982.4  475.63
  4985.2  475.13  4988.4  475.63  5015.4     478  5175.5   479.6  5235.5  482.26
  5267.7   481.2  5535.6  485.96  5555.6  486.05  5575.6  484.49  5615.6  487.41
  5815.6  492.56  5875.6  495.57  5975.6  497.96  6085.6  502.34  6152.1  503.43
#Mann= 3 ,-1 , 0
  3568.6     .05       0  4982.4     .04       0  4988.4     .05       0
Bank Sta=4975.4,5015.4
XS Rating Curve= 0 ,0
Exp/Cntr=0.3,0.1

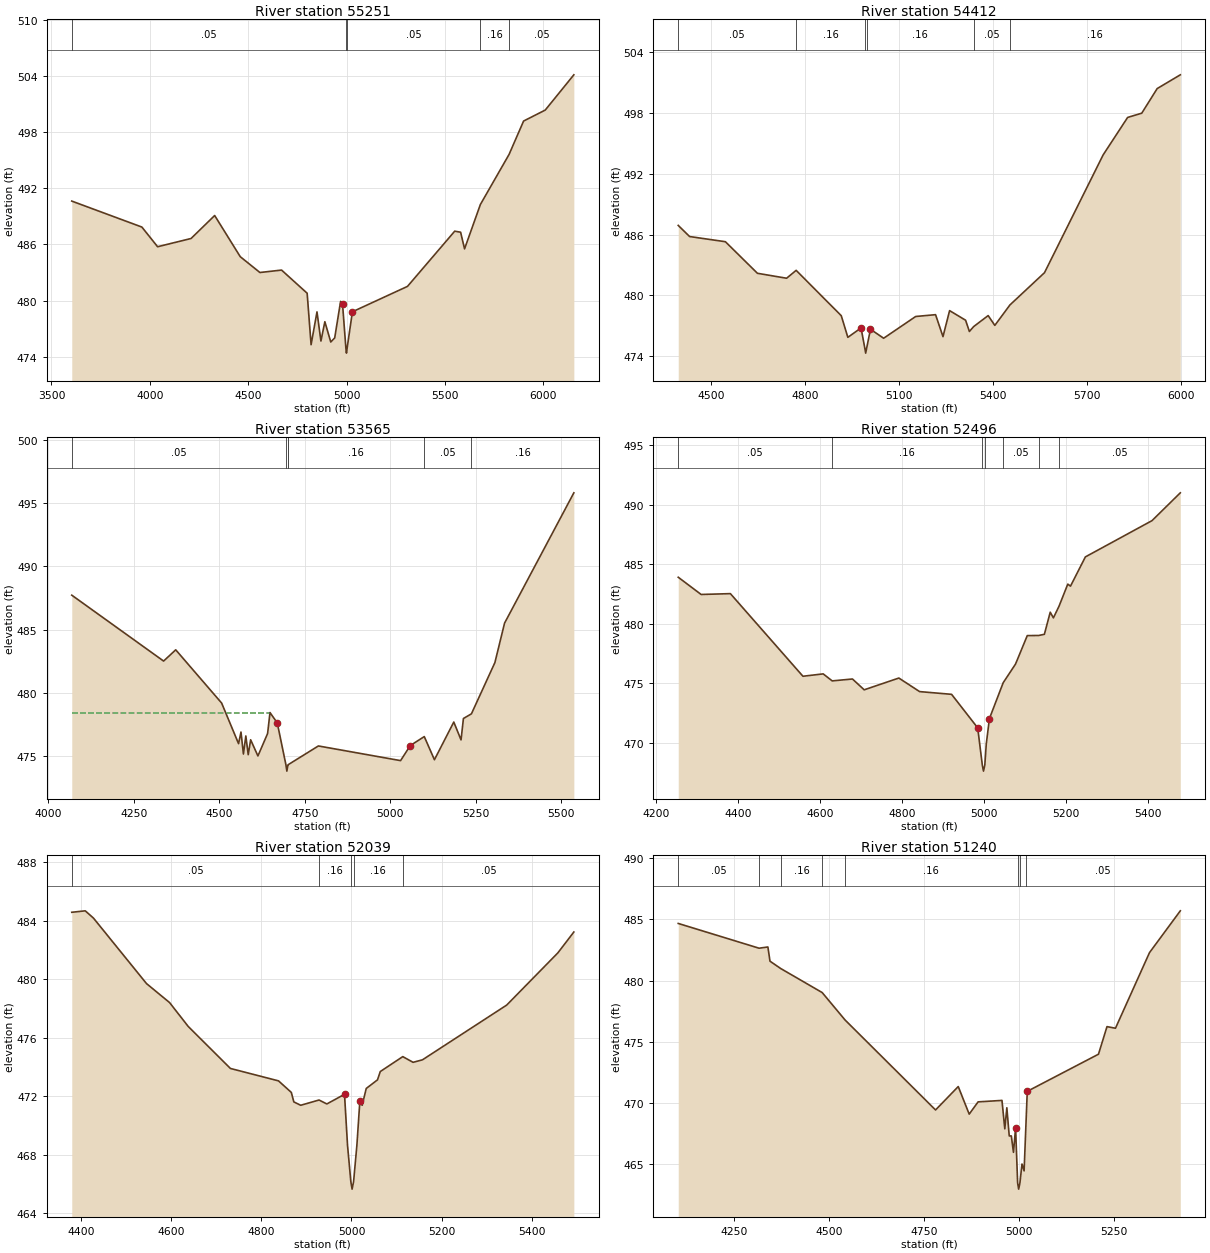
Type RM Length L Ch R = 1 ,55251   ,839,839,839
BEGIN DESCRIPTION:
PERRY CREEK 80.0
END DESCRIPTION:
XS GIS Cut Line= 3
      3515138.41     10571733.94      3514370.22     10571716.58
      3512586.75     10571668.84
#Sta/Elev= 30
  3603.2  490.63  3959.6  487.86  4039.6  485.76  4209.7  486.64  4329.7  489.09
  4459.7   484.7  4559.8  483.01  4669.8  483.27  4799.9   480.8  4819.9  475.31
  4849.9  478.81  4869.9   475.7  4889.9  477.76  4919.9   475.6  4939.9  476.03
  4969.9  479.93  4979.9  479.62  4996.9  474.91  4999.7  474.41  5002.9  474.91
  5029.9  478.82    5310  481.53  5550.1  487.42  5580.1  487.31  5600.1  485.53
  5680.4  490.26  5826.2   495.6  5900.3  499.17  6010.3  500.34  6155.7   504.1
#Mann= 5 ,-1 , 0
  3603.2     .05       0  4996.9     .04       0  5002.9     .05       0
  5680.4     .16       0  5826.2     .05       0
Bank Sta=4979.9,5029.9
XS Rating Curve= 0 ,0
Exp/Cntr=0.3,0.1

Type RM Length L Ch R = 1 ,54412   ,847,847,847
BEGIN DESCRIPTION:
PERRY CREEK 79.0
END DESCRIPTION:
XS GIS Cut Line= 2
      3514787.28     10571626.71      3513450.51     10570741.31
#Sta/Elev= 30
  4394.5   486.9  4430.8   485.8  4545.1  485.29  4647.4  482.17  4740.6  481.68
  4771.1  482.46  4915.1  477.98  4936.2  475.84  4978.3  476.77  4990.3  474.78
  4993.1  474.28  4996.3  474.78  5008.4  476.64  5050.5  475.75  5152.8   477.9
  5216.3  478.08    5240  475.91  5261.1  478.48  5312.2  477.53  5324.3  476.42
  5338.2  476.91  5384.3  477.99  5405.5  477.02  5453.8  479.04  5564.2  482.23
  5751.5  493.87  5829.7  497.57  5874.8  497.99    5924  500.42  5997.9  501.78
#Mann= 6 ,-1 , 0
  4394.5     .05       0  4771.1     .16       0  4990.3     .07       0
  4996.3     .16       0  5338.2     .05       0  5453.8     .16       0
Bank Sta=4978.3,5008.4
XS Rating Curve= 0 ,0
Exp/Cntr=0.3,0.1

Type RM Length L Ch R = 1 ,53565   ,1069,1069,1069
BEGIN DESCRIPTION:
PERRY CREEK 78.0
END DESCRIPTION:
XS GIS Cut Line= 2
      3515040.79     10571362.84      3514009.51     10570317.67
#Sta/Elev= 30
  4068.6  487.73  4337.2  482.52  4372.6  483.41  4506.9   479.2  4556.4  475.99
  4563.5  476.91  4570.6  475.17  4577.6   476.6  4584.7  475.12  4591.7   476.3
    4613  475.02  4641.3  476.79  4648.3  478.45  4669.6  477.63  4694.9  474.32
  4697.6  473.82  4700.9  474.32    4701  474.32  4789.8  475.81  5030.2  474.65
  5058.5  475.84  5099.5  476.55  5129.2  474.72  5185.8   477.7    5207  476.29
    5214  477.98  5237.4  478.35    5306   482.4  5334.3  485.52  5536.9  495.82
#Mann= 6 ,-1 , 0
  4068.6     .05       0  4694.9     .07       0  4700.9     .05       0
    4701     .16       0  5099.5     .05       0  5237.4     .16       0
#XS Ineff= 2 , 0
         4648.12  478.45
Permanent Ineff=
       F       F
Bank Sta=4669.6,5058.5
XS Rating Curve= 0 ,0
Exp/Cntr=0.3,0.1

Type RM Length L Ch R = 1 ,52496   ,457,457,457
BEGIN DESCRIPTION:
PERRY CREEK 77.0
END DESCRIPTION:
XS GIS Cut Line= 2
      3515141.51      10570821.2      3514349.84     10569887.17
#Sta/Elev= 30
  4253.5  483.91  4309.3  482.46  4380.7  482.53  4557.6  475.58    4607  475.78
    4629  475.19  4678.4  475.35    4707  474.44  4791.5  475.43  4842.1  474.29
  4920.1  474.06  4983.8  471.24  4995.1   468.1  4997.9   467.6  5001.1   468.1
  5004.7  469.88  5012.4  472.02  5045.9  475.03  5076.1  476.61  5104.7     479
  5132.7  479.01  5146.4  479.11  5160.7  480.97  5168.4  480.49  5182.1  481.47
  5203.5  483.33  5210.1  483.16  5246.4  485.62  5408.9  488.67  5477.9  491.01
#Mann= 7 ,-1 , 0
  4253.5     .05       0    4629     .16       0  4995.1     .07       0
  5001.1     .16       0  5045.9     .05       0  5132.7     .16       0
  5182.1     .05       0
Bank Sta=4983.8,5012.4
XS Rating Curve= 0 ,0
Exp/Cntr=0.3,0.1

Type RM Length L Ch R = 1 ,52039   ,799,799,799
BEGIN DESCRIPTION:
PERRY CREEK 76.0
END DESCRIPTION:
XS GIS Cut Line= 3
      3515210.92     10570720.46      3514912.32     10569661.45
      3514906.24     10569649.29
#Sta/Elev= 30
  4379.4  484.58  4409.3  484.68  4427.6  484.18  4545.2   479.7  4596.4   478.4
  4637.9  476.76  4731.4  473.89  4838.1  473.04  4866.5  472.25  4872.1   471.6
  4887.3  471.37    4928  471.73  4945.3  471.46  4984.5  472.12  4991.2  468.63
  4998.6  466.13  5001.3  465.63  5004.6  466.13    5012  468.65  5018.5  471.64
  5023.7  471.37  5032.7  472.52  5057.7  473.11  5063.9  473.68  5113.8   474.7
  5136.6  474.31  5157.4  474.48  5344.4  478.23  5457.8   481.8  5493.3  483.23
#Mann= 5 ,-1 , 0
  4379.4     .05       0    4928     .16       0  4998.6     .07       0
  5004.6     .16       0  5113.8     .05       0
Bank Sta=4984.5,5018.5
XS Rating Curve= 0 ,0
Exp/Cntr=0.3,0.1

Type RM Length L Ch R = 1 ,51240   ,513,513,513
BEGIN DESCRIPTION:
PERRY CREEK 74.0
END DESCRIPTION:
XS GIS Cut Line= 3
      3515892.11     10570641.64      3515542.11     10569841.64
      3515342.12     10569441.67
#Sta/Elev= 30
  4103.3  484.66  4315.9  482.64  4339.1  482.74  4344.6  481.58  4372.9  480.98
  4481.9  479.02  4542.1  476.78    4780  469.44  4839.7  471.35  4868.5   469.1
  4891.9   470.1  4954.7  470.22  4962.1   467.9  4967.5  469.62  4973.8  467.32
  4979.3  467.32  4984.9  465.98  4990.5  467.97  4995.9  463.48  4998.6  462.98
  5001.9  463.48  5007.3  465.03  5012.9  464.47  5018.1  468.54  5021.2  470.96
  5208.5  473.99  5230.9  476.24  5253.2  476.11  5342.7  482.28  5423.7  485.69
#Mann= 8 ,-1 , 0
  4103.3     .05       0  4315.9     .12       0  4372.9     .16       0
  4481.9     .12       0  4542.1     .16       0  4995.9     .07       0
  5001.9     .16       0  5018.1     .05       0
Bank Sta=4990.5,5021.2
XS Rating Curve= 0 ,0
Exp/Cntr=0.3,0.1

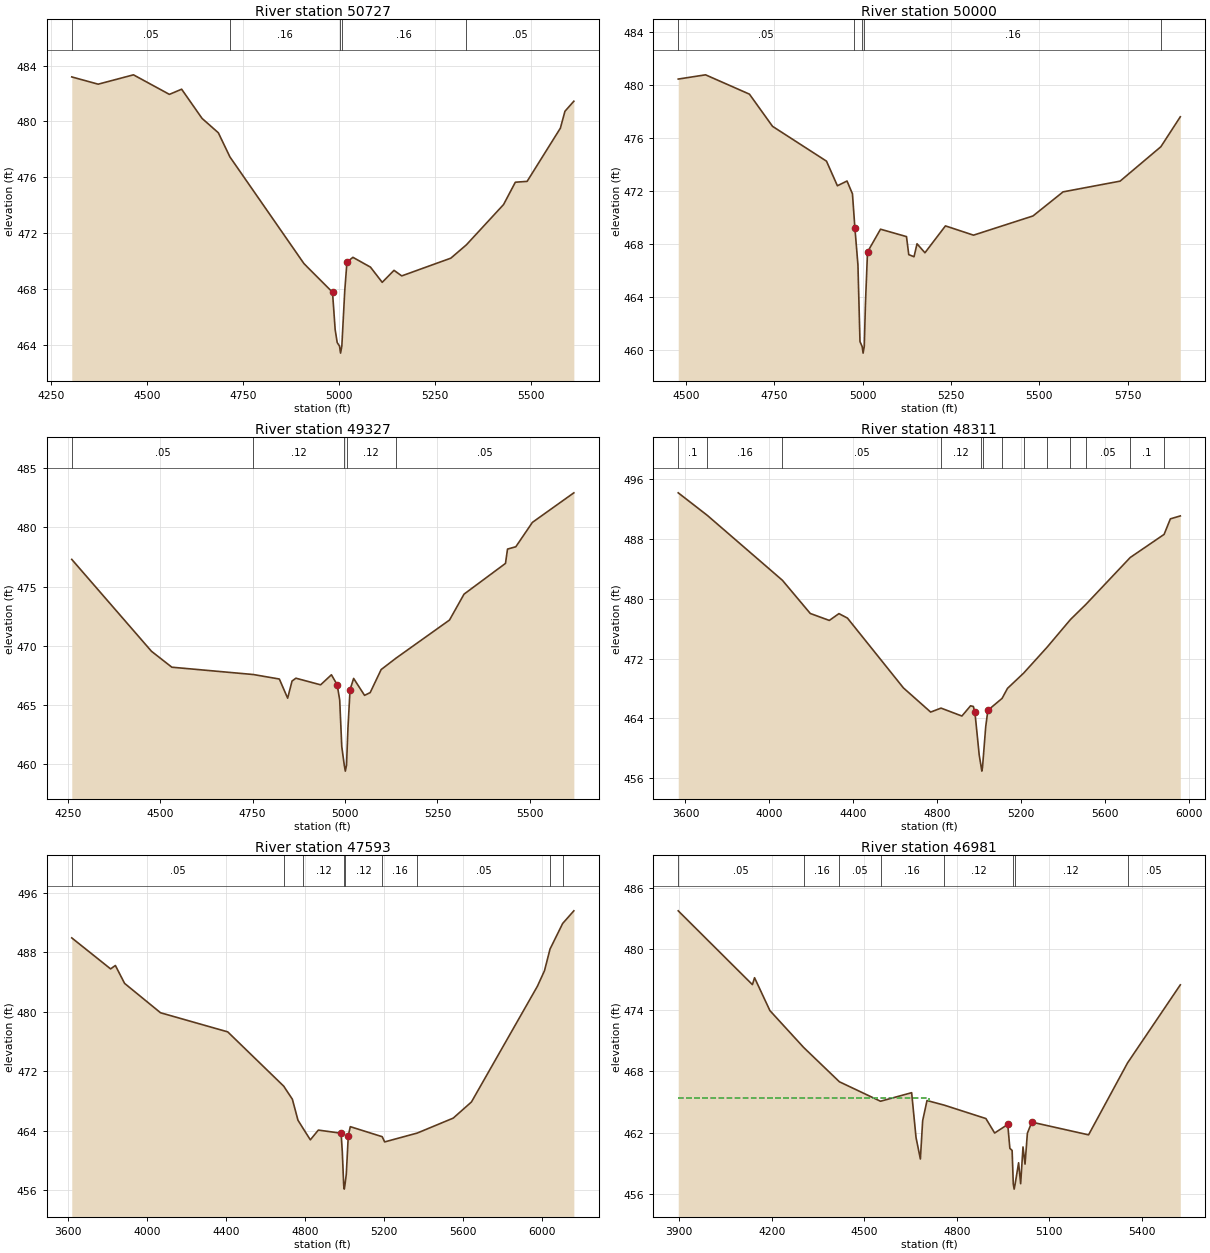
Type RM Length L Ch R = 1 ,50727   ,727,727,727
BEGIN DESCRIPTION:
PERRY CREEK 73.0
END DESCRIPTION:
XS GIS Cut Line= 2
      3516200.52     10570401.06      3515756.59     10569169.85
#Sta/Elev= 30
  4303.3  483.19  4372.1  482.67  4464.1  483.34  4557.8  481.94  4589.7  482.31
  4642.9  480.22  4685.4  479.19  4715.6  477.46  4908.6  469.82    4983  467.77
  4989.9   465.1  4995.2  464.17  5001.3  463.91    5004  463.41  5007.3  463.91
  5014.9  467.87  5020.6  469.93  5036.2  470.27  5081.9  469.57  5112.6  468.48
  5143.3  469.34  5163.4  468.94  5291.4  470.21  5331.8  471.16  5428.9  474.05
  5459.6  475.65  5490.3  475.71    5577  479.52  5588.9  480.73  5612.1  481.45
#Mann= 5 ,-1 , 0
  4303.3     .05       0  4715.6     .16       0  5001.3     .07       0
  5007.3     .16       0  5331.8     .05       0
Bank Sta=4983,5020.6
XS Rating Curve= 0 ,0
Exp/Cntr=0.3,0.1

Type RM Length L Ch R = 1 ,50000   ,673,673,673
BEGIN DESCRIPTION:
PERRY CREEK 71.0
END DESCRIPTION:
XS GIS Cut Line= 4
      3516447.06     10570057.59      3516556.42     10569797.22
      3516056.42     10568979.51      3515885.81     10568922.64
#Sta/Elev= 30
    4478  480.43  4555.3  480.75  4679.5  479.29  4744.8  476.86  4897.5  474.23
  4928.4  472.37  4955.6  472.73    4971  471.76    4975  470.26  4977.9  469.18
  4986.5   466.4  4992.3   460.6  4998.4  460.23  5001.1  459.73  5004.4  460.23
  5007.8  463.51  5013.6  467.37  5050.4  469.09  5123.9  468.53  5130.3  467.17
  5145.2  467.01  5153.7  467.99  5176.1  467.31  5234.1  469.34  5313.5  468.64
  5481.8  470.09    5567  471.91  5728.3  472.72  5843.7  475.32  5898.7  477.58
#Mann= 5 ,-1 , 0
    4478     .05       0    4975     .16       0  4998.4     .07       0
  5004.4     .16       0  5843.7     .05       0
Bank Sta=4977.9,5013.6
XS Rating Curve= 0 ,0
Exp/Cntr=0.3,0.1

Type RM Length L Ch R = 1 ,49327   ,1016,1016,1016
BEGIN DESCRIPTION:
PERRY CREEK 70.0
END DESCRIPTION:
XS GIS Cut Line= 2
      3517259.56     10569984.75       3516656.4     10568768.04
#Sta/Elev= 30
  4260.8   477.3  4476.3  469.53  4531.5  468.18  4752.1  467.56  4822.3  467.18
  4844.7  465.56  4856.6  467.01    4867  467.25  4933.9  466.69  4963.1  467.54
  4978.6   466.7  4985.5  465.41  4991.1  461.47  4997.9  459.89  5000.7  459.39
  5003.9  459.89  5007.9  463.08  5013.5  466.28  5023.2  467.23  5052.7   465.8
  5067.9  466.03  5097.6  467.98  5137.6  468.94  5282.5  472.17  5321.8  474.36
  5433.9  476.96  5439.4  478.17  5461.9  478.37  5506.7  480.43  5618.8  482.93
#Mann= 5 ,-1 , 0
  4260.8     .05       0  4752.1     .12       0  4997.9     .07       0
  5003.9     .12       0  5137.6     .05       0
Bank Sta=4978.6,5013.5
XS Rating Curve= 0 ,0
Exp/Cntr=0.3,0.1

Type RM Length L Ch R = 1 ,48311   ,718,718,718
BEGIN DESCRIPTION:
PERRY CREEK 68.0
END DESCRIPTION:
XS GIS Cut Line= 3
      3518107.58     10570691.37      3517697.85     10569101.07
      3517364.52     10568427.47
#Sta/Elev= 30
  3565.6  494.18  3704.4  491.16  4062.3  482.48  4195.2  478.04    4286  477.11
  4331.8  478.02  4372.5  477.42  4639.3  468.08  4769.1  464.85  4818.6  465.38
  4918.1  464.32  4959.4  465.69  4972.6   465.6  4980.1  464.83  5000.7  459.08
  5010.3  457.45  5013.1  456.95  5016.3  457.45  5031.7  462.92    5042  465.09
  5109.6  466.68  5135.4  468.02  5212.4  470.06    5324  473.52  5435.6  477.23
  5509.1  479.25  5720.7  485.53  5882.1  488.62  5912.1   490.7  5959.4  491.09
#Mann= 13 ,-1 , 0
  3565.6      .1       0  3704.4     .16       0  4062.3     .05       0
  4818.6     .12       0  5010.3     .07       0  5016.3     .12       0
  5109.6     .16       0  5212.4      .1       0    5324     .16       0
  5435.6      .1       0  5509.1     .05       0  5720.7      .1       0
  5882.1     .05       0
Bank Sta=4980.1,5042
XS Rating Curve= 0 ,0
Exp/Cntr=0.3,0.1

Type RM Length L Ch R = 1 ,47593   ,612,612,612
BEGIN DESCRIPTION:
PERRY CREEK 66.0
END DESCRIPTION:
XS GIS Cut Line= 3
      3518447.85     10570476.07      3518227.17     10568917.43
       3517592.1     10568191.64
#Sta/Elev= 30
  3620.3  489.94  3816.7  485.77  3840.8  486.23  3887.4  483.82  4069.2  479.87
  4408.9   477.3  4691.9     470  4735.7  468.24    4764  465.42  4791.5  464.25
  4826.6  462.78    4867  464.09  4982.1  463.67  4988.2  461.17  4995.3  456.65
  4998.1  456.15  5001.3  456.65  5008.4  458.17  5018.5  463.34  5028.6  464.55
    5190   463.2  5202.2   462.5    5367  463.69  5549.1   465.7  5641.1  467.87
  5974.3  483.42  6010.4  485.52  6038.5  488.44  6102.4  491.88  6158.9  493.58
#Mann= 9 ,-1 , 0
  3620.3     .05       0  4691.9     .16       0  4791.5     .12       0
  4995.3     .07       0  5001.3     .12       0    5190     .16       0
    5367     .05       0  6038.5      .1       0  6102.4     .05       0
Bank Sta=4982.1,5018.5
XS Rating Curve= 0 ,0
Exp/Cntr=0.3,0.1

Type RM Length L Ch R = 1 ,46981   ,699,699,699
BEGIN DESCRIPTION:
PERRY CREEK 65.0
END DESCRIPTION:
XS GIS Cut Line= 3
      3519242.14     10569391.67      3518442.11     10568641.64
      3518092.13     10568241.67
#Sta/Elev= 30
  3896.5  483.77  4137.1  476.52    4144   477.2  4193.8  473.97  4303.3  470.35
  4419.2  466.98  4552.4  465.07  4653.4  465.91  4667.6  461.51  4681.7   459.4
  4689.1  463.16  4703.2  465.14  4758.8  464.69  4894.2  463.37  4922.5  461.95
    4965  462.79  4971.9  460.44  4979.2  460.24    4983  456.94  4985.8  456.44
    4989  456.94  5000.2  459.03  5006.9  456.97  5014.5  460.58  5021.1   458.9
  5028.7  461.93    5043  463.02  5227.1  461.77  5353.4  468.83  5524.6   476.5
#Mann= 8 ,-1 , 0
  3896.5     .05       0  4303.3     .16       0  4419.2     .05       0
  4552.4     .16       0  4758.8     .12       0    4983     .07       0
    4989     .12       0  5353.4     .05       0
#XS Ineff= 2 , 0
         4709.94  465.35
Permanent Ineff=
       F       F
Bank Sta=4965,5043
XS Rating Curve= 0 ,0
Exp/Cntr=0.3,0.1

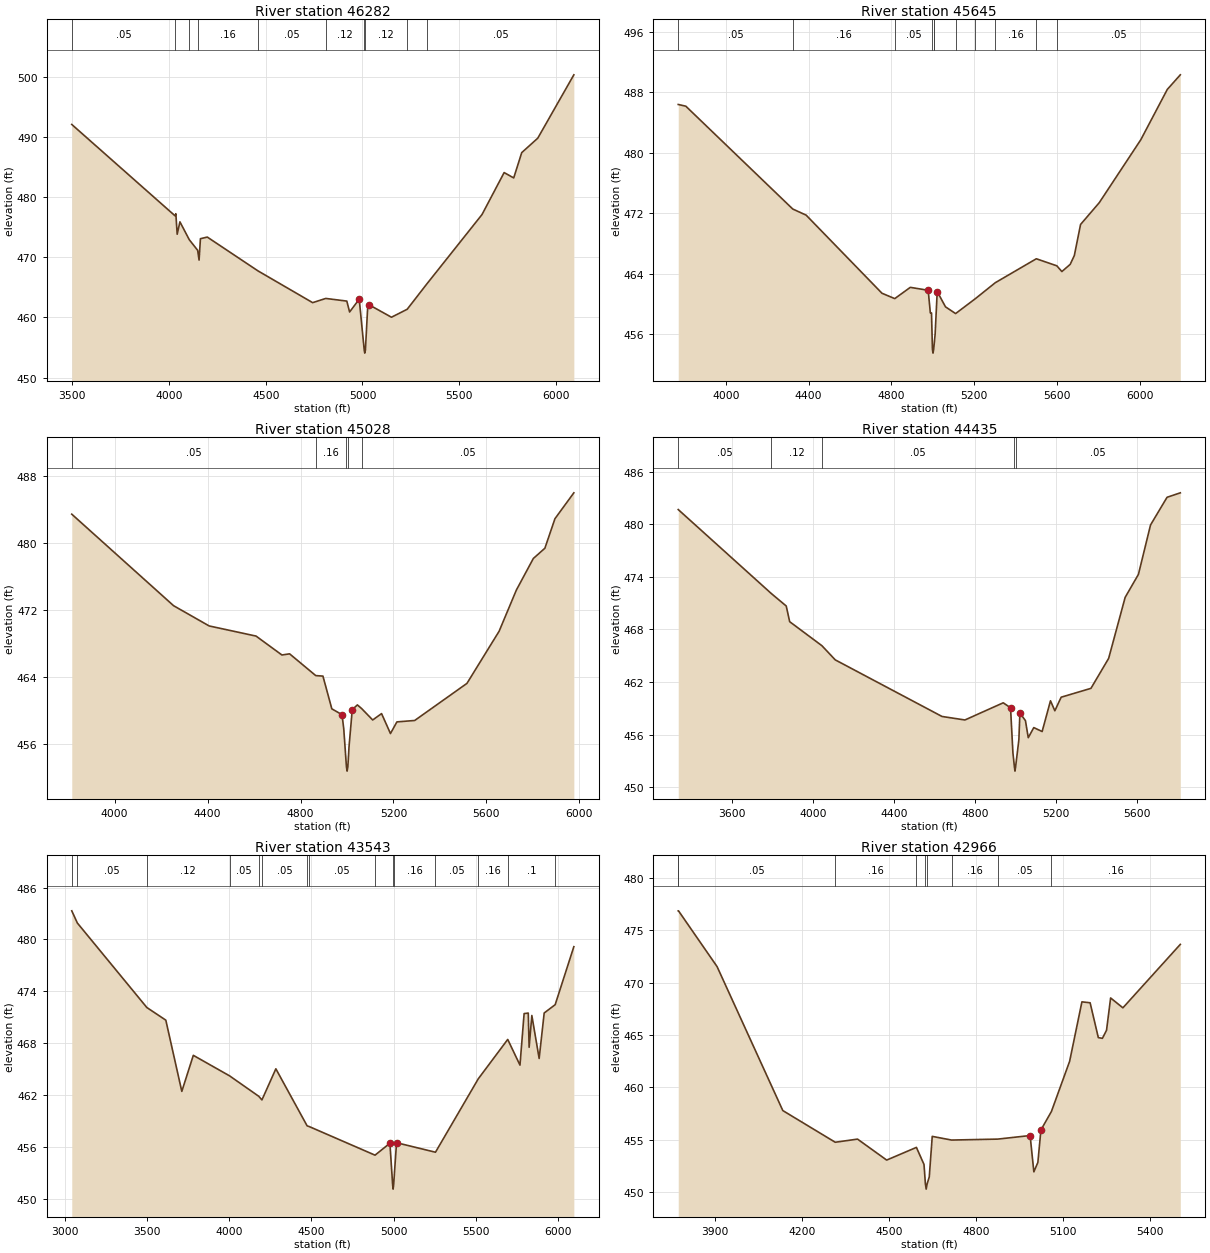
Type RM Length L Ch R = 1 ,46282   ,637,637,637
BEGIN DESCRIPTION:
PERRY CREEK 64.0
END DESCRIPTION:
XS GIS Cut Line= 4
       3519795.1     10569219.16      3518857.57     10568246.91
      3518704.79     10568052.46      3517742.13     10567791.65
#Sta/Elev= 30
  3497.2  492.05  4031.1  476.88  4035.2  477.23  4042.1  473.82  4056.3  475.88
  4104.7  472.91    4148  471.15  4155.3  469.53  4162.3  473.08  4197.8  473.35
  4459.5  467.74  4742.4  462.46  4810.2  463.16  4918.9  462.72  4933.4  460.91
  4983.1  463.04    5009  454.58  5011.7  454.08    5015  454.58  5026.4  461.44
  5032.8  462.13  5149.7  460.04    5231  461.36  5332.4  465.56  5617.8  477.09
  5732.2  484.06  5781.7  483.17  5823.1  487.37    5906  489.77  6092.5  500.29
#Mann= 10 ,-1 , 0
  3497.2     .05       0  4031.1     .16       0  4104.7     .05       0
    4148     .16       0  4459.5     .05       0  4810.2     .12       0
    5009     .07       0    5015     .12       0    5231     .16       0
  5332.4     .05       0
Bank Sta=4983.1,5032.8
XS Rating Curve= 0 ,0
Exp/Cntr=0.3,0.1

Type RM Length L Ch R = 1 ,45645   ,617,617,617
BEGIN DESCRIPTION:
PERRY CREEK 62.0
END DESCRIPTION:
XS GIS Cut Line= 3
      3519892.13     10568741.67      3519192.11     10567741.64
      3517992.06     10567641.64
#Sta/Elev= 30
  3770.1  486.37  3806.8  486.14  4323.2  472.54  4387.9  471.73  4754.1   461.4
  4815.8  460.69    4891  462.18  4977.3  461.79  4987.7   458.8  4993.3   458.8
  4997.8  453.98  5000.6  453.48  5003.8  453.98    5005  454.32  5010.9  456.01
  5020.9  461.62    5061   459.6  5109.7  458.71  5205.5  460.69  5301.7   462.8
  5499.6  465.96  5598.5  465.03    5623  464.27  5663.1  465.22  5683.2  466.39
  5713.3   470.5  5803.6  473.38  6004.3  481.71  6132.2  488.36    6195  490.29
#Mann= 11 ,-1 , 0
  3770.1     .05       0  4323.2     .16       0  4815.8     .05       0
  4997.8     .03       0  5003.8     .05       0    5005     .12       0
  5109.7     .16       0  5205.5     .12       0  5301.7     .16       0
  5499.6     .12       0  5598.5     .05       0
Bank Sta=4977.3,5020.9
XS Rating Curve= 0 ,0
Exp/Cntr=0.3,0.1

Type RM Length L Ch R = 1 ,45028   ,593,593,593
BEGIN DESCRIPTION:
PERRY CREEK 61.0
END DESCRIPTION:
XS GIS Cut Line= 4
      3519997.53     10568511.39      3519705.88     10567539.21
      3519469.77     10567094.76      3519142.13     10566541.68
#Sta/Elev= 30
  3815.4  483.42  4253.6  472.49  4406.8  470.07  4608.6  468.86    4720   466.6
    4753  466.74  4865.5  464.14  4896.5  464.08  4934.8  460.17  4978.7  459.47
  4986.2  457.76  4997.7  453.23  5000.5  452.73  5003.7  453.23  5008.8  455.63
  5022.7  460.07  5044.7  460.64  5062.8  460.21  5110.7  458.84  5148.9   459.6
  5187.2  457.22  5214.9  458.61  5291.5  458.78  5516.4  463.21  5654.9  469.44
    5729  474.35  5802.2  478.13  5851.8  479.35  5895.2  482.88  5976.5  485.97
#Mann= 5 ,-1 , 0
  3815.4     .05       0  4865.5     .16       0  4997.7     .07       0
  5003.7     .16       0  5062.8     .05       0
Bank Sta=4978.7,5022.7
XS Rating Curve= 0 ,0
Exp/Cntr=0.3,0.1

Type RM Length L Ch R = 1 ,44435   ,892,892,892
BEGIN DESCRIPTION:
PERRY CREEK 59.0
END DESCRIPTION:
XS GIS Cut Line= 3
      3520336.11     10568505.69      3519886.11      10566705.7
      3519337.51     10566406.46
#Sta/Elev= 30
  3334.1  481.68  3794.1  472.09  3867.6  470.67  3884.6  468.88  4043.8  466.14
  4109.8  464.52  4637.1  458.06  4750.4  457.66  4939.6  459.62  4975.7  459.05
  4987.5   453.9  4994.8  452.32  4997.6  451.82  5000.8  452.32  5016.9  455.41
    5022  458.46  5049.4  457.58  5063.3  455.64  5090.6  456.79  5131.8  456.34
  5173.1  459.85  5194.6  458.71  5225.9  460.26    5373  461.27  5460.4  464.69
    5542  471.66  5607.5  474.28  5667.3  479.92  5748.9  483.08  5814.4  483.59
#Mann= 5 ,-1 , 0
  3334.1     .05       0  3794.1     .12       0  4043.8     .05       0
  4994.8     .03       0  5000.8     .05       0
Bank Sta=4975.7,5022
XS Rating Curve= 0 ,0
Exp/Cntr=0.3,0.1

Type RM Length L Ch R = 1 ,43543   ,577,577,577
BEGIN DESCRIPTION:
PERRY CREEK 58.0
END DESCRIPTION:
XS GIS Cut Line= 4
      3520997.53     10568775.27      3520476.71      10567115.6
      3520400.32      10566553.1      3520143.38     10565851.72
#Sta/Elev= 30
  3042.4  483.31  3076.4   481.9  3499.2  472.12  3614.5  470.66  3711.8  462.42
  3781.8  466.59    4002  464.22    4180  461.85  4199.1  461.43  4283.9  465.03
  4474.1  458.43  4486.6  458.35  4887.2  455.04  4977.6  456.42  4994.3  451.61
  4997.1  451.11  5000.3  451.61    5018  456.48  5254.8  455.38  5515.1  463.87
  5694.3  468.43  5768.8  465.46    5794  471.42  5819.2  471.48  5824.5  467.52
    5841   471.2  5885.5  466.23  5916.1  471.49  5982.9  472.45  6096.5  479.16
#Mann= 15 ,-1 , 0
  3042.4      .1       0  3076.4     .05       0  3499.2     .12       0
    4002     .05       0    4180     .16       0  4199.1     .05       0
  4474.1     .16       0  4486.6     .05       0  4887.2     .16       0
  4994.3     .07       0  5000.3     .16       0  5254.8     .05       0
  5515.1     .16       0  5694.3      .1       0  5982.9     .16       0
#XS Ineff= 2 , 0
         4283.94  465.02
Permanent Ineff=
       F       F
Bank Sta=4977.6,5018
XS Rating Curve= 0 ,0
Exp/Cntr=0.3,0.1

Type RM Length L Ch R = 1 ,42966   ,1026,1026,1026
BEGIN DESCRIPTION:
PERRY CREEK 56.0
END DESCRIPTION:
XS GIS Cut Line= 3
      3521092.11     10567691.67      3520792.11     10566491.64
      3520442.13     10566141.67
#Sta/Elev= 30
    3772  476.84  3772.9  476.84    3906  471.52  4132.8  457.79  4313.6  454.77
  4390.5  455.07    4491  453.07  4593.6  454.28  4619.8  452.65  4624.6   450.8
  4627.3   450.3  4630.6   450.8  4637.9  451.46  4648.2  455.33  4714.7  454.98
    4874  455.07  4985.8  455.41  4998.7  451.95  5012.5  452.84  5023.1  455.94
  5059.4  457.71  5122.1  462.49  5164.5  468.16  5192.8  468.07  5221.1  464.75
  5235.2  464.68  5249.4  465.45  5263.5  468.53  5305.9  467.59  5503.9  473.64
#Mann= 9 ,-1 , 0
    3772     .16       0  3772.9     .05       0  4313.6     .16       0
  4593.6     .05       0  4624.6     .03       0  4630.6     .05       0
  4714.7     .16       0    4874     .05       0  5059.4     .16       0
Bank Sta=4985.8,5023.1
XS Rating Curve= 0 ,0
Exp/Cntr=0.3,0.1

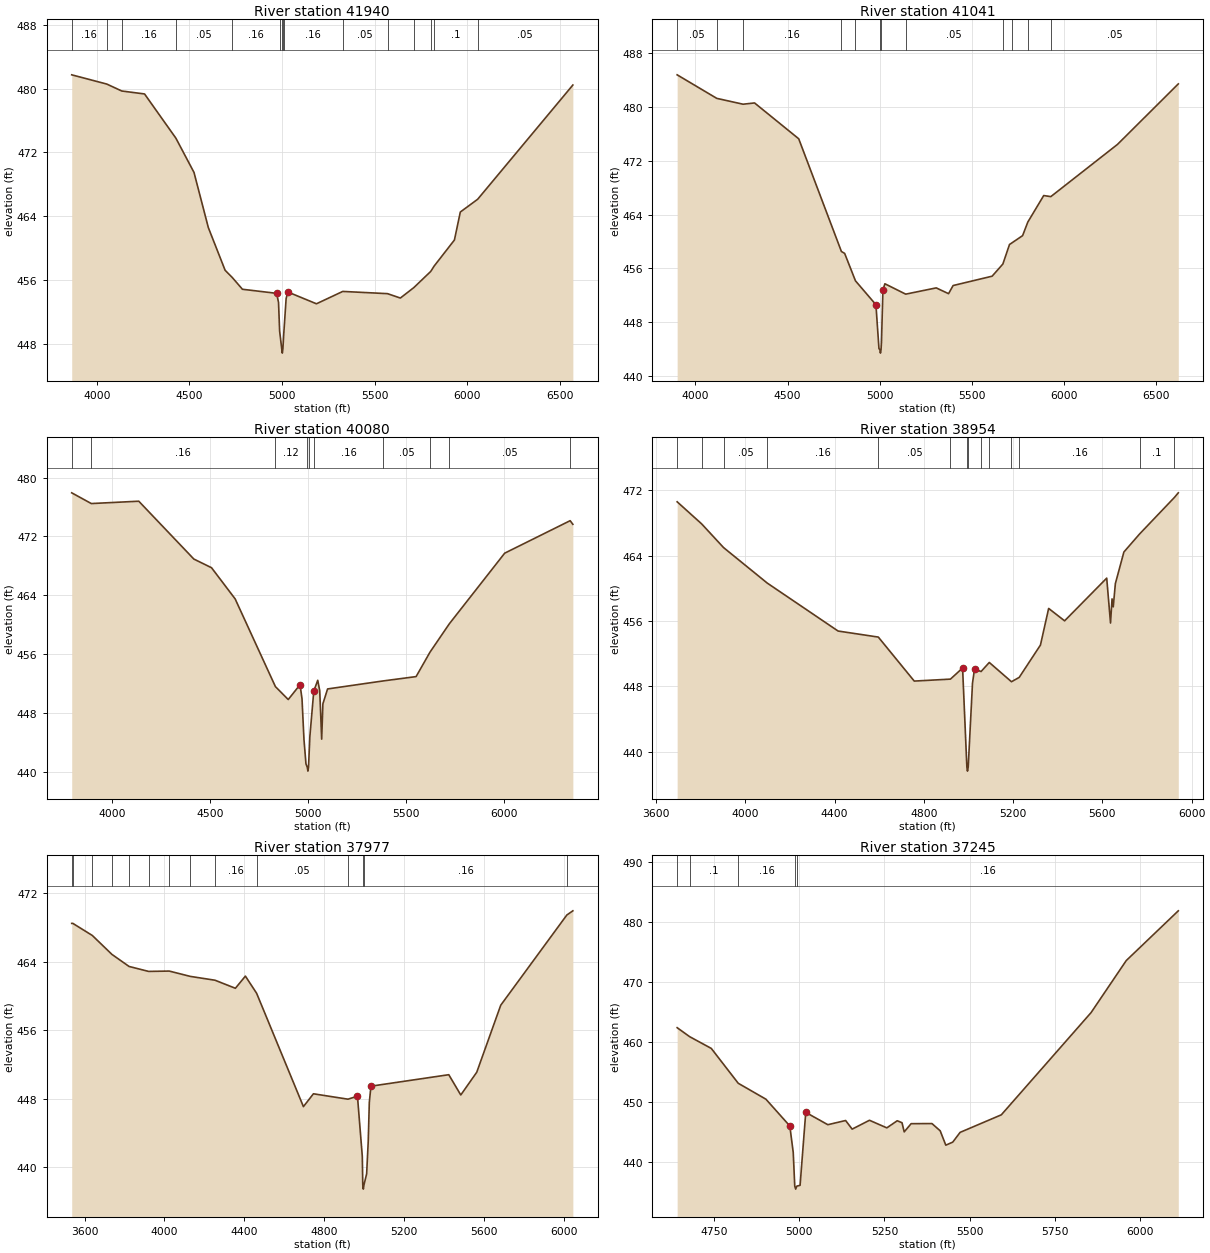
Type RM Length L Ch R = 1 ,41940   ,899,899,899
BEGIN DESCRIPTION:
PERRY CREEK 55.0
END DESCRIPTION:
XS GIS Cut Line= 5
      3521476.73     10568039.25      3521073.93      10567053.1
      3521143.38      10566740.6       3521201.6     10566361.29
      3520742.09     10565541.61
#Sta/Elev= 30
  3863.4  481.74    4053  480.58    4134  479.71  4257.1  479.34  4426.6  473.79
  4524.3   469.5  4601.8  462.58  4692.6  457.22  4731.1  456.32  4786.2  454.84
  4971.1  454.33  4981.3  453.18  4987.2   449.6  4998.8  447.33  5001.6  446.83
  5004.8  447.33  5008.4  448.86  5022.3  453.67  5031.5   454.5  5186.2  453.02
  5328.5  454.57  5570.3  454.29  5639.8  453.74  5712.6  455.05  5804.1  457.08
  5822.1  457.74    5932  461.02  5963.9  464.53  6057.6  466.13  6572.2  480.46
#Mann= 15 ,-1 , 0
  3863.4     .16       0    4053     .05       0    4134     .16       0
  4426.6     .05       0  4731.1     .16       0  4987.2     .12       0
  4998.8     .07       0  5004.8     .12       0  5008.4     .16       0
  5328.5     .05       0  5570.3     .16       0  5712.6     .05       0
  5804.1     .16       0  5822.1      .1       0  6057.6     .05       0
Bank Sta=4971.1,5031.5
XS Rating Curve= 0 ,0
Exp/Cntr=0.3,0.1

Type RM Length L Ch R = 1 ,41041   ,961,961,961
BEGIN DESCRIPTION:
PERRY CREEK 53.0
END DESCRIPTION:
XS GIS Cut Line= 3
      3522032.25     10567733.62      3521476.71     10566282.26
      3520792.12     10565341.66
#Sta/Elev= 30
  3901.1  484.78  4115.9  481.28  4258.6  480.41  4320.8   480.6  4560.3  475.27
  4791.8  458.51  4809.3  458.23    4868  454.15  4978.9   450.6  4995.4  444.08
  5000.6   443.9  5003.4   443.4  5006.6   443.9    5009  445.04  5016.8  452.74
  5027.5  453.71  5140.4  452.17  5305.9   453.1  5372.8  452.24  5397.5  453.45
    5609  454.84  5667.3  456.65  5703.2  459.55  5719.4  459.85  5774.3  460.87
  5802.4  462.88  5888.8  466.83  5927.3  466.67    6289  474.44  6618.5  483.43
#Mann= 12 ,-1 , 0
  3901.1     .05       0  4115.9     .12       0  4258.6     .16       0
  4791.8     .12       0    4868     .16       0  5000.6     .07       0
  5006.6     .16       0  5140.4     .05       0  5667.3     .16       0
  5719.4      .1       0  5802.4     .16       0  5927.3     .05       0
Bank Sta=4978.9,5016.8
XS Rating Curve= 0 ,0
Exp/Cntr=0.3,0.1

Type RM Length L Ch R = 1 ,40080   ,1126,1126,1126
BEGIN DESCRIPTION:
PERRY CREEK 52.0
END DESCRIPTION:
XS GIS Cut Line= 3
      3522393.38     10567372.55      3522268.38     10565712.82
      3522344.65     10564825.32
#Sta/Elev= 30
  3794.1  477.93    3894  476.47    4136  476.79  4416.8  468.92    4507  467.74
  4627.4   463.5  4832.6  451.57  4898.1  449.81  4958.3  451.83  4968.3  449.92
  4978.3  444.38  4988.4  441.07  4995.4  440.57  4998.2  440.07  5001.4  440.57
  5008.4   444.8  5028.5  451.01  5029.9  451.07  5048.5  452.43  5058.6  451.02
  5068.6  444.42  5074.8  449.23  5098.7  451.25  5382.2  452.34    5550  452.93
    5621  456.26  5719.1   460.1  6001.7  469.72  6335.5  474.14  6349.3  473.65
#Mann= 10 ,-1 , 0
  3794.1     .05       0    3894     .16       0  4832.6     .12       0
  4995.4     .07       0  5001.4     .12       0  5029.9     .16       0
  5382.2     .05       0    5621     .16       0  5719.1     .05       0
  6335.5      .1       0
Bank Sta=4958.3,5028.5
XS Rating Curve= 0 ,0
Exp/Cntr=0.3,0.1

Type RM Length L Ch R = 1 ,38954   ,977,977,977
BEGIN DESCRIPTION:
PERRY CREEK 50.0
END DESCRIPTION:
XS GIS Cut Line= 4
      3523143.38     10566969.73      3523254.49     10565768.38
      3523040.26     10565658.82      3522733.67      10564921.2
#Sta/Elev= 30
  3694.3   470.6  3803.9   467.9    3902     465  4098.3  460.64  4415.5  454.77
  4595.8  454.03  4756.9  448.64  4919.1  448.88  4973.5  450.24  4992.7  438.11
  4995.4  437.61  4998.7  438.11  5017.9  448.38    5027  450.13  5056.2  449.81
  5093.2  450.92  5192.6  448.56  5227.1  449.09  5322.4  453.05  5359.2  457.54
  5430.7  456.02  5619.4  461.25  5636.5  455.75  5643.3  458.71  5648.7  457.73
  5658.2  460.58  5696.4  464.45  5767.1  466.67    5923  471.14  5940.2   471.7
#Mann= 14 ,-1 , 0
  3694.3     .05       0  3803.9     .16       0    3902     .05       0
  4098.3     .16       0  4595.8     .05       0  4919.1     .12       0
  4992.7     .07       0  4998.7     .12       0  5056.2     .05       0
  5093.2     .12       0  5192.6     .05       0  5227.1     .16       0
  5767.1      .1       0    5923     .05       0
Bank Sta=4973.5,5027
XS Rating Curve= 0 ,0
Exp/Cntr=0.3,0.1

Type RM Length L Ch R = 1 ,37977   ,732,732,732
BEGIN DESCRIPTION:
PERRY CREEK 48.0
END DESCRIPTION:
XS GIS Cut Line= 4
       3523303.1     10566969.74      3523368.62     10565723.49
      3523511.43      10565365.6      3523518.38     10564490.64
#Sta/Elev= 30
  3535.7   468.5  3540.8  468.51  3638.8  467.09  3736.9  464.88  3822.7  463.47
  3920.5  462.89  4023.9  462.93  4128.9  462.31    4253  461.86  4354.9  460.92
    4405  462.34  4461.3  460.33  4695.4  447.09  4745.5  448.59  4918.2  447.96
  4965.9  448.31  4990.1  441.28  4992.5  437.95  4995.3  437.45  4998.5  437.95
  5011.8  439.23  5019.8  443.02  5025.2  447.57  5033.3  449.48    5423  450.82
    5483  448.45    5563  451.11    5683  458.94  6013.8  469.48    6044  469.97
#Mann= 14 ,-1 , 0
  3535.7     .12       0  3540.8     .05       0  3638.8     .16       0
  3736.9     .05       0  3822.7     .16       0  3920.5     .05       0
  4023.9     .16       0  4128.9     .05       0    4253     .16       0
  4461.3     .05       0  4918.2     .16       0  4992.5     .07       0
  4998.5     .16       0  6013.8     .05       0
Bank Sta=4965.9,5033.3
XS Rating Curve= 0 ,0
Exp/Cntr=0.3,0.1

Type RM Length L Ch R = 1 ,37245   ,822,822,822
BEGIN DESCRIPTION:
PERRY CREEK 46.0
END DESCRIPTION:
XS GIS Cut Line= 3
      3524042.11     10565991.61      3524042.11     10565641.64
      3523842.11     10564541.65
#Sta/Elev= 30
  4642.8  462.39  4679.5  460.89  4742.8  458.93  4821.7  453.11  4902.8  450.45
  4972.8  445.98  4982.8  441.58  4987.3  435.93    4990  435.43  4993.3  435.93
  5002.9  436.06  5019.5  448.25  5084.2  446.19  5136.3  446.89  5155.4  445.45
  5206.2  446.93    5257  445.66  5287.5  446.85  5301.5  446.52  5307.9  444.99
  5328.2  446.36  5389.2  446.38  5413.3  445.17  5429.8  442.77  5450.1  443.28
  5471.7  444.91  5592.4  447.84  5855.4  464.92  5958.3   473.6  6110.8  481.91
#Mann= 5 ,-1 , 0
  4642.8     .16       0  4679.5      .1       0  4821.7     .16       0
  4987.3     .07       0  4993.3     .16       0
Bank Sta=4972.8,5019.5
XS Rating Curve= 0 ,0
Exp/Cntr=0.3,0.1