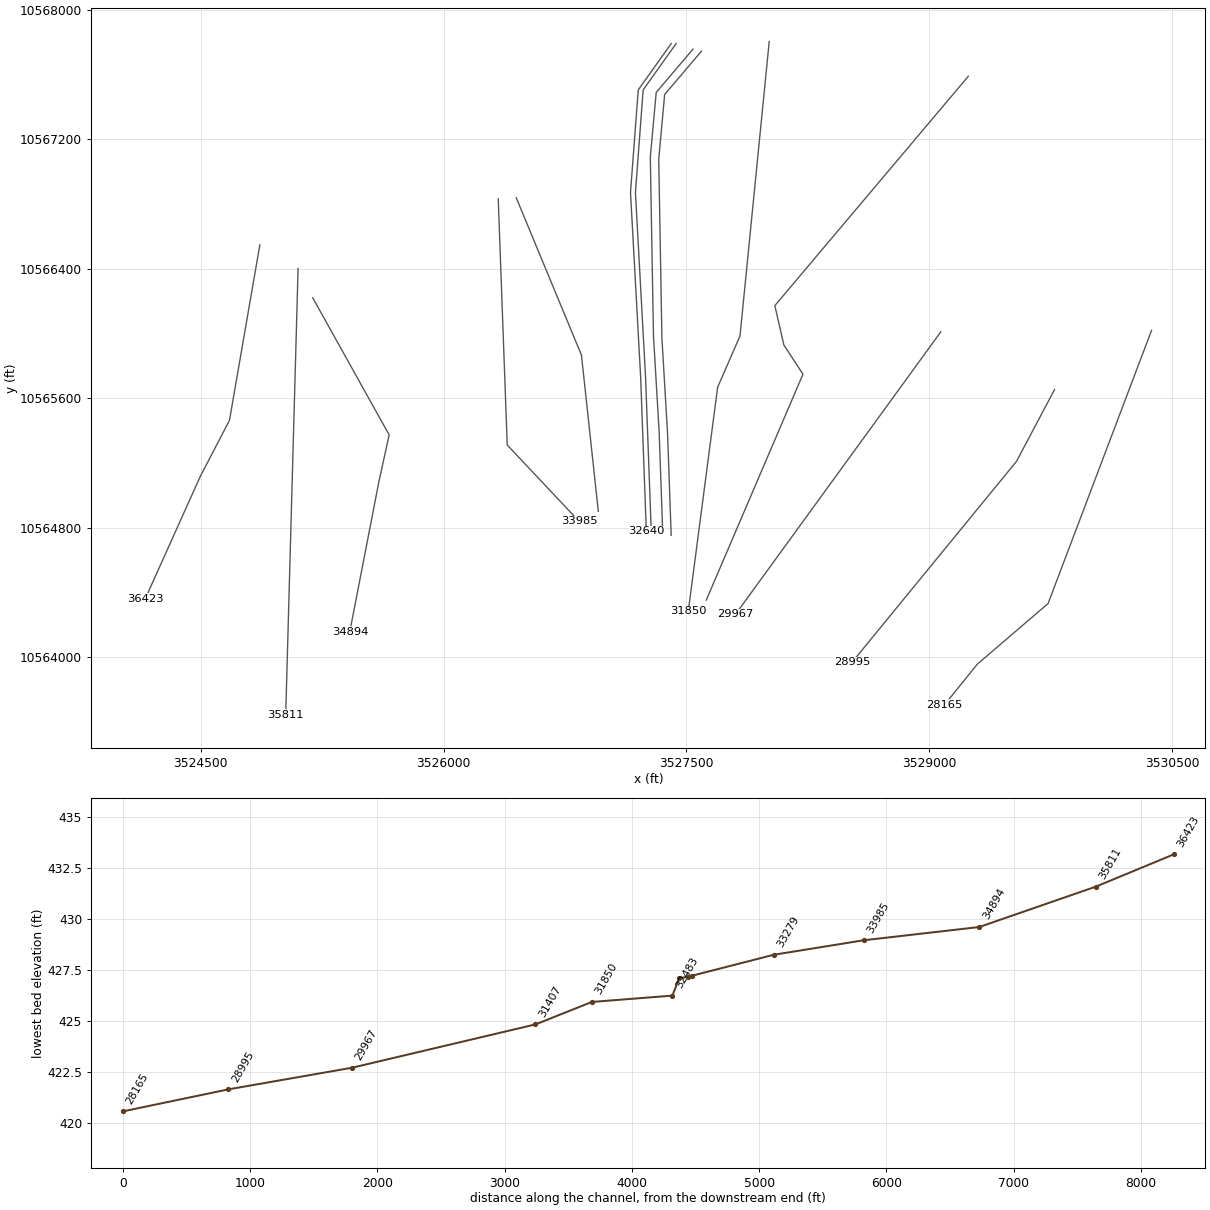
HEC-RAS study PERRY CREEK.prj: PERRY CREEK Base Level Engineering

--- PERRY CREEK.g01 (geometry) --- (continued)

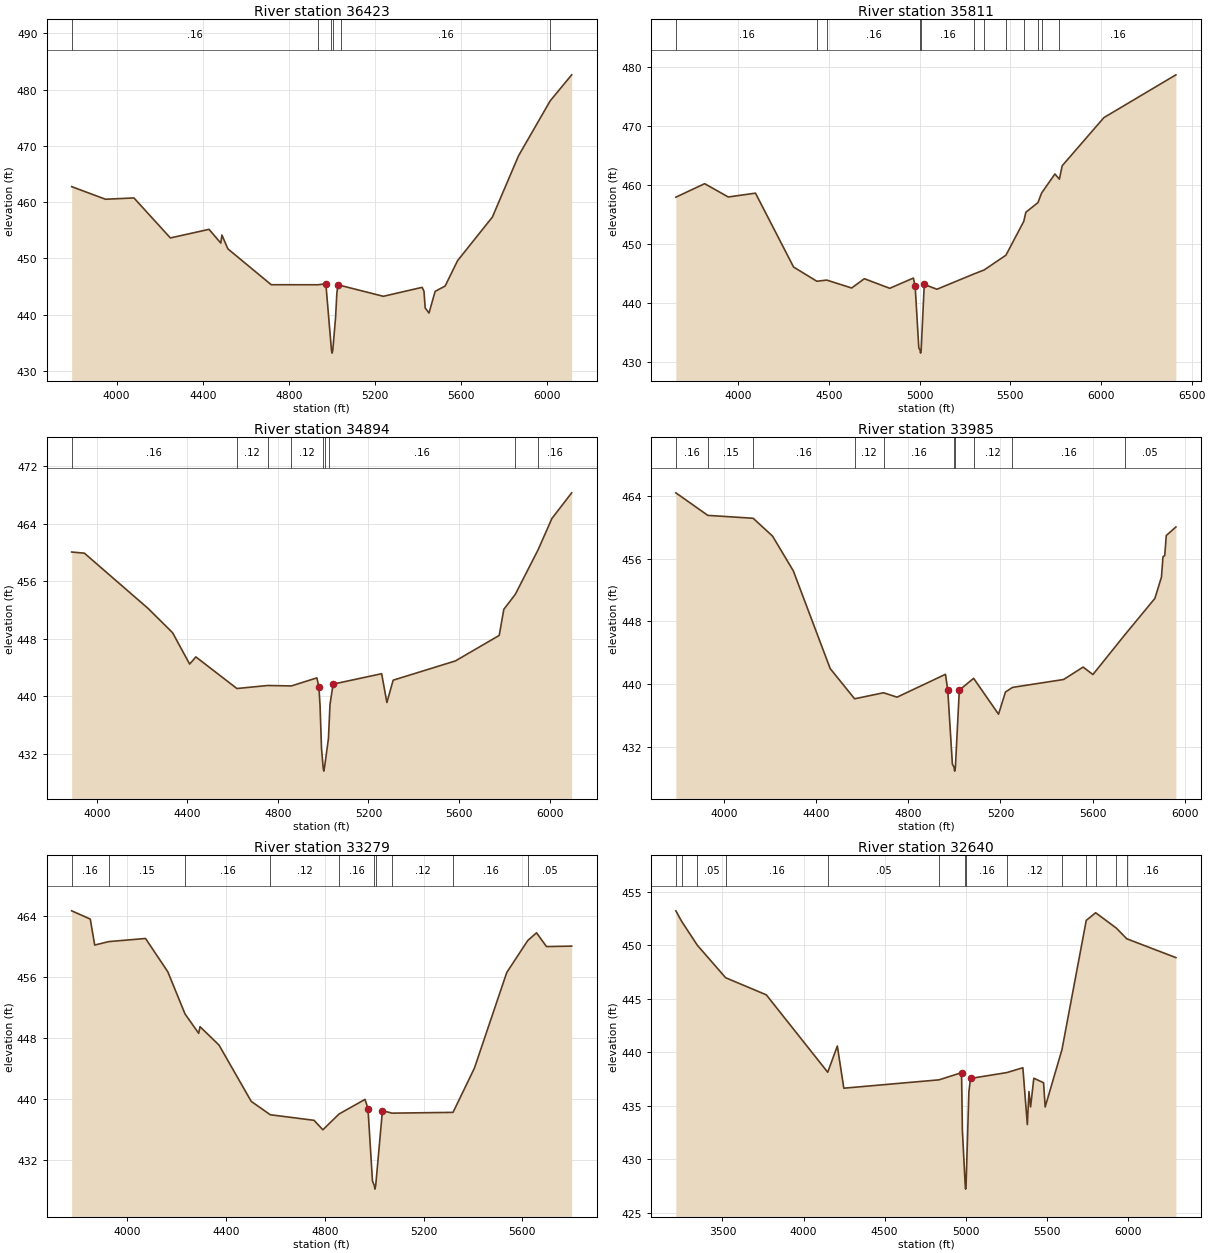
Type RM Length L Ch R = 1 ,36423   ,612,612,612
BEGIN DESCRIPTION:
PERRY CREEK 45.0
END DESCRIPTION:
XS GIS Cut Line= 4
       3524865.6     10566546.17       3524678.1     10565462.82
      3524497.54      10565115.6      3524157.28     10564358.68
#Sta/Elev= 30
  3791.9  462.74  3948.7   460.5    4081  460.73  4250.1  453.62  4429.4  455.15
  4484.1  452.71  4489.2  454.14    4517  451.68  4718.1  445.31  4934.4   445.3
  4971.6  445.47  4997.8  433.65  5000.6  433.15  5003.8  433.65  5016.7  439.45
  5022.9  443.93  5028.6  445.21  5040.5  445.17  5238.4  443.25  5418.6  444.84
  5427.1  444.15  5432.6  441.19  5450.3  440.27  5478.9  444.13  5525.2  445.07
  5583.1  449.59  5744.6  457.33  5865.9  468.22  6012.9  477.99  6112.6  482.61
#Mann= 6 ,-1 , 0
  3791.9     .16       0  4934.4     .12       0  4997.8     .07       0
  5003.8     .12       0  5040.5     .16       0  6012.9     .05       0
Bank Sta=4971.6,5028.6
XS Rating Curve= 0 ,0
Exp/Cntr=0.3,0.1

Type RM Length L Ch R = 1 ,35811   ,917,917,917
BEGIN DESCRIPTION:
PERRY CREEK 44.0
END DESCRIPTION:
XS GIS Cut Line= 2
      3525101.71     10566400.33      3525025.37     10563644.98
#Sta/Elev= 30
  3656.7  457.96  3815.4  460.24  3945.5  457.99  4095.6  458.64  4305.6  446.14
  4434.1  443.73  4488.2  443.93  4625.8  442.59  4695.8  444.16  4835.8  442.54
  4965.9  444.27  4975.9   442.9  4995.9  432.48  5002.9  432.07  5005.7  431.57
  5008.9  432.07  5025.9  443.19  5095.9  442.38  5299.2  444.96    5356  445.64
  5476.3  448.14  5574.5  453.86  5586.1  455.41  5652.9  457.04  5672.7  458.65
  5746.2  461.88    5771  461.01  5786.2  463.27  6016.3  471.42  6413.1  478.66
#Mann= 12 ,-1 , 0
  3656.7     .16       0  4434.1     .12       0  4488.2     .16       0
  5002.9     .07       0  5008.9     .16       0  5299.2      .1       0
    5356     .16       0  5476.3      .1       0  5574.5     .16       0
  5652.9      .1       0  5672.7     .05       0    5771     .16       0
Bank Sta=4975.9,5025.9
XS Rating Curve= 0 ,0
Exp/Cntr=0.3,0.1

Type RM Length L Ch R = 1 ,34894   ,909,909,909
BEGIN DESCRIPTION:
PERRY CREEK 43.0
END DESCRIPTION:
XS GIS Cut Line= 4
      3525192.01     10566219.73      3525664.21     10565372.54
      3525601.71     10565087.82      3525421.16     10564157.28
#Sta/Elev= 30
  3888.5  460.09  3944.7  459.93  4225.8  452.25  4334.4  448.86  4409.8  444.49
  4437.3  445.49  4618.6  441.09  4754.4  441.51  4859.5  441.45  4971.9  442.57
  4980.9  441.32  4986.1  438.65  4992.4  432.76  4999.7  430.09  5002.4  429.59
  5005.7  430.09  5023.1  434.15  5026.3  436.37  5029.9  438.86  5043.6   441.7
  5258.1  443.15  5281.3  439.14    5309  442.25    5584  444.93  5777.6  448.48
  5797.9  452.11  5848.7   454.2  5949.4   460.4  6010.4  464.76  6097.8  468.33
#Mann= 9 ,-1 , 0
  3888.5     .16       0  4618.6     .12       0  4754.4     .16       0
  4859.5     .12       0  4999.7     .07       0  5005.7     .12       0
  5026.3     .16       0  5848.7     .05       0  5949.4     .16       0
Bank Sta=4980.9,5043.6
XS Rating Curve= 0 ,0
Exp/Cntr=0.3,0.1

Type RM Length L Ch R = 1 ,33985   ,706,706,706
BEGIN DESCRIPTION:
PERRY CREEK 41.0
END DESCRIPTION:
XS GIS Cut Line= 3
      3526337.82     10566830.87      3526393.38     10565310.04
      3526837.46      10564838.2
#Sta/Elev= 30
  3791.4  464.38  3929.9  461.51  4126.8  461.14  4210.9  458.87    4301  454.45
  4461.1     442  4567.1  438.15  4692.5  438.92  4751.3  438.36  4961.4  441.27
  4971.4  439.22  4991.4  429.82  4998.4  429.44  5001.2  428.94  5004.4  429.44
  5021.4  439.25  5083.5  440.76  5191.6  436.19  5221.6  439.01    5252   439.6
  5474.1  440.61  5558.6  442.19  5601.1  441.24  5738.6  446.26  5870.2  450.94
  5898.5  453.64  5905.4  456.26  5912.7  456.37  5919.5  458.94  5961.2  460.03
#Mann= 10 ,-1 , 0
  3791.4     .16       0  3929.9     .15       0  4126.8     .16       0
  4567.1     .12       0  4692.5     .16       0  4998.4     .07       0
  5004.4     .16       0  5083.5     .12       0    5252     .16       0
  5738.6     .05       0
Bank Sta=4971.4,5021.4
XS Rating Curve= 0 ,0
Exp/Cntr=0.3,0.1

Type RM Length L Ch R = 1 ,33279   ,639,639,639
BEGIN DESCRIPTION:
PERRY CREEK 40.0
END DESCRIPTION:
XS GIS Cut Line= 3
      3526448.95     10566837.78      3526851.71      10565865.6
      3526955.88     10564900.31
#Sta/Elev= 30
  3776.2  464.67  3851.5  463.59  3869.4  460.19  3926.5  460.64  4075.1  461.05
  4165.2  456.69  4234.9  451.17  4290.1  448.63  4295.5   449.5  4372.5  447.09
  4502.8  439.72  4579.8  437.97    4757  437.24  4792.6     436  4858.3  438.07
  4963.2  439.98  4975.2  438.76  4993.4  429.27  5000.5  428.73  5003.2  428.23
  5006.5  428.73  5033.7   438.5  5072.5  438.18  5319.3  438.28  5405.8  444.07
  5536.6  456.59  5621.6  460.78  5657.2  461.79  5697.5  459.99  5799.4  460.05
#Mann= 10 ,-1 , 0
  3776.2     .16       0  3926.5     .15       0  4234.9     .16       0
  4579.8     .12       0  4858.3     .16       0  5000.5     .07       0
  5006.5     .16       0  5072.5     .12       0  5319.3     .16       0
  5621.6     .05       0
Bank Sta=4975.2,5033.7
XS Rating Curve= 0 ,0
Exp/Cntr=0.3,0.1

Type RM Length L Ch R = 1 ,32640   ,32,32,32
BEGIN DESCRIPTION:
PERRY CREEK 39.1
END DESCRIPTION:
XS GIS Cut Line= 5
      3527406.45     10567790.47      3527202.47     10567504.03
      3527154.72     10566870.35      3527217.66     10565721.81
      3527252.36     10564776.13
#Sta/Elev= 30
  3212.8  453.21    3248  452.24  3345.5  449.99  3519.8  446.96  3770.7  445.36
  4149.3  438.13  4208.6  440.58  4248.7  436.64  4835.8  437.42  4974.7  438.09
  4979.8  432.72  4996.8  427.71  4999.6  427.21  5002.8  427.71  5019.9   436.3
  5029.9  437.55  5254.4   438.1  5352.8  438.55  5380.4  433.24  5390.4  436.33
  5400.4  434.89  5420.4  437.57  5480.4  437.15  5490.4  434.89  5593.9  440.24
  5743.8  452.32  5801.9  453.03  5929.8  451.59  5993.4   450.6  6296.5  448.84
#Mann= 14 ,-1 , 0
  3212.8     .05       0    3248     .16       0  3345.5     .05       0
  3519.8     .16       0  4149.3     .05       0  4835.8     .16       0
  4996.8     .07       0  5002.8     .16       0  5254.4     .12       0
  5593.9     .16       0  5743.8     .05       0  5801.9     .16       0
  5929.8     .05       0  5993.4     .16       0
Bank Sta=4974.7,5029.9
XS Rating Curve= 0 ,0
Exp/Cntr=0.3,0.1

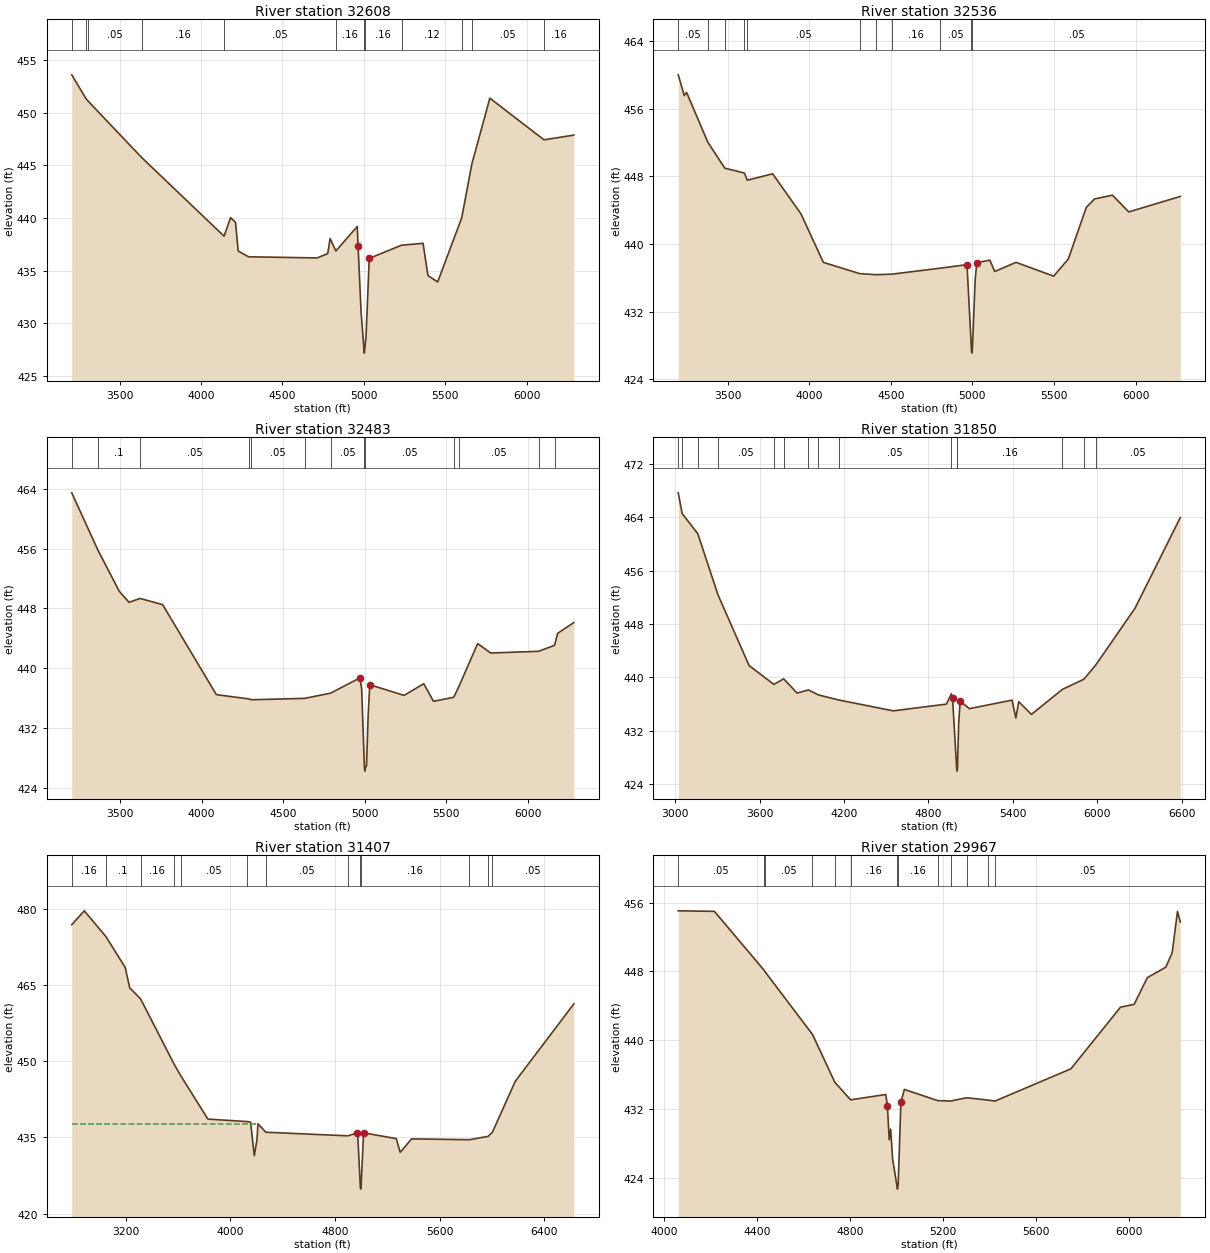
Type RM Length L Ch R = 1 ,32608   ,72,72,72
BEGIN DESCRIPTION:
PERRY CREEK 39.0
END DESCRIPTION:
XS GIS Cut Line= 5
      3527436.83     10567790.47      3527232.85     10567504.03
       3527185.1     10566870.35      3527248.04     10565721.81
      3527282.74     10564776.13
#Sta/Elev= 30
  3206.3  453.61  3291.1  451.41    3305  451.14  3634.7  445.76  4141.6  438.27
  4182.1  440.03  4212.2  439.58  4228.6  436.85  4292.3  436.31  4712.9   436.2
  4778.2  436.61    4793  438.04  4828.1  436.86  4959.7  439.19  4964.7  437.35
  4983.3  431.05  5000.3  427.65  5003.1  427.15  5006.3  427.65  5013.4   428.6
  5033.4  436.16  5231.5  437.41  5363.9  437.59  5393.9  434.52  5453.9  433.92
  5601.4  440.02  5663.9  445.15  5774.1  451.39  6106.9  447.43    6290  447.88
#Mann= 12 ,-1 , 0
  3206.3     .05       0  3291.1     .16       0    3305     .05       0
  3634.7     .16       0  4141.6     .05       0  4828.1     .16       0
  5000.3     .07       0  5006.3     .16       0  5231.5     .12       0
  5601.4     .16       0  5663.9     .05       0  6106.9     .16       0
Bank Sta=4964.7,5033.4
XS Rating Curve= 0 ,0
Exp/Cntr=0.3,0.1

Type RM Length L Ch R = 1 ,32536   ,53,53,53
BEGIN DESCRIPTION:
PERRY CREEK 38.0
END DESCRIPTION:
XS GIS Cut Line= 6
      3527540.52     10567755.74      3527313.45     10567488.17
      3527276.99     10567088.43      3527296.52     10565984.26
      3527331.68     10565389.21      3527353.79     10564766.07
#Sta/Elev= 30
  3197.5  460.01  3234.7  457.55    3249  457.92  3378.2  452.06  3482.5  448.97
    3603  448.39  3620.9  447.54  3775.9   448.3  3949.2  443.57  4086.6  437.82
  4308.7  436.49  4406.7  436.36  4504.8  436.42  4798.9  437.12  4966.8  437.55
  4993.8  427.58  4996.5  427.08  4999.8  427.58  5016.8  435.74  5026.8  437.78
  5106.9  438.08  5136.9  436.74  5267.2  437.82  5497.6  436.19  5587.7  438.22
  5697.9  444.33  5747.9  445.32    5858  445.77    5958  443.79  6273.8  445.62
#Mann= 11 ,-1 , 0
  3197.5     .05       0  3378.2      .1       0  3482.5     .05       0
    3603      .1       0  3620.9     .05       0  4308.7     .16       0
  4406.7     .05       0  4504.8     .16       0  4798.9     .05       0
  4993.8     .04       0  4999.8     .05       0
Bank Sta=4966.8,5026.8
XS Rating Curve= 0 ,0
Exp/Cntr=0.3,0.1

Type RM Length L Ch R = 1 ,32483   ,633,633,633
BEGIN DESCRIPTION:
PERRY CREEK 38.1
END DESCRIPTION:
XS GIS Cut Line= 6
       3527592.6     10567742.71      3527365.53     10567475.15
      3527329.07     10567075.41       3527348.6     10565971.24
      3527383.76     10565376.19      3527405.89     10564752.53
#Sta/Elev= 30
  3204.1  463.46  3364.3   455.8  3495.7  450.27    3555  448.81  3622.8  449.33
  3761.1   448.5  4090.2  436.46  4289.9  435.89  4305.3  435.78  4630.6  435.96
  4790.4  436.66  4970.3  438.71  4980.7  437.21  4997.4  426.73  5000.1  426.23
  5003.4  426.73  5010.4  426.92  5020.4  433.74  5030.4  437.79  5240.7  436.36
  5360.9  437.92    5421  435.57  5544.9  436.11  5574.7  437.46  5691.4  443.29
  5771.5  442.03  6064.8  442.26  6162.8  443.06  6181.7  444.66  6280.9  446.11
#Mann= 13 ,-1 , 0
  3204.1     .05       0  3364.3      .1       0  3622.8     .05       0
  4289.9     .16       0  4305.3     .05       0  4630.6     .16       0
  4790.4     .05       0  4997.4     .04       0  5003.4     .05       0
  5544.9      .1       0  5574.7     .05       0  6064.8      .1       0
  6162.8     .05       0
Bank Sta=4970.3,5030.4
XS Rating Curve= 0 ,0
Exp/Cntr=0.3,0.1

Type RM Length L Ch R = 1 ,31850   ,443,443,443
BEGIN DESCRIPTION:
PERRY CREEK 37.0
END DESCRIPTION:
XS GIS Cut Line= 4
      3528011.43     10567803.08      3527830.88     10565983.65
       3527692.8     10565667.08      3527511.43     10564282.25
#Sta/Elev= 30
  3020.5  467.66  3048.3  464.56  3159.4  461.54  3302.9  452.38  3524.4  441.75
  3700.6  438.93  3770.3  439.76  3866.1  437.62  3946.3   438.1  4017.4  437.35
  4163.5  436.58  4549.4  434.96  4927.4  435.97  4963.2  437.52  4971.1  436.92
  5000.4  426.42  5003.1  425.92  5006.4  426.42  5014.7  433.05  5025.6  436.41
  5091.1  435.29  5394.3  436.57  5421.6  433.88  5441.8  436.33  5532.5  434.43
  5752.4  438.18  5904.9   439.7  5990.1  441.85  6268.8  450.35  6590.9  463.95
#Mann= 15 ,-1 , 0
  3020.5      .1       0  3048.3     .05       0  3159.4      .1       0
  3302.9     .05       0  3700.6      .1       0  3770.3     .16       0
  3946.3     .05       0  4017.4     .16       0  4163.5     .05       0
  4963.2     .16       0  5000.4     .07       0  5006.4     .16       0
  5752.4     .05       0  5904.9      .1       0  5990.1     .05       0
Bank Sta=4971.1,5025.6
XS Rating Curve= 0 ,0
Exp/Cntr=0.3,0.1

Type RM Length L Ch R = 1 ,31407   ,1440,1440,1440
BEGIN DESCRIPTION:
PERRY CREEK 37.1
END DESCRIPTION:
XS GIS Cut Line= 5
       3529240.6     10567587.83      3528046.16     10566171.15
      3528101.71      10565928.1      3528219.77     10565747.54
      3527622.54     10564351.71
#Sta/Elev= 30
  2788.5  476.92  2884.3  479.65  3048.7   474.6  3196.4  468.52  3231.5  464.46
  3314.2  462.31  3570.3  449.45  3621.2  447.17  3828.4  438.62  4130.8  438.12
  4154.7  438.02  4183.1  431.41  4204.2  434.67  4210.7  437.68  4271.7  436.03
  4898.2  435.32    4969   435.9    4975  434.85  4993.1  425.32  4995.8  424.82
  4999.1  425.32    5018  435.91  5268.3  434.77  5297.9  432.06  5384.9  434.72
  5825.3  434.55  5969.6  435.21  6002.6  436.03  6177.3  446.07  6624.8  461.32
#Mann= 13 ,-1 , 0
  2788.5     .16       0  3048.7      .1       0  3314.2     .16       0
  3570.3     .12       0  3621.2     .05       0  4130.8     .16       0
  4271.7     .05       0  4898.2     .16       0  4993.1     .07       0
  4999.1     .16       0  5825.3     .05       0  5969.6      .1       0
  6002.6     .05       0
#XS Ineff= 2 , 0
         4210.56   437.7
Permanent Ineff=
       F       F
Bank Sta=4969,5018
XS Rating Curve= 0 ,0
Exp/Cntr=0.3,0.1

Type RM Length L Ch R = 1 ,29967   ,972,972,972
BEGIN DESCRIPTION:
PERRY CREEK 36.0
END DESCRIPTION:
XS GIS Cut Line= 2
      3529070.88     10566008.99      3527802.66     10564263.34
#Sta/Elev= 30
  4062.5  455.05  4217.9  454.99  4429.8   448.2  4433.3  448.05  4639.5  440.68
  4735.5  435.12  4803.2  433.08  4954.5   433.7  4961.5  432.35  4969.2  428.44
  4975.4  429.68  4983.9  426.19  5001.7   423.2  5004.5   422.7  5007.7   423.2
  5019.4  432.78  5034.1  434.29  5177.6  432.99  5232.8  432.94  5302.5  433.32
  5392.4  433.05  5424.2  432.94  5749.8  436.68  5963.2  443.85  6021.9  444.18
  6078.3  447.28    6158   448.5  6185.2  450.18  6208.2  454.99  6220.2  453.76
#Mann= 13 ,-1 , 0
  4062.5     .05       0  4429.8     .16       0  4433.3     .05       0
  4639.5     .16       0  4735.5     .05       0  4803.2     .16       0
  5001.7     .07       0  5007.7     .16       0  5177.6     .12       0
  5232.8     .16       0  5302.5     .12       0  5392.4     .16       0
  5424.2     .05       0
Bank Sta=4961.5,5019.4
XS Rating Curve= 0 ,0
Exp/Cntr=0.3,0.1

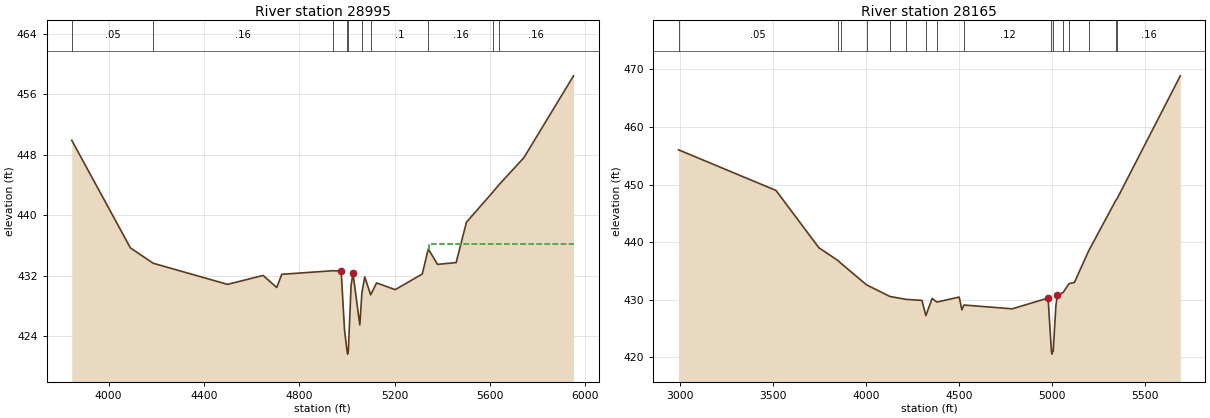
Type RM Length L Ch R = 1 ,28995   ,830,830,830
BEGIN DESCRIPTION:
PERRY CREEK 34.0
END DESCRIPTION:
XS GIS Cut Line= 3
      3529773.15     10565652.23      3529538.77     10565209.52
      3528523.14     10563968.19
#Sta/Elev= 30
  3845.1   449.9  4091.1  435.68  4186.7  433.65  4498.3  430.86  4647.8  432.04
  4705.1  430.44    4726  432.19  4940.4  432.66  4975.1  432.63  4989.3  424.83
  4999.4  422.14  5002.2  421.64  5005.4  422.14  5016.8   430.7  5024.7  432.35
  5053.4  425.49  5062.2  429.78  5074.2  431.85  5098.9  429.47  5123.7  431.05
    5202  430.16  5315.4  432.23  5340.7  435.55  5379.3   433.5  5457.5  433.74
  5500.6  439.07  5611.8  443.07  5637.6  444.04  5741.8  447.61  5949.9  458.42
#Mann= 10 ,-1 , 0
  3845.1     .05       0  4186.7     .16       0  4940.4     .12       0
  4999.4     .07       0  5005.4     .12       0  5062.2     .16       0
  5098.9      .1       0  5340.7     .16       0  5611.8      .1       0
  5637.6     .16       0
#XS Ineff= 2 , 0
                         5344.56          436.14
Permanent Ineff=
       F       F
Bank Sta=4975.1,5024.7
XS Rating Curve= 0 ,0
Exp/Cntr=0.3,0.1

Type RM Length L Ch R = 1 ,28165   ,658,658,658
BEGIN DESCRIPTION:
PERRY CREEK 33.0
END DESCRIPTION:
XS GIS Cut Line= 4
      3530372.54     10566018.36      3529733.66     10564330.88
      3529296.16     10563955.88      3529094.78     10563705.89
#Sta/Elev= 30
  2990.8  456.05  3515.5  448.99  3746.5  439.04  3848.1  436.84  3865.2  436.34
  4002.8   432.6  4128.5  430.58  4215.8  430.07  4301.2   429.9  4322.3  427.25
    4356  430.23  4381.4   429.6  4501.7  430.47  4516.3  428.25  4527.5  429.09
  4787.2  428.43  4980.5   430.3  4998.4  421.06  5001.2  420.56  5004.4  421.06
    5008  421.09  5022.3   428.9  5029.9  430.77  5061.3  431.27    5093   432.8
  5122.1  433.01  5199.5  438.53    5345  447.26  5351.8  447.55  5692.4   468.9
#Mann= 16 ,-1 , 0
  2990.8     .05       0  3848.1     .16       0  3865.2     .05       0
  4002.8     .16       0  4128.5     .05       0  4215.8     .16       0
  4322.3     .12       0  4381.4     .16       0  4527.5     .12       0
  4998.4     .07       0  5004.4     .12       0  5061.3     .16       0
    5093     .12       0  5199.5     .16       0    5345      .1       0
  5351.8     .16       0
Bank Sta=4980.5,5029.9
XS Rating Curve= 0 ,0
Exp/Cntr=0.3,0.1