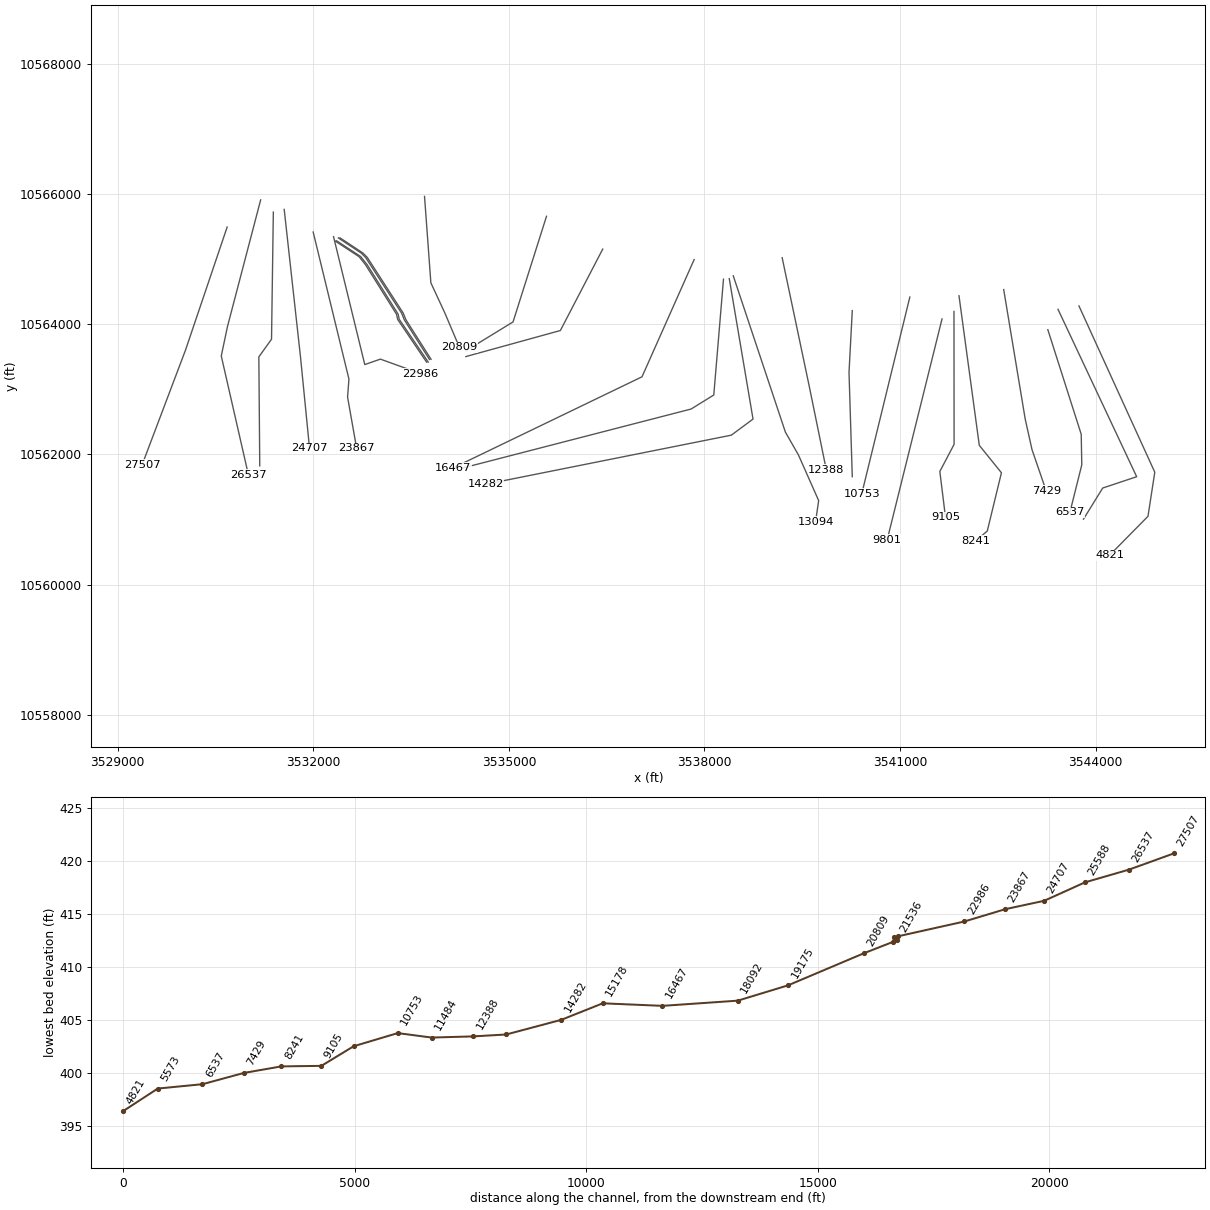
HEC-RAS study PERRY CREEK.prj: PERRY CREEK Base Level Engineering

--- PERRY CREEK.g01 (geometry) --- (continued)

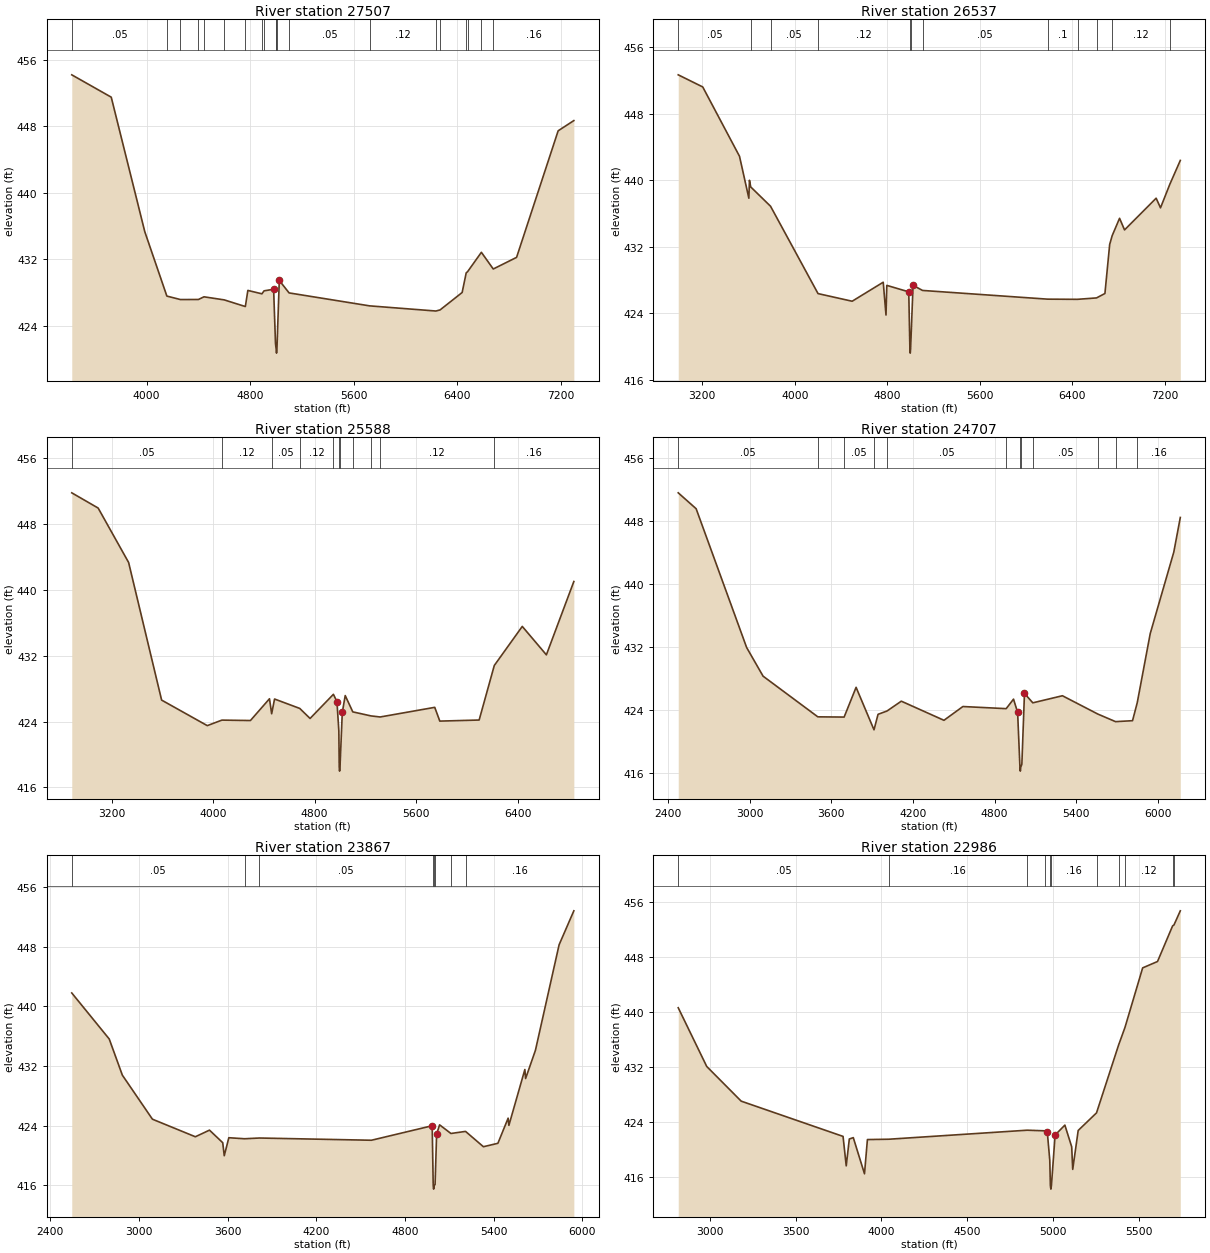
Type RM Length L Ch R = 1 ,27507   ,970,970,970
BEGIN DESCRIPTION:
PERRY CREEK 32.0
END DESCRIPTION:
XS GIS Cut Line= 3
      3530678.09     10565490.58      3530039.21     10563601.71
      3529372.53     10561837.78
#Sta/Elev= 30
  3422.1  454.22  3727.1  451.53  3986.4  435.33  4156.9  427.58  4261.8  427.16
    4401  427.17  4443.9  427.49  4600.3  427.12  4763.4  426.32  4782.8  428.26
  4891.6  427.85  4908.1  428.21  4981.9   428.4  4996.5  421.82  5001.5  421.21
  5004.2  420.71  5007.5  421.21  5025.6  429.46  5101.5  427.96  5724.1   426.4
  6235.6  425.78    6268  425.91  6438.7  428.01  6469.9  430.37  6480.9  430.52
  6587.3  432.85  6679.1  430.84  6859.3  432.24  7180.6  447.48  7301.8  448.71
#Mann= 20 ,-1 , 0
  3422.1     .05       0  4156.9     .16       0  4261.8     .12       0
    4401     .16       0  4443.9     .12       0  4600.3     .16       0
  4763.4     .12       0  4891.6     .16       0  4908.1     .12       0
  4996.5     .16       0  5001.5     .07       0  5007.5     .16       0
  5101.5     .05       0  5724.1     .12       0  6235.6     .16       0
    6268     .12       0  6469.9      .1       0  6480.9     .16       0
  6587.3     .12       0  6679.1     .16       0
Bank Sta=4981.9,5025.6
XS Rating Curve= 0 ,0
Exp/Cntr=0.3,0.1

Type RM Length L Ch R = 1 ,26537   ,949,949,949
BEGIN DESCRIPTION:
PERRY CREEK 31.0
END DESCRIPTION:
XS GIS Cut Line= 4
      3531191.99     10565907.26      3530683.17     10563964.17
      3530587.82     10563511.43      3531004.31     10561685.81
#Sta/Elev= 30
  2991.4   452.7  3203.4  451.24  3521.5  442.89  3602.4  437.84  3607.5     440
  3618.4   439.2  3790.1  436.87  4200.9  426.35  4496.1  425.43  4764.9  427.72
  4788.9  423.77  4795.9  427.34  4985.8  426.56  4995.7  419.68  4998.5  419.18
  5001.7  419.68    5023  427.35  5104.9  426.73  6187.8  425.68  6445.9  425.66
  6610.2  425.83    6683  426.36  6724.1  432.27  6745.8  433.33  6809.7  435.42
  6852.7  434.02  7126.1  437.84  7163.9  436.68  7243.7  439.49  7335.2  442.39
#Mann= 12 ,-1 , 0
  2991.4     .05       0  3618.4     .16       0  3790.1     .05       0
  4200.9     .12       0  4995.7     .07       0  5001.7     .12       0
  5104.9     .05       0  6187.8      .1       0  6445.9     .12       0
  6610.2     .16       0  6745.8     .12       0  7243.7     .16       0
Bank Sta=4985.8,5023
XS Rating Curve= 0 ,0
Exp/Cntr=0.3,0.1

Type RM Length L Ch R = 1 ,25588   ,881,881,881
BEGIN DESCRIPTION:
PERRY CREEK 30.0
END DESCRIPTION:
XS GIS Cut Line= 4
      3531386.43     10565719.75      3531358.66     10563768.38
      3531164.21     10563497.54      3531178.09     10561825.27
#Sta/Elev= 30
  2885.5  451.75  3093.6   449.9  3333.6   443.3  3593.7   426.6  3953.7   423.5
  4068.8  424.17  4293.7  424.12  4443.8  426.76  4461.1  424.94  4483.8  426.73
  4682.3  425.59  4763.8  424.37  4947.7   427.3  4975.8  426.41  4990.5  422.87
  4993.6  418.48  4996.4  417.98  4999.6  418.48  5017.7   425.1  5040.8  427.15
  5100.5  425.17    5244  424.68  5316.3  424.55  5746.4  425.72  5786.4  424.05
  6096.4  424.18  6215.8   430.8  6436.4  435.54  6626.4  432.09  6842.8  440.99
#Mann= 11 ,-1 , 0
  2885.5     .05       0  4068.8     .12       0  4461.1     .05       0
  4682.3     .12       0  4947.7     .16       0  4993.6     .07       0
  4999.6     .16       0  5100.5     .05       0    5244     .16       0
  5316.3     .12       0  6215.8     .16       0
Bank Sta=4975.8,5017.7
XS Rating Curve= 0 ,0
Exp/Cntr=0.3,0.1

Type RM Length L Ch R = 1 ,24707   ,840,840,840
BEGIN DESCRIPTION:
PERRY CREEK 29.0
END DESCRIPTION:
XS GIS Cut Line= 3
       3531553.1     10565761.44       3531803.1     10563497.54
       3531942.1     10562091.66
#Sta/Elev= 30
  2474.9  451.61  2606.5  449.59  2977.7  431.95  3098.5  428.31  3500.9  423.14
  3694.3  423.11  3782.2  426.89  3913.9  421.49  3943.6  423.46  4009.4  423.88
  4114.6  425.13  4428.1   422.7  4567.3  424.45  4885.3  424.18  4939.4  425.39
  4969.5  423.71  4986.6  416.74  4989.4  416.24  4992.6  416.74  5000.6  417.11
  5019.8  426.12  5081.1  424.92  5298.8  425.82  5560.6  423.48  5689.3  422.53
  5814.1  422.65  5848.7  424.93  5944.2  433.72  6117.3  444.07  6165.3  448.48
#Mann= 12 ,-1 , 0
  2474.9     .05       0  3500.9      .1       0  3694.3     .05       0
  3913.9     .16       0  4009.4     .05       0  4885.3     .16       0
  4986.6     .07       0  4992.6     .16       0  5081.1     .05       0
  5560.6     .16       0  5689.3     .12       0  5848.7     .16       0
Bank Sta=4969.5,5019.8
XS Rating Curve= 0 ,0
Exp/Cntr=0.3,0.1

Type RM Length L Ch R = 1 ,23867   ,881,881,881
BEGIN DESCRIPTION:
PERRY CREEK 27.0
END DESCRIPTION:
XS GIS Cut Line= 4
      3531997.53     10565414.26      3532546.16     10563157.26
      3532525.32     10562879.49      3532664.04     10562095.74
#Sta/Elev= 30
  2544.9  441.82  2798.4  435.63  2887.2  430.77  3090.7  424.85  3381.2  422.49
  3476.7  423.38  3566.4  421.69  3576.7  419.94  3607.6  422.36  3713.9  422.22
  3813.9  422.32  4572.5  422.02  4983.6  423.97  4990.6  415.95  4993.4  415.45
  4996.6  415.95  5003.1  416.05  5013.6  422.84  5033.7  424.09  5110.5  422.93
  5209.3  423.21  5330.2  421.15  5428.3  421.61  5497.5  424.99  5502.6  424.02
  5610.7  431.53  5615.8  430.32  5682.2  434.11  5842.3  448.29  5942.1  452.86
#Mann= 8 ,-1 , 0
  2544.9     .05       0  3713.9      .1       0  3813.9     .05       0
  4990.6     .03       0  4996.6     .05       0  5003.1     .16       0
  5110.5      .1       0  5209.3     .16       0
Bank Sta=4983.6,5013.6
XS Rating Curve= 0 ,0
Exp/Cntr=0.3,0.1

Type RM Length L Ch R = 1 ,22986   ,1425,1425,1425
BEGIN DESCRIPTION:
PERRY CREEK 26.0
END DESCRIPTION:
XS GIS Cut Line= 4
      3532310.05       10565343.      3532789.21     10563379.49
      3533028.79     10563462.82      3533642.13     10563241.63
#Sta/Elev= 30
  2815.1  440.64  2981.2  432.11  3182.1  427.07  3775.9  421.95  3794.4  417.67
  3812.4  421.57  3835.6  421.77  3900.9  416.52  3917.9  421.49  4042.7  421.54
  4848.8  422.85  4952.1  422.76  4966.4  422.62    4981  418.48  4984.5  414.79
  4987.3  414.29  4990.5  414.79  5012.1  422.15    5069  423.59  5108.7  420.44
  5114.7  417.16  5146.6  422.81  5253.5  425.37    5382  435.21  5419.2  437.77
  5522.4  446.43  5609.1  447.36    5697  452.53  5704.8  452.66  5741.9  454.72
#Mann= 11 ,-1 , 0
  2815.1     .05       0  4042.7     .16       0  4848.8     .05       0
  4952.1     .16       0  4984.5     .07       0  4990.5     .16       0
  5253.5     .12       0    5382     .16       0  5419.2     .12       0
    5697      .1       0  5704.8     .05       0
Bank Sta=4966.4,5012.1
XS Rating Curve= 0 ,0
Exp/Cntr=0.3,0.1

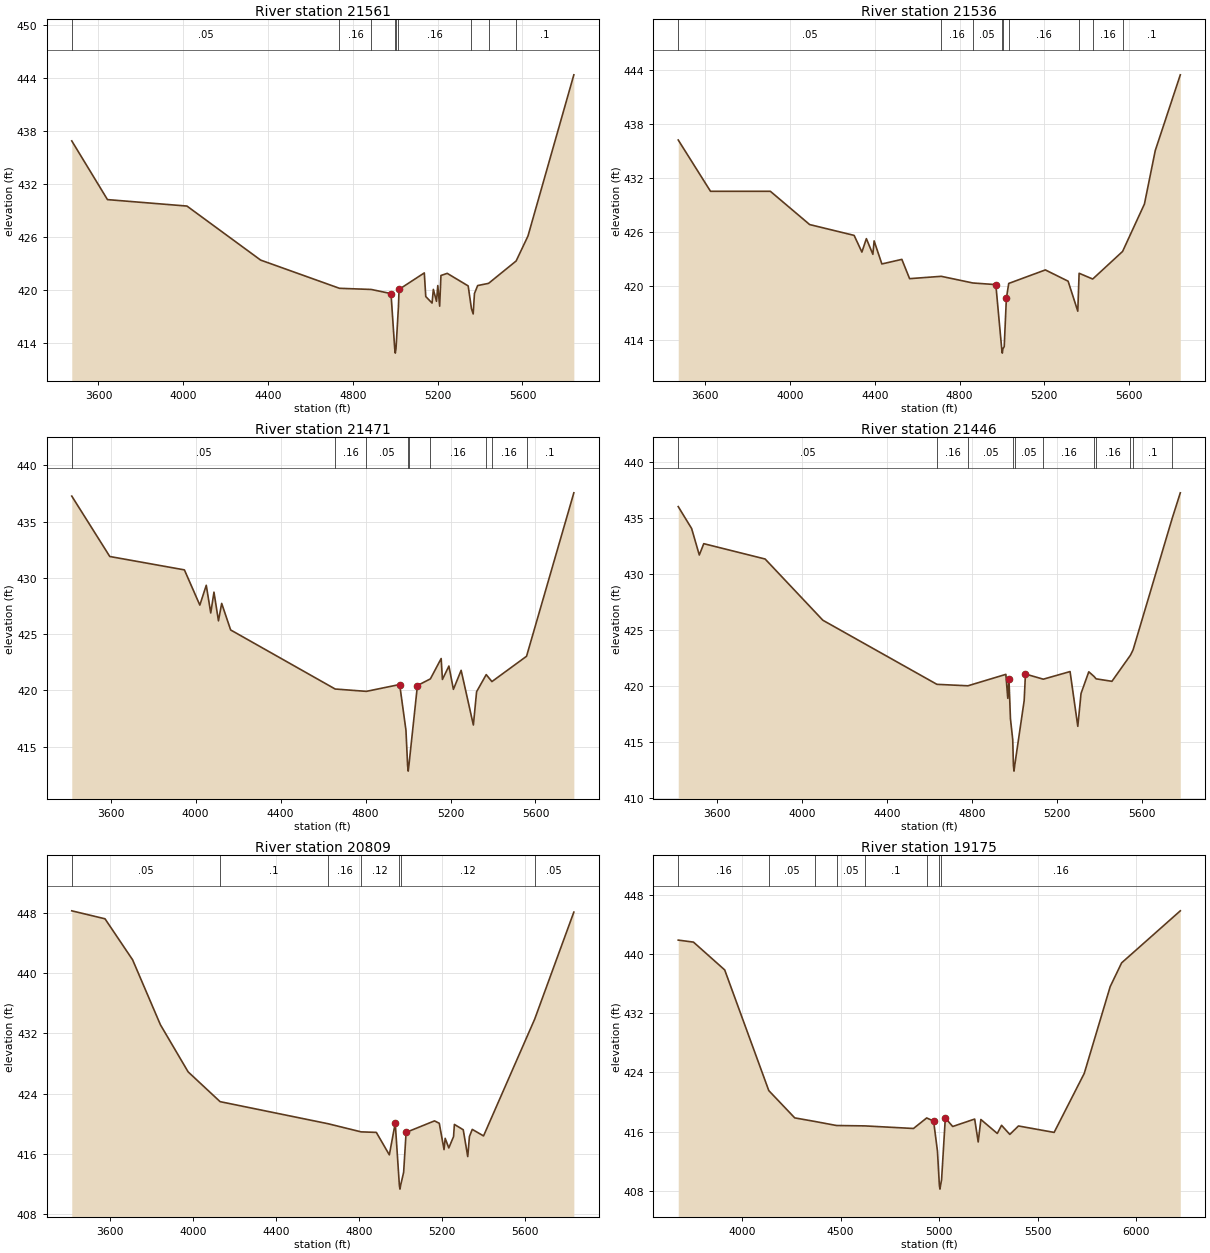
Type RM Length L Ch R = 1 ,21561   ,25,25,25
BEGIN DESCRIPTION:
PERRY CREEK 24.1
END DESCRIPTION:
XS GIS Cut Line= 6
      3532333.56     10565277.24      3532701.62     10565035.91
      3532798.84     10564914.38      3533276.27     10564152.23
      3533293.63     10564072.37      3533737.44     10563417.07
#Sta/Elev= 30
  3474.1   436.9  3642.5  430.26  4017.4  429.53  4365.1  423.42  4736.9  420.23
    4887   420.1    4980  419.63  4997.5   413.4  5000.2   412.9  5003.5   413.4
  5014.9   418.1    5018  420.11    5137  421.97  5143.9   419.3  5173.6  418.56
  5179.7  420.11  5194.5  418.76  5200.6  420.54  5209.4  418.21  5215.5  421.68
  5245.2  421.92    5344   420.5  5359.4  417.93  5367.6  417.33  5373.6  419.64
  5388.7  420.54  5440.2  420.79  5570.2  423.32    5626  426.14  5842.4  444.37
#Mann= 9 ,-1 , 0
  3474.1     .05       0  4736.9     .16       0    4887     .05       0
  4997.5     .03       0  5003.5     .05       0  5014.9     .16       0
  5359.4     .12       0  5440.2     .16       0  5570.2      .1       0
Bank Sta=4980,5018
XS Rating Curve= 0 ,0
Exp/Cntr=0.3,0.1

Type RM Length L Ch R = 1 ,21536   ,65,65,65
BEGIN DESCRIPTION:
PERRY CREEK 24.0
END DESCRIPTION:
XS GIS Cut Line= 6
       3532357.9     10565278.94      3532725.93     10565037.65
      3532823.15     10564916.12      3533300.58     10564153.97
      3533317.94     10564074.11      3533762.39     10563417.85
#Sta/Elev= 30
  3472.5  436.22  3624.8  430.53  3907.3  430.53  4092.8  426.84  4302.6  425.64
  4339.2  423.79  4360.4  425.28    4391  423.54  4396.9  425.03  4433.5  422.47
  4527.8  422.98  4564.3  420.84  4713.6   421.1    4863  420.36  4971.3  420.18
    4999  413.08  5001.8  412.58    5005  413.08  5010.9   413.3  5021.1  418.68
  5032.2  420.31    5205  421.81  5312.4  420.56  5358.1  417.23  5364.3  421.44
  5428.5   420.8  5569.5  423.86  5672.6  429.12  5723.7  435.05  5841.9  443.45
#Mann= 9 ,-1 , 0
  3472.5     .05       0  4713.6     .16       0    4863     .05       0
    4999     .03       0    5005     .05       0  5032.2     .16       0
  5364.3     .12       0  5428.5     .16       0  5569.5      .1       0
Bank Sta=4971.3,5021.1
XS Rating Curve= 0 ,0
Exp/Cntr=0.3,0.1

Type RM Length L Ch R = 1 ,21471   ,25,25,25
BEGIN DESCRIPTION:
PERRY CREEK 24.2
END DESCRIPTION:
XS GIS Cut Line= 6
      3532384.36     10565323.14      3532734.61     10565091.38
      3532802.31     10565023.67       3533354.4      10564168.2
      3533396.06     10564065.34      3533781.48     10563458.56
#Sta/Elev= 30
  3416.9  437.27  3595.9   431.9  3947.2  430.71  4019.8  427.58  4050.1  429.34
  4071.2  426.88  4086.4  428.73  4107.5  426.18  4122.7  427.73  4164.9  425.37
  4656.9  420.12  4803.7  419.91  4960.6  420.52  4990.2  416.46    4998  413.32
  5000.8  412.82    5004  413.32  5044.2  420.43  5105.2  421.02    5156  422.83
  5161.9  420.97  5192.4  422.16  5213.6  420.09    5250  421.78  5307.6  416.92
  5322.8  419.88  5368.1   421.4  5394.9  420.78  5557.9  423.03  5780.6  437.56
#Mann= 9 ,-1 , 0
  3416.9     .05       0  4656.9     .16       0  4803.7     .05       0
    4998     .03       0    5004     .05       0  5105.2     .16       0
  5368.1     .12       0  5394.9     .16       0  5557.9      .1       0
Bank Sta=4960.6,5044.2
XS Rating Curve= 0 ,0
Exp/Cntr=0.3,0.1

Type RM Length L Ch R = 1 ,21446   ,637,637,637
BEGIN DESCRIPTION:
PERRY CREEK 24.3
END DESCRIPTION:
XS GIS Cut Line= 6
      3532409.08     10565324.46      3532759.35     10565092.68
      3532827.05     10565024.97      3533379.14     10564169.51
       3533420.8     10564066.64      3533806.21     10563459.89
#Sta/Elev= 30
  3415.6  435.99  3478.7  434.03  3514.8  431.67  3535.8  432.68  3824.7  431.31
  4096.7  425.84  4633.4  420.12  4779.5  419.99    4958  421.01  4967.1  418.87
  4972.5  420.64  4979.6  417.06  4990.4  415.18  4993.6  412.87  4996.3  412.37
  4999.6  412.87  5044.3  418.68  5050.2  421.04  5134.2  420.58  5260.3  421.26
  5296.7  416.37    5312  419.31  5348.4  421.24  5372.8  420.83    5383  420.61
  5457.4  420.39  5544.5  422.72    5557   423.2  5741.2  434.95  5779.3  437.22
#Mann= 11 ,-1 , 0
  3415.6     .05       0  4633.4     .16       0  4779.5     .05       0
  4993.6     .03       0  4999.6     .05       0  5134.2     .16       0
  5372.8     .12       0    5383     .16       0  5544.5     .12       0
    5557      .1       0  5741.2     .12       0
Bank Sta=4972.5,5050.2
XS Rating Curve= 0 ,0
Exp/Cntr=0.3,0.1

Type RM Length L Ch R = 1 ,20809   ,1634,1634,1634
BEGIN DESCRIPTION:
PERRY CREEK 22.0
END DESCRIPTION:
XS GIS Cut Line= 4
      3533705.88      10565961.1       3533803.1      10564634.7
      3534018.38     10564169.42      3534242.12     10563641.61
#Sta/Elev= 30
  3417.4  448.31  3577.3  447.25  3710.2  441.79  3843.8  433.16  3977.4  426.88
  4131.1  422.92    4651  419.98  4809.4   418.9  4882.9  418.83  4945.5  415.84
  4973.9  420.07  4993.8  411.78  4996.6  411.28  4999.8  411.78  5014.3  413.52
  5026.2  418.83  5162.8  420.36  5185.8  420.04  5208.7  416.54  5214.2  418.04
  5231.6  416.76  5254.5  418.27  5258.5  419.89  5301.1  419.18  5322.8  415.61
  5330.9  418.28  5344.5  419.23  5398.8  418.36  5644.9   433.9  5833.3  448.14
#Mann= 7 ,-1 , 0
  3417.4     .05       0  4131.1      .1       0    4651     .16       0
  4809.4     .12       0  4993.8     .07       0  4999.8     .12       0
  5644.9     .05       0
Bank Sta=4973.9,5026.2
XS Rating Curve= 0 ,0
Exp/Cntr=0.3,0.1

Type RM Length L Ch R = 1 ,19175   ,1083,1083,1083
BEGIN DESCRIPTION:
PERRY CREEK 21.0
END DESCRIPTION:
XS GIS Cut Line= 3
      3535576.98     10565655.34      3535063.74     10564034.06
      3534342.14     10563591.66
#Sta/Elev= 30
  3676.5  441.85  3753.8  441.58  3912.2  437.83  4135.9  421.55  4267.5  417.87
  4371.5  417.38  4479.6  416.84  4622.3  416.79  4869.9  416.44  4936.9  417.86
    4972  417.44  4991.5  413.39  5001.3  408.76  5004.1  408.26  5007.3  408.76
  5012.5  409.55  5031.4  417.85  5068.9  416.71  5180.3  417.71  5198.2  414.62
  5211.8  417.65  5295.1  415.77  5316.7  416.87  5358.6  415.64  5402.5  416.78
  5583.4  415.91  5736.2  423.87  5867.7  435.57  5925.7  438.78  6223.5   445.8
#Mann= 8 ,-1 , 0
  3676.5     .16       0  4135.9     .05       0  4371.5      .1       0
  4479.6     .05       0  4622.3      .1       0  4936.9     .16       0
  5001.3     .07       0  5007.3     .16       0
Bank Sta=4972,5031.4
XS Rating Curve= 0 ,0
Exp/Cntr=0.3,0.1

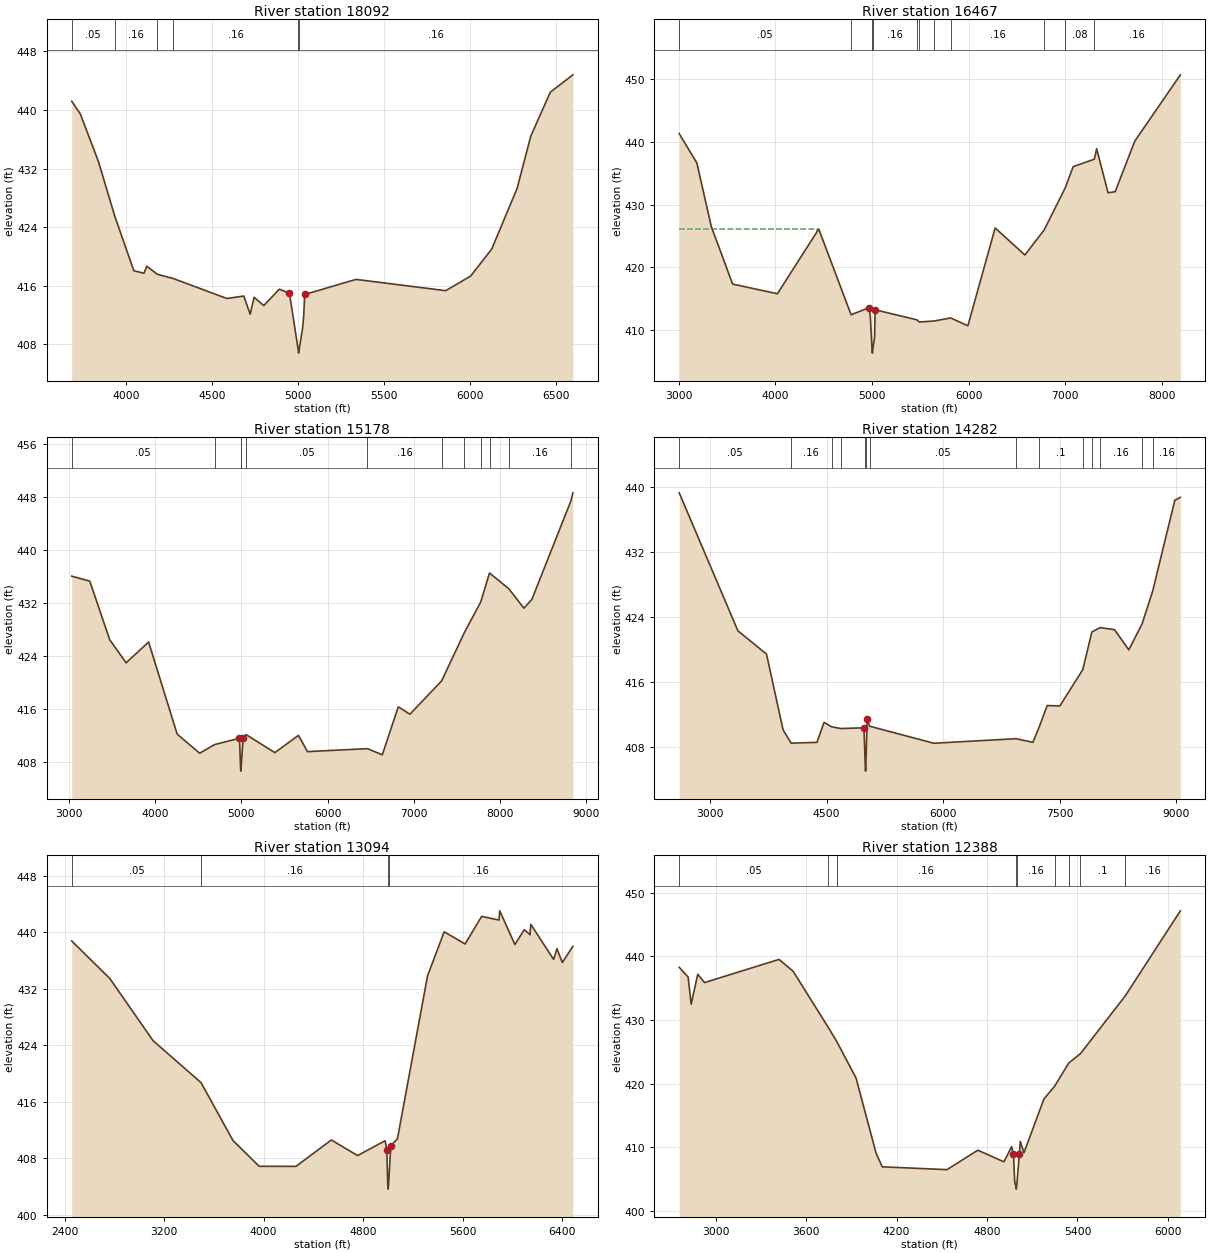
Type RM Length L Ch R = 1 ,18092   ,1625,1625,1625
BEGIN DESCRIPTION:
PERRY CREEK 20.0
END DESCRIPTION:
XS GIS Cut Line= 3
       3536439.6     10565151.99      3535789.62     10563902.03
      3534339.63     10563502.03
#Sta/Elev= 30
    3685  441.19  3734.9  439.46  3839.8  432.99  3935.1  425.52  4046.1  418.06
  4105.1  417.72  4121.6  418.68  4182.5  417.58  4275.3     417  4587.1  414.27
  4685.2  414.61  4722.3  412.13  4744.9  414.44  4801.4  413.31  4891.4  415.54
  4950.5  415.01  5001.1  407.32  5003.9  406.82  5007.1  407.32  5026.7   410.2
  5033.3  411.84  5038.9  414.82  5337.4  416.88  5858.9  415.34  6004.1  417.34
  6126.4  421.02  6273.9   429.3  6353.3  436.42  6466.8  442.42    6598  444.79
#Mann= 6 ,-1 , 0
    3685     .05       0  3935.1     .16       0  4182.5     .05       0
  4275.3     .16       0  5001.1     .07       0  5007.1     .16       0
Bank Sta=4950.5,5038.9
XS Rating Curve= 0 ,0
Exp/Cntr=0.3,0.1

Type RM Length L Ch R = 1 ,16467   ,1289,1289,1289
BEGIN DESCRIPTION:
PERRY CREEK 17.0
END DESCRIPTION:
XS GIS Cut Line= 3
       3537842.1     10564991.64      3537042.11     10563191.64
      3534142.12     10561791.65
#Sta/Elev= 30
  3003.7  441.33  3186.3  436.66  3336.8  426.48    3557  417.34  4020.7   415.8
  4448.9  426.12  4783.7  412.45  4964.6  413.54    4982  412.44  5001.6  406.83
  5004.3  406.33  5007.6  406.83  5027.2  408.86  5032.8  413.24  5465.5  411.64
  5491.3  411.29  5641.9  411.45  5814.6  411.94  5993.3  410.69  6275.6  426.29
  6583.6  421.98  6784.5     426  7001.4  432.69  7083.5  436.06  7303.2  437.26
  7326.6  438.93  7445.2   431.9  7518.5  432.07    7722  440.14  8193.7  450.71
#Mann= 11 ,-1 , 0
  3003.7     .05       0  4783.7     .16       0  5001.6     .07       0
  5007.6     .16       0  5465.5      .1       0  5491.3     .05       0
  5641.9      .1       0  5814.6     .16       0  6784.5      .1       0
  7001.4     .08       0  7303.2     .16       0
#XS Ineff= 2 , 0
         4426.11  426.18
Permanent Ineff=
       F       F
Bank Sta=4964.6,5032.8
XS Rating Curve= 0 ,0
Exp/Cntr=0.3,0.1

Type RM Length L Ch R = 1 ,15178   ,896,896,896
BEGIN DESCRIPTION:
PERRY CREEK 15.0
END DESCRIPTION:
XS GIS Cut Line= 4
      3538292.11     10564690.25      3538143.38     10562912.47
      3537796.16      10562697.2       3534292.1     10561791.64
#Sta/Elev= 30
  3033.1  436.07  3242.4  435.32  3473.2  426.47  3663.9  422.96  3924.8   426.1
    4256  412.17  4516.9  409.28    4690  410.59  4978.7  411.54  4991.1  407.07
  4993.8  406.57  4997.1  407.07  5021.2  411.63  5055.2   412.1  5388.8  409.37
    5663  411.98  5766.9  409.52  6462.5  409.97  6634.5  409.04  6820.4   416.3
  6954.7  415.18  7322.6  420.22  7586.2  427.52    7777  432.18  7878.1  436.55
  8102.5  434.16  8276.7  431.22  8369.7  432.56  8824.6  447.54  8844.8  448.68
#Mann= 12 ,-1 , 0
  3033.1     .05       0    4690     .16       0  4991.1     .07       0
  4997.1     .16       0  5055.2     .05       0  6462.5     .16       0
  7322.6     .05       0  7586.2      .1       0    7777     .05       0
  7878.1     .08       0  8102.5     .16       0  8824.6      .1       0
Bank Sta=4978.7,5021.2
XS Rating Curve= 0 ,0
Exp/Cntr=0.3,0.1

Type RM Length L Ch R = 1 ,14282   ,1188,1188,1188
BEGIN DESCRIPTION:
PERRY CREEK 14.0
END DESCRIPTION:
XS GIS Cut Line= 4
      3538380.79      10564698.7      3538745.37     10562542.46
      3538412.43     10562295.71      3534642.06     10561541.63
#Sta/Elev= 30
  2603.7  439.25  3358.8  422.27  3726.5  419.41  3939.5   410.1  4043.4  408.45
  4375.6  408.55  4466.8  411.01  4563.1  410.47  4680.3  410.25  4980.1  410.34
  4997.9  405.51  5000.7  405.01  5003.9  405.51  5021.8  411.38  5051.7  410.54
  5878.4  408.44  6936.4     409  7153.1  408.55  7236.6  410.49  7336.7  413.08
  7499.9  413.03  7795.3   417.5  7911.5  422.13    8017  422.67  8203.5  422.41
  8387.1  419.93    8559  423.16  8694.6  427.18  8978.6  438.33    9050  438.69
#Mann= 14 ,-1 , 0
  2603.7     .05       0  4043.4     .16       0  4563.1     .05       0
  4680.3     .16       0  4997.9     .07       0  5003.9     .16       0
  5051.7     .05       0  6936.4     .16       0  7236.6      .1       0
  7795.3     .05       0  7911.5      .1       0    8017     .16       0
    8559     .05       0  8694.6     .16       0
Bank Sta=4980.1,5021.8
XS Rating Curve= 0 ,0
Exp/Cntr=0.3,0.1

Type RM Length L Ch R = 1 ,13094   ,706,706,706
BEGIN DESCRIPTION:
PERRY CREEK 13.0
END DESCRIPTION:
XS GIS Cut Line= 5
      3538442.11     10564741.62      3539242.11     10562341.64
      3539442.11     10561991.64      3539752.07     10561291.17
      3539704.55     10560965.01
#Sta/Elev= 30
  2457.5  438.75  2763.2  433.45    3111  424.65  3497.3   418.7    3754   410.5
  3964.8  406.86    4260  406.85  4544.6  410.59  4755.4  408.38  4976.8  410.48
  4990.2  409.22    4998  404.13  5000.7  403.63    5004  404.13  5022.6   409.8
  5075.8  410.75  5317.7  433.81  5451.4  440.05  5619.9  438.33  5752.7  442.23
  5892.5  441.71    5898  443.02  6019.9  438.25  6095.2  440.36  6141.8  439.63
  6147.3  441.12  6331.2  436.14    6358  437.66  6401.2   435.7    6486  437.99
#Mann= 4 ,-1 , 0
  2457.5     .05       0  3497.3     .16       0    4998     .07       0
    5004     .16       0
Bank Sta=4990.2,5022.6
XS Rating Curve= 0 ,0
Exp/Cntr=0.3,0.1

Type RM Length L Ch R = 1 ,12388   ,904,904,904
BEGIN DESCRIPTION:
PERRY CREEK 12.0
END DESCRIPTION:
XS GIS Cut Line= 3
      3539192.25     10565019.35      3539608.92     10563040.21
      3539869.08     10561765.41
#Sta/Elev= 30
  2758.8  438.28  2817.8  436.75  2838.2  432.49  2881.8   437.2  2926.5  435.88
  3420.7  439.52  3514.1  437.67  3744.8  428.94  3802.6  426.68  3931.7  420.89
  4064.5  409.09  4105.4  406.95  4534.8  406.51    4739  409.56  4912.5  407.74
  4963.6  410.12  4975.6  408.96    4984  404.54  4991.2  403.95  4993.9  403.45
  4997.2  403.95  5014.6  408.94    5021  410.93  5045.2  409.17  5177.9  417.62
    5248  419.59  5342.2  423.25  5419.5  424.71  5717.4  433.81  6082.4  447.15
#Mann= 9 ,-1 , 0
  2758.8     .05       0  3744.8      .1       0  3802.6     .16       0
  4991.2     .07       0  4997.2     .16       0    5248      .1       0
  5342.2     .16       0  5419.5      .1       0  5717.4     .16       0
Bank Sta=4975.6,5014.6
XS Rating Curve= 0 ,0
Exp/Cntr=0.3,0.1

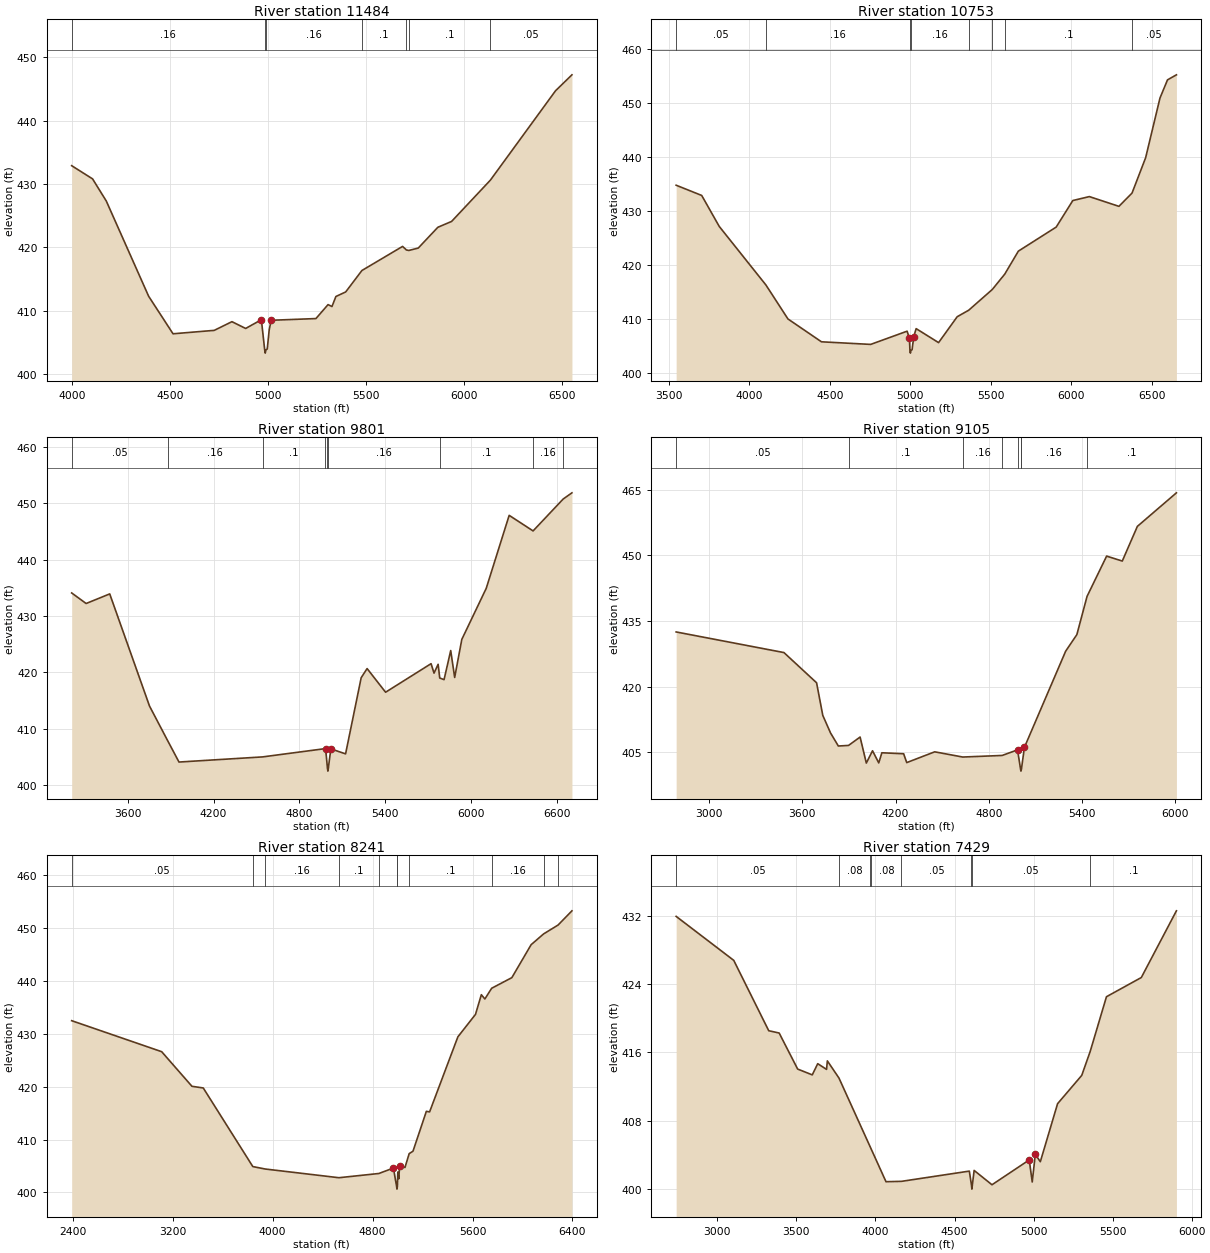
Type RM Length L Ch R = 1 ,11484   ,731,731,731
BEGIN DESCRIPTION:
PERRY CREEK 10.0
END DESCRIPTION:
XS GIS Cut Line= 3
       3540267.8     10564208.05       3540217.8     10563258.01
       3540267.8     10561658.05
#Sta/Elev= 30
  3999.8   432.9  4106.4  430.82  4176.5  427.32  4392.6   412.3  4516.9  406.39
  4727.2  406.93  4817.3   408.3  4887.4  407.23  4967.5  408.61  4984.5  403.84
  4987.3  403.34  4990.5  403.84  4997.5  403.99  5007.5  407.01  5017.6  408.52
  5245.9  408.79  5307.7  410.99  5327.7  410.69  5347.7  412.27  5397.7  412.99
  5480.5  416.37  5687.9  420.17  5707.4  419.61  5719.7  419.53  5767.9  419.91
    5868  423.19    5938  424.11  6135.8  430.62  6468.3  444.72  6551.9  447.23
#Mann= 7 ,-1 , 0
  3999.8     .16       0  4984.5     .07       0  4990.5     .16       0
  5480.5      .1       0  5707.4     .16       0  5719.7      .1       0
  6135.8     .05       0
Bank Sta=4967.5,5017.6
XS Rating Curve= 0 ,0
Exp/Cntr=0.3,0.1

Type RM Length L Ch R = 1 ,10753   ,952,952,952
BEGIN DESCRIPTION:
PERRY CREEK 8.0
END DESCRIPTION:
XS GIS Cut Line= 2
      3541150.87     10564415.88      3540413.22     10561395.86
#Sta/Elev= 30
  3544.7  434.76  3703.5  432.87  3812.5  427.15  4102.8  416.33  4239.4  410.07
  4447.7  405.85  4753.5  405.37  4979.9  407.81  4994.4  406.49  4997.5  404.26
  5000.3  403.76  5003.5  404.26  5010.8  404.37  5021.1   406.8  5036.1  408.28
  5175.5   405.7  5291.2  410.48  5362.6  411.68  5509.3  415.51  5586.6  418.34
  5671.3  422.59  5906.4  427.03  6009.7  431.93  6112.3  432.66  6296.2  430.86
  6377.7  433.31  6462.3  439.84  6551.3  450.85  6598.1  454.21  6653.5  455.14
#Mann= 8 ,-1 , 0
  3544.7     .05       0  4102.8     .16       0  4997.5     .07       0
  5003.5     .16       0  5362.6      .1       0  5509.3     .16       0
  5586.6      .1       0  6377.7     .05       0
Bank Sta=4994.4,5021.1
XS Rating Curve= 0 ,0
Exp/Cntr=0.3,0.1

Type RM Length L Ch R = 1 ,9801    ,696,696,696
BEGIN DESCRIPTION:
PERRY CREEK 7.0
END DESCRIPTION:
XS GIS Cut Line= 2
       3541644.5     10564079.67      3540802.62     10560686.14
#Sta/Elev= 30
  3208.7  434.09  3309.7  432.22  3474.6  433.92  3752.7  414.05  3880.1  407.89
  3958.8  404.13  4543.2  405.04  4975.7  406.49  4983.8   406.4  4996.4  403.02
  4999.2  402.52  5002.4  403.02    5020  406.46  5123.1  405.58  5232.1  419.07
  5273.4  420.69  5402.7   416.5  5720.6  421.56  5741.2  419.88  5769.9  421.45
  5781.1  419.02  5811.3  418.73  5857.8  423.88  5885.5  419.12  5935.4  425.86
    6106   434.9  6266.4  447.84  6433.5  445.08  6644.2  450.74  6705.1  451.83
#Mann= 9 ,-1 , 0
  3208.7     .05       0  3880.1     .16       0  4543.2      .1       0
  4975.7     .16       0  4996.4     .07       0  5002.4     .16       0
  5781.1      .1       0  6433.5     .16       0  6644.2      .1       0
Bank Sta=4983.8,5020
XS Rating Curve= 0 ,0
Exp/Cntr=0.3,0.1

Type RM Length L Ch R = 1 ,9105    ,864,864,864
BEGIN DESCRIPTION:
PERRY CREEK 3.2
END DESCRIPTION:
XS GIS Cut Line= 4
      3541828.02     10564195.09      3541829.62     10562154.39
        3541611.     10561738.51      3541697.74     10561035.98
#Sta/Elev= 30
  2788.8  432.47  3482.2  427.76  3692.2  420.86  3732.2   413.4  3782.2  409.38
  3832.2  406.41  3897.8  406.54  3972.2  408.46  4012.2  402.51  4052.2  405.32
  4092.2  402.55  4112.2  404.86  4252.3  404.64  4272.3  402.62  4452.3  405.08
  4632.5  403.89  4886.3  404.25  4985.2  405.53  4987.5  404.97  5004.3  401.17
    5007  400.67  5010.3  401.17  5029.3   406.1  5294.7  428.08  5366.7  431.86
  5432.1  440.58  5558.2   449.8  5658.9  448.67  5755.9  456.59  6007.2  464.26
#Mann= 8 ,-1 , 0
  2788.8     .05       0  3897.8      .1       0  4632.5     .16       0
  4886.3      .1       0  4987.5     .16       0  5004.3     .07       0
  5010.3     .16       0  5432.1      .1       0
Bank Sta=4985.2,5029.3
XS Rating Curve= 0 ,0
Exp/Cntr=0.3,0.1

Type RM Length L Ch R = 1 ,8241    ,812,812,812
BEGIN DESCRIPTION:
PERRY CREEK 5.0
END DESCRIPTION:
XS GIS Cut Line= 5
      3541904.92     10564435.64      3542216.22     10562139.55
      3542555.96     10561718.59      3542338.95      10560824.5
      3542166.23     10560677.68
#Sta/Elev= 30
    2391  432.51  3111.5  426.64  3353.7  420.09  3444.4  419.77  3841.1  404.89
  3939.6  404.43  4530.4  402.78  4850.2  403.58  4966.6  404.61  4992.3  401.12
  4995.1  400.62  4998.3  401.12  5001.8  403.86  5009.7  402.58  5016.1  405.01
  5059.3  404.73  5092.8  407.34  5123.3   407.8  5230.4  415.35  5256.2  415.24
  5482.6  429.45  5623.6   433.7  5670.6  437.43  5698.7  436.62  5753.2  438.65
  5914.8  440.66  6069.1   446.9    6169  448.94  6284.9  450.62  6395.8  453.31
#Mann= 11 ,-1 , 0
    2391     .05       0  3841.1      .1       0  3939.6     .16       0
  4530.4      .1       0  4850.2     .16       0  4992.3     .07       0
  4998.3     .16       0  5092.8      .1       0  5753.2     .16       0
    6169      .1       0  6284.9     .16       0
Bank Sta=4966.6,5016.1
XS Rating Curve= 0 ,0
Exp/Cntr=0.3,0.1

Type RM Length L Ch R = 1 ,7429    ,892,892,892
BEGIN DESCRIPTION:
PERRY CREEK 4.0
END DESCRIPTION:
XS GIS Cut Line= 4
      3542590.69     10564531.06      3542920.55     10562543.25
      3543024.71      10562074.5       3543242.1     10561441.67
#Sta/Elev= 30
  2739.4  431.94  3103.7  426.79    3325  418.55    3391  418.28  3507.9  414.06
  3600.4  413.38  3634.9  414.69  3690.7  414.02  3695.8  415.02  3769.2  413.01
  3966.8  404.95  3973.2  404.69  4066.7  400.87  4164.3  400.91  4593.8  402.11
  4607.1   400.5  4609.9     400  4613.1   400.5  4624.2  402.19  4737.1  400.51
  4972.7  403.42  4991.7  400.84  5011.1  404.07  5042.9  403.21  5151.9     410
  5304.9  413.32  5358.1  416.11  5461.2  422.53  5681.7  424.78  5903.7  432.59
#Mann= 8 ,-1 , 0
  2739.4     .05       0  3769.2     .08       0  3966.8     .05       0
  3973.2     .08       0  4164.3     .05       0  4607.1     .03       0
  4613.1     .05       0  5358.1      .1       0
Bank Sta=4972.7,5011.1
XS Rating Curve= 0 ,0
Exp/Cntr=0.3,0.1

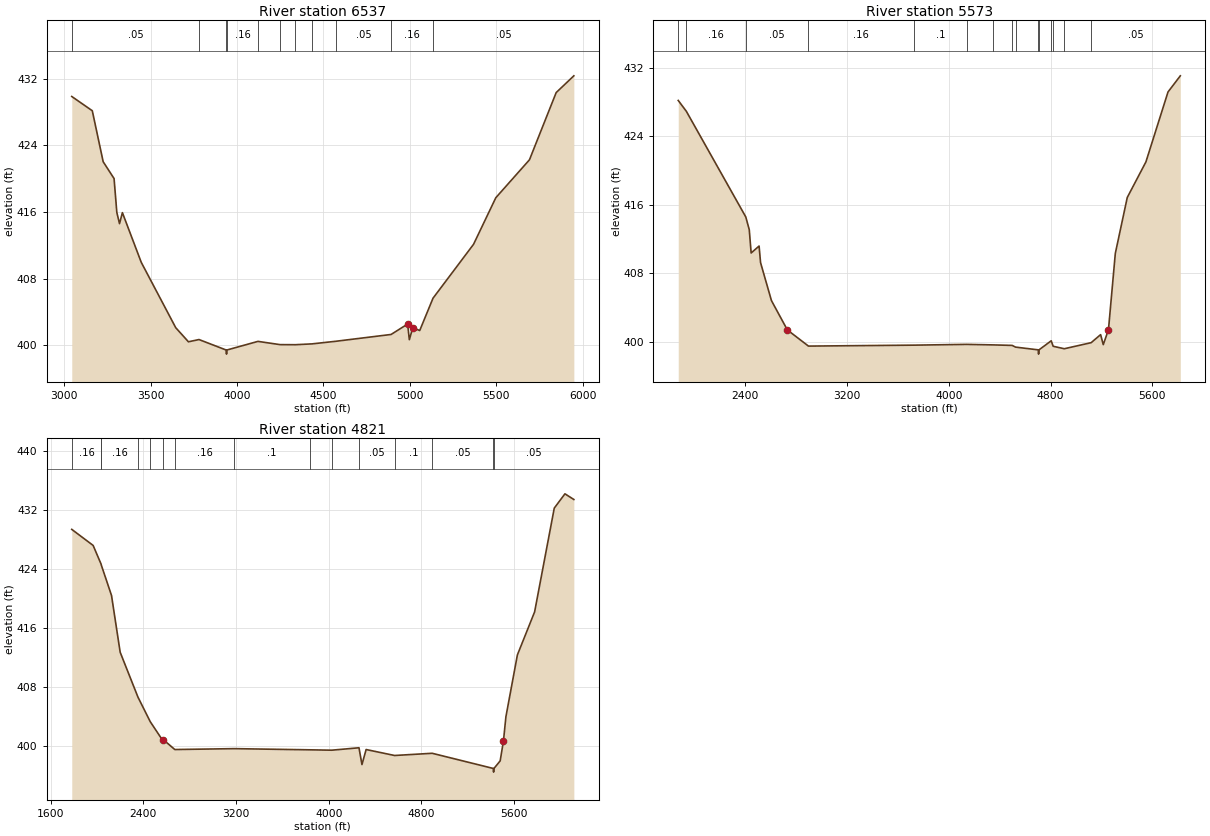
Type RM Length L Ch R = 1 ,6537    ,964,964,964
BEGIN DESCRIPTION:
PERRY CREEK 3.0
END DESCRIPTION:
XS GIS Cut Line= 4
      3543267.78     10563914.75      3543779.92     10562308.87
       3543788.6     10561840.12       3543606.7     10561112.51
#Sta/Elev= 30
    3044  429.86  3162.7  428.15  3225.7  422.03  3288.7  420.01  3304.7  415.94
  3320.2   414.6  3336.9  415.92  3446.1  409.95  3645.5  402.11    3719  400.42
  3779.9  400.69  3936.4  399.44  3939.2  398.94  3942.4  399.44    4121  400.47
  4248.7  400.08  4337.5  400.07  4433.7  400.17  4570.6  400.48  4891.2   401.3
  4986.8  402.55  4996.8  400.67  5016.8  402.12  5056.8  401.77  5133.7  405.65
  5368.2  412.12    5497  417.71  5691.6  422.26  5846.2  430.33  5948.4  432.34
#Mann= 11 ,-1 , 0
    3044     .05       0  3779.9     .16       0  3936.4     .07       0
  3942.4     .16       0    4121     .05       0  4248.7     .16       0
  4337.5     .05       0  4433.7     .16       0  4570.6     .05       0
  4891.2     .16       0  5133.7     .05       0
Bank Sta=4986.8,5016.8
XS Rating Curve= 0 ,0
Exp/Cntr=0.3,0.1

Type RM Length L Ch R = 1 ,5573    ,752,752,752
BEGIN DESCRIPTION:
PERRY CREEK 3.1
END DESCRIPTION:
XS GIS Cut Line= 4
      3543424.03     10564227.24      3544630.62     10561657.83
      3544109.78     10561484.22      3543814.65      10561006.8
#Sta/Elev= 30
  1871.5   428.2  1935.3  426.93  2402.6  414.58  2430.1  413.09    2445  410.36
  2507.4  411.17    2519  409.23  2604.7  404.79  2729.8  401.36  2895.7  399.47
  3725.5  399.58  4140.4  399.67  4345.2  399.61  4497.8  399.55  4524.8  399.35
    4703  399.03  4705.7  398.53    4709  399.03  4805.1  400.09  4820.3  399.45
  4907.9  399.16  5119.3  399.87  5193.5  400.81  5214.5  399.64  5255.3  401.38
  5309.2  410.31  5403.2  416.85  5549.8  421.01  5723.6  429.19  5820.4  431.08
#Mann= 15 ,-1 , 0
  1871.5     .05       0  1935.3     .16       0  2402.6     .05       0
  2895.7     .16       0  3725.5      .1       0  4140.4     .07       0
  4345.2     .05       0  4497.8     .16       0  4524.8     .05       0
    4703     .07       0    4709     .05       0  4805.1     .16       0
  4820.3     .05       0  4907.9     .16       0  5119.3     .05       0
Bank Sta=2729.8,5255.3
XS Rating Curve= 0 ,0
Exp/Cntr=0.3,0.1

Type RM Length L Ch R = 1 ,4821    ,0,0,0
BEGIN DESCRIPTION:
PERRY CREEK 1.0
END DESCRIPTION:
XS GIS Cut Line= 4
       3543745.2     10564279.36      3544908.39     10561727.27
      3544804.23     10561050.19      3544213.92      10560451.2
#Sta/Elev= 30
  1783.4  429.37  1967.7  427.19  2036.9  424.63  2038.5  424.51  2126.3  420.39
  2200.9  412.68  2354.6  406.57  2460.5  403.24  2566.4  400.73  2572.1  400.81
  2672.3  399.46  3185.4  399.58  3837.2  399.42  4025.8  399.37  4260.8   399.7
  4286.5  397.42  4322.4  399.46  4568.3  398.65  4892.2  398.95  5419.1  396.89
  5421.9  396.39  5425.1  396.89  5478.7  397.92    5507  400.63  5528.1  403.91
  5627.1  412.31  5775.7  418.16  5945.3  432.26  6037.3   434.2  6114.1  433.43
#Mann= 15 ,-1 , 0
  1783.4     .16       0  2036.9     .05       0  2038.5     .16       0
  2354.6     .05       0  2460.5     .16       0  2566.4     .05       0
  2672.3     .16       0  3185.4      .1       0  3837.2     .07       0
  4025.8     .16       0  4260.8     .05       0  4568.3      .1       0
  4892.2     .05       0  5419.1     .03       0  5425.1     .05       0
Bank Sta=2572.1,5507
XS Rating Curve= 0 ,0
Exp/Cntr=0.3,0.1

Chan Stop Cuts=-1
Use User Specified Reach Order=0
Composite Channel Slope=5