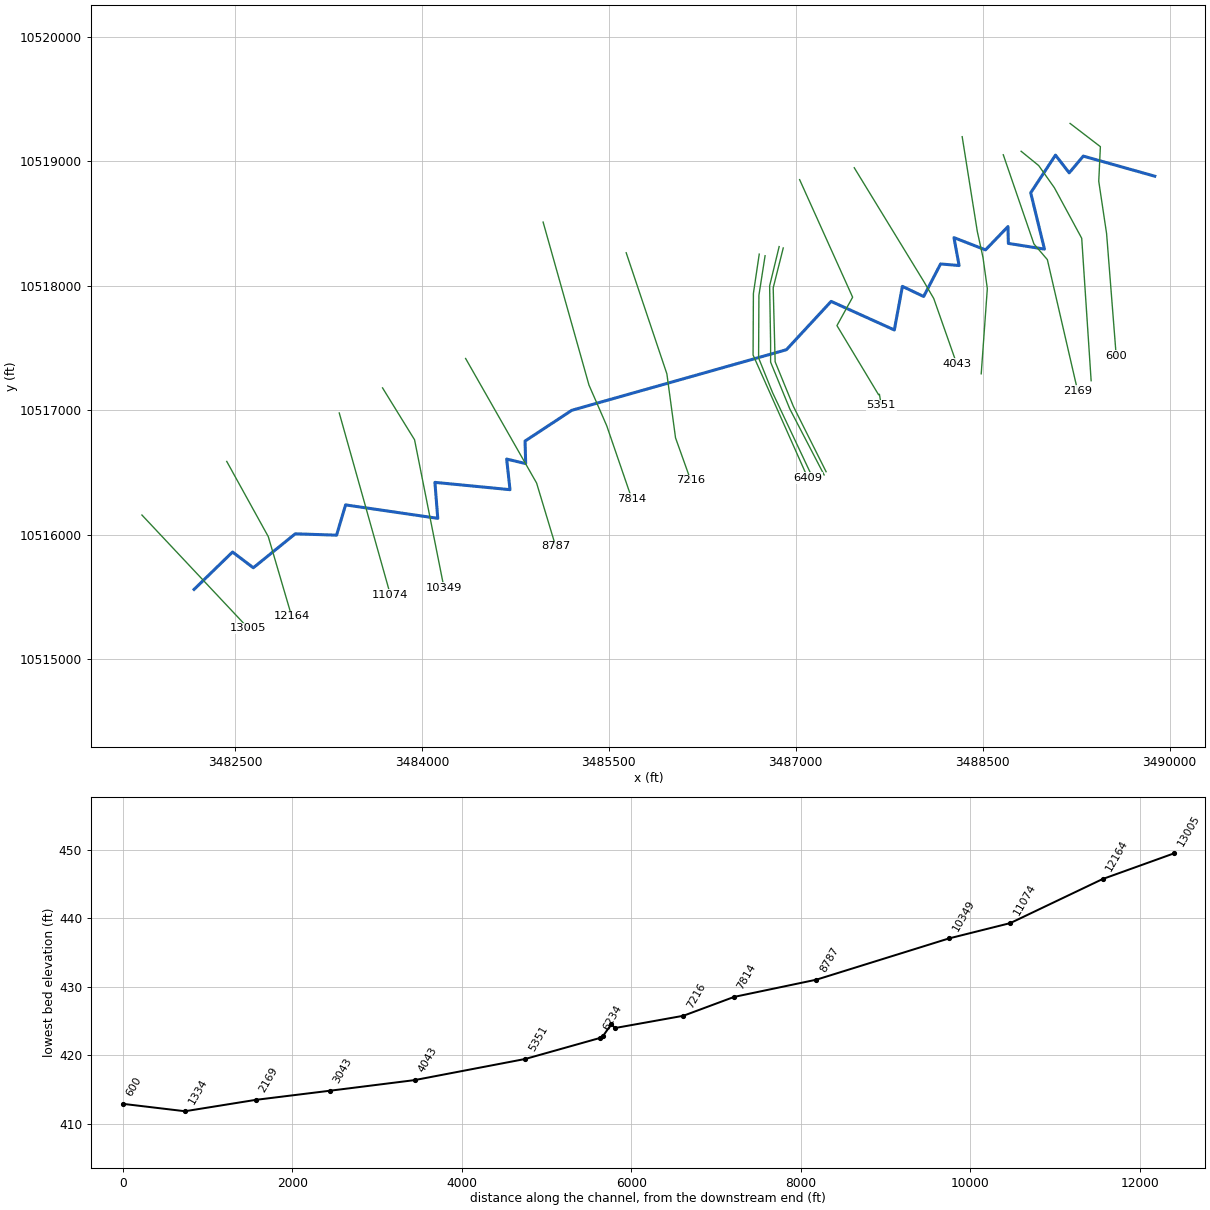
--- PHIFER CREEK.prj (project) ---

Proj Title=PHIFER CREEK Base Level Engineering
Current Plan=p01
Default Exp/Contr=0.3,0.1
English Units
Geom File=g01
Flow File=f01
Plan File=p01
Y Axis Title=Elevation
X Axis Title(PF)=Main Channel Distance
X Axis Title(XS)=Station
BEGIN DESCRIPTION:
PHIFER CREEK
END DESCRIPTION:
DSS Export Rating Curves= 0
DSS Export Rating Curve Sorted= 0
DSS Export Volume Flow Curves= 0
DXF OffsetX= 0
DXF OffsetY= 0
DXF ScaleX= 1
DXF ScaleY= 10

--- PHIFER CREEK.p01 (plan) ---

Plan Title=Multiple Run
Short Identifier=Multiple
Geom File=g01
Flow File=f01
Subcritical Flow
K Sum by GR= 0
Std Step Tol= 0.01
Critical Tol= 0.01
Num of Std Step Trials= 20
Max Error Tol= 0.3
Flow Tol Ratio= 0.001
Split Flow NTrial= 30
Split Flow Tol= 0.02
Split Flow Ratio= 0.02
Log Output Level= 0
Friction Slope Method= 1
Unsteady Friction Slope Method= 2
Unsteady Bridges Friction Slope Method= 1
Parabolic Critical Depth
Global Vel Dist=  1 , 1 , 1
Global Log Level= 0
CheckData=True
Encroach Param= -1, 0, 0, 0
BEGIN DESCRIPTION:
Multiple Run
END DESCRIPTION:

--- PHIFER CREEK.f01 (steady flow) ---

Flow Title=Multiple
Number of Profiles=7
Profile Names=10-year,25-year,50-year,1pct_min,100-year,1pct_plu,500-year
River Rch & RM= PHIFER CREEK,Reach-1,13005
    1805    2539    3156    2853    3859    5219    5760
Boundary for River Rch & Prof#=PHIFER CREEK,Reach-1,1
Up Type=0
Dn Type=3
Dn Slope=0.005
Boundary for River Rch & Prof#=PHIFER CREEK,Reach-1,2
Up Type=0
Dn Type=3
Dn Slope=0.005
Boundary for River Rch & Prof#=PHIFER CREEK,Reach-1,3
Up Type=0
Dn Type=3
Dn Slope=0.005
Boundary for River Rch & Prof#=PHIFER CREEK,Reach-1,4
Up Type=0
Dn Type=3
Dn Slope=0.005
Boundary for River Rch & Prof#=PHIFER CREEK,Reach-1,5
Up Type=0
Dn Type=3
Dn Slope=0.005
Boundary for River Rch & Prof#=PHIFER CREEK,Reach-1,6
Up Type=0
Dn Type=3
Dn Slope=0.005
Boundary for River Rch & Prof#=PHIFER CREEK,Reach-1,7
Up Type=0
Dn Type=3
Dn Slope=0.005

--- PHIFER CREEK.g01 (geometry) ---

Geom Title=Existing Conditions
Program Version=4.10

River Reach=PHIFER CREEK    ,Reach-1
Reach XY= 30
      3482172.11     10515561.64      3482480.73     10515861.78
      3482647.33     10515735.22      3482983.69     10516007.95
      3483315.35     10515997.01      3483387.67     10516240.09
      3484127.31     10516132.12      3484104.48     10516420.98
      3484706.95     10516362.41      3484680.09      10516608.1
      3484832.67     10516571.94      3484827.79     10516752.77
       3485202.7     10516999.72      3486924.87     10517486.26
      3487283.53     10517874.28      3487790.72     10517644.87
      3487855.36      10517994.8      3488026.04     10517913.59
      3488161.78     10518174.86       3488310.5     10518162.14
      3488269.08     10518386.17      3488522.36     10518287.87
      3488702.47     10518474.94      3488705.62     10518339.84
      3488995.24     10518294.09      3488884.88     10518746.28
      3489083.75     10519048.66      3489193.81     10518906.37
      3489306.79     10519040.77      3489880.41     10518879.47

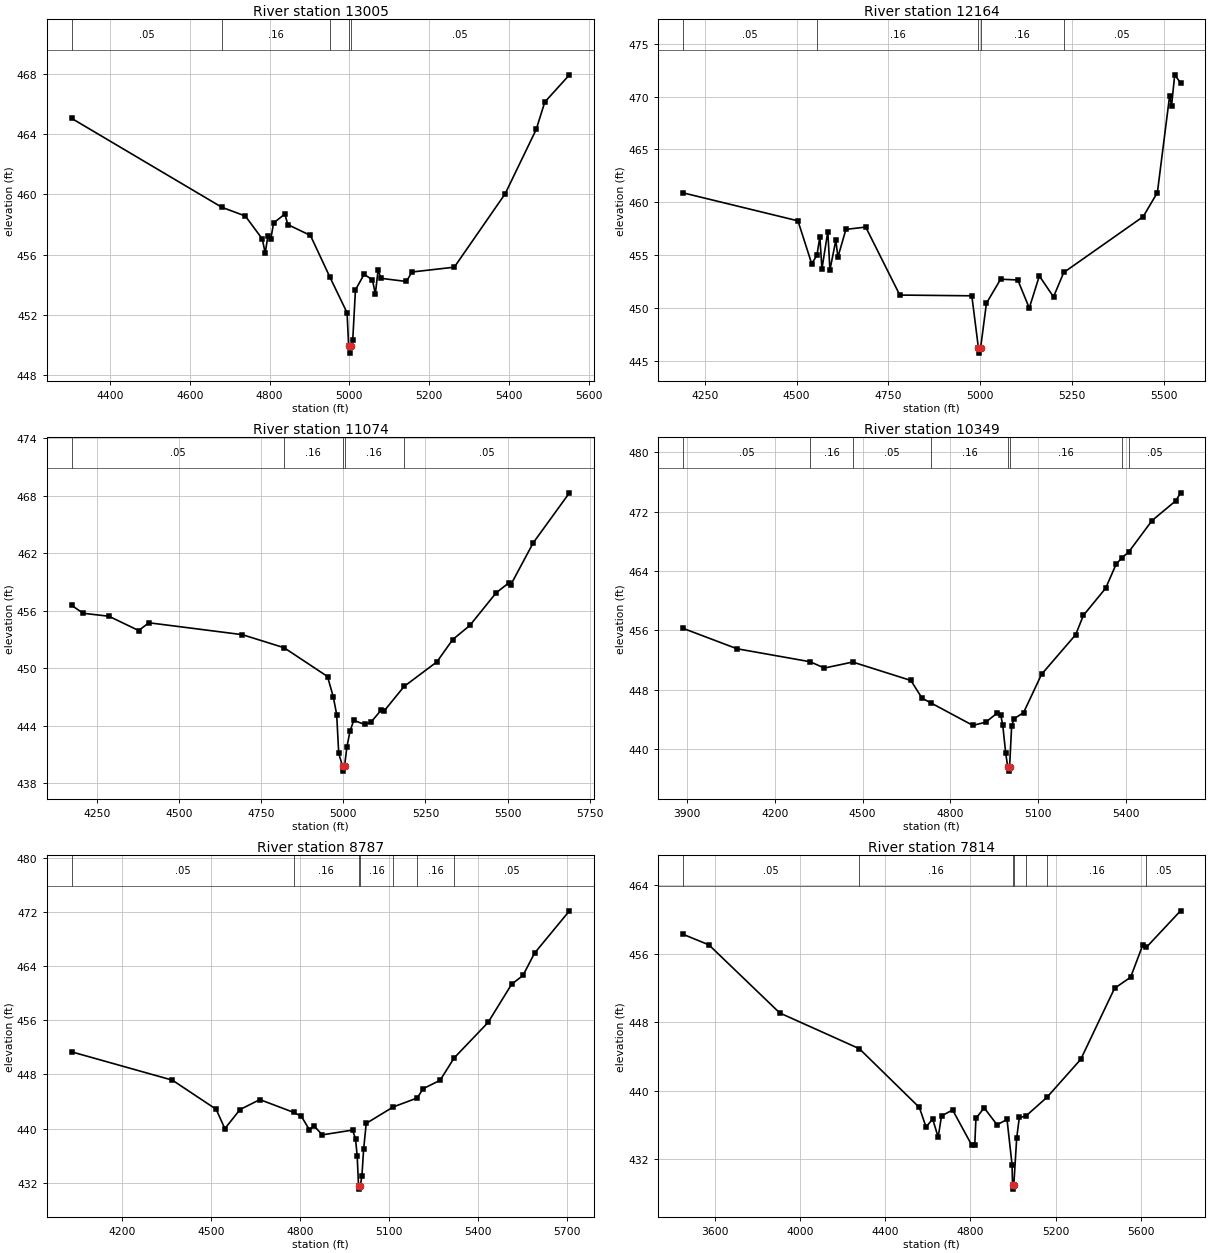
Type RM Length L Ch R = 1 ,13005   ,841,841,841
BEGIN DESCRIPTION:
PHIFER CREEK 19.0
END DESCRIPTION:
XS GIS Cut Line= 2
      3481753.66     10516158.73      3482607.43     10515249.43
#Sta/Elev= 30
    4304  465.05  4680.5  459.14  4739.3  458.56  4781.7  457.04  4789.1   456.1
  4795.9  457.24  4803.2  457.04  4810.1   458.1  4838.4  458.69  4845.7  457.99
  4902.4  457.27    4951  454.51  4994.2  452.13  4998.1  449.95  5000.8  449.45
  5004.1  449.95  5008.4  450.31  5015.2  453.65  5036.7  454.68  5057.7  454.33
    5065  453.38  5071.9  454.97  5079.2  454.42  5142.7  454.21  5156.8  454.84
  5262.8  455.16  5390.3  460.04    5468  464.31  5489.5  466.13  5551.3  467.94
#Mann= 5 ,-1 , 0
    4304     .05       0  4680.5     .16       0    4951     .05       0
  4998.1    .035       0  5004.1     .05       0
Bank Sta=4998.1,5004.1
XS Rating Curve= 0 ,0
Exp/Cntr=0.3,0.1

Type RM Length L Ch R = 1 ,12164   ,1090,1090,1090
BEGIN DESCRIPTION:
PHIFER CREEK 17.0
END DESCRIPTION:
XS GIS Cut Line= 3
       3482434.2     10516589.29      3482767.52     10515985.15
      3482954.96     10515346.48
#Sta/Elev= 30
  4189.8   460.9  4503.8  458.24  4541.2  454.18  4555.4  454.97  4563.4  456.72
  4569.1  453.69  4585.1  457.23  4590.8  453.58  4606.9  456.39  4612.6  454.81
  4634.4  457.43  4688.3  457.65  4781.1  451.21  4977.2  451.14  4995.1  446.21
  4997.8  445.71  5001.1  446.21    5017  450.44  5055.6  452.71  5102.3  452.64
  5133.6  449.98    5161  453.02  5199.6  451.04  5227.5  453.35  5443.8  458.64
  5482.4  460.92  5515.7  470.07    5521  469.15  5529.6  472.07  5545.4  471.31
#Mann= 5 ,-1 , 0
  4189.8     .05       0  4555.4     .16       0  4995.1     .07       0
  5001.1     .16       0  5227.5     .05       0
Bank Sta=4995.1,5001.1
XS Rating Curve= 0 ,0
Exp/Cntr=0.3,0.1

Type RM Length L Ch R = 1 ,11074   ,725,725,725
BEGIN DESCRIPTION:
PHIFER CREEK 15.0
END DESCRIPTION:
XS GIS Cut Line= 2
      3483336.98     10516978.16       3483746.7     10515519.83
#Sta/Elev= 30
  4173.3  456.56  4208.4  455.73  4286.9  455.42  4377.4  453.93  4408.6  454.74
  4692.8   453.5  4819.8  452.14    4952  449.14  4969.5  447.03  4979.9  445.18
  4986.1  441.15  4997.7  439.78  5000.4  439.28  5003.7  439.78    5011  441.79
  5020.2  443.41  5031.8  444.57  5064.6  444.15  5083.8  444.36  5114.9  445.63
  5125.3  445.59  5184.9   448.1  5284.6  450.66    5333  452.99    5385  454.46
  5465.3  457.87  5504.6  458.92  5509.8  458.71  5577.9  463.07  5688.1  468.28
#Mann= 5 ,-1 , 0
  4173.3     .05       0  4819.8     .16       0  4997.7     .07       0
  5003.7     .16       0  5184.9     .05       0
Bank Sta=4997.7,5003.7
XS Rating Curve= 0 ,0
Exp/Cntr=0.3,0.1

Type RM Length L Ch R = 1 ,10349   ,1562,1562,1562
BEGIN DESCRIPTION:
PHIFER CREEK 13.0
END DESCRIPTION:
XS GIS Cut Line= 3
      3483684.16     10517179.64      3483941.13     10516762.93
      3484177.05     10515576.42
#Sta/Elev= 30
  3885.9  456.29  4071.5  453.52  4321.2  451.77  4369.5  450.92  4466.4  451.73
  4664.9  449.25    4703  446.87  4733.6  446.22  4876.4   443.2  4920.6  443.63
  4957.9  444.81  4971.7  444.55  4978.3  443.29  4988.5  439.48  4995.7  437.54
  4998.5  437.04  5001.7  437.54  5008.9  443.18  5017.7  444.11  5049.7  444.93
  5110.9  450.08  5227.3  455.41  5253.6  458.01  5329.6  461.67  5365.8  464.94
  5385.3  465.77  5409.1  466.59  5488.1  470.79  5569.7  473.47  5585.2  474.52
#Mann= 8 ,-1 , 0
  3885.9     .05       0  4321.2     .16       0  4466.4     .05       0
  4733.6     .16       0  4995.7     .07       0  5001.7     .16       0
  5385.3     .12       0  5409.1     .05       0
Bank Sta=4995.7,5001.7
XS Rating Curve= 0 ,0
Exp/Cntr=0.3,0.1

Type RM Length L Ch R = 1 ,8787    ,973,973,973
BEGIN DESCRIPTION:
PHIFER CREEK 12.0
END DESCRIPTION:
XS GIS Cut Line= 3
      3484350.84     10517415.73       3484920.3     10516415.71
      3485073.09     10515908.73
#Sta/Elev= 30
  4028.3  451.35  4368.4  447.16  4516.3  442.85  4545.6  439.98  4596.9  442.81
  4663.8  444.28  4778.3  442.38  4803.6  441.83  4830.9  439.82  4846.8  440.39
  4874.2  439.06  4976.6  439.77  4986.6  438.48  4992.3  435.92  4996.7  431.53
  4999.4  431.03  5002.7  431.53  5008.2  432.98  5013.9   436.9  5022.7  440.76
  5114.2   443.2  5194.8  444.52  5214.7  445.89  5272.1  447.14  5319.5  450.45
    5434   455.7  5513.5  461.36  5551.7  462.65  5590.7  465.95  5708.6  472.22
#Mann= 7 ,-1 , 0
  4028.3     .05       0  4778.3     .16       0  4996.7     .07       0
  5002.7     .16       0  5114.2     .12       0  5194.8     .16       0
  5319.5     .05       0
Bank Sta=4996.7,5002.7
XS Rating Curve= 0 ,0
Exp/Cntr=0.3,0.1

Type RM Length L Ch R = 1 ,7814    ,598,598,598
BEGIN DESCRIPTION:
PHIFER CREEK 10.0
END DESCRIPTION:
XS GIS Cut Line= 4
      3484972.59     10518511.12      3485340.66     10517202.06
      3485483.02     10516875.67       3485684.4     10516288.87
#Sta/Elev= 30
  3450.3  458.27  3573.5  457.02    3906  449.07  4279.4   444.9  4561.2  438.04
  4592.4  435.76  4623.6  436.69  4649.4  434.57  4665.1  437.05  4717.1  437.75
  4807.7  433.61  4821.1  433.67  4826.6  436.76  4865.1     438  4925.7  436.02
  4972.5  436.64    4996  431.38  4998.4  429.01  5001.2  428.51  5004.4  429.01
  5017.9  434.49  5030.3  436.89  5059.2     437  5160.9  439.25  5318.5  443.66
  5477.1  451.95  5552.4  453.24  5609.7  457.01  5626.3  456.73  5786.6  460.99
#Mann= 7 ,-1 , 0
  3450.3     .05       0  4279.4     .16       0  4998.4     .07       0
  5004.4     .16       0  5059.2     .12       0  5160.9     .16       0
  5626.3     .05       0
Bank Sta=4998.4,5004.4
XS Rating Curve= 0 ,0
Exp/Cntr=0.3,0.1

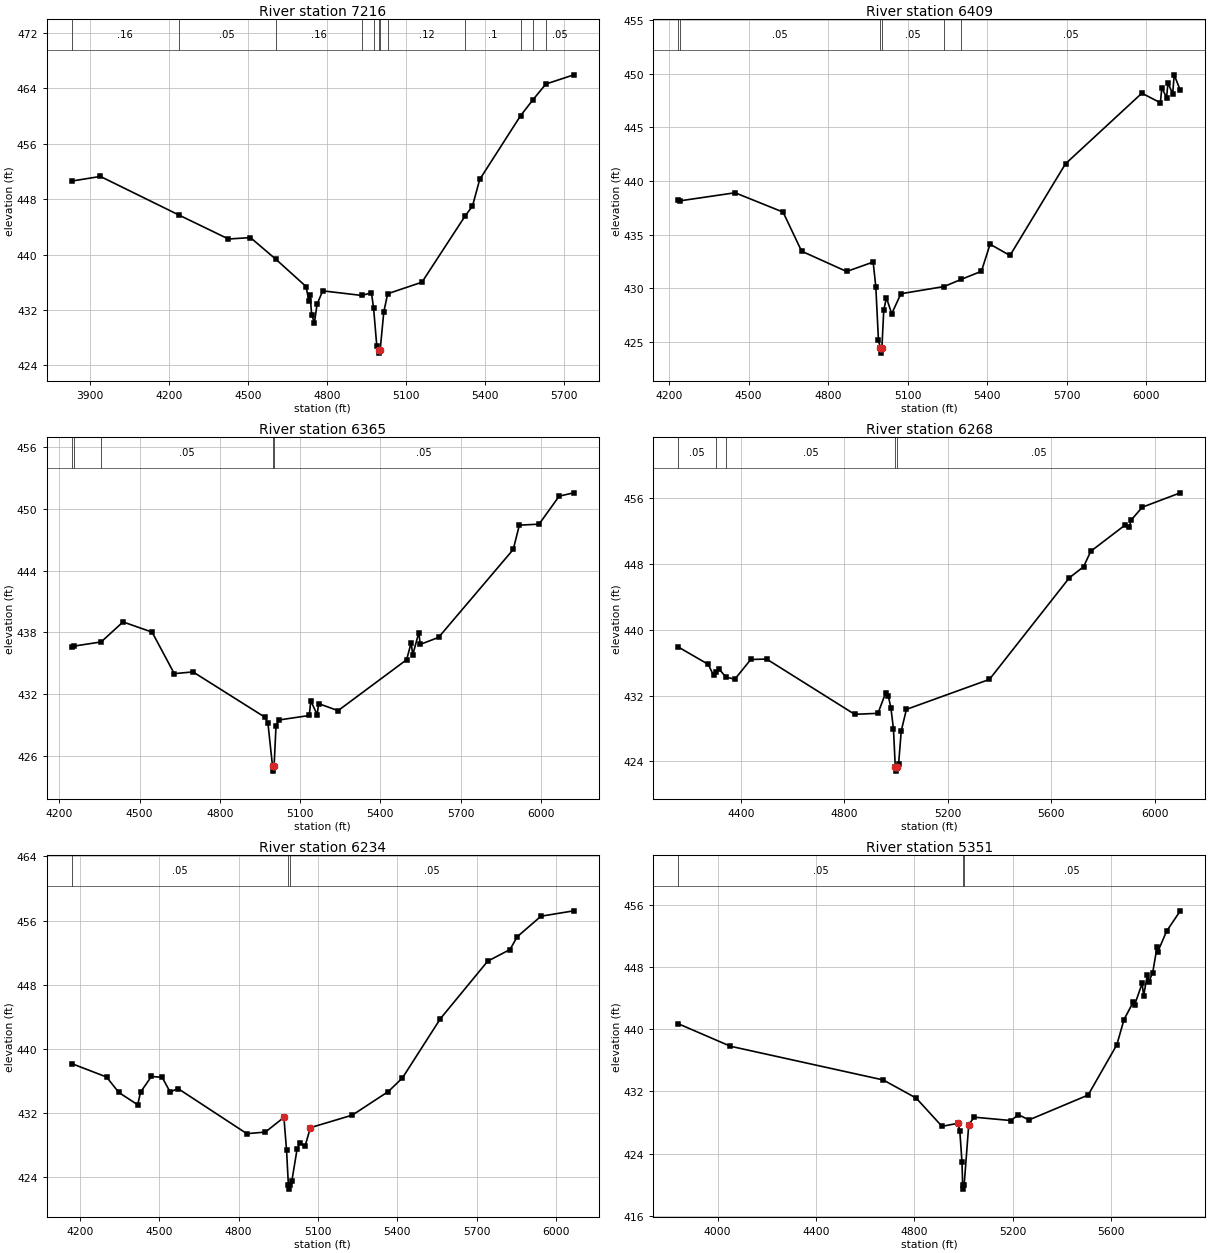
Type RM Length L Ch R = 1 ,7216    ,807,807,807
BEGIN DESCRIPTION:
PHIFER CREEK 9.0
END DESCRIPTION:
XS GIS Cut Line= 4
      3485639.27     10518264.56      3485965.66     10517292.33
       3486035.1     10516778.45      3486156.61     10516438.21
#Sta/Elev= 30
    3832  450.62  3940.6  451.29  4237.2  445.74  4426.6  442.25  4510.2  442.45
  4606.6  439.32  4721.2  435.38  4731.4  433.36  4736.7  434.15  4742.2  431.33
  4752.8  430.15    4763  432.83  4784.4  434.76  4933.1  434.09  4969.3  434.49
  4977.6  432.21  4989.4  426.85  4996.5  426.26  4999.3  425.76  5002.5  426.26
  5016.2  431.72  5030.9  434.34    5161  436.01  5325.4  445.61  5352.7     447
  5380.1  450.85  5535.7  460.09    5581  462.31  5631.3  464.64  5737.4  465.97
#Mann= 12 ,-1 , 0
    3832     .16       0  4237.2     .05       0  4606.6     .16       0
  4933.1     .12       0  4977.6     .16       0  4996.5     .07       0
  5002.5     .16       0  5030.9     .12       0  5325.4      .1       0
  5535.7     .05       0    5581      .1       0  5631.3     .05       0
Bank Sta=4996.5,5002.5
XS Rating Curve= 0 ,0
Exp/Cntr=0.3,0.1

Type RM Length L Ch R = 1 ,6409    ,44,44,44
BEGIN DESCRIPTION:
PHIFER CREEK 8.1
END DESCRIPTION:
XS GIS Cut Line= 4
      3486706.76     10518253.81      3486659.88     10517938.71
      3486657.28     10517443.92      3487096.73      10516455.8
#Sta/Elev= 30
  4234.2  438.25  4240.9  438.15  4448.7   438.9  4629.8   437.1  4699.8  433.46
  4869.8  431.57  4969.8  432.45  4979.8  430.16  4989.8  425.18  4996.8  424.47
  4999.6  423.97  5002.8  424.47  5009.8  427.96  5019.8  429.13  5039.8  427.64
  5074.6   429.5  5237.6  430.17  5301.5  430.83  5378.4  431.59    5411  434.11
  5486.2  433.06  5695.8   441.6    5984  448.17  6053.8  447.28  6059.3  448.68
    6077  447.75  6082.5  449.12  6100.3  448.11  6105.8  449.88    6129  448.44
#Mann= 6 ,-1 , 0
  4234.2     .16       0  4240.9     .05       0  4996.8    .035       0
  5002.8     .05       0  5237.6     .16       0  5301.5     .05       0
Bank Sta=4996.8,5002.8
XS Rating Curve= 0 ,0
Exp/Cntr=0.3,0.1

Type RM Length L Ch R = 1 ,6365    ,97,97,97
BEGIN DESCRIPTION:
PHIFER CREEK 8.0
END DESCRIPTION:
XS GIS Cut Line= 5
      3486753.64     10518240.83      3486704.16     10517923.08
      3486701.55     10517420.48      3486813.53     10517141.83
      3487133.85     10516462.13
#Sta/Elev= 30
  4246.8  436.62  4256.7  436.67  4356.6  437.07  4438.3  439.01  4546.9  438.02
  4629.8  433.99  4699.8  434.16  4969.8  429.74  4979.8  429.17  4996.8  425.03
  4999.6  424.53  5002.8  425.03  5009.8  428.88  5019.8  429.49  5134.3  429.93
  5139.7  431.35  5163.8  430.01  5169.2  431.08  5241.8   430.4  5497.8  435.34
  5515.1     437  5520.6  435.79  5543.4  437.97  5548.9  436.83  5617.3  437.51
  5896.2  446.04    5919   448.4  5992.8   448.5    6068  451.22  6122.7  451.54
#Mann= 5 ,-1 , 0
  4246.8     .05       0  4256.7     .16       0  4356.6     .05       0
  4996.8    .035       0  5002.8     .05       0
Bank Sta=4996.8,5002.8
XS Rating Curve= 0 ,0
Exp/Cntr=0.3,0.1

Type RM Length L Ch R = 1 ,6268    ,34,34,34
BEGIN DESCRIPTION:
PHIFER CREEK 6.0
END DESCRIPTION:
XS GIS Cut Line= 6
      3486866.48     10518314.15      3486790.09      10517998.6
      3486797.91     10517540.27      3486797.91     10517386.63
      3486951.55     10517011.63      3487227.34     10516480.86
#Sta/Elev= 30
  4158.4  437.91  4274.2   435.8  4294.7  434.47  4305.4   434.9  4315.3  435.27
  4341.9  434.26    4377  433.99  4438.8  436.39    4500  436.44  4840.1  429.72
  4930.1  429.84  4960.1  432.34  4970.1  431.97  4980.1  430.51  4990.1  427.94
  4997.1  423.31  4999.8  422.81  5003.1  423.31  5010.1  423.73  5020.1  427.69
  5040.1  430.32    5361  433.97  5669.6  446.32  5724.7  447.67  5752.4  449.55
  5885.1  452.74  5901.6  452.45  5907.2   453.3  5951.5  454.91  6098.5  456.66
#Mann= 5 ,-1 , 0
  4158.4     .05       0  4305.4     .16       0  4341.9     .05       0
  4997.1     .04       0  5003.1     .05       0
Bank Sta=4997.1,5003.1
XS Rating Curve= 0 ,0
Exp/Cntr=0.3,0.1

Type RM Length L Ch R = 1 ,6234    ,883,883,883
BEGIN DESCRIPTION:
PHIFER CREEK 6.1
END DESCRIPTION:
XS GIS Cut Line= 5
      3486899.47     10518303.28      3486818.74     10517982.98
      3486834.36     10517389.23       3486980.2     10517032.46
      3487243.16     10516506.54
#Sta/Elev= 30
  4169.2  438.17  4300.7   436.5  4346.9  434.58  4418.4  433.04  4429.1  434.61
  4470.2  436.57  4510.9  436.46  4540.9  434.64  4570.9  435.06    4831  429.44
    4901  429.64    4971  431.47    4981  427.39    4988  423.03  4990.8  422.53
    4994  423.03    5001  423.54    5021  427.55    5031  428.29    5051  427.88
  5071.1  430.19  5229.4  431.75  5365.7  434.69  5419.1  436.39  5562.5  443.77
  5741.4  450.94  5825.3  452.38  5853.2  453.99  5942.7  456.54  6066.9  457.21
#Mann= 3 ,-1 , 0
  4169.2     .05       0    4988     .04       0    4994     .05       0
#XS Ineff= 2 , 0
         4503.67  436.47
Permanent Ineff=
       F       F
Bank Sta=4971,5071.1
XS Rating Curve= 0 ,0
Exp/Cntr=0.3,0.1

Type RM Length L Ch R = 1 ,5351    ,1308,1308,1308
BEGIN DESCRIPTION:
PHIFER CREEK 5.0
END DESCRIPTION:
XS GIS Cut Line= 6
      3487030.75     10518851.83      3487456.11     10517907.79
      3487330.24     10517679.92      3487664.44     10517124.37
      3487670.95     10517128.71      3487686.14     10517039.71
#Sta/Elev= 30
  3840.1   440.7  4052.3  437.81  4673.9  433.48    4808  431.15    4913  427.52
  4978.3  427.92  4985.4  426.96  4994.3  422.89    4997  419.96  4999.8  419.46
    5003  419.96  5021.8  427.74  5043.6   428.7    5193  428.27  5224.1  429.01
  5266.8  428.35  5507.3  431.54    5624  437.99  5653.4  441.24  5690.3  443.45
  5696.1  443.09  5727.2  445.89    5733  444.27  5748.5     447  5754.4  446.12
  5769.9  447.25  5787.8  450.56  5790.2  449.91  5826.6  452.59  5882.3   455.2
#Mann= 3 ,-1 , 0
  3840.1     .05       0    4997    .035       0    5003     .05       0
Bank Sta=4978.3,5021.8
XS Rating Curve= 0 ,0
Exp/Cntr=0.3,0.1

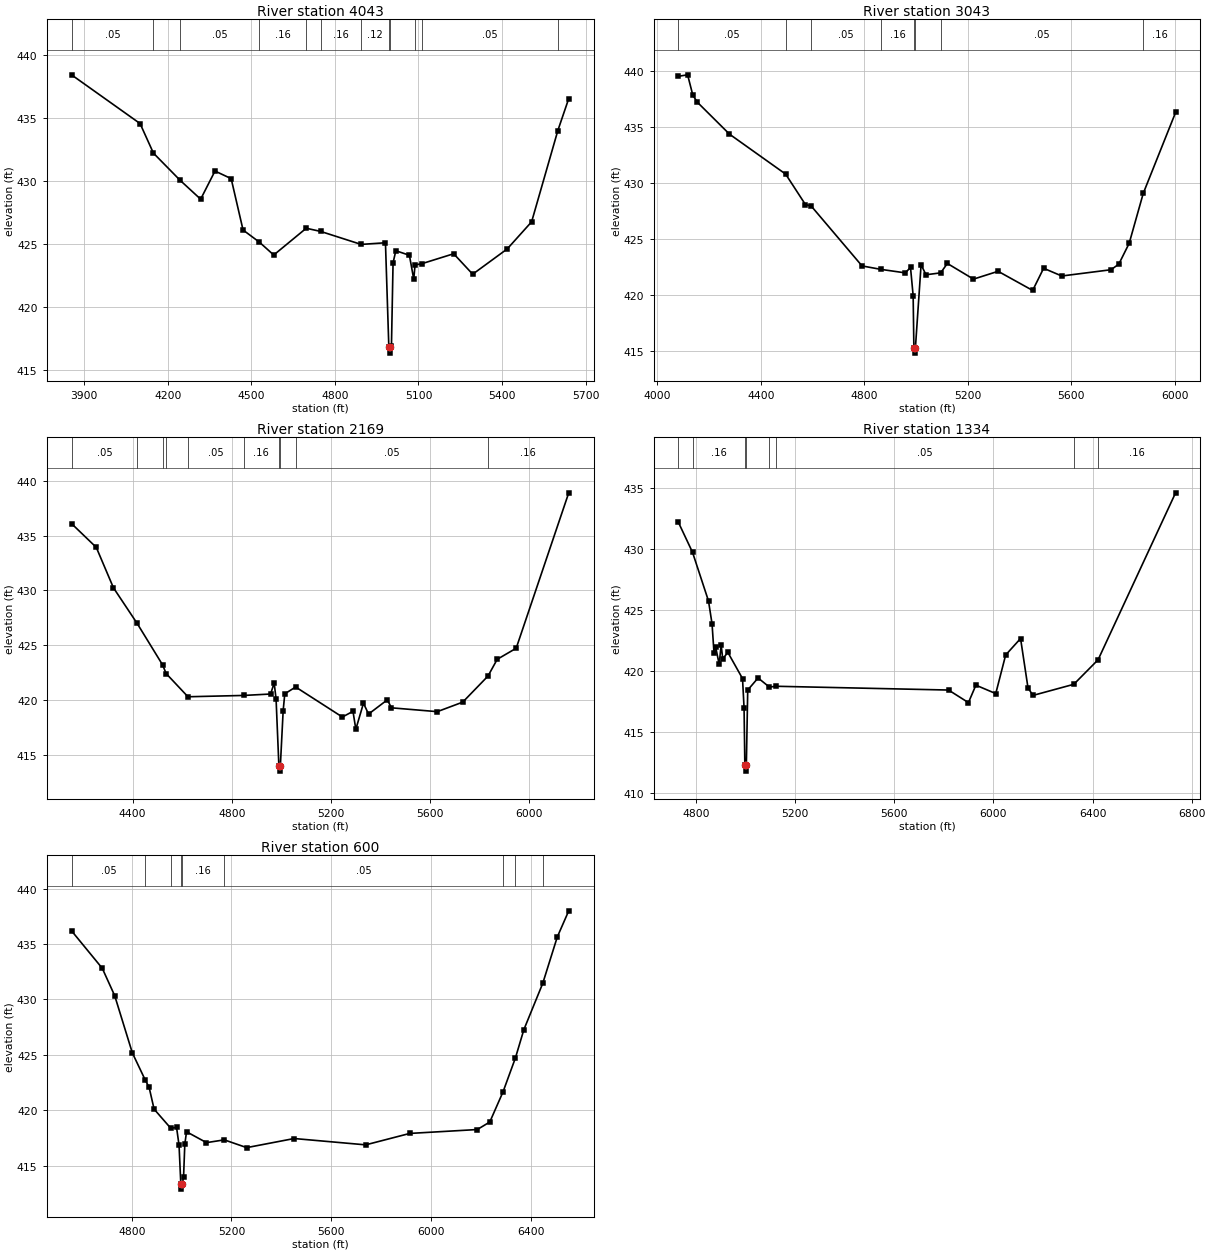
Type RM Length L Ch R = 1 ,4043    ,1000,1000,1000
BEGIN DESCRIPTION:
PHIFER CREEK 4.0
END DESCRIPTION:
XS GIS Cut Line= 4
      3487469.11     10518947.31      3488029.06     10518030.77
      3488107.15     10517896.94       3488291.6     10517371.79
#Sta/Elev= 30
    3854  438.41  4100.2  434.55  4148.1  432.21  4244.3  430.05  4317.7  428.56
  4369.2  430.79  4427.3  430.19    4470  426.12  4528.6  425.16  4580.2  424.14
  4696.9  426.26  4748.5  426.01    4894  424.98  4981.4  425.11  4993.5  416.87
  4996.3  416.37  4999.5  416.87  5002.9   416.9  5008.7  423.52  5018.6  424.48
  5067.4  424.12    5083  422.22  5087.7  423.35  5113.1  423.46  5226.4  424.24
  5294.7  422.62  5418.6  424.62  5506.3  426.77  5600.5     434  5639.6  436.53
#Mann= 12 ,-1 , 0
    3854     .05       0  4148.1     .16       0  4244.3     .05       0
  4528.6     .16       0  4696.9     .05       0  4748.5     .16       0
    4894     .12       0  4993.5     .07       0  4999.5     .12       0
  5087.7     .16       0  5113.1     .05       0  5600.5     .12       0
Bank Sta=4993.5,4999.5
XS Rating Curve= 0 ,0
Exp/Cntr=0.3,0.1

Type RM Length L Ch R = 1 ,3043    ,874,874,874
BEGIN DESCRIPTION:
PHIFER CREEK 3.0
END DESCRIPTION:
XS GIS Cut Line= 5
      3488335.01     10519196.86      3488456.54     10518435.13
      3488502.11      10518226.8      3488536.84     10517977.23
      3488487.86     10517292.58
#Sta/Elev= 30
    4081  439.55  4116.7  439.68  4136.9  437.86  4154.9  437.22  4278.7  434.38
  4495.9  430.81  4572.4  428.09  4594.7  427.96  4791.3  422.61  4864.7   422.3
  4958.3  421.99  4978.8  422.47    4989  419.96  4991.8  415.32  4994.5  414.82
  4997.8  415.32  5019.7  422.72  5038.6  421.82  5095.4  421.99  5121.3  422.83
  5222.3  421.43  5317.6  422.13  5451.2  420.42  5493.6   422.4  5563.8  421.71
  5754.3  422.27  5784.4  422.77  5824.5  424.63  5878.9  429.09    6004  436.32
#Mann= 8 ,-1 , 0
    4081     .05       0  4495.9     .16       0  4594.7     .05       0
  4864.7     .16       0  4991.8     .07       0  4997.8     .16       0
  5095.4     .05       0  5878.9     .16       0
Bank Sta=4991.8,4997.8
XS Rating Curve= 0 ,0
Exp/Cntr=0.3,0.1

Type RM Length L Ch R = 1 ,2169    ,835,835,835
BEGIN DESCRIPTION:
PHIFER CREEK 2.0
END DESCRIPTION:
XS GIS Cut Line= 4
      3488664.86     10519051.49      3488910.81     10518335.54
      3489018.61     10518209.44      3489261.83     10517155.15
#Sta/Elev= 30
    4154  436.09  4253.8  433.92    4323  430.23  4418.8  426.97  4521.2  423.19
  4535.5   422.4  4623.5  420.28  4847.8   420.4  4956.8  420.53  4971.1  421.55
  4978.8  420.07  4990.1  413.99  4992.8  413.49  4996.1  413.99  5007.4  419.02
  5013.9  420.55  5057.8  421.17  5246.1  418.43  5288.9  418.95  5300.4  417.31
  5331.2  419.69  5351.7   418.7  5427.4     420  5444.1  419.27  5628.8  418.92
  5731.5  419.79  5833.3  422.17  5870.5   423.7    5947  424.71  6158.9   438.9
#Mann= 10 ,-1 , 0
    4154     .05       0  4418.8     .16       0  4521.2     .05       0
  4535.5     .16       0  4623.5     .05       0  4847.8     .16       0
  4990.1     .07       0  4996.1     .16       0  5057.8     .05       0
  5833.3     .16       0
Bank Sta=4990.1,4996.1
XS Rating Curve= 0 ,0
Exp/Cntr=0.3,0.1

Type RM Length L Ch R = 1 ,1334    ,734,734,734
BEGIN DESCRIPTION:
PHIFER CREEK 1.0
END DESCRIPTION:
XS GIS Cut Line= 5
       3488808.1     10519079.67      3488949.16     10518964.64
      3489075.03     10518786.69      3489294.21     10518380.88
       3489369.8     10517237.08
#Sta/Elev= 30
  4727.7  432.21  4784.8  429.75  4849.4  425.76  4863.7  423.88  4871.6  421.49
  4878.1     422  4892.4  420.58  4900.4  422.16  4906.8  421.03  4927.6  421.55
  4986.7  419.41  4992.9  417.01  4996.1  412.33  4998.9  411.83  5002.1  412.33
  5007.7  418.47  5049.5  419.46  5095.3  418.71  5120.4  418.78  5818.6  418.47
  5898.8  417.44  5928.9  418.87  6009.1  418.18  6049.1  421.34  6109.3  422.69
  6139.3  418.65  6159.4  418.03  6324.2  418.94  6422.3  420.95  6735.2  434.62
#Mann= 8 ,-1 , 0
  4727.7     .05       0  4784.8     .16       0  4996.1     .07       0
  5002.1     .16       0  5095.3     .12       0  5120.4     .05       0
  6324.2     .12       0  6422.3     .16       0
Bank Sta=4996.1,5002.1
XS Rating Curve= 0 ,0
Exp/Cntr=0.3,0.1

Type RM Length L Ch R = 1 ,600     ,0,0,0
BEGIN DESCRIPTION:
MONTGOMERY CREEK 35.0
END DESCRIPTION:
XS GIS Cut Line= 5
      3489200.93     10519303.16      3489443.95     10519116.55
      3489430.93     10518838.78      3489493.87     10518417.77
      3489571.13     10517435.77
#Sta/Elev= 30
  4558.2  436.19  4681.6  432.81  4731.5  430.34  4802.2  425.19  4854.7  422.71
  4869.6  422.08  4889.5  420.12  4956.7  418.39  4979.6  418.48  4989.6  416.88
  4996.7  413.41  4999.4  412.91  5002.7  413.41  5007.8  414.03  5012.8  416.96
  5019.7  418.08  5099.8   417.1  5171.3  417.35  5261.1  416.65  5451.6  417.47
  5738.6   416.9  5915.6  417.93  6186.4  418.28  6236.6  418.96  6289.8  421.68
  6339.7  424.75  6373.3  427.28  6449.2  431.46  6507.4  435.63  6553.4  437.99
#Mann= 9 ,-1 , 0
  4558.2     .05       0  4854.7     .12       0  4956.7     .16       0
  4996.7     .07       0  5002.7     .16       0  5171.3     .05       0
  6289.8     .16       0  6339.7     .12       0  6449.2     .16       0
Bank Sta=4996.7,5002.7
XS Rating Curve= 0 ,0
Exp/Cntr=0.3,0.1

Chan Stop Cuts=-1
Use User Specified Reach Order=0
Composite Channel Slope=5