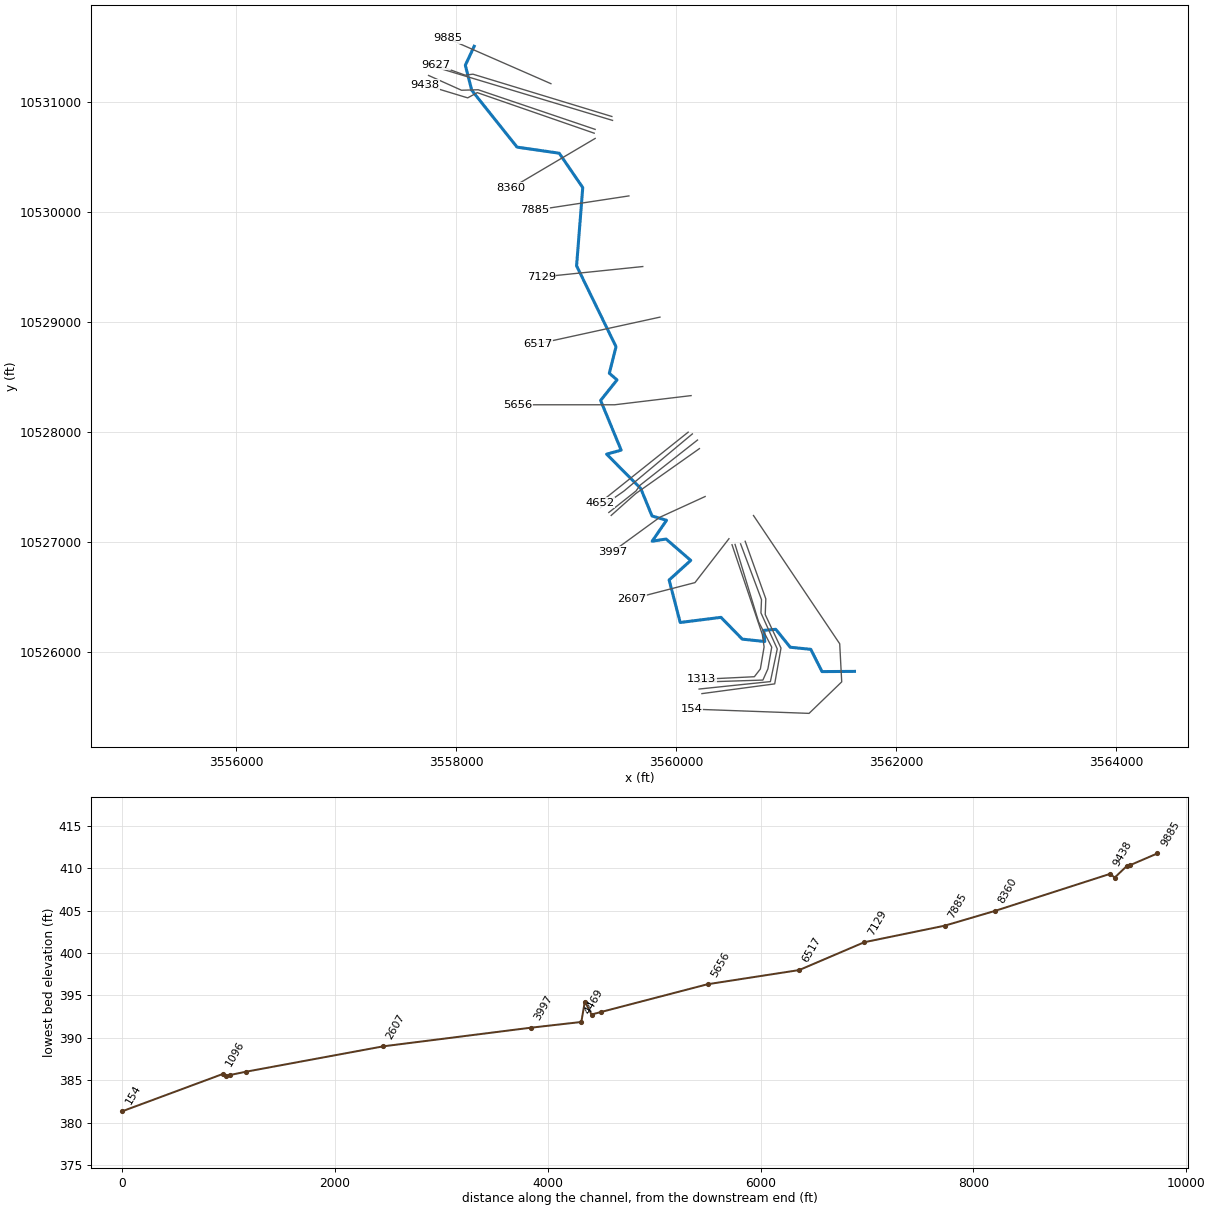
--- PINOAK CREEK.prj (project) ---

Proj Title=PINOAK CREEK Base Level Engineering
Current Plan=p01
Default Exp/Contr=0.3,0.1
English Units
Geom File=g01
Flow File=f01
Plan File=p01
Y Axis Title=Elevation
X Axis Title(PF)=Main Channel Distance
X Axis Title(XS)=Station
BEGIN DESCRIPTION:
PINOAK CREEK
END DESCRIPTION:
DSS Export Rating Curves= 0
DSS Export Rating Curve Sorted= 0
DSS Export Volume Flow Curves= 0
DXF OffsetX= 0
DXF OffsetY= 0
DXF ScaleX= 1
DXF ScaleY= 10

--- PINOAK CREEK.p01 (plan) ---

Plan Title=Multiple Run
Short Identifier=Multiple
Geom File=g01
Flow File=f01
Subcritical Flow
K Sum by GR= 0
Std Step Tol= 0.01
Critical Tol= 0.01
Num of Std Step Trials= 20
Max Error Tol= 0.3
Flow Tol Ratio= 0.001
Split Flow NTrial= 30
Split Flow Tol= 0.02
Split Flow Ratio= 0.02
Log Output Level= 0
Friction Slope Method= 1
Unsteady Friction Slope Method= 2
Unsteady Bridges Friction Slope Method= 1
Parabolic Critical Depth
Global Vel Dist=  1 , 1 , 1
Global Log Level= 0
CheckData=True
Encroach Param= -1, 0, 0, 0
BEGIN DESCRIPTION:
Multiple Run
END DESCRIPTION:

--- PINOAK CREEK.f01 (steady flow) ---

Flow Title=Multiple
Number of Profiles=7
Profile Names=10-year,25-year,50-year,1pct_min,100-year,1pct_plu,500-year
River Rch & RM= PINOAK CREEK,Reach-1,9885
     970    1323    1612    1432    1937    2619    2788
River Rch & RM= PINOAK CREEK,Reach-1,9484
    1304    1801    2213    1981    2679    3623    3914
Boundary for River Rch & Prof#=PINOAK CREEK,Reach-1,1
Up Type=0
Dn Type=3
Dn Slope=0.005
Boundary for River Rch & Prof#=PINOAK CREEK,Reach-1,2
Up Type=0
Dn Type=3
Dn Slope=0.005
Boundary for River Rch & Prof#=PINOAK CREEK,Reach-1,3
Up Type=0
Dn Type=3
Dn Slope=0.005
Boundary for River Rch & Prof#=PINOAK CREEK,Reach-1,4
Up Type=0
Dn Type=3
Dn Slope=0.005
Boundary for River Rch & Prof#=PINOAK CREEK,Reach-1,5
Up Type=0
Dn Type=3
Dn Slope=0.005
Boundary for River Rch & Prof#=PINOAK CREEK,Reach-1,6
Up Type=0
Dn Type=3
Dn Slope=0.005
Boundary for River Rch & Prof#=PINOAK CREEK,Reach-1,7
Up Type=0
Dn Type=3
Dn Slope=0.005

--- PINOAK CREEK.g01 (geometry) ---

Geom Title=Existing Conditions
Program Version=4.10

River Reach=PINOAK CREEK    ,Reach-1
Reach XY= 30
      3558162.19     10531509.21       3558081.6     10531336.55
      3558139.93     10531108.78      3558551.89     10530591.82
      3558935.09     10530536.61      3559149.21     10530224.05
        3559093.      10529512.4      3559451.74     10528776.49
      3559390.71     10528535.45      3559460.85     10528475.04
      3559311.55     10528288.23      3559498.35     10527836.15
      3559366.41     10527799.34      3559676.13     10527487.54
      3559778.91     10527237.54      3559910.85     10527197.95
       3559780.3     10527007.68      3559906.68     10527027.82
      3560130.99     10526833.37      3559934.46      10526654.9
      3560035.16     10526268.79      3560405.99     10526315.32
      3560599.54     10526117.14      3560803.79     10526095.61
      3560794.76     10526197.35      3560904.14     10526206.37
      3561035.74     10526043.53      3561222.54     10526024.43
      3561324.28       10525822.      3561619.63     10525824.04

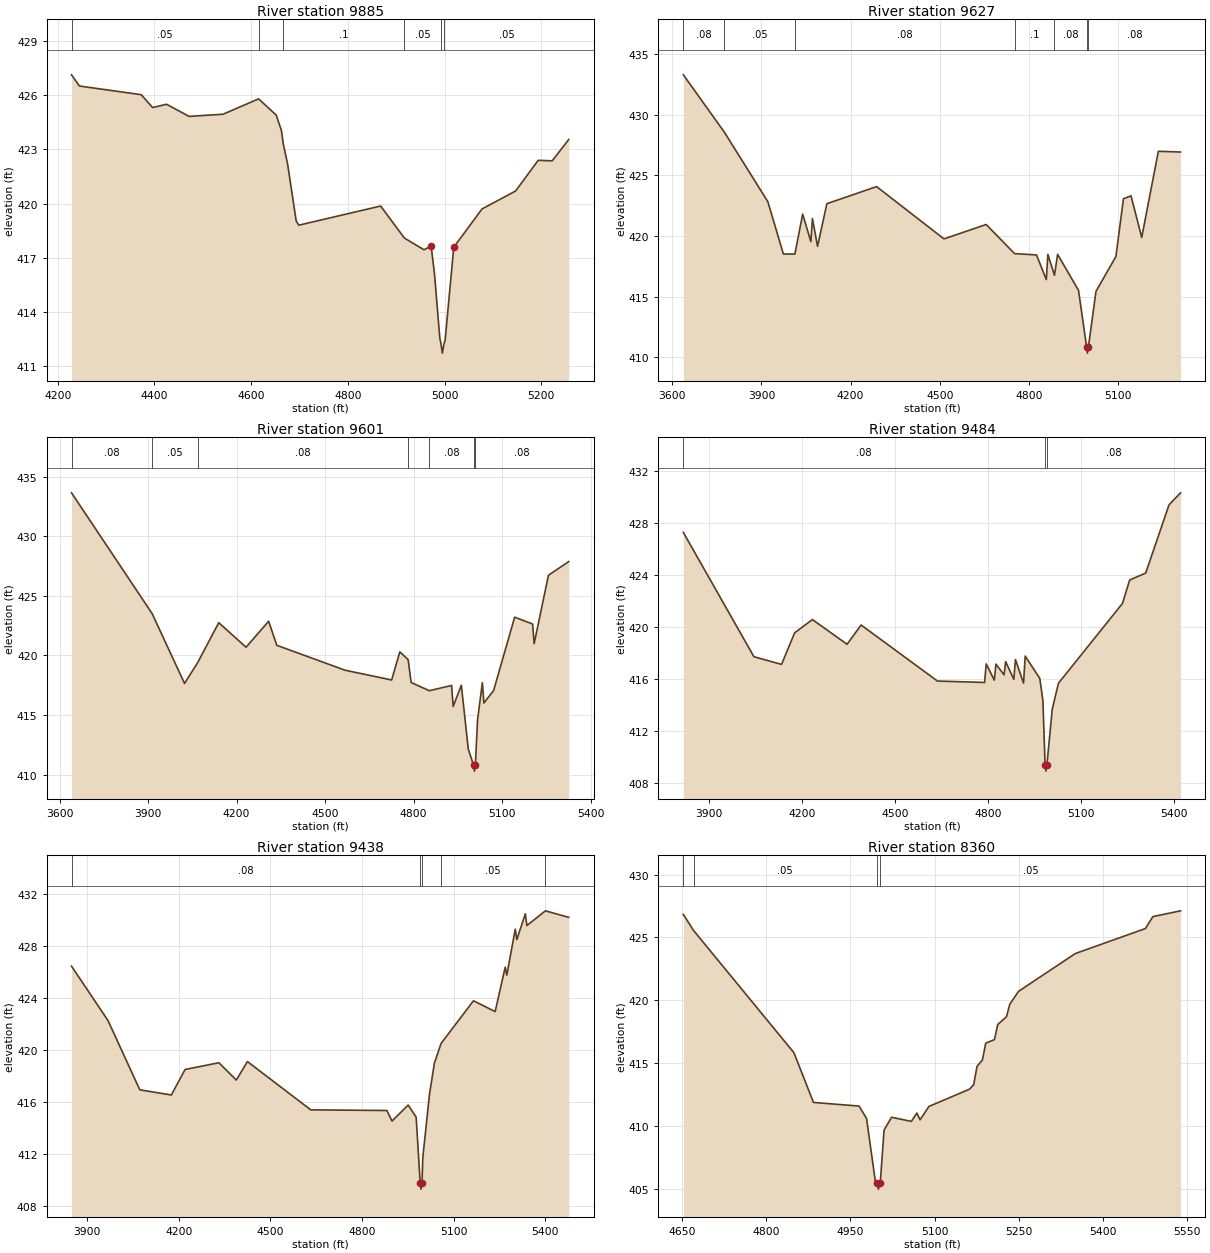
Type RM Length L Ch R = 1 ,9885    ,258,258,258
BEGIN DESCRIPTION:
PINOAK CREEK 16.4
END DESCRIPTION:
XS GIS Cut Line= 2
      3558859.73     10531169.02      3557917.93     10531581.33
#Sta/Elev= 30
  4228.7  427.13  4245.1  426.51  4372.9  426.03  4396.3  425.32  4425.2   425.5
  4471.9  424.83  4542.1  424.95  4615.5   425.8    4652   424.9  4662.8  424.04
  4666.6   423.3  4675.4  422.21  4693.3  419.04  4698.7  418.81  4867.9  419.87
  4916.9   418.1  4957.5  417.45  4972.3  417.65  4979.3   416.1  4990.2  412.57
  4992.7  412.23  4995.5  411.73  4998.7  412.23  5001.2  412.44  5019.1  417.59
  5077.6  419.71  5146.9   420.7  5193.7   422.4  5222.6  422.37  5256.8  423.55
#Mann= 6 ,-1 , 0
  4228.7     .05       0  4615.5     .08       0  4666.6      .1       0
  4916.9     .05       0  4992.7     .03       0  4998.7     .05       0
Bank Sta=4972.3,5019.1
XS Rating Curve= 0 ,0
Exp/Cntr=0.3,0.1

Type RM Length L Ch R = 1 ,9627    ,26,26,26
BEGIN DESCRIPTION:
PINOAK CREEK 16.3
END DESCRIPTION:
XS GIS Cut Line= 4
      3559413.87     10530870.57      3558151.21     10531255.23
      3558079.59     10531246.55      3557816.01     10531341.61
#Sta/Elev= 30
  3637.6  433.27  3775.4  428.55  3921.7  422.82    3974  418.51  4012.7   418.5
  4038.9  421.79  4066.5  419.53  4071.7  421.43    4089  419.14  4120.3  422.65
  4287.6  424.06  4514.3  419.75  4656.1  420.94  4751.6  418.54  4825.5  418.43
  4858.4   416.4  4863.6  418.47  4885.9  416.76  4896.4  418.48  4966.7  415.51
  4993.9  410.84  4996.7  410.34  4999.9  410.84  5025.5  415.43  5092.5   418.3
  5117.9  423.06  5143.3   423.3  5179.3  419.87  5235.3  426.97  5309.9  426.91
#Mann= 7 ,-1 , 0
  3637.6     .08       0  3775.4     .05       0  4012.7     .08       0
  4751.6      .1       0  4885.9     .08       0  4993.9     .07       0
  4999.9     .08       0
Bank Sta=4993.9,4999.9
XS Rating Curve= 0 ,0
Exp/Cntr=0.3,0.1

Type RM Length L Ch R = 1 ,9601    ,117,117,117
BEGIN DESCRIPTION:
PINOAK CREEK 16.0
END DESCRIPTION:
XS GIS Cut Line= 2
      3559419.93     10530834.99      3557806.19     10531320.84
#Sta/Elev= 30
  3640.7  433.65  3913.8  423.52  4023.8  417.65  4067.9  419.38  4139.7  422.75
  4232.3  420.69  4308.8  422.87  4336.6  420.85  4567.9  418.76  4725.8  417.94
  4753.5   420.3  4781.7  419.65  4791.8  417.73  4853.3  417.04    4929  417.48
  4934.3  415.72    4962   417.5  4985.6  412.13  5003.5  410.79  5006.3  410.29
  5009.5  410.79    5017  414.61  5033.3  417.71  5038.5  416.01  5071.5  417.06
  5142.7  423.21  5203.5  422.64  5208.8  420.99  5257.2  426.73    5326  427.88
#Mann= 7 ,-1 , 0
  3640.7     .08       0  3913.8     .05       0  4067.9     .08       0
  4781.7      .1       0  4853.3     .08       0  5003.5     .07       0
  5009.5     .08       0
Bank Sta=5003.5,5009.5
XS Rating Curve= 0 ,0
Exp/Cntr=0.3,0.1

Type RM Length L Ch R = 1 ,9484    ,46,46,46
BEGIN DESCRIPTION:
PINOAK CREEK 16.1
END DESCRIPTION:
XS GIS Cut Line= 4
      3559261.97     10530753.38      3558198.59     10531113.63
      3558046.68     10531109.29      3557747.23     10531243.82
#Sta/Elev= 30
    3818  427.25  4045.6  417.69  4134.6   417.1  4176.8  419.53  4234.1  420.55
  4345.8  418.65  4391.2  420.13  4637.3  415.82  4789.1  415.71  4794.4  417.14
  4820.5  415.89  4825.8  417.12    4852   416.3  4857.2  417.31  4883.4  415.95
  4888.7  417.47  4914.8  415.66  4920.1  417.74  4967.2  416.02  4977.2  414.31
  4984.2  409.39    4987  408.89  4990.2  409.39  5007.3  413.65  5027.3  415.65
  5233.7  421.79  5256.9  423.59  5308.7  424.13  5383.7  429.37    5421   430.3
#Mann= 3 ,-1 , 0
    3818     .08       0  4984.2     .07       0  4990.2     .08       0
Bank Sta=4984.2,4990.2
XS Rating Curve= 0 ,0
Exp/Cntr=0.3,0.1

Type RM Length L Ch R = 1 ,9438    ,1078,1078,1078
BEGIN DESCRIPTION:
PINOAK CREEK 16.2
END DESCRIPTION:
XS GIS Cut Line= 4
      3559253.27     10530718.67      3558189.91     10531087.59
       3558103.1     10531039.84      3557717.56     10531156.81
#Sta/Elev= 30
  3848.8  426.44  3968.2  422.26  4072.3  416.94  4175.5  416.54  4220.5   418.5
  4331.2  419.02  4388.2  417.69  4424.6  419.11  4631.9   415.4    4881  415.35
  4897.9  414.54  4950.8  415.77  4976.9  414.84    4990  409.81  4992.7  409.31
    4996  409.81  4998.7  411.75  5020.5  416.59  5036.6  418.99  5058.4   420.5
  5164.5  423.78  5235.5  422.95  5268.4  426.36  5273.6  425.75  5301.3  429.28
  5306.5  428.48  5334.2  430.46  5339.4  429.56    5400  430.69  5476.3  430.19
#Mann= 5 ,-1 , 0
  3848.8     .08       0    4990     .07       0    4996     .08       0
  5058.4     .05       0    5400     .08       0
Bank Sta=4990,4996
XS Rating Curve= 0 ,0
Exp/Cntr=0.3,0.1

Type RM Length L Ch R = 1 ,8360    ,475,475,475
BEGIN DESCRIPTION:
PINOAK CREEK 14.0
END DESCRIPTION:
XS GIS Cut Line= 2
        3559262.     10530670.94       3558498.1     10530219.55
#Sta/Elev= 30
  4651.8  426.82  4670.1  425.54  4849.1  415.82    4884  411.86  4965.3  411.57
  4978.7  410.59  4994.4  405.59  4997.2  405.46  4999.9  404.96  5003.2  405.46
    5010  409.66  5023.4  410.68  5058.7  410.35  5068.5  411.01  5074.3  410.48
    5090  411.54  5162.7  412.92  5169.9  413.27  5175.8  414.72  5185.6  415.25
  5191.4  416.58    5207  416.86  5212.8  418.06  5228.5  418.68  5234.3  419.67
  5249.9   420.7  5351.3  423.71  5476.4   425.7  5489.8  426.65  5539.1  427.11
#Mann= 4 ,-1 , 0
  4651.8     .08       0  4670.1     .05       0  4997.2     .03       0
  5003.2     .05       0
Bank Sta=4997.2,5003.2
XS Rating Curve= 0 ,0
Exp/Cntr=0.3,0.1

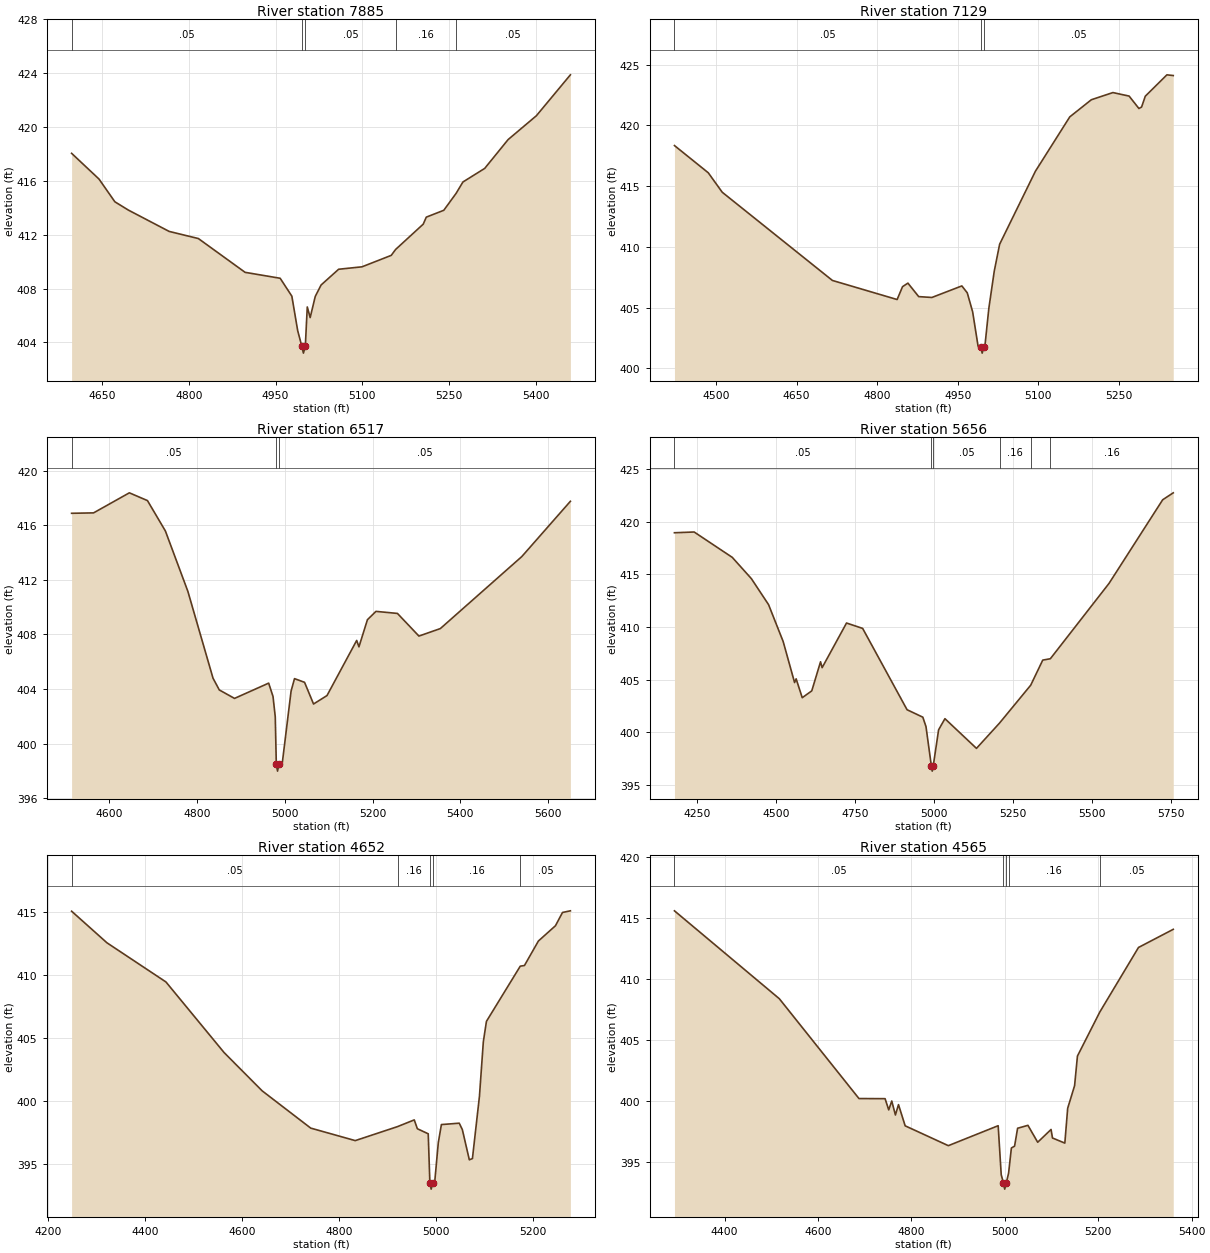
Type RM Length L Ch R = 1 ,7885    ,756,756,756
BEGIN DESCRIPTION:
PINOAK CREEK 12.0
END DESCRIPTION:
XS GIS Cut Line= 2
      3559568.99     10530148.25      3558715.53     10530018.28
#Sta/Elev= 30
  4597.1  418.05  4644.5  416.14    4672  414.45  4695.1  413.84  4765.9  412.25
  4816.5  411.72  4897.4  409.21  4958.1  408.77  4978.3  407.44  4988.4  404.88
  4995.6  403.71  4998.3  403.21  5001.6  403.71    5005  406.64    5010  405.85
  5018.8  407.42  5028.9  408.27  5059.3  409.44  5099.7  409.62  5150.3  410.47
  5157.9  410.91  5205.7  412.79    5211  413.31  5241.3  413.82  5262.5  415.07
  5274.4  415.92  5312.1  416.93  5352.6  419.07  5401.5  420.84  5460.4  423.88
#Mann= 5 ,-1 , 0
  4597.1     .05       0  4995.6     .03       0  5001.6     .05       0
  5157.9     .16       0  5262.5     .05       0
Bank Sta=4995.6,5001.6
XS Rating Curve= 0 ,0
Exp/Cntr=0.3,0.1

Type RM Length L Ch R = 1 ,7129    ,612,612,612
BEGIN DESCRIPTION:
PINOAK CREEK 10.0
END DESCRIPTION:
XS GIS Cut Line= 2
      3559694.81     10529505.88      3558770.33     10529410.39
#Sta/Elev= 30
  4422.3  418.34  4485.3   416.1  4511.3   414.5  4716.6  407.24  4837.2  405.67
  4847.3  406.73  4857.3  407.02  4877.4  405.91    4902  405.84  4957.8  406.79
  4967.9  406.22  4977.9  404.66    4988  401.84  4992.9  401.76  4995.7  401.26
  4998.9  401.76    5001  401.95  5008.1  404.95  5018.2  408.01  5028.2  410.22
  5094.9  416.23  5158.9   420.7  5199.1  422.11  5239.3   422.7  5269.5  422.41
  5287.7  421.39  5292.7  421.51  5299.6   422.4  5339.9  424.16  5351.7   424.1
#Mann= 3 ,-1 , 0
  4422.3     .05       0  4992.9     .03       0  4998.9     .05       0
Bank Sta=4992.9,4998.9
XS Rating Curve= 0 ,0
Exp/Cntr=0.3,0.1

Type RM Length L Ch R = 1 ,6517    ,861,861,861
BEGIN DESCRIPTION:
PINOAK CREEK 9.0
END DESCRIPTION:
XS GIS Cut Line= 2
      3559851.08     10529045.81      3558739.95     10528802.75
#Sta/Elev= 30
  4513.7  416.88  4563.8  416.91  4645.4  418.38  4686.7  417.81  4727.6  415.58
  4778.8  411.16  4836.2  404.79  4850.5  403.93  4885.2  403.31  4963.1  404.43
    4973  403.45  4978.1  401.96  4980.5  398.48  4983.3  397.98  4986.5  398.48
  4993.8  398.49  5014.2  403.85    5022  404.76  5044.9  404.49  5065.4   402.9
  5096.1  403.52  5163.8  407.56  5168.9  407.09  5188.3  409.08  5207.7  409.69
  5256.7  409.54  5305.7  407.88  5354.6  408.43  5540.4  413.71  5651.1  417.76
#Mann= 3 ,-1 , 0
  4513.7     .05       0  4980.5     .03       0  4986.5     .05       0
Bank Sta=4980.5,4986.5
XS Rating Curve= 0 ,0
Exp/Cntr=0.3,0.1

Type RM Length L Ch R = 1 ,5656    ,1004,1004,1004
BEGIN DESCRIPTION:
PINOAK CREEK 7.0
END DESCRIPTION:
XS GIS Cut Line= 3
      3560134.13     10528332.04      3559438.81      10528248.7
      3558558.61      10528248.7
#Sta/Elev= 30
  4177.6  418.94  4240.1  419.01  4360.9   416.6  4421.4  414.58  4475.9  412.11
  4522.1  408.61  4558.2  404.72  4563.2  405.07  4582.5  403.28  4612.7  403.93
  4640.5  406.69  4645.5  406.13  4722.8  410.37  4773.9  409.86  4914.6  402.14
  4964.6  401.43  4974.6  400.54  4991.6  396.81  4994.4  396.31  4997.6  396.81
  5014.6  400.23  5034.6  401.29  5134.6  398.47  5207.6  400.87  5306.5  404.47
  5344.6  406.85  5368.7  406.98  5554.6  414.13  5724.6  422.07  5758.1  422.73
#Mann= 6 ,-1 , 0
  4177.6     .05       0  4991.6     .03       0  4997.6     .05       0
  5207.6     .16       0  5306.5     .05       0  5368.7     .16       0
Bank Sta=4991.6,4997.6
XS Rating Curve= 0 ,0
Exp/Cntr=0.3,0.1

Type RM Length L Ch R = 1 ,4652    ,87,87,87
BEGIN DESCRIPTION:
PINOAK CREEK 6.2
END DESCRIPTION:
XS GIS Cut Line= 2
      3560107.48      10527999.4      3559303.63     10527357.01
#Sta/Elev= 30
  4248.6  415.03  4321.5  412.53  4443.2  409.43  4563.2  403.84  4641.7  400.81
  4741.9  397.86  4833.8  396.87  4921.1  397.98  4955.5  398.51  4961.9  397.81
  4984.3  397.41  4987.7  393.53  4990.4  393.03  4993.7  393.53  4997.9  393.68
  5005.1  396.71  5011.5  398.14  5048.3  398.25  5054.7  397.74  5069.1  395.35
  5075.5  395.45    5090  400.39    5098   404.7  5104.4  406.31  5174.2  410.68
  5182.8  410.73  5211.6  412.67  5246.8  413.88  5261.3  414.93  5277.6  415.06
#Mann= 5 ,-1 , 0
  4248.6     .05       0  4921.1     .16       0  4987.7     .07       0
  4993.7     .16       0  5174.2     .05       0
Bank Sta=4987.7,4993.7
XS Rating Curve= 0 ,0
Exp/Cntr=0.3,0.1

Type RM Length L Ch R = 1 ,4565    ,63,63,63
BEGIN DESCRIPTION:
PINOAK CREEK 6.0
END DESCRIPTION:
XS GIS Cut Line= 3
       3560145.6     10527983.71      3559522.37     10527462.91
      3559313.21     10527315.98
#Sta/Elev= 30
  4292.8   415.6  4517.3  408.38  4687.8  400.18  4743.7  400.17  4751.5  399.25
    4758  399.98  4765.8  398.83  4772.4  399.68  4786.7  397.94  4879.1  396.31
  4985.8  397.95  4992.3  393.93  4997.1  393.24  4999.8  392.74  5003.1  393.24
  5008.1  394.05  5014.1  396.12  5020.9  396.27  5027.4  397.74  5049.5  397.98
  5070.4  396.59    5099  397.64  5102.1  396.94  5128.5  396.52  5134.6  399.38
  5149.4  401.24  5155.5  403.67  5203.4  407.29  5286.2  412.59  5360.6  414.08
#Mann= 5 ,-1 , 0
  4292.8     .05       0  4997.1     .03       0  5003.1     .05       0
  5008.1     .16       0  5203.4     .05       0
Bank Sta=4997.1,5003.1
XS Rating Curve= 0 ,0
Exp/Cntr=0.3,0.1

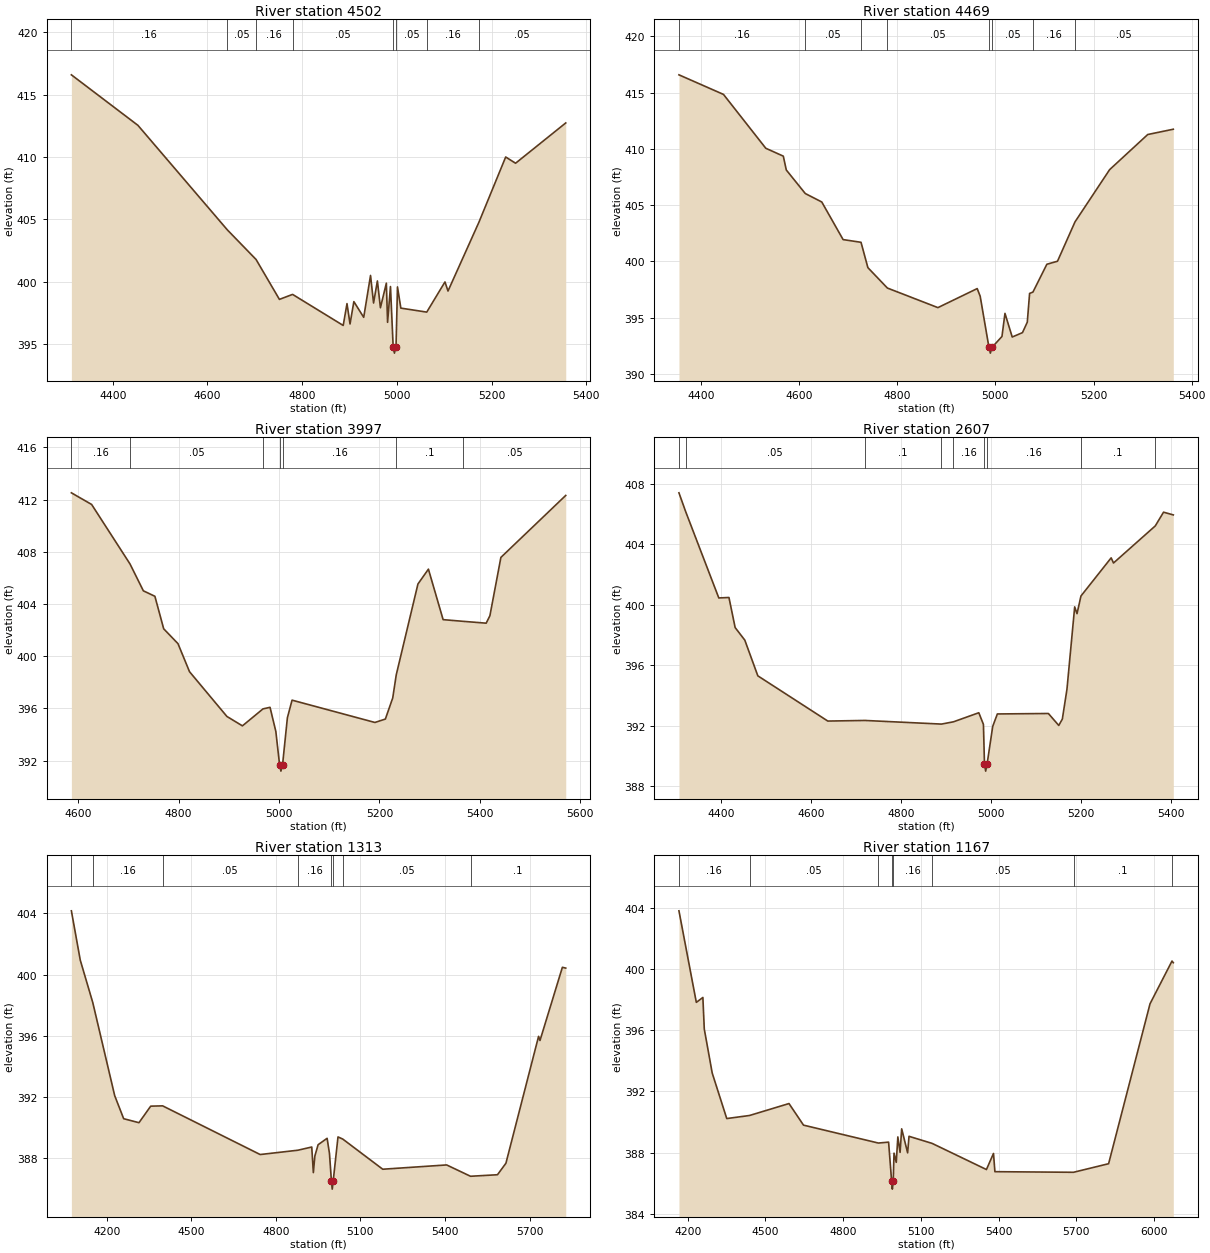
Type RM Length L Ch R = 1 ,4502    ,33,33,33
BEGIN DESCRIPTION:
PINOAK CREEK 6.1
END DESCRIPTION:
XS GIS Cut Line= 4
      3560192.52      10527928.2      3559669.94     10527516.73
      3559633.49     10527464.65      3559386.18     10527269.22
#Sta/Elev= 30
  4312.7  416.59  4453.2  412.54  4641.9  404.16  4702.7  401.78    4752  398.58
  4779.8  398.98  4886.7  396.49  4894.7  398.24  4901.1  396.61  4909.2   398.4
    4930  397.14  4944.4   400.5  4950.8  398.29  4958.9  400.06  4965.3  397.91
  4977.8  399.88  4980.4  396.74  4986.5  399.61  4992.2  394.77  4994.9  394.27
  4998.2  394.77  5001.3  399.58  5008.4  397.88  5063.1  397.56  5101.6  399.98
    5108  399.25  5173.2  404.76  5229.8     410  5250.7   409.5  5356.6  412.73
#Mann= 8 ,-1 , 0
  4312.7     .16       0  4641.9     .05       0  4702.7     .16       0
  4779.8     .05       0  4992.2     .03       0  4998.2     .05       0
  5063.1     .16       0  5173.2     .05       0
Bank Sta=4992.2,4998.2
XS Rating Curve= 0 ,0
Exp/Cntr=0.3,0.1

Type RM Length L Ch R = 1 ,4469    ,472,472,472
BEGIN DESCRIPTION:
PINOAK CREEK 6.3
END DESCRIPTION:
XS GIS Cut Line= 3
      3560209.87     10527850.06      3559630.01     10527440.34
      3559407.78     10527242.41
#Sta/Elev= 30
    4355  416.57  4445.8  414.83    4532  410.05  4567.7  409.35  4573.8  408.12
  4612.5  406.03  4646.1  405.28  4689.6  401.94  4726.1   401.7  4740.1  399.45
  4779.8  397.64  4882.8   395.9  4962.9  397.59    4969  396.91  4986.9  392.36
  4989.7  391.86  4992.9  392.36  5013.4  393.34  5019.5  395.39  5034.3  393.29
  5055.2  393.68    5065  394.61  5069.7  397.16  5076.5  397.28  5104.9  399.75
  5126.6  400.02  5162.2  403.51  5232.8  408.15  5310.5  411.27  5362.6  411.74
#Mann= 8 ,-1 , 0
    4355     .16       0  4612.5     .05       0  4726.1     .16       0
  4779.8     .05       0  4986.9     .03       0  4992.9     .05       0
  5076.5     .16       0  5162.2     .05       0
Bank Sta=4986.9,4992.9
XS Rating Curve= 0 ,0
Exp/Cntr=0.3,0.1

Type RM Length L Ch R = 1 ,3997    ,1390,1390,1390
BEGIN DESCRIPTION:
PINOAK CREEK 4.0
END DESCRIPTION:
XS GIS Cut Line= 3
      3560261.92     10527414.28      3559848.76     10527225.06
      3559419.97     10526912.58
#Sta/Elev= 30
  4586.3  412.52  4626.6  411.63  4703.1  407.07  4729.7  405.01  4752.7  404.59
  4770.2   402.1  4798.7  400.96  4821.7  398.81  4896.2  395.38  4927.1  394.66
  4968.1  395.96  4982.1  396.08  4993.7  394.23  5001.1  391.69  5003.8  391.19
  5007.1  391.69  5016.7  395.28    5026  396.63  5191.1  394.92  5211.9  395.18
  5226.6   396.8  5233.6  398.57  5276.8  405.53  5297.7  406.67    5327   402.8
  5367.1  402.67  5412.8  402.53  5420.2   403.1  5442.1  407.57  5571.3  412.32
#Mann= 7 ,-1 , 0
  4586.3     .16       0  4703.1     .05       0  4968.1     .16       0
  5001.1     .07       0  5007.1     .16       0  5233.6      .1       0
  5367.1     .05       0
Bank Sta=5001.1,5007.1
XS Rating Curve= 0 ,0
Exp/Cntr=0.3,0.1

Type RM Length L Ch R = 1 ,2607    ,1294,1294,1294
BEGIN DESCRIPTION:
PINOAK CREEK 3.0
END DESCRIPTION:
XS GIS Cut Line= 3
      3560478.39     10527030.61      3560169.37     10526631.31
        3559593.     10526482.01
#Sta/Elev= 30
  4305.6  407.39  4320.4  406.16  4394.3  400.44  4416.9  400.47  4430.7  398.48
  4452.2  397.65  4481.2  395.29  4636.9   392.3  4719.7  392.34  4889.9   392.1
  4916.6  392.25    4973  392.85  4983.3  392.08  4985.6  389.49  4988.3  388.99
  4991.6  389.49    5004  391.95  5014.3  392.77  5127.9   392.8    5151  392.01
  5158.9  392.43  5169.2   394.4  5186.4  399.85  5191.6   399.4  5200.4  400.57
  5267.6  403.09  5272.8  402.75  5365.7   405.2  5384.2  406.11  5405.9  405.93
#Mann= 9 ,-1 , 0
  4305.6     .16       0  4320.4     .05       0  4719.7      .1       0
  4889.9     .05       0  4916.6     .16       0  4985.6     .07       0
  4991.6     .16       0  5200.4      .1       0  5365.7     .05       0
Bank Sta=4985.6,4991.6
XS Rating Curve= 0 ,0
Exp/Cntr=0.3,0.1

Type RM Length L Ch R = 1 ,1313    ,146,146,146
BEGIN DESCRIPTION:
PINOAK CREEK 2.1
END DESCRIPTION:
XS GIS Cut Line= 6
      3560506.19     10526975.89      3560782.21     10526158.22
      3560797.84     10526046.24      3560763.98     10525845.72
       3560709.3     10525775.41      3560230.18     10525751.98
#Sta/Elev= 30
  4074.8  404.17  4106.3  400.95  4150.8  398.17  4228.4   392.1  4260.3  390.59
  4314.6  390.33  4356.2  391.41  4398.5  391.43  4744.5  388.25  4877.9  388.53
  4927.5  388.74  4933.2  387.07  4938.5  388.15    4950  388.89    4982  389.31
  4990.3  388.33  4997.4  386.49  5000.2  385.99  5003.4  386.49  5020.6   389.4
  5037.5  389.26  5179.3  387.29  5406.1  387.57  5490.7  386.83  5586.3  386.93
  5616.3  387.68  5732.2  395.97  5737.2   395.7  5816.6  400.48  5828.5  400.43
#Mann= 8 ,-1 , 0
  4074.8     .05       0  4150.8     .16       0  4398.5     .05       0
  4877.9     .16       0  4997.4     .07       0  5003.4     .16       0
  5037.5     .05       0  5490.7      .1       0
Bank Sta=4997.4,5003.4
XS Rating Curve= 0 ,0
Exp/Cntr=0.3,0.1

Type RM Length L Ch R = 1 ,1167    ,42,42,42
BEGIN DESCRIPTION:
PINOAK CREEK 2.0
END DESCRIPTION:
XS GIS Cut Line= 6
      3560533.93     10526978.58      3560747.92     10526274.54
      3560867.28     10526044.51      3560832.56     10525847.03
      3560786.99     10525745.03       3560192.4      10525725.5
#Sta/Elev= 30
    4166  403.79  4233.1  397.81  4258.4  398.13  4263.8  396.07  4294.5  393.19
  4350.6  390.22  4438.5  390.42  4590.9   391.2    4647  389.79  4936.2  388.62
  4975.5  388.68  4987.3  386.11    4990  385.61  4993.3  386.11  4996.4  387.96
  5005.1  387.36  5011.2  389.02  5019.9  388.01    5026  389.55    5049  387.98
  5054.3  389.06  5143.2   388.6  5353.3  386.89  5380.5  387.94    5386  386.75
  5689.5  386.71    5825  387.27    5985  397.72  6069.8  400.51  6074.8   400.4
#Mann= 8 ,-1 , 0
    4166     .16       0  4438.5     .05       0  4936.2     .16       0
  4987.3     .07       0  4993.3     .16       0  5143.2     .05       0
  5689.5      .1       0  6069.8     .16       0
Bank Sta=4987.3,4993.3
XS Rating Curve= 0 ,0
Exp/Cntr=0.3,0.1

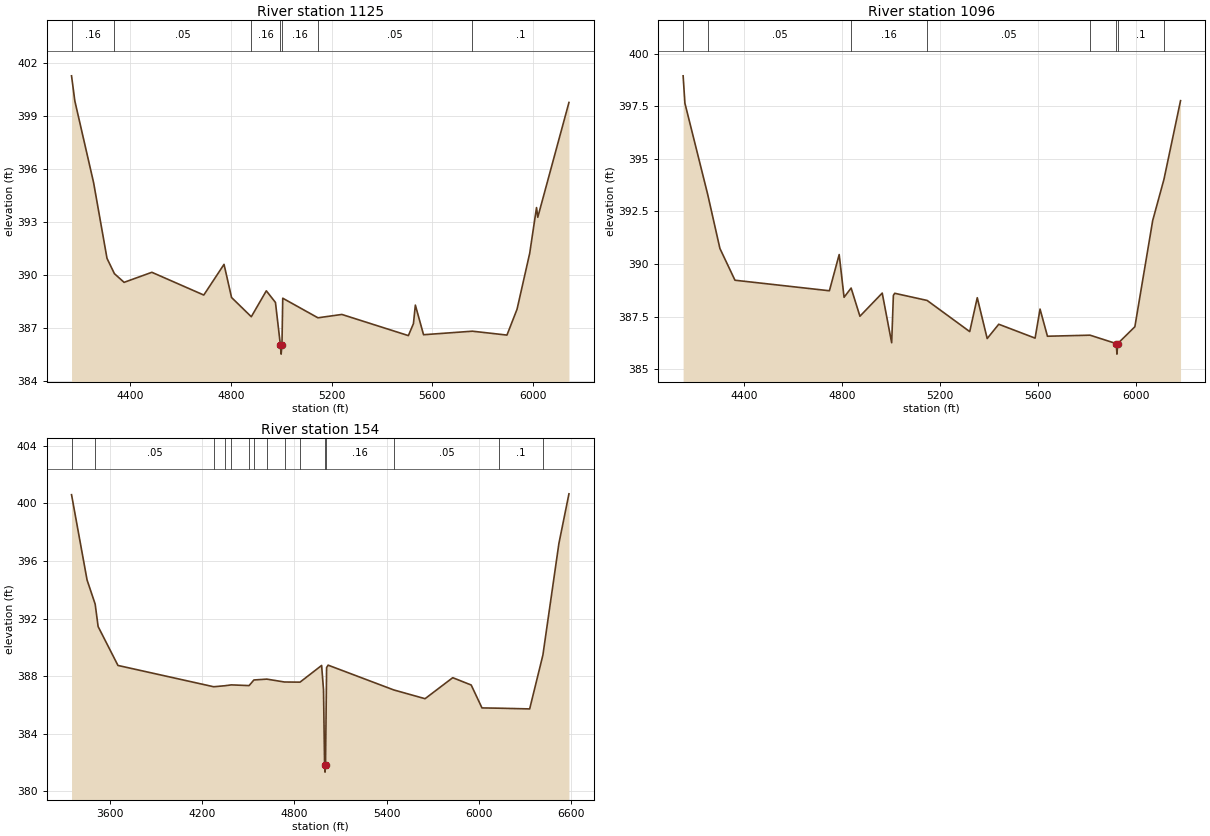
Type RM Length L Ch R = 1 ,1125    ,29,29,29
BEGIN DESCRIPTION:
PINOAK CREEK 2.2
END DESCRIPTION:
XS GIS Cut Line= 6
      3560584.28     10526983.78       3560774.4     10526475.93
      3560769.19     10526356.14      3560917.63     10526028.02
      3560855.13     10525731.14      3560206.86     10525663.45
#Sta/Elev= 30
  4165.7   401.3  4178.9  399.87  4253.4  395.25  4306.8  390.95  4336.4  390.08
  4374.8  389.59  4485.2  390.16  4691.8  388.87  4772.3  390.61  4802.3  388.73
  4880.8  387.64  4940.6  389.11  4976.9  388.45  4996.7  386.02  4999.5  385.52
  5002.7  386.02  5005.9  388.69  5145.9  387.58    5241  387.77  5505.7  386.57
  5525.8  387.25  5533.4   388.3    5566  386.62  5760.3  386.82  5897.8   386.6
    5938  388.07  5988.3  391.24  6015.4  393.83  6020.4  393.28  6144.4  399.79
#Mann= 7 ,-1 , 0
  4165.7     .16       0  4336.4     .05       0  4880.8     .16       0
  4996.7     .07       0  5002.7     .16       0  5145.9     .05       0
  5760.3      .1       0
Bank Sta=4996.7,5002.7
XS Rating Curve= 0 ,0
Exp/Cntr=0.3,0.1

Type RM Length L Ch R = 1 ,1096    ,942,942,942
BEGIN DESCRIPTION:
PINOAK CREEK 2.3
END DESCRIPTION:
XS GIS Cut Line= 6
      3560625.97     10527007.15      3560813.46     10526483.74
      3560808.25     10526340.52      3560951.48     10526035.83
      3560894.19     10525710.31      3560232.68     10525621.76
#Sta/Elev= 30
  4149.6  398.94  4156.9  397.64  4249.8  393.32    4300  390.74  4361.6  389.23
  4747.7  388.73  4787.7  390.45  4807.7  388.42  4836.5  388.86  4872.5  387.52
  4963.7  388.62  5002.3  386.26  5009.3  388.51  5014.8  388.61  5147.3  388.27
  5321.5  386.79  5352.3   388.4  5392.9  386.46  5440.1  387.14  5588.8  386.48
    5609  387.86  5639.3  386.57  5813.5  386.62  5920.7  386.22  5923.4  385.72
  5926.7  386.22  5996.7  387.02  6069.7  392.07  6115.6  394.02  6183.5  397.76
#Mann= 8 ,-1 , 0
  4149.6     .16       0  4249.8     .05       0  4836.5     .16       0
  5147.3     .05       0  5813.5      .1       0  5920.7     .07       0
  5926.7      .1       0  6115.6     .16       0
Bank Sta=5920.7,5926.7
XS Rating Curve= 0 ,0
Exp/Cntr=0.3,0.1

Type RM Length L Ch R = 1 ,154     ,0,0,0
BEGIN DESCRIPTION:
PINOAK CREEK 1.0
END DESCRIPTION:
XS GIS Cut Line= 5
      3560701.49     10527241.55      3561485.34     10526074.89
      3561503.57     10525728.54      3561206.69     10525442.08
      3560136.72     10525481.13
#Sta/Elev= 30
  3349.7  400.61  3450.7  394.69  3503.4  393.01  3522.7  391.45  3651.7  388.75
  4274.4  387.27  4347.4  387.34  4389.5   387.4  4504.7  387.35  4535.8  387.74
  4619.8   387.8    4735   387.6    4836  387.59  4976.5  388.75  4988.8  387.06
  4995.8  381.84  4998.6  381.34  5001.8  381.84  5008.8   388.6  5018.8  388.77
  5445.4  387.05  5649.3  386.44  5829.4   387.9  5949.5  387.39  6019.5   385.8
  6132.3  385.78  6329.7  385.73  6415.8  389.47  6519.9  397.22  6585.3  400.67
#Mann= 15 ,-1 , 0
  3349.7     .16       0  3503.4     .05       0  4274.4     .16       0
  4347.4     .12       0  4389.5     .16       0  4504.7      .1       0
  4535.8     .12       0  4619.8      .1       0    4735     .12       0
    4836     .16       0  4995.8     .07       0  5001.8     .16       0
  5445.4     .05       0  6132.3      .1       0  6415.8     .16       0
Bank Sta=4995.8,5001.8
XS Rating Curve= 0 ,0
Exp/Cntr=0.3,0.1

Chan Stop Cuts=-1
Use User Specified Reach Order=0
Composite Channel Slope=5