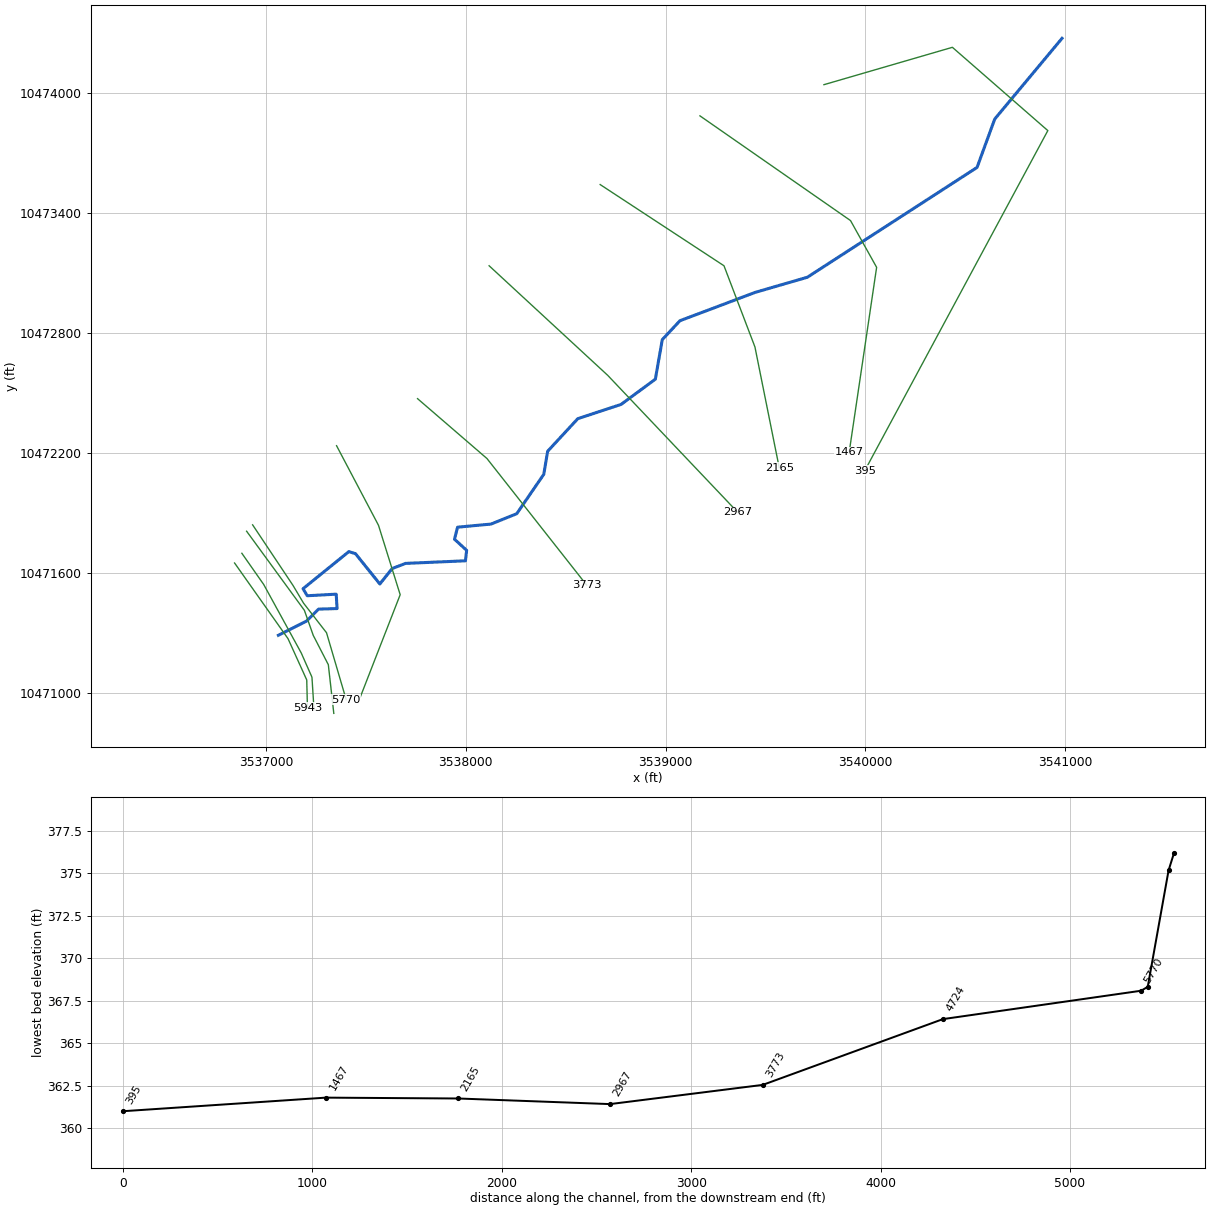
--- RUNNINGBRTRIB3.prj (project) ---

Proj Title=RUNNING BRANCH TRIBUTARY 3
Current Plan=p01
Default Exp/Contr=0.3,0.1
English Units
Geom File=g01
Flow File=f01
Plan File=p01
Y Axis Title=Elevation
X Axis Title(PF)=Main Channel Distance
X Axis Title(XS)=Station
BEGIN DESCRIPTION:
UNT0749 IN SAND CR
END DESCRIPTION:
DSS Export Rating Curves= 0
DSS Export Rating Curve Sorted= 0
DSS Export Volume Flow Curves= 0
DXF OffsetX= 0
DXF OffsetY= 0
DXF ScaleX= 1
DXF ScaleY= 10

--- RUNNINGBRTRIB3.p01 (plan) ---

Plan Title=Multiple Run
Short Identifier=Multiple
Geom File=g01
Flow File=f01
Subcritical Flow
K Sum by GR= 0
Std Step Tol= 0.01
Critical Tol= 0.01
Num of Std Step Trials= 20
Max Error Tol= 0.3
Flow Tol Ratio= 0.001
Split Flow NTrial= 30
Split Flow Tol= 0.02
Split Flow Ratio= 0.02
Log Output Level= 0
Friction Slope Method= 1
Unsteady Friction Slope Method= 2
Unsteady Bridges Friction Slope Method= 1
Parabolic Critical Depth
Global Vel Dist=  1 , 1 , 1
Global Log Level= 0
CheckData=True
Encroach Param= -1, 0, 0, 0
BEGIN DESCRIPTION:
Multiple Run
END DESCRIPTION:

--- RUNNINGBRTRIB3.f01 (steady flow) ---

Flow Title=Multiple
Program Version=4.10
Number of Profiles= 7
Profile Names=10-year,25-year,50-year,1pct_min,100-year,1pct_plu,500-year
River Rch & RM=UNT0749 IN SAND,Reach-1         ,5943
     633     844    1013     888    1201    1625    1684
River Rch & RM=RUNNINGBRTRIB3,Reach-1         ,5943
     633     844    1013     888    1201    1625    1684
Boundary for River Rch & Prof#=RUNNINGBRTRIB3,Reach-1         , 1
Up Type= 0
Dn Type= 3
Dn Slope=0.005
Boundary for River Rch & Prof#=RUNNINGBRTRIB3,Reach-1         , 2
Up Type= 0
Dn Type= 3
Dn Slope=0.005
Boundary for River Rch & Prof#=RUNNINGBRTRIB3,Reach-1         , 3
Up Type= 0
Dn Type= 3
Dn Slope=0.005
Boundary for River Rch & Prof#=RUNNINGBRTRIB3,Reach-1         , 4
Up Type= 0
Dn Type= 3
Dn Slope=0.005
Boundary for River Rch & Prof#=RUNNINGBRTRIB3,Reach-1         , 5
Up Type= 0
Dn Type= 3
Dn Slope=0.005
Boundary for River Rch & Prof#=RUNNINGBRTRIB3,Reach-1         , 6
Up Type= 0
Dn Type= 3
Dn Slope=0.005
Boundary for River Rch & Prof#=RUNNINGBRTRIB3,Reach-1         , 7
Up Type= 0
Dn Type= 3
Dn Slope=0.005
DSS Import GetInterval= 0
DSS Import GetPeak= 0
DSS Import FillOption= 0

--- RUNNINGBRTRIB3.g01 (geometry) ---

Geom Title=Existing Conditions
Program Version=4.10

River Reach=RUNNINGBRTRIB3  ,Reach-1
Reach XY= 30
      3537062.88     10471287.06      3537203.18     10471357.89
      3537263.65     10471417.99      3537356.43     10471420.74
      3537352.09     10471492.73      3537207.19     10471484.89
      3537186.29     10471520.06      3537415.29      10471705.6
      3537448.36     10471695.49       3537570.3     10471543.76
      3537632.17     10471621.05      3537698.76     10471646.67
      3537998.62     10471659.68       3538004.6     10471712.14
      3537943.82     10471767.76      3537959.24     10471827.88
      3538126.33     10471843.38      3538255.25     10471895.26
      3538390.51     10472092.31      3538410.03     10472207.86
      3538560.72     10472370.77      3538776.99     10472441.91
      3538948.69     10472568.16      3538983.37     10472766.13
      3539071.92     10472860.88      3539448.81     10473002.75
      3539709.22     10473078.27      3540558.18     10473627.75
      3540646.72     10473869.94      3540983.21     10474273.54

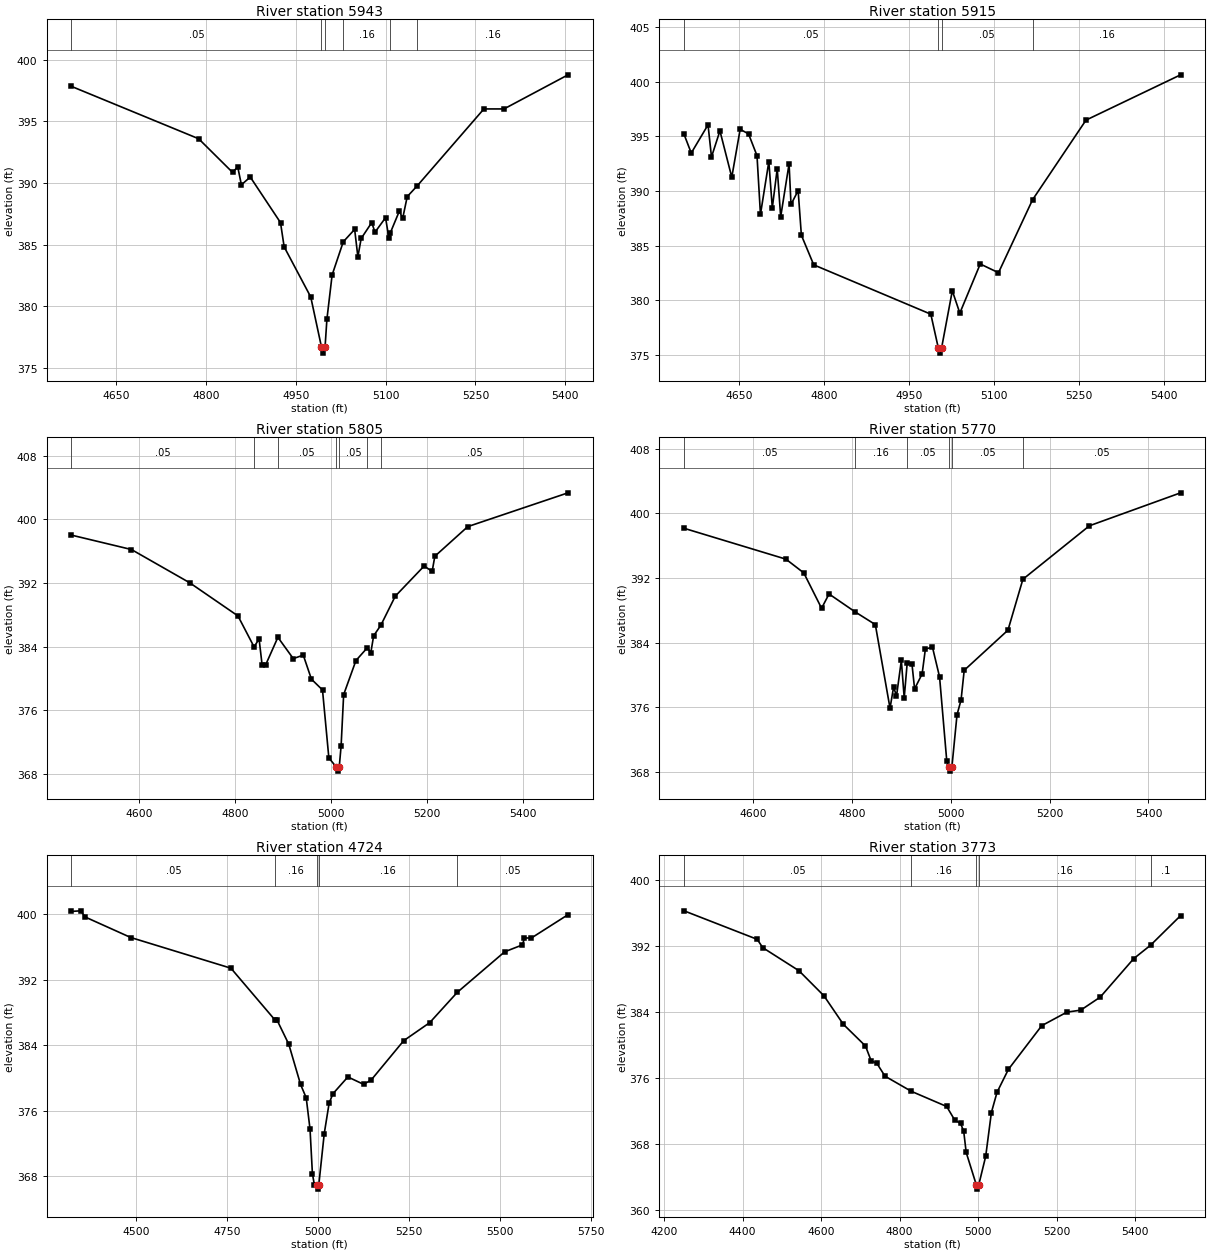
Type RM Length L Ch R = 1 ,5943    ,28,28,28
BEGIN DESCRIPTION:
UNT0749 IN SAND CR 11.02
END DESCRIPTION:
XS GIS Cut Line= 4
      3536843.61     10471648.66      3537110.95     10471270.23
       3537204.7     10471063.63      3537208.13     10470924.78
#Sta/Elev= 30
  4575.6  397.84  4787.9  393.59  4844.5  390.86  4853.2   391.3  4859.3  389.85
  4874.1  390.48  4924.6  386.78  4930.7  384.81  4975.1  380.74    4993  376.68
  4995.7  376.18    4999  376.68  5002.1  378.94  5010.8  382.53  5029.4  385.22
  5048.4  386.23  5053.8     384  5059.3  385.49  5076.9  386.78  5082.4     386
    5100  387.18  5105.5  385.56  5107.9  385.94  5123.1  387.72  5128.6  387.12
  5136.2  388.89  5152.8  389.76  5264.2  396.01  5297.8  396.01  5404.7  398.78
#Mann= 6 ,-1 , 0
  4575.6     .05       0    4993     .03       0    4999     .05       0
  5029.4     .16       0  5107.9     .05       0  5152.8     .16       0
Bank Sta=4993,4999
XS Rating Curve= 0 ,0
Exp/Cntr=0.3,0.1

Type RM Length L Ch R = 1 ,5915    ,110,110,110
BEGIN DESCRIPTION:
UNT0749 IN SAND CR 11.01
END DESCRIPTION:
XS GIS Cut Line= 5
      3536880.03     10471697.33      3536989.42     10471541.06
      3537176.92     10471199.05      3537230.74     10471077.52
      3537241.08     10470915.45
#Sta/Elev= 30
  4552.8  395.18  4565.5  393.47  4595.1  396.05  4601.2  393.11  4616.1   395.5
    4637  391.26  4651.8  395.64  4666.6  395.22  4681.5  393.23  4687.6  387.86
  4702.4  392.69  4708.5  388.46  4717.2  392.04  4723.3  387.64  4738.1  392.49
  4741.5  388.77  4754.1  390.04  4759.8  385.96  4781.6  383.25  4988.2  378.74
  5001.3  375.68  5004.1  375.18  5007.3  375.68  5026.1  380.88  5039.4  378.84
  5075.4  383.33  5107.6  382.53  5167.7   389.2    5262  396.48  5428.9  400.62
#Mann= 4 ,-1 , 0
  4552.8     .05       0  5001.3     .03       0  5007.3     .05       0
  5167.7     .16       0
Bank Sta=5001.3,5007.3
XS Rating Curve= 0 ,0
Exp/Cntr=0.3,0.1

Type RM Length L Ch R = 1 ,5805    ,35,35,35
BEGIN DESCRIPTION:
UNT0749 IN SAND CR 11.0
END DESCRIPTION:
XS GIS Cut Line= 5
      3536903.86     10471807.68      3537192.94     10471411.83
      3537237.21     10471286.83      3537312.73     10471139.69
      3537340.05     10470896.38
#Sta/Elev= 30
  4460.2  398.01  4584.9   396.2  4706.1  392.02  4806.5  387.85    4840  383.96
  4850.5  384.95  4856.7  381.71  4863.9  381.66  4889.6  385.16  4921.6  382.48
  4942.4  382.92  4959.4  379.89  4982.4  378.54  4995.6     370  5011.2  368.83
    5014  368.33  5017.2  368.83  5021.1  371.49  5026.4  377.95    5052  382.24
    5076  383.87  5082.8  383.18  5088.8  385.35  5103.9  386.69  5133.8  390.33
  5193.9  394.13  5210.5  393.44  5216.1  395.35  5284.6  399.08  5493.2  403.33
#Mann= 7 ,-1 , 0
  4460.2     .05       0    4840     .16       0  4889.6     .05       0
  5011.2     .04       0  5017.2     .05       0    5076     .16       0
  5103.9     .05       0
Bank Sta=5011.2,5017.2
XS Rating Curve= 0 ,0
Exp/Cntr=0.3,0.1

Type RM Length L Ch R = 1 ,5770    ,1046,1046,1046
BEGIN DESCRIPTION:
UNT0749 IN SAND CR 11.03
END DESCRIPTION:
XS GIS Cut Line= 5
      3536933.88     10471839.65      3537135.25     10471537.59
      3537189.07     10471447.31      3537303.66     10471299.74
      3537402.08     10470964.77
#Sta/Elev= 30
  4460.8  398.16  4666.8  394.34  4702.9  392.64  4738.9  388.26    4754  390.03
  4806.8  387.81  4847.6  386.24  4877.3  375.89  4884.6  378.53  4890.4  377.37
  4900.2   381.8    4906  377.16    4912  381.48  4921.6  381.41    4927  378.28
  4942.2  380.13  4948.8  383.21  4963.1  383.45  4977.5  379.76    4992  369.39
  4996.4   368.6  4999.2   368.1  5002.4   368.6  5012.8  375.08    5021  376.92
  5027.3  380.58  5115.8  385.55    5146  391.85  5280.5  398.47  5464.9  402.55
#Mann= 6 ,-1 , 0
  4460.8     .05       0  4806.8     .16       0    4912     .05       0
  4996.4     .07       0  5002.4     .05       0    5146     .05       0
Bank Sta=4996.4,5002.4
XS Rating Curve= 0 ,0
Exp/Cntr=0.3,0.1

Type RM Length L Ch R = 1 ,4724    ,951,951,951
BEGIN DESCRIPTION:
UNT0749 IN SAND CR 10.0
END DESCRIPTION:
XS GIS Cut Line= 4
      3537353.85     10472235.54      3537563.65     10471837.28
      3537672.16     10471490.05      3537472.51     10470977.92
#Sta/Elev= 30
  4322.5  400.37  4347.4  400.44  4360.8  399.67  4485.2  397.18  4760.3  393.43
  4882.1  387.06  4886.7  387.11  4919.2  384.14  4951.6  379.22  4967.1  377.59
  4977.6  373.75  4984.1  368.33  4989.3  366.99  4995.6  366.93  4998.3  366.43
  5001.6  366.93  5016.6  373.21    5030  376.93  5040.5  378.09  5081.5  380.14
  5124.5  379.24  5145.2  379.75  5234.8  384.57  5306.4  386.78    5382  390.48
    5512  395.43    5561  396.28  5566.4  397.12  5585.5  397.12  5686.1  399.97
#Mann= 5 ,-1 , 0
  4322.5     .05       0  4882.1     .16       0  4995.6     .07       0
  5001.6     .16       0    5382     .05       0
Bank Sta=4995.6,5001.6
XS Rating Curve= 0 ,0
Exp/Cntr=0.3,0.1

Type RM Length L Ch R = 1 ,3773    ,806,806,806
BEGIN DESCRIPTION:
UNT0749 IN SAND CR 9.0
END DESCRIPTION:
XS GIS Cut Line= 3
      3537758.97     10472470.95      3538106.19     10472171.48
      3538605.34     10471537.78
#Sta/Elev= 30
  4250.8  396.24  4437.2  392.79  4451.4  391.78  4543.6  388.99  4607.2  385.96
  4656.6  382.51  4713.1  379.88  4727.6  378.08    4742  377.79  4762.8  376.23
  4829.8   374.4    4920  372.56  4940.8  370.89  4955.3  370.53  4963.4  369.55
  4969.7     367  4995.6  363.06  4998.4  362.56  5001.6  363.06  5019.4  366.53
  5033.9  371.83  5048.3  374.28  5077.2  377.05  5162.2  382.34  5226.3  383.98
  5261.6  384.22  5311.3   385.8  5396.5  390.45  5439.5  392.08    5516  395.66
#Mann= 5 ,-1 , 0
  4250.8     .05       0  4829.8     .16       0  4995.6     .07       0
  5001.6     .16       0  5439.5      .1       0
Bank Sta=4995.6,5001.6
XS Rating Curve= 0 ,0
Exp/Cntr=0.3,0.1

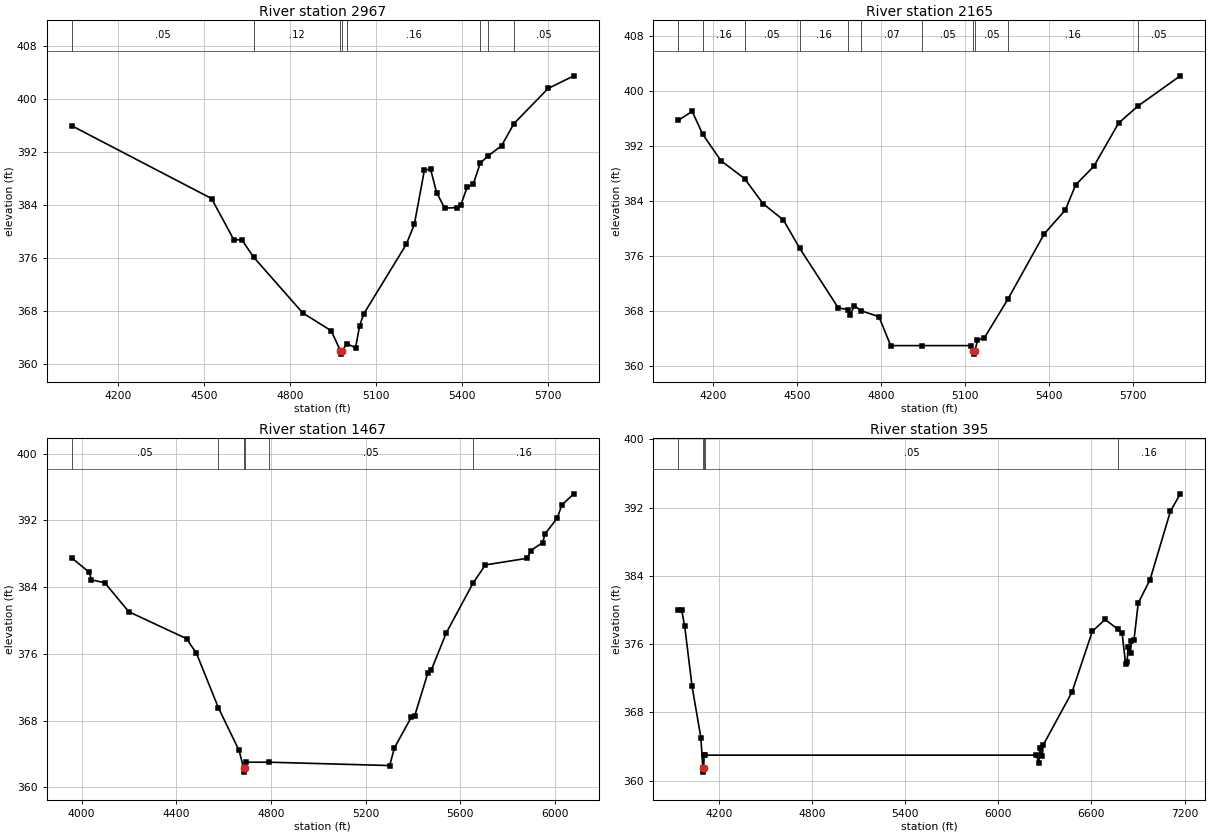
Type RM Length L Ch R = 1 ,2967    ,802,802,802
BEGIN DESCRIPTION:
UNT0749 IN SAND CR 7.0
END DESCRIPTION:
XS GIS Cut Line= 3
      3538117.09     10473135.74      3538710.85     10472587.12
      3539360.13     10471903.13
#Sta/Elev= 30
  4037.7  395.95  4525.3  384.95  4602.9  378.73  4631.3  378.69  4671.7  376.11
  4843.6  367.65  4942.8  364.96    4975  361.93  4977.8  361.43    4981  361.93
  4997.7     363  5027.8   362.4  5041.9  365.73  5056.1   367.5  5204.5  378.02
  5232.8  381.05  5268.1   389.3  5289.5  389.38  5310.5  385.84  5338.8   383.5
  5381.3  383.58  5395.5  384.03  5416.9  386.68  5437.9  387.08  5462.5  390.29
  5489.4  391.37    5537  392.93  5580.4  396.29  5699.6  401.59  5789.2   403.5
#Mann= 8 ,-1 , 0
  4037.7     .05       0  4671.7     .12       0    4975     .07       0
    4981     .12       0  4997.7     .16       0  5462.5     .05       0
  5489.4     .16       0  5580.4     .05       0
Bank Sta=4975,4981
XS Rating Curve= 0 ,0
Exp/Cntr=0.3,0.1

Type RM Length L Ch R = 1 ,2165    ,698,698,698
BEGIN DESCRIPTION:
UNT0749 IN SAND CR 5.0
END DESCRIPTION:
XS GIS Cut Line= 4
      3538672.63       10473542.      3539292.11     10473135.73
      3539446.97     10472729.48      3539568.37     10472125.95
#Sta/Elev= 30
    4077  395.77  4126.7  397.09    4164  393.78  4229.3  389.91  4313.6  387.31
  4379.9  383.64  4452.3  381.28  4510.4  377.16  4648.2  368.48  4684.1  368.24
  4690.4  367.46  4705.5  368.83  4729.7  368.07  4792.9  367.21    4835     363
  4945.2     363  5121.8     363  5129.5  362.26  5132.3  361.76  5135.5  362.26
  5144.6  363.76  5169.4  364.14  5253.1  369.76    5383  379.28  5457.8  382.72
  5495.2  386.41  5559.5  389.09  5648.2  395.39    5717  397.86  5868.2  402.26
#Mann= 11 ,-1 , 0
    4077      .1       0    4164     .16       0  4313.6     .05       0
  4510.4     .16       0  4684.1     .05       0  4729.7     .07       0
  4945.2     .05       0  5129.5    .033       0  5135.5     .05       0
  5253.1     .16       0    5717     .05       0
Bank Sta=5129.5,5135.5
XS Rating Curve= 0 ,0
Exp/Cntr=0.3,0.1

Type RM Length L Ch R = 1 ,1467    ,1072,1072,1072
BEGIN DESCRIPTION:
UNT0749 IN SAND CR 3.0
END DESCRIPTION:
XS GIS Cut Line= 4
      3539171.82     10473885.71      3539925.15     10473361.82
      3540055.75     10473127.87      3539918.32     10472201.73
#Sta/Elev= 30
  3958.6  387.51  4032.6  385.78  4041.3  384.88  4098.1  384.53  4199.3  381.06
  4443.7  377.82  4485.6  376.06  4578.6  369.51  4665.4  364.42  4685.1  362.31
  4687.9  361.81  4691.1  362.31  4694.2     363  4794.1     363  5302.1   362.6
  5322.3  364.73    5393  368.38  5407.8  368.56  5463.8  373.74  5477.3  374.01
  5541.7  378.54  5654.3  384.48  5706.4  386.67  5883.8  387.47  5898.5   388.4
  5948.2  389.34  5959.2  390.42  6009.7  392.26  6029.9  393.87  6080.4   395.2
#Mann= 6 ,-1 , 0
  3958.6     .05       0  4578.6     .07       0  4685.1    .033       0
  4691.1     .07       0  4794.1     .05       0  5654.3     .16       0
Bank Sta=4685.1,4691.1
XS Rating Curve= 0 ,0
Exp/Cntr=0.3,0.1

Type RM Length L Ch R = 1 ,395     ,0,0,0
BEGIN DESCRIPTION:
UNT0749 IN SAND CR 1.0
END DESCRIPTION:
XS GIS Cut Line= 4
       3539792.1     10474041.64      3540434.81     10474228.62
      3540912.24     10473811.95       3539996.8     10472111.21
#Sta/Elev= 30
  3938.1  379.97  3960.1     380  3979.8  378.11  4027.1  371.06  4083.9  365.06
  4096.4  361.51  4099.1  361.01  4102.4  361.51  4104.7     363  4110.8     363
  6245.1     363  6261.3  362.05    6267  363.84  6283.2  362.93  6288.9  364.17
  6474.7  370.38  6606.1  377.52  6688.1   378.9  6772.2  377.74  6797.6  377.29
  6820.1  373.74  6830.1   373.9  6835.7  375.63    6852  374.97  6857.6  376.41
  6873.9  376.44  6901.4  380.82  6977.7  383.57  7109.2   391.6  7172.6  393.63
#Mann= 5 ,-1 , 0
  3938.1      .1       0  4096.4    .033       0  4102.4      .1       0
  4110.8     .05       0  6772.2     .16       0
Bank Sta=4096.4,4102.4
XS Rating Curve= 0 ,0
Exp/Cntr=0.3,0.1

Chan Stop Cuts=-1
Use User Specified Reach Order=0
Composite Channel Slope=5