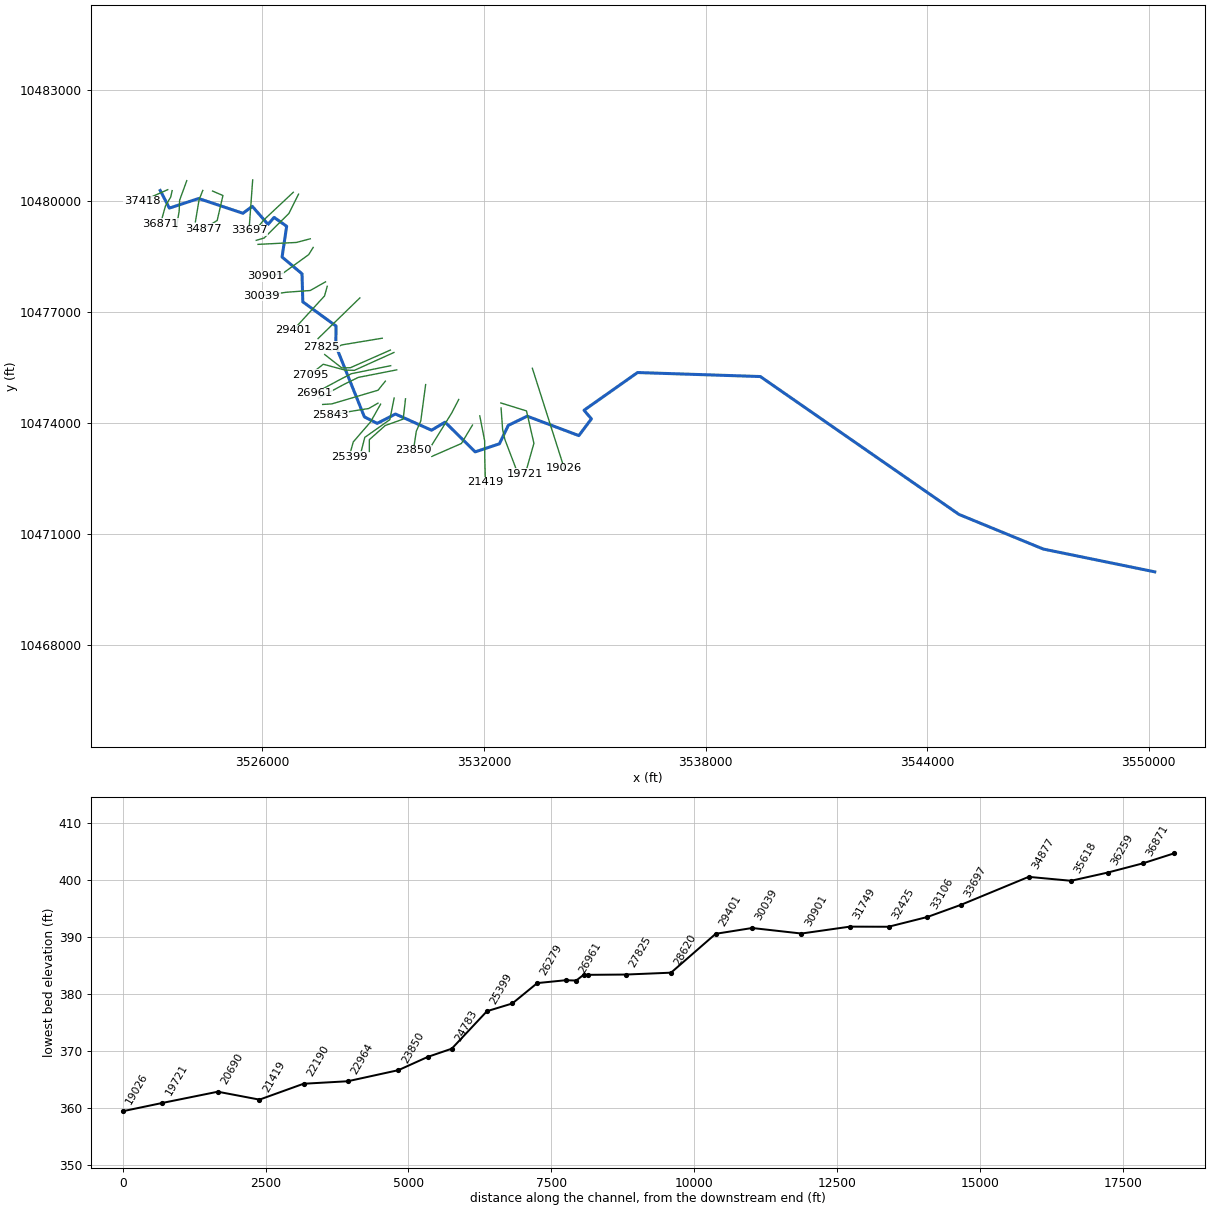
--- RUNNING BRANCH.prj (project) ---

Proj Title=RUNNING BRANCH Base Level Engineering
Current Plan=p01
Default Exp/Contr=0.3,0.1
English Units
Geom File=g01
Flow File=f01
Plan File=p01
Y Axis Title=Elevation
X Axis Title(PF)=Main Channel Distance
X Axis Title(XS)=Station
BEGIN DESCRIPTION:
RUNNING BRANCH
END DESCRIPTION:
DSS Export Rating Curves= 0
DSS Export Rating Curve Sorted= 0
DSS Export Volume Flow Curves= 0
DXF OffsetX= 0
DXF OffsetY= 0
DXF ScaleX= 1
DXF ScaleY= 10

--- RUNNING BRANCH.p01 (plan) ---

Plan Title=Multiple Run
Short Identifier=Multiple
Geom File=g01
Flow File=f01
Subcritical Flow
K Sum by GR= 0
Std Step Tol= 0.01
Critical Tol= 0.01
Num of Std Step Trials= 20
Max Error Tol= 0.3
Flow Tol Ratio= 0.001
Split Flow NTrial= 30
Split Flow Tol= 0.02
Split Flow Ratio= 0.02
Log Output Level= 0
Friction Slope Method= 1
Unsteady Friction Slope Method= 2
Unsteady Bridges Friction Slope Method= 1
Parabolic Critical Depth
Global Vel Dist=  1 , 1 , 1
Global Log Level= 0
CheckData=True
Encroach Param= -1, 0, 0, 0
BEGIN DESCRIPTION:
Multiple Run
END DESCRIPTION:

--- RUNNING BRANCH.f01 (steady flow) ---

Flow Title=Multiple
Program Version=4.10
Number of Profiles= 7
Profile Names=10-year,25-year,50-year,1pct_min,100-year,1pct_plu,500-year
River Rch & RM=RUNNING BRANCH,Reach-1         ,37418
    1230    1700    2089    1870    2529    3421    3700
River Rch & RM=RUNNING BRANCH,Reach-1         ,32425
    1809    2545    3163    2861    3869    5232    5775
River Rch & RM=RUNNING BRANCH,Reach-1         ,26961
    2244    3190    3995    3637    4918    6651    7443
River Rch & RM=RUNNING BRANCH,Reach-1         ,25399
    2767    3955    4968    4533    6130    8290    9318
River Rch & RM=RUNNING BRANCH,Reach-1         ,19026
    3364    4833    6091    5572    7536   10192   11516
River Rch & RM=RUNNING BRANCH,Reach-1         ,12574
    3458    4964    6253    5716    7731   10455   11797
River Rch & RM=RUNNING BRANCH,Reach-1         ,9990
    3605    5178    6525    5966    8069   10912   12316
River Rch & RM=RUNNING BRANCH,Reach-1         ,8042
    3774    5424    6838    6253    8457   11437   12916
River Rch & RM=RUNNING BRANCH,Reach-1         ,6446
    3835    5491    6904    6295    8514   11514   12924
Boundary for River Rch & Prof#=RUNNING BRANCH,Reach-1         , 1
Up Type= 0
Dn Type= 3
Dn Slope=0.001
Boundary for River Rch & Prof#=RUNNING BRANCH,Reach-1         , 2
Up Type= 0
Dn Type= 3
Dn Slope=0.001
Boundary for River Rch & Prof#=RUNNING BRANCH,Reach-1         , 3
Up Type= 0
Dn Type= 3
Dn Slope=0.001
Boundary for River Rch & Prof#=RUNNING BRANCH,Reach-1         , 4
Up Type= 0
Dn Type= 3
Dn Slope=0.001
Boundary for River Rch & Prof#=RUNNING BRANCH,Reach-1         , 5
Up Type= 0
Dn Type= 3
Dn Slope=0.001
Boundary for River Rch & Prof#=RUNNING BRANCH,Reach-1         , 6
Up Type= 0
Dn Type= 3
Dn Slope=0.001
Boundary for River Rch & Prof#=RUNNING BRANCH,Reach-1         , 7
Up Type= 0
Dn Type= 3
Dn Slope=0.001
DSS Import GetInterval= 0
DSS Import GetPeak= 0
DSS Import FillOption= 0

--- RUNNING BRANCH.g01 (geometry) ---

Geom Title=Existing Conditions
Program Version=4.10

River Reach=RUNNING BRANCH  ,Reach-1
Reach XY= 30
      3523240.38     10480290.39      3523487.38     10479813.77
      3524279.99     10480072.53      3525478.05     10479672.95
      3525731.97     10479860.86      3526157.99     10479371.25
      3526322.11     10479561.64      3526662.11     10479321.64
      3526538.02     10478489.22      3527078.07      10478034.7
      3527099.27     10477276.28      3527999.09      10476620.3
      3527992.58     10476087.26      3528765.71     10474162.71
      3529113.49     10473985.47      3529606.59     10474239.19
      3530582.51     10473801.27      3530950.81     10474018.93
      3531765.69     10473215.34       3532421.5     10473433.84
      3532661.35     10473932.18      3533172.52       10474181.
      3534570.63      10473655.1      3534910.88     10474107.47
      3534712.11     10474341.64      3536159.48     10475362.29
      3539484.13     10475253.78      3544860.29     10471521.86
       3547142.1     10470584.36      3550159.97     10469967.41

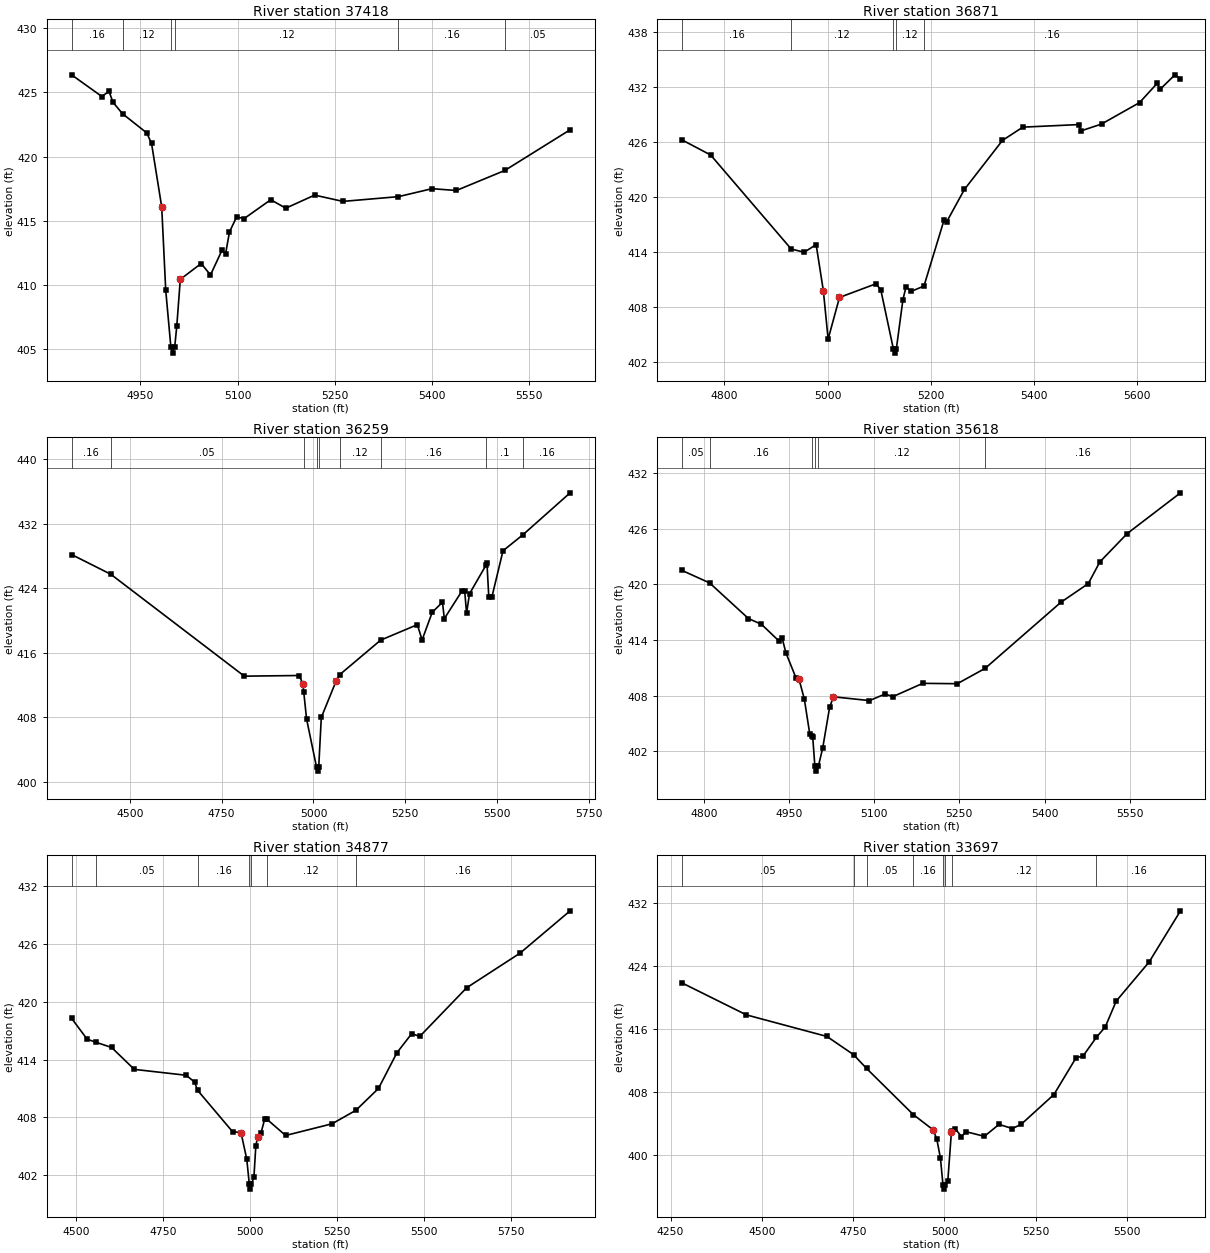
Type RM Length L Ch R = 1 ,37418   ,547,547,547
BEGIN DESCRIPTION:
RUNNING BRANCH 63.0
END DESCRIPTION:
XS GIS Cut Line= 2
      3523444.84     10480312.87      3522741.66     10480000.35
#Sta/Elev= 30
  4843.9  426.37  4890.7  424.68  4901.6  425.09  4907.8  424.23  4922.5  423.34
  4959.8  421.85  4967.3  421.03    4983  416.08  4989.2  409.59  4997.1  405.19
  4999.8  404.69  5003.1  405.19  5006.3  406.82  5011.7  410.44  5043.9  411.67
  5058.3  410.78    5076   412.7  5081.5   412.4  5087.6  414.13  5098.6   415.3
  5110.2  415.17  5151.3  416.64  5174.5  415.98    5219     417  5262.7  416.51
  5348.4  416.88  5400.2   417.5  5437.8  417.36  5512.6  418.92  5613.4  422.09
#Mann= 6 ,-1 , 0
  4843.9     .16       0  4922.5     .12       0  4997.1     .07       0
  5003.1     .12       0  5348.4     .16       0  5512.6     .05       0
Bank Sta=4983,5011.7
XS Rating Curve= 0 ,0
Exp/Cntr=0.3,0.1

Type RM Length L Ch R = 1 ,36871   ,612,612,612
BEGIN DESCRIPTION:
RUNNING BRANCH 62.0
END DESCRIPTION:
XS GIS Cut Line= 4
      3523563.05     10480285.86      3523523.51     10480111.47
      3523380.76     10479869.21      3523245.33      10479382.2
#Sta/Elev= 30
    4718   426.2  4773.6  424.55  4929.6  414.29  4954.7  413.94  4977.9  414.77
  4991.8  409.75  5001.1  404.46  5023.1  409.01  5093.9   410.5  5103.1  409.83
  5127.3  403.43  5130.1  402.93  5133.3  403.43    5146  408.78    5152  410.17
  5161.6  409.66  5186.7  410.25  5225.6  417.45  5230.8  417.27    5265  420.79
  5338.7  426.14  5378.1  427.59    5486  427.87  5491.2  427.19  5530.6  427.93
  5604.2  430.27  5638.5  432.38  5643.7   431.7  5672.7   433.3  5683.5  432.88
#Mann= 5 ,-1 , 0
    4718     .16       0  4929.6     .12       0  5127.3     .07       0
  5133.3     .12       0  5186.7     .16       0
Bank Sta=4991.8,5023.1
XS Rating Curve= 0 ,0
Exp/Cntr=0.3,0.1

Type RM Length L Ch R = 1 ,36259   ,641,641,641
BEGIN DESCRIPTION:
RUNNING BRANCH 61.0
END DESCRIPTION:
XS GIS Cut Line= 4
      3523958.87     10480556.67      3523764.74     10480025.27
      3523753.16      10479736.4      3523669.83     10479241.62
#Sta/Elev= 30
  4341.8  428.16  4448.4  425.72  4811.8  413.09  4961.2  413.17  4971.2  412.13
  4973.4  411.18  4981.2  407.79  5008.3  401.82    5011  401.32  5014.3  401.82
  5021.3  407.97  5061.3  412.45  5071.8  413.29  5182.7  417.55  5282.6  419.47
  5295.6  417.58  5323.2  421.01    5351  422.25  5356.1  420.22  5404.3  423.66
  5411.5  423.64  5416.6  420.89  5424.6   423.3  5470.2   426.9  5472.1  427.07
  5477.1  422.89  5485.4  422.88  5515.8  428.63  5570.4  430.63  5698.4  435.81
#Mann= 9 ,-1 , 0
  4341.8     .16       0  4448.4     .05       0  4973.4     .16       0
  5008.3     .07       0  5014.3     .16       0  5071.8     .12       0
  5182.7     .16       0  5470.2      .1       0  5570.4     .16       0
Bank Sta=4971.2,5061.3
XS Rating Curve= 0 ,0
Exp/Cntr=0.3,0.1

Type RM Length L Ch R = 1 ,35618   ,741,741,741
BEGIN DESCRIPTION:
RUNNING BRANCH 60.0
END DESCRIPTION:
XS GIS Cut Line= 3
      3524392.11     10480291.66      3524292.11     10480041.64
       3524192.1      10479441.6
#Sta/Elev= 30
  4761.7  421.51  4810.4  420.16  4878.8  416.32  4901.7   415.7  4932.7  413.89
  4938.1   414.2  4944.8  412.61  4962.3  409.95  4967.7   409.8  4977.1  407.65
  4986.6  403.92  4990.6  403.65  4991.9  403.56  4995.7  400.38  4998.4  399.88
  5001.7  400.38  5009.4  402.35  5021.6  406.74  5028.3  407.89  5091.8  407.48
  5119.7   408.2  5132.4  407.89  5185.6  409.34  5246.4   409.3  5295.3  410.95
  5428.9  418.08    5477  420.09  5497.3  422.42  5545.5  425.48  5639.3  429.87
#Mann= 6 ,-1 , 0
  4761.7     .05       0  4810.4     .16       0  4990.6     .12       0
  4995.7     .07       0  5001.7     .12       0  5295.3     .16       0
Bank Sta=4967.7,5028.3
XS Rating Curve= 0 ,0
Exp/Cntr=0.3,0.1

Type RM Length L Ch R = 1 ,34877   ,1180,1180,1180
BEGIN DESCRIPTION:
RUNNING BRANCH 58.0
END DESCRIPTION:
XS GIS Cut Line= 4
      3524656.29     10480274.21      3524937.55     10480154.41
       3524781.3     10479477.33      3524411.53     10479253.38
#Sta/Elev= 30
  4486.9  418.27  4531.5  416.11  4557.6  415.78  4601.9  415.25  4667.1  412.98
    4816  412.37  4840.4  411.67    4849  410.81  4949.4  406.53  4973.8  406.43
  4990.5  403.65  4997.7  401.07  5000.5  400.57  5003.7  401.07    5011  401.84
  5016.5  405.09  5021.7  405.96  5031.5  406.42  5041.8  407.81    5048  407.82
  5102.1  406.13  5235.5  407.34  5304.1  408.74  5368.9     411  5421.9   414.7
  5464.7  416.69  5487.5  416.39  5622.5  421.44  5775.7  425.02  5919.8  429.41
#Mann= 7 ,-1 , 0
  4486.9     .16       0  4557.6     .05       0    4849     .16       0
  4997.7     .07       0  5003.7     .16       0    5048     .12       0
  5304.1     .16       0
Bank Sta=4973.8,5021.7
XS Rating Curve= 0 ,0
Exp/Cntr=0.3,0.1

Type RM Length L Ch R = 1 ,33697   ,591,591,591
BEGIN DESCRIPTION:
RUNNING BRANCH 57.0
END DESCRIPTION:
XS GIS Cut Line= 2
      3525742.74     10480577.58      3525643.82     10479216.07
#Sta/Elev= 30
  4281.2  421.85  4457.6  417.79  4678.2  415.05  4751.1  412.74  4786.7  410.99
  4914.5  405.14  4968.9   403.2    4979  402.02    4989  399.61    4996  396.17
  4998.8  395.67    5002  396.17  5009.1  396.66  5019.1  402.97  5021.3  403.06
  5029.1  403.36  5046.6  402.34  5059.2  402.96  5109.3  402.37  5149.4  403.89
  5185.7  403.36  5209.6  403.88  5299.8  407.68    5360  412.32    5380   412.6
    5416  414.94  5440.2  416.25  5470.3  419.54  5560.5  424.51  5646.3     431
#Mann= 8 ,-1 , 0
  4281.2     .05       0  4751.1     .16       0  4786.7     .05       0
  4914.5     .16       0    4996     .07       0    5002     .16       0
  5021.3     .12       0    5416     .16       0
Bank Sta=4968.9,5019.1
XS Rating Curve= 0 ,0
Exp/Cntr=0.3,0.1

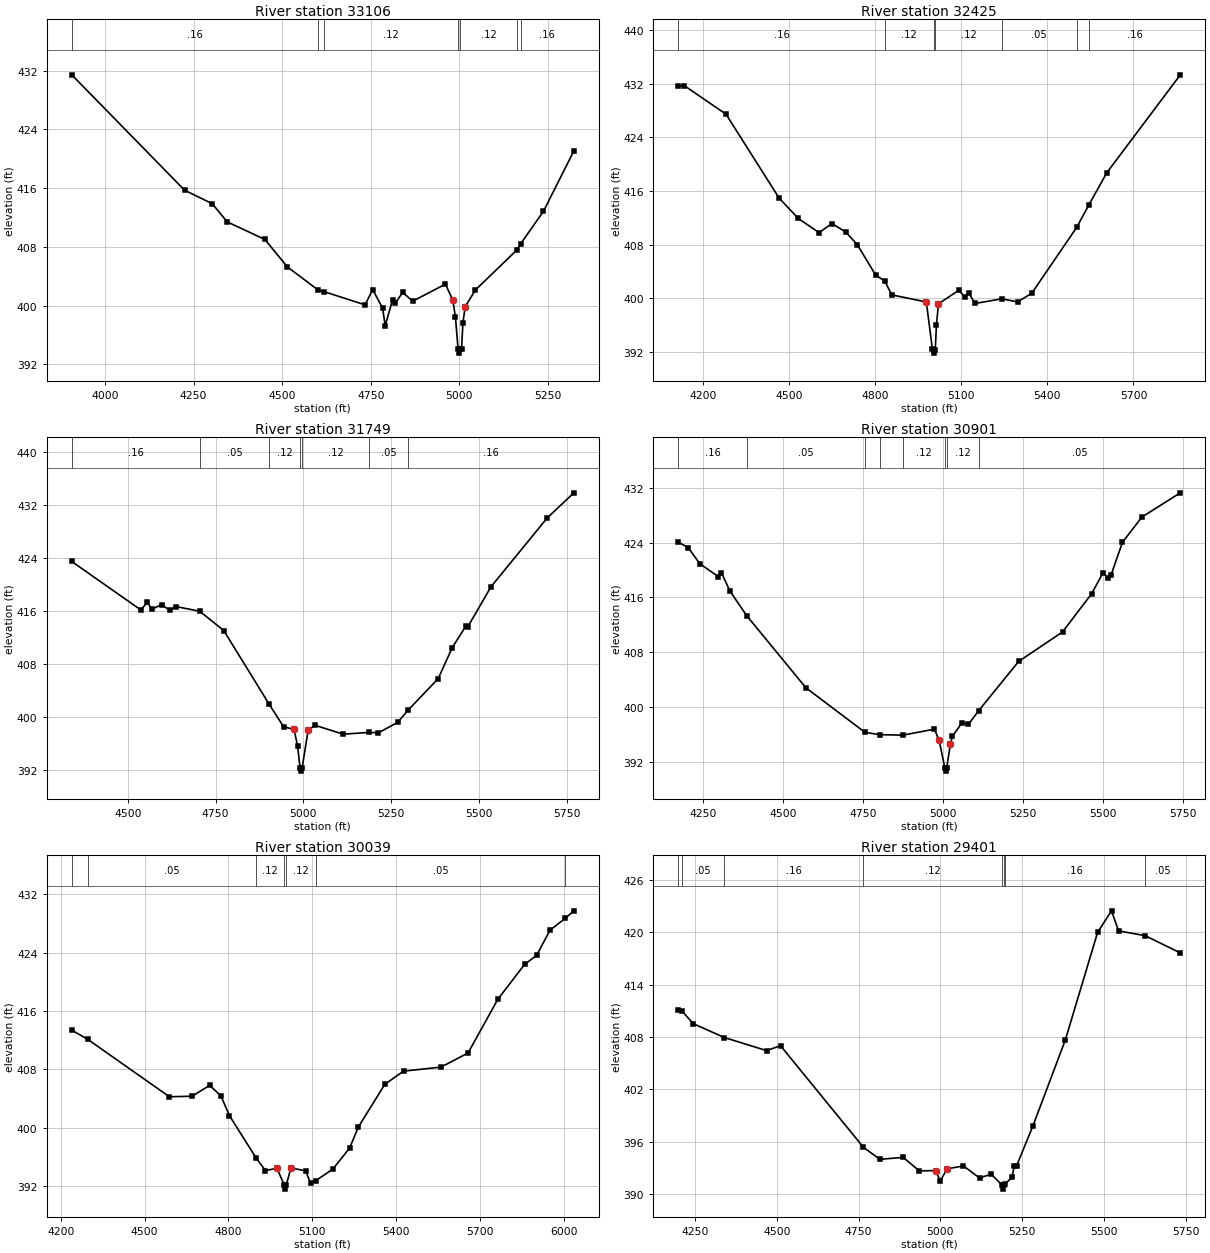
Type RM Length L Ch R = 1 ,33106   ,681,681,681
BEGIN DESCRIPTION:
RUNNING BRANCH 55.0
END DESCRIPTION:
XS GIS Cut Line= 3
      3526842.13     10480241.67      3526042.11     10479491.64
      3525842.09     10479241.63
#Sta/Elev= 30
  3906.3  431.44  4224.6  415.72  4302.7  413.88    4345   411.4  4451.2  409.01
  4514.7  405.27  4600.5  402.15  4618.5  401.89    4734   400.1  4755.5  402.18
  4783.6  399.63  4790.7  397.25  4811.7  400.81    4819  400.29    4840  401.79
  4868.4   400.6  4960.7  402.92  4981.7  400.73    4989   398.4  4996.5  394.02
  4999.2  393.52  5002.5  394.02  5006.1  394.02  5010.1  397.66  5016.5  399.85
  5045.3  402.12  5162.4  407.58  5173.4  408.44  5237.4  412.85  5323.1  421.07
#Mann= 7 ,-1 , 0
  3906.3     .16       0  4600.5      .1       0  4618.5     .12       0
  4996.5     .07       0  5002.5     .12       0  5162.4      .1       0
  5173.4     .16       0
Bank Sta=4981.7,5016.5
XS Rating Curve= 0 ,0
Exp/Cntr=0.3,0.1

Type RM Length L Ch R = 1 ,32425   ,676,676,676
BEGIN DESCRIPTION:
RUNNING BRANCH 54.0
END DESCRIPTION:
XS GIS Cut Line= 4
      3526984.42     10480190.84      3526724.01     10479670.04
      3526052.14     10479003.37      3525838.58     10478940.86
#Sta/Elev= 30
  4112.2  431.63  4133.9   431.7    4279  427.45  4463.7  414.96  4530.8   411.9
  4603.5  409.78  4648.2  411.14  4696.9  409.86  4737.1  407.97  4800.8  403.44
  4832.1  402.57  4857.3  400.49  4977.6  399.43  4998.7   392.4  5002.8   392.3
  5005.6   391.8  5008.8   392.3  5012.9  396.07    5020  399.17  5090.7  401.17
  5111.9  400.21    5126  400.77  5147.3  399.21  5240.7   399.9  5295.7  399.45
  5345.2  400.72  5502.1  410.57  5544.3   413.9  5606.9  418.71  5863.5  433.33
#Mann= 7 ,-1 , 0
  4112.2     .16       0  4832.1     .12       0  5002.8     .07       0
  5008.8     .12       0  5240.7     .05       0  5502.1      .1       0
  5544.3     .16       0
Bank Sta=4977.6,5020
XS Rating Curve= 0 ,0
Exp/Cntr=0.3,0.1

Type RM Length L Ch R = 1 ,31749   ,848,848,848
BEGIN DESCRIPTION:
RUNNING BRANCH 52.0
END DESCRIPTION:
XS GIS Cut Line= 3
      3527302.14     10478982.54      3526927.14     10478883.58
      3525886.28     10478831.53
#Sta/Elev= 30
  4340.5  423.43    4537  416.13  4556.1  417.28  4568.1  416.23  4596.3  416.91
  4619.8  416.06  4636.6  416.64  4704.8  415.93  4773.4  413.02  4902.9  401.89
  4943.6  398.52  4973.7   398.1  4983.7  395.57  4990.7  392.32  4993.5  391.82
  4996.7  392.32  5013.7     398  5033.8  398.72  5113.9  397.39  5187.3  397.66
    5214   397.6  5268.4  399.16    5298  400.99  5384.2  405.77  5424.2  410.45
  5463.6  413.73  5468.6  413.59  5534.4  419.61  5694.6  429.99  5770.5  433.78
#Mann= 7 ,-1 , 0
  4340.5     .16       0  4704.8     .05       0  4902.9     .12       0
  4990.7     .07       0  4996.7     .12       0  5187.3     .05       0
    5298     .16       0
Bank Sta=4973.7,5013.7
XS Rating Curve= 0 ,0
Exp/Cntr=0.3,0.1

Type RM Length L Ch R = 1 ,30901   ,862,862,862
BEGIN DESCRIPTION:
RUNNING BRANCH 50.0
END DESCRIPTION:
XS GIS Cut Line= 4
      3527380.26     10478748.16      3527260.47     10478555.45
      3526557.35     10478045.04      3526088.58     10477966.91
#Sta/Elev= 30
  4171.1  424.09  4202.3  423.29  4238.7  420.93  4296.6  419.05    4306  419.65
  4333.2  416.91  4386.3  413.28  4570.7  402.79  4755.1  396.29  4801.2  395.94
  4873.9  395.87  4972.7  396.75  4987.4  395.11  5005.2  391.11    5008  390.61
  5011.2  391.11  5022.9  394.61  5029.1   395.7  5058.5  397.66  5079.3  397.46
  5111.4  399.46  5236.3  406.65  5373.6  410.96  5464.8  416.56  5500.3  419.63
  5515.5  418.84  5525.6  419.31  5561.2  424.08    5622  427.76  5742.1   431.3
#Mann= 8 ,-1 , 0
  4171.1     .16       0  4386.3     .05       0  4755.1     .12       0
  4801.2     .05       0  4873.9     .12       0  5005.2     .07       0
  5011.2     .12       0  5111.4     .05       0
Bank Sta=4987.4,5022.9
XS Rating Curve= 0 ,0
Exp/Cntr=0.3,0.1

Type RM Length L Ch R = 1 ,30039   ,638,638,638
BEGIN DESCRIPTION:
RUNNING BRANCH 49.0
END DESCRIPTION:
XS GIS Cut Line= 4
      3527714.05      10477817.1      3527300.03     10477582.75
       3526656.8     10477535.88      3525987.56     10477436.92
#Sta/Elev= 30
  4239.4  413.37  4296.4  412.11  4588.8  404.24  4669.6  404.31  4733.1   405.8
  4773.2  404.37  4803.8  401.65  4898.5  395.89  4932.7  394.12  4973.8  394.44
  5000.8  392.08  5003.6  391.58  5006.8  392.08  5023.9  394.49  5076.7  394.08
  5094.1  392.38  5112.3  392.73  5174.3  394.33  5234.4  397.24  5264.5  400.04
  5359.9  405.94  5426.9  407.75    5561   408.3    5658  410.24  5764.6   417.6
  5860.2  422.37  5903.7  423.63  5951.1  427.06  6005.1  428.67  6036.6  429.72
#Mann= 7 ,-1 , 0
  4239.4     .16       0  4296.4     .05       0  4898.5     .12       0
  5000.8     .07       0  5006.8     .12       0  5112.3     .05       0
  6005.1     .16       0
Bank Sta=4973.8,5023.9
XS Rating Curve= 0 ,0
Exp/Cntr=0.3,0.1

Type RM Length L Ch R = 1 ,29401   ,781,781,781
BEGIN DESCRIPTION:
RUNNING BRANCH 47.0
END DESCRIPTION:
XS GIS Cut Line= 3
      3527760.48      10477696.1      3527687.55     10477435.66
      3526833.38     10476503.36
#Sta/Elev= 30
  4198.9  411.09  4209.9  411.02  4244.2  409.55  4339.7  407.95  4468.8  406.45
  4511.6  407.01  4765.2  395.35  4815.6  393.98  4886.5   394.2  4935.9  392.66
  4985.8  392.68  4999.9   391.5  5020.9  392.89  5070.9  393.22  5120.2  391.83
  5155.3  392.28  5188.1  391.06  5190.9  390.56  5194.1  391.06  5197.9  391.15
  5219.5  391.91  5226.3  393.26  5233.7  393.27    5283  397.79  5382.3  407.67
  5480.9     420  5523.5  422.48  5545.1  420.18  5626.5  419.63  5733.8  417.65
#Mann= 8 ,-1 , 0
  4198.9     .16       0  4209.9     .05       0  4339.7     .16       0
  4765.2     .12       0  5188.1     .07       0  5194.1     .12       0
  5197.9     .16       0  5626.5     .05       0
Bank Sta=4985.8,5020.9
XS Rating Curve= 0 ,0
Exp/Cntr=0.3,0.1

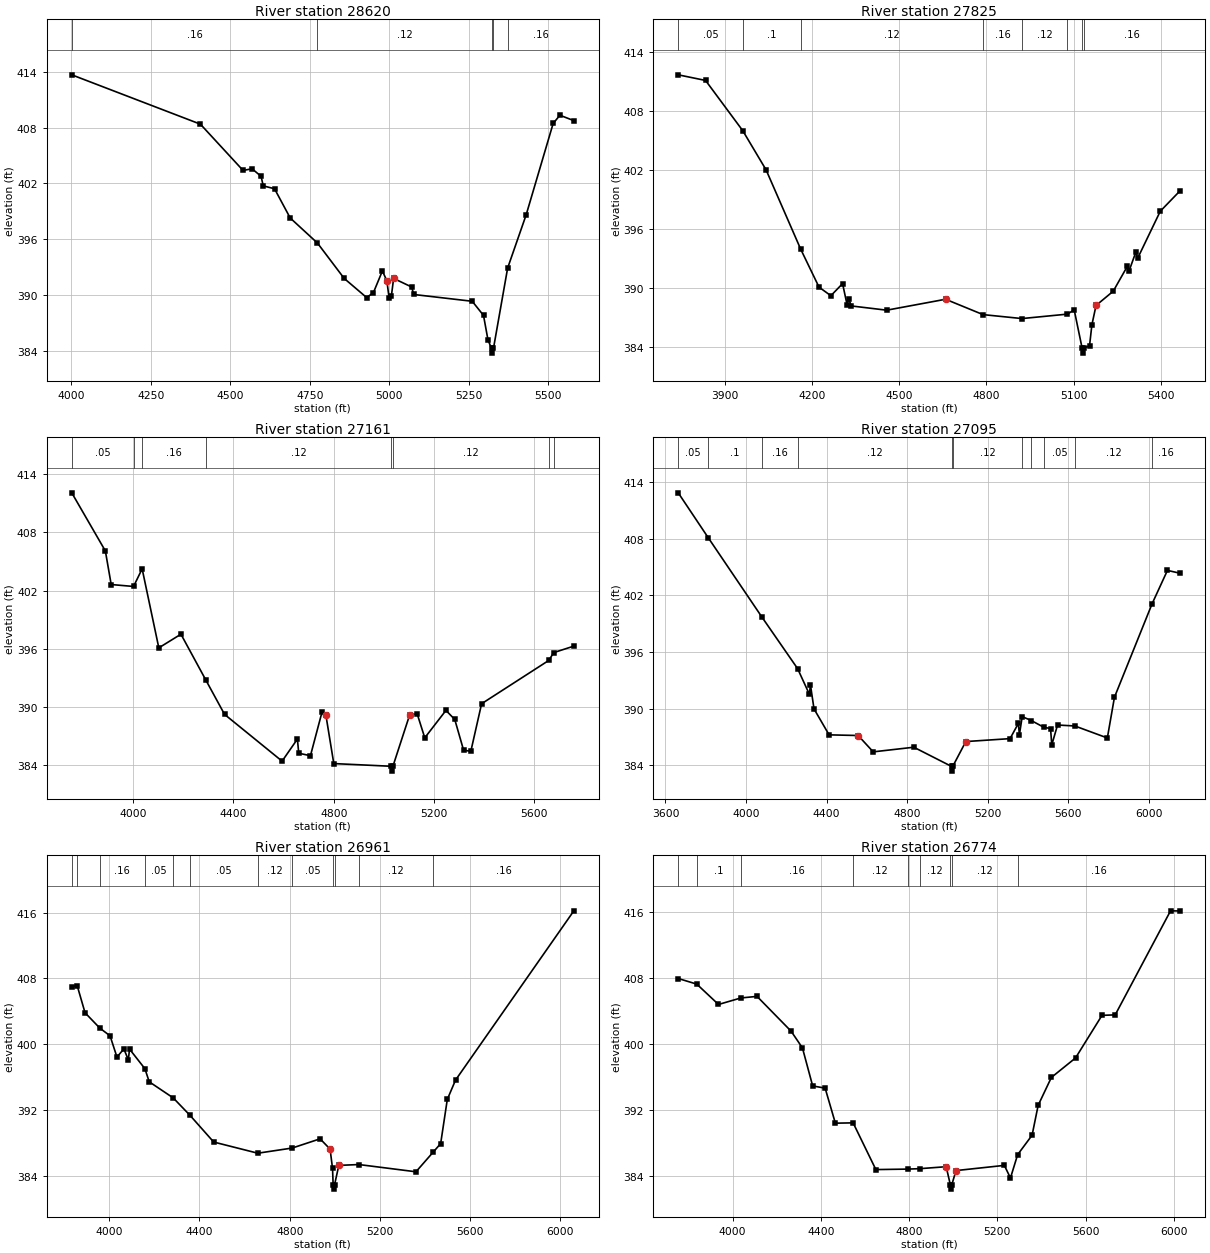
Type RM Length L Ch R = 1 ,28620   ,795,795,795
BEGIN DESCRIPTION:
RUNNING BRANCH 46.0
END DESCRIPTION:
XS GIS Cut Line= 2
      3528643.79     10477382.24      3527510.98     10476280.68
#Sta/Elev= 30
  4001.2  413.68    4406  408.37  4540.3  403.39  4568.6  403.57  4596.9  402.76
  4603.8  401.73  4639.3  401.42  4688.7  398.27  4774.3  395.58  4858.5  391.77
  4929.2  389.71  4950.5  390.24  4978.8  392.58  4992.9   391.5  4999.9  389.66
  5007.1  389.89  5014.1  391.77  5070.7  390.85  5077.6  390.04  5261.5  389.31
    5297  387.79  5311.1  385.14  5322.3  384.23    5325  383.73  5328.3  384.23
  5372.9  392.88  5431.3  398.62  5516.2  408.45  5537.5  409.33  5581.3  408.75
#Mann= 5 ,-1 , 0
  4001.2     .16       0  4774.3     .12       0  5322.3     .07       0
  5328.3     .12       0  5372.9     .16       0
Bank Sta=4992.9,5014.1
XS Rating Curve= 0 ,0
Exp/Cntr=0.3,0.1

Type RM Length L Ch R = 1 ,27825   ,664,664,664
BEGIN DESCRIPTION:
RUNNING BRANCH 45.0
END DESCRIPTION:
XS GIS Cut Line= 4
      3529250.58     10476291.96      3528152.46     10476109.66
      3527855.15     10475957.75      3527592.58     10476061.92
#Sta/Elev= 30
  3738.4  411.66  3832.5  411.09  3960.6  405.99    4041  402.01  4159.7  393.99
  4223.4   390.1  4264.2  389.23  4304.5  390.46  4320.1   388.3  4325.1  388.93
  4334.9  388.19  4456.6  387.76  4659.3  388.87  4788.5  387.31  4922.5  386.91
  5079.1  387.36  5102.3   387.8  5129.7   383.9  5132.4   383.4  5135.7   383.9
  5155.2  384.15  5163.3  386.27  5177.6  388.24  5236.9  389.69  5285.5  392.22
  5290.9  391.71  5315.2   393.7  5320.6  393.01  5398.9  397.81  5467.9  399.91
#Mann= 8 ,-1 , 0
  3738.4     .05       0  3960.6      .1       0  4159.7     .12       0
  4788.5     .16       0  4922.5     .12       0  5079.1     .16       0
  5129.7     .07       0  5135.7     .16       0
Bank Sta=4659.3,5177.6
XS Rating Curve= 0 ,0
Exp/Cntr=0.3,0.1

Type RM Length L Ch R = 1 ,27161   ,66,66,66
BEGIN DESCRIPTION:
RUNNING BRANCH 44.0
END DESCRIPTION:
XS GIS Cut Line= 4
      3529469.75     10475970.78      3528389.01     10475493.34
      3528154.63     10475486.83      3527692.43     10475849.22
#Sta/Elev= 30
  3754.9  412.09  3888.9  406.09  3912.2  402.62  4001.4  402.42  4035.7  404.24
  4102.2  396.08  4190.5  397.49  4289.3  392.78  4364.5  389.21  4594.1  384.38
  4655.1  386.66  4660.6   385.2  4707.2  384.94  4753.8  389.49    4769  389.11
  4800.4  384.13  5030.3  383.85  5033.1  383.35  5036.3  383.85  5103.4  389.18
  5133.4  389.24  5163.4  386.79  5247.8  389.62    5283  388.69  5318.3  385.51
  5347.2   385.4  5390.1  390.31  5658.1  394.78  5677.9  395.59  5758.2  396.26
#Mann= 8 ,-1 , 0
  3754.9     .05       0  4001.4      .1       0  4035.7     .16       0
  4289.3     .12       0  5030.3     .07       0  5036.3     .12       0
  5658.1     .05       0  5677.9     .12       0
Bank Sta=4769,5103.4
XS Rating Curve= 0 ,0
Exp/Cntr=0.3,0.1

Type RM Length L Ch R = 1 ,27095   ,134,134,134
BEGIN DESCRIPTION:
RUNNING BRANCH 43.0
END DESCRIPTION:
XS GIS Cut Line= 5
      3529567.41     10475905.68      3528495.34     10475421.73
      3528241.44     10475428.24      3527653.33     10475586.66
      3527297.43     10475306.71
#Sta/Elev= 30
  3663.3  412.85  3811.5  408.12  4079.2  399.68  4255.8  394.24  4314.1  391.53
  4319.6  392.52  4337.2  389.98  4412.1  387.23  4556.3  387.16  4631.1  385.43
  4832.6  385.92  5019.8  383.89  5022.6  383.39  5025.8  383.89  5090.7  386.52
  5310.3  386.83  5351.5  388.44  5356.7  387.24  5370.6  389.16  5416.3  388.74
    5478  388.03  5511.3   387.9  5517.4  386.17    5546  388.27  5631.9  388.17
  5793.2   386.9  5828.5  391.21  6015.2   401.1  6091.5  404.64  6155.4  404.33
#Mann= 11 ,-1 , 0
  3663.3     .05       0  3811.5      .1       0  4079.2     .16       0
  4255.8     .12       0  5019.8     .07       0  5025.8     .12       0
  5370.6     .05       0  5416.3     .12       0    5478     .05       0
  5631.9     .12       0  6015.2     .16       0
Bank Sta=4556.3,5090.7
XS Rating Curve= 0 ,0
Exp/Cntr=0.3,0.1

Type RM Length L Ch R = 1 ,26961   ,187,187,187
BEGIN DESCRIPTION:
RUNNING BRANCH 42.0
END DESCRIPTION:
XS GIS Cut Line= 4
      3529478.44      10475547.6      3528412.88     10475330.58
      3528130.76     10475185.18      3527408.07     10474796.71
#Sta/Elev= 30
    3834  406.97  3857.9  407.12  3892.8  403.81    3958  401.95  4003.7     401
  4034.2  398.42    4065  399.41  4084.8  398.07  4089.9  399.39  4158.2     397
  4177.2  395.41  4283.6  393.45  4358.3  391.32    4463  388.08  4658.5  386.72
  4811.1  387.35  4934.6  388.47  4978.9  387.22  4989.8  384.86  4992.5  382.85
  4995.2  382.35  4998.5  382.85  5017.6  385.24  5106.8  385.34  5359.5  384.46
  5435.8  386.85    5469  387.89  5498.4  393.26  5534.8  395.61  6059.3  416.21
#Mann= 12 ,-1 , 0
    3834     .05       0  3857.9      .1       0    3958     .16       0
  4158.2     .05       0  4283.6     .16       0  4358.3     .05       0
  4658.5     .12       0  4811.1     .05       0  4992.5     .04       0
  4998.5     .05       0  5106.8     .12       0  5435.8     .16       0
Bank Sta=4978.9,5017.6
XS Rating Curve= 0 ,0
Exp/Cntr=0.3,0.1

Type RM Length L Ch R = 1 ,26774   ,495,495,495
BEGIN DESCRIPTION:
RUNNING BRANCH 41.0
END DESCRIPTION:
XS GIS Cut Line= 4
      3529641.16     10475434.75      3528601.68     10475230.76
      3528217.57     10475044.12      3527523.12     10474668.69
#Sta/Elev= 30
  3753.7  407.95  3837.7  407.27  3936.2   404.8  4037.6  405.59  4110.9  405.78
  4265.3  401.56  4316.7  399.53    4363  394.92  4419.6  394.65  4465.9   390.4
  4546.4  390.44  4649.5  384.77  4793.4  384.83  4847.9  384.88  4968.2  385.12
  4987.4   382.9  4990.2   382.4  4993.4   382.9  5012.7  384.65  5231.9  385.28
  5259.6  383.75  5292.1  386.58  5357.6  388.94  5385.2  392.57  5445.1  395.95
  5554.5  398.31  5674.5  403.48  5734.4  403.54  5985.2  416.16  6029.5  416.14
#Mann= 9 ,-1 , 0
  3753.7     .16       0  3837.7      .1       0  4037.6     .16       0
  4546.4     .12       0  4793.4     .05       0  4847.9     .12       0
  4987.4     .07       0  4993.4     .12       0  5292.1     .16       0
Bank Sta=4968.2,5012.7
XS Rating Curve= 0 ,0
Exp/Cntr=0.3,0.1

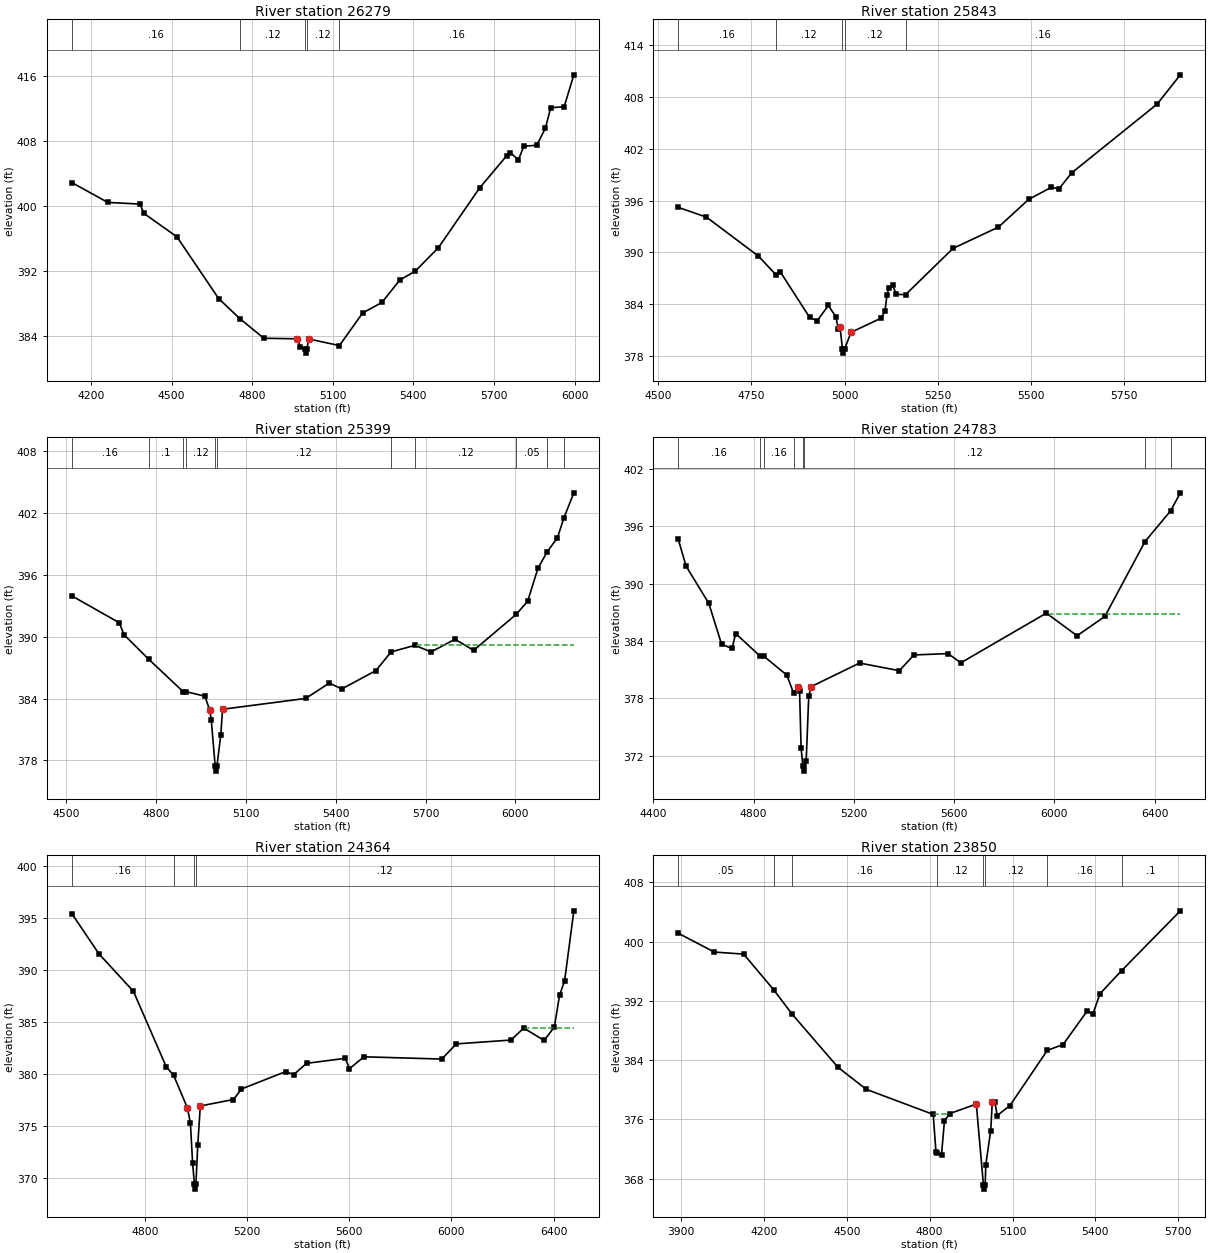
Type RM Length L Ch R = 1 ,26279   ,436,436,436
BEGIN DESCRIPTION:
RUNNING BRANCH 41.1
END DESCRIPTION:
XS GIS Cut Line= 4
       3529333.4     10475128.38      3529135.47     10474883.58
      3527885.47     10474513.79      3527636.32     10474498.21
#Sta/Elev= 30
  4128.9  402.89  4262.9  400.44  4382.9  400.24  4397.3  399.09  4520.2  396.21
  4675.5  388.61  4753.6  386.16  4843.5  383.73  4968.6  383.66  4979.1  382.66
    4998   382.4  5000.8   381.9    5004   382.4  5010.4  383.64  5124.8  382.83
  5211.1  386.84  5282.8  388.13  5349.4   390.9  5406.6  391.98  5492.9  394.87
  5646.5  402.23  5746.4  406.16  5760.7  406.55  5790.7  405.69  5810.8  407.36
  5858.8  407.47  5890.9  409.57  5910.9  412.09    5961  412.22  5996.9  416.14
#Mann= 5 ,-1 , 0
  4128.9     .16       0  4753.6     .12       0    4998     .07       0
    5004     .12       0  5124.8     .16       0
Bank Sta=4968.6,5010.4
XS Rating Curve= 0 ,0
Exp/Cntr=0.3,0.1

Type RM Length L Ch R = 1 ,25843   ,444,444,444
BEGIN DESCRIPTION:
RUNNING BRANCH 40.0
END DESCRIPTION:
XS GIS Cut Line= 4
      3529134.36     10474533.55      3528882.64     10474388.16
      3528535.42     10474333.91        3527841.      10474218.9
#Sta/Elev= 30
    4554  395.21  4629.7  394.08    4769  389.56  4816.5  387.38  4827.9  387.72
    4906  382.48  4926.2  382.06  4956.6  383.84  4976.8  382.51    4983  381.09
    4988  381.29  4994.1  378.82  4996.8  378.32  5000.1  378.82  5017.3  380.73
  5098.3  382.38  5108.4  383.21  5113.5  385.02  5118.6  385.83  5128.6  386.19
  5138.8  385.13  5163.5   385.1  5290.7  390.46  5412.3  392.92  5493.4  396.13
  5554.3  397.54  5574.5  397.35  5608.9  399.21  5838.1  407.19    5900  410.57
#Mann= 5 ,-1 , 0
    4554     .16       0  4816.5     .12       0  4994.1     .07       0
  5000.1     .12       0  5163.5     .16       0
Bank Sta=4988,5017.3
XS Rating Curve= 0 ,0
Exp/Cntr=0.3,0.1

Type RM Length L Ch R = 1 ,25399   ,616,616,616
BEGIN DESCRIPTION:
RUNNING BRANCH 39.0
END DESCRIPTION:
XS GIS Cut Line= 4
      3529204.71     10474505.68      3528933.86     10474026.47
      3528465.11     10473484.81      3528355.72     10473088.93
#Sta/Elev= 30
    4518  393.96  4676.7  391.35  4692.6  390.19  4775.1  387.81  4890.4  384.66
  4900.4  384.66  4962.6  384.23  4978.5  382.92  4984.2  381.88  4997.1  377.46
  4999.9  376.96  5003.1  377.46    5016  380.51  5021.8  382.96  5299.7  384.01
  5378.4   385.5  5420.1  384.93  5534.2  386.71  5584.9  388.52  5664.7  389.16
  5718.4  388.52  5798.4  389.75  5860.7  388.67  6003.5  392.18  6041.2  393.44
  6075.5  396.63  6106.4  398.23  6140.8   399.6    6162   401.5  6195.5  403.95
#Mann= 11 ,-1 , 0
    4518     .16       0  4775.1      .1       0  4890.4     .16       0
  4900.4     .12       0  4997.1     .07       0  5003.1     .12       0
  5584.9     .16       0  5664.7     .12       0  6003.5     .05       0
  6106.4     .12       0    6162     .05       0
#XS Ineff= 2 , 0
                         5670.23          389.19
Permanent Ineff=
       F       F
Bank Sta=4978.5,5021.8
XS Rating Curve= 0 ,0
Exp/Cntr=0.3,0.1

Type RM Length L Ch R = 1 ,24783   ,419,419,419
BEGIN DESCRIPTION:
RUNNING BRANCH 38.1
END DESCRIPTION:
XS GIS Cut Line= 5
      3529571.88     10474672.31      3529454.69     10474086.37
      3528814.07     10473633.24      3528777.61     10473609.81
      3528634.38      10473049.9
#Sta/Elev= 30
  4499.4  394.67  4530.7  391.84  4621.5  387.94  4672.5  383.65  4714.2  383.22
  4728.6  384.78  4824.2  382.46  4840.2  382.42  4932.6  380.43  4959.6  378.55
  4978.5  379.22  4983.6  378.73  4989.6  372.82  4996.8  370.87  4999.5  370.37
  5002.8  370.87    5010  371.48  5020.2  378.21  5029.5  379.22  5223.2  381.69
  5381.8  380.89  5439.9  382.54  5576.5  382.68  5626.8  381.71  5968.4  386.92
  6090.9  384.55  6201.8  386.57  6362.1  394.42  6464.5  397.64  6502.9  399.52
#Mann= 8 ,-1 , 0
  4499.4     .16       0  4824.2      .1       0  4840.2     .16       0
  4959.6     .12       0  4996.8     .07       0  5002.8     .12       0
  6362.1     .05       0  6464.5      .1       0
#XS Ineff= 2 , 0
                         5984.09          386.82
Permanent Ineff=
       F       F
Bank Sta=4978.5,5029.5
XS Rating Curve= 0 ,0
Exp/Cntr=0.3,0.1

Type RM Length L Ch R = 1 ,24364   ,514,514,514
BEGIN DESCRIPTION:
RUNNING BRANCH 38.0
END DESCRIPTION:
XS GIS Cut Line= 5
      3529879.17     10474651.48      3529816.67     10474101.99
      3529329.69     10473927.52        3528900.      10473544.7
        3528900.      10473225.5
#Sta/Elev= 30
  4514.4  395.44  4620.5  391.57  4755.8  387.95  4884.1   380.7  4912.8  379.89
  4967.1  376.74  4978.7  375.28  4987.3  371.46  4994.3  369.43  4997.1  368.93
  5000.3  369.43  5007.4  373.15  5017.5  376.93  5147.3  377.55  5178.5  378.56
  5351.9  380.24  5382.7  379.94  5433.4  381.03  5584.7  381.51  5601.3  380.52
  5658.2  381.66  5962.5  381.44  6019.4   382.9  6233.3  383.27  6283.3  384.42
  6363.3  383.23  6403.3  384.54  6423.3  387.57  6443.3  388.97  6479.4   395.7
#Mann= 4 ,-1 , 0
  4514.4     .16       0  4912.8     .12       0  4994.3     .07       0
  5000.3     .12       0
#XS Ineff= 2 , 0
                         6284.09          384.41
Permanent Ineff=
       F       F
Bank Sta=4967.1,5017.5
XS Rating Curve= 0 ,0
Exp/Cntr=0.3,0.1

Type RM Length L Ch R = 1 ,23850   ,886,886,886
BEGIN DESCRIPTION:
RUNNING BRANCH 37.0
END DESCRIPTION:
XS GIS Cut Line= 4
      3530424.31     10475036.45      3530292.36     10474050.35
      3530170.84     10473772.57      3530094.45     10473258.71
#Sta/Elev= 30
  3889.9  401.12  4020.2  398.58  4126.8   398.3  4236.5  393.44  4302.7  390.18
  4468.4  383.03  4570.7  380.06  4812.9  376.68    4823  371.58  4827.2  371.41
  4843.1  371.25  4853.7  375.84  4873.4   376.8    4969  378.07  4994.9   367.1
  4997.6   366.6  5000.9   367.1  5003.4  369.92  5021.2   374.5  5026.7  378.29
  5036.2  378.35  5044.6  376.52  5090.8  377.88    5226  385.32  5283.2   386.1
  5370.9  390.66  5391.1  390.24  5416.9  392.97  5494.7  396.06  5707.5  404.14
#Mann= 8 ,-1 , 0
  3889.9     .05       0  4236.5      .1       0  4302.7     .16       0
  4827.2     .12       0  4994.9     .07       0  5000.9     .12       0
    5226     .16       0  5494.7      .1       0
#XS Ineff= 1 ,-1
  4812.5 4873.58  376.71
Permanent Ineff=
       F
Bank Sta=4969,5026.7
XS Rating Curve= 0 ,0
Exp/Cntr=0.3,0.1

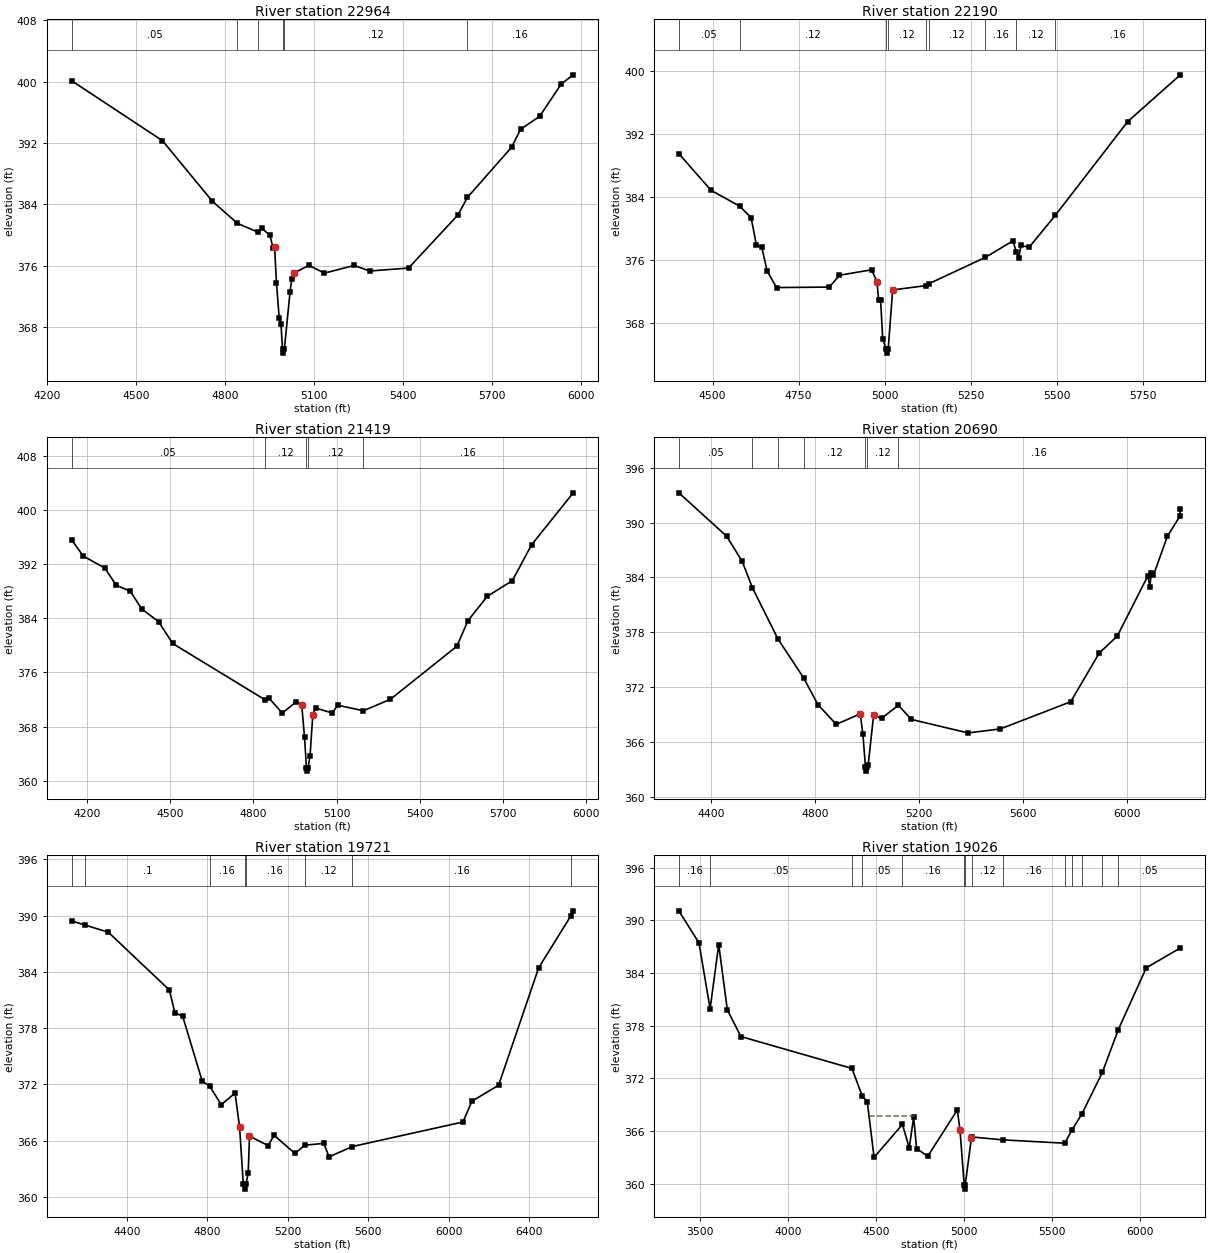
Type RM Length L Ch R = 1 ,22964   ,774,774,774
BEGIN DESCRIPTION:
RUNNING BRANCH 36.0
END DESCRIPTION:
XS GIS Cut Line= 3
      3531320.35     10474633.54      3531127.66     10474263.79
      3530456.42     10473181.48
#Sta/Elev= 30
  4284.3  400.09  4589.8  392.31    4758  384.43  4842.8  381.54  4913.6  380.37
  4925.7  380.87  4952.9  379.97  4962.3  378.38  4968.2   378.4  4974.4  373.79
  4983.6  369.24  4989.5  368.47  4994.9  365.15  4997.7  364.65  5000.9  365.15
  5020.2  372.59  5026.1  374.33  5033.2  375.07    5084  376.08    5136  375.06
  5236.4  376.06  5288.4  375.34  5419.5  375.72  5586.3  382.64    5618  384.91
  5766.7  391.43  5797.5  393.79  5861.2  395.45  5934.5  399.68  5974.8  400.87
#Mann= 6 ,-1 , 0
  4284.3     .05       0  4842.8     .16       0  4913.6     .12       0
  4994.9     .07       0  5000.9     .12       0    5618     .16       0
Bank Sta=4968.2,5033.2
XS Rating Curve= 0 ,0
Exp/Cntr=0.3,0.1

Type RM Length L Ch R = 1 ,22190   ,771,771,771
BEGIN DESCRIPTION:
RUNNING BRANCH 34.0
END DESCRIPTION:
XS GIS Cut Line= 3
      3531692.09     10473941.62      3531392.11     10473441.64
      3530592.08     10473091.63
#Sta/Elev= 30
    4402  389.49  4495.3  384.85  4578.4  382.84  4611.9  381.38  4627.4  377.86
    4643  377.61  4658.5  374.59  4685.7  372.52  4839.3  372.58  4868.4  374.08
  4961.7  374.77  4977.3  373.28  4982.1  370.95  4987.8  370.95    4994  366.06
  5003.9  364.71  5006.6  364.21  5009.9  364.71  5022.9  372.22  5119.1  372.76
  5128.9  373.02  5292.3  376.35  5372.2  378.44    5382     377  5388.9  376.26
  5395.6  377.87  5418.9  377.61  5495.5  381.69  5705.5  393.56  5858.3  399.48
#Mann= 9 ,-1 , 0
    4402     .05       0  4578.4     .12       0  5003.9     .07       0
  5009.9     .12       0  5119.1     .16       0  5128.9     .12       0
  5292.3     .16       0    5382     .12       0  5495.5     .16       0
Bank Sta=4977.3,5022.9
XS Rating Curve= 0 ,0
Exp/Cntr=0.3,0.1

Type RM Length L Ch R = 1 ,21419   ,729,729,729
BEGIN DESCRIPTION:
RUNNING BRANCH 32.0
END DESCRIPTION:
XS GIS Cut Line= 4
      3531889.59      10474189.2       3532021.7     10473513.66
        3532025.      10473043.4      3532042.11     10472391.63
#Sta/Elev= 30
    4144  395.57  4185.3  393.21  4263.8  391.41  4304.5  388.88  4355.5     388
  4396.5  385.39  4457.4  383.51  4508.3  380.28    4841  371.98  4854.4  372.27
  4904.4  370.01  4954.4  371.66  4974.4  371.18  4984.4  366.44  4991.4  361.92
  4994.1  361.42  4997.4  361.92  5004.4   363.7  5014.4  369.77  5024.4  370.75
  5084.4     370  5104.4  371.16  5196.8  370.34  5294.4  372.03  5534.4  379.87
  5574.5  383.65  5644.5  387.26  5734.5  389.55  5804.5  394.88  5954.6  402.54
#Mann= 5 ,-1 , 0
    4144     .05       0    4841     .12       0  4991.4     .07       0
  4997.4     .12       0  5196.8     .16       0
Bank Sta=4974.4,5014.4
XS Rating Curve= 0 ,0
Exp/Cntr=0.3,0.1

Type RM Length L Ch R = 1 ,20690   ,969,969,969
BEGIN DESCRIPTION:
RUNNING BRANCH 31.0
END DESCRIPTION:
XS GIS Cut Line= 4
      3532465.98     10474404.52      3532507.64     10473821.18
      3532570.14     10473546.87      3532948.08     10472555.21
#Sta/Elev= 30
  4276.1  393.26  4459.4  388.52  4519.6  385.76  4559.1  382.85  4657.2  377.26
  4755.3  373.03  4810.3   370.1    4881  367.92  4973.3  369.08  4983.5  366.83
  4993.2  363.31    4996  362.81  4999.2  363.31    5004  363.53  5024.5  368.91
  5055.3  368.59  5119.9  370.02  5169.3  368.47  5387.5  366.99  5511.7  367.43
  5782.1   370.4  5891.8  375.73  5961.2  377.59  6078.9  384.19  6086.3  382.93
  6091.7  384.47  6100.3  384.25  6153.8  388.51  6201.4  390.68  6203.5  391.48
#Mann= 7 ,-1 , 0
  4276.1     .05       0  4559.1      .1       0  4657.2     .16       0
  4755.3     .12       0  4993.2     .07       0  4999.2     .12       0
  5119.9     .16       0
Bank Sta=4973.3,5024.5
XS Rating Curve= 0 ,0
Exp/Cntr=0.3,0.1

Type RM Length L Ch R = 1 ,19721   ,695,695,695
BEGIN DESCRIPTION:
RUNNING BRANCH 30.0
END DESCRIPTION:
XS GIS Cut Line= 4
      3532459.47     10474539.29      3533154.04     10474323.55
      3533354.86     10473446.18       3533119.3     10472614.77
#Sta/Elev= 30
    4126  389.43  4194.2  388.98  4307.7  388.23  4611.3  382.06  4638.6   379.6
  4676.4  379.32  4774.1  372.36  4811.3  371.81  4868.8  369.85  4937.3  371.07
  4959.8  367.47  4978.4  361.35  4985.6  361.34  4988.4  360.84  4991.6  361.34
  5002.7  362.58  5009.1  366.49  5101.5  365.48  5131.5  366.58  5234.8  364.64
  5283.3  365.52  5378.4  365.72  5404.5  364.28    5520  365.38  6069.9     368
  6114.3  370.22  6246.6  371.91  6445.7  384.43  6606.6  390.01  6617.5  390.51
#Mann= 8 ,-1 , 0
    4126     .05       0  4194.2      .1       0  4811.3     .16       0
  4985.6     .07       0  4991.6     .16       0  5283.3     .12       0
    5520     .16       0  6606.6     .05       0
Bank Sta=4959.8,5009.1
XS Rating Curve= 0 ,0
Exp/Cntr=0.3,0.1

Type RM Length L Ch R = 1 ,19026   ,901,901,901
BEGIN DESCRIPTION:
RUNNING BRANCH 29.0
END DESCRIPTION:
XS GIS Cut Line= 2
      3533313.01     10475477.18      3534176.88     10472765.87
#Sta/Elev= 30
  3380.8  391.08    3495  387.43  3558.2  379.92    3607  387.23    3656  379.79
    3733  376.76  4362.9  373.13  4421.6  369.98  4450.1  369.33  4488.6     363
  4649.6  366.75    4688  364.08  4713.1  367.56    4730     364    4793  363.12
  4960.9  368.39    4976  366.15  4999.9  359.88  5002.6  359.38  5005.9  359.88
  5040.5  365.15  5044.4  365.32  5219.5  364.99  5570.7  364.61  5611.3  366.12
  5666.7   367.9  5783.8  372.67  5874.4  377.55  6033.1  384.59  6226.4  386.85
#Mann= 14 ,-1 , 0
  3380.8     .16       0  3558.2     .05       0  4362.9     .07       0
  4421.6     .05       0  4649.6     .16       0  4999.9     .07       0
  5005.9     .16       0  5044.4     .12       0  5219.5     .16       0
  5570.7     .05       0  5611.3     .16       0  5666.7     .05       0
  5783.8     .16       0  5874.4     .05       0
#XS Ineff= 1 ,-1
 4459.66  4714.2  367.67
Permanent Ineff=
       F
Bank Sta=4976,5040.5
XS Rating Curve= 0 ,0
Exp/Cntr=0.3,0.1