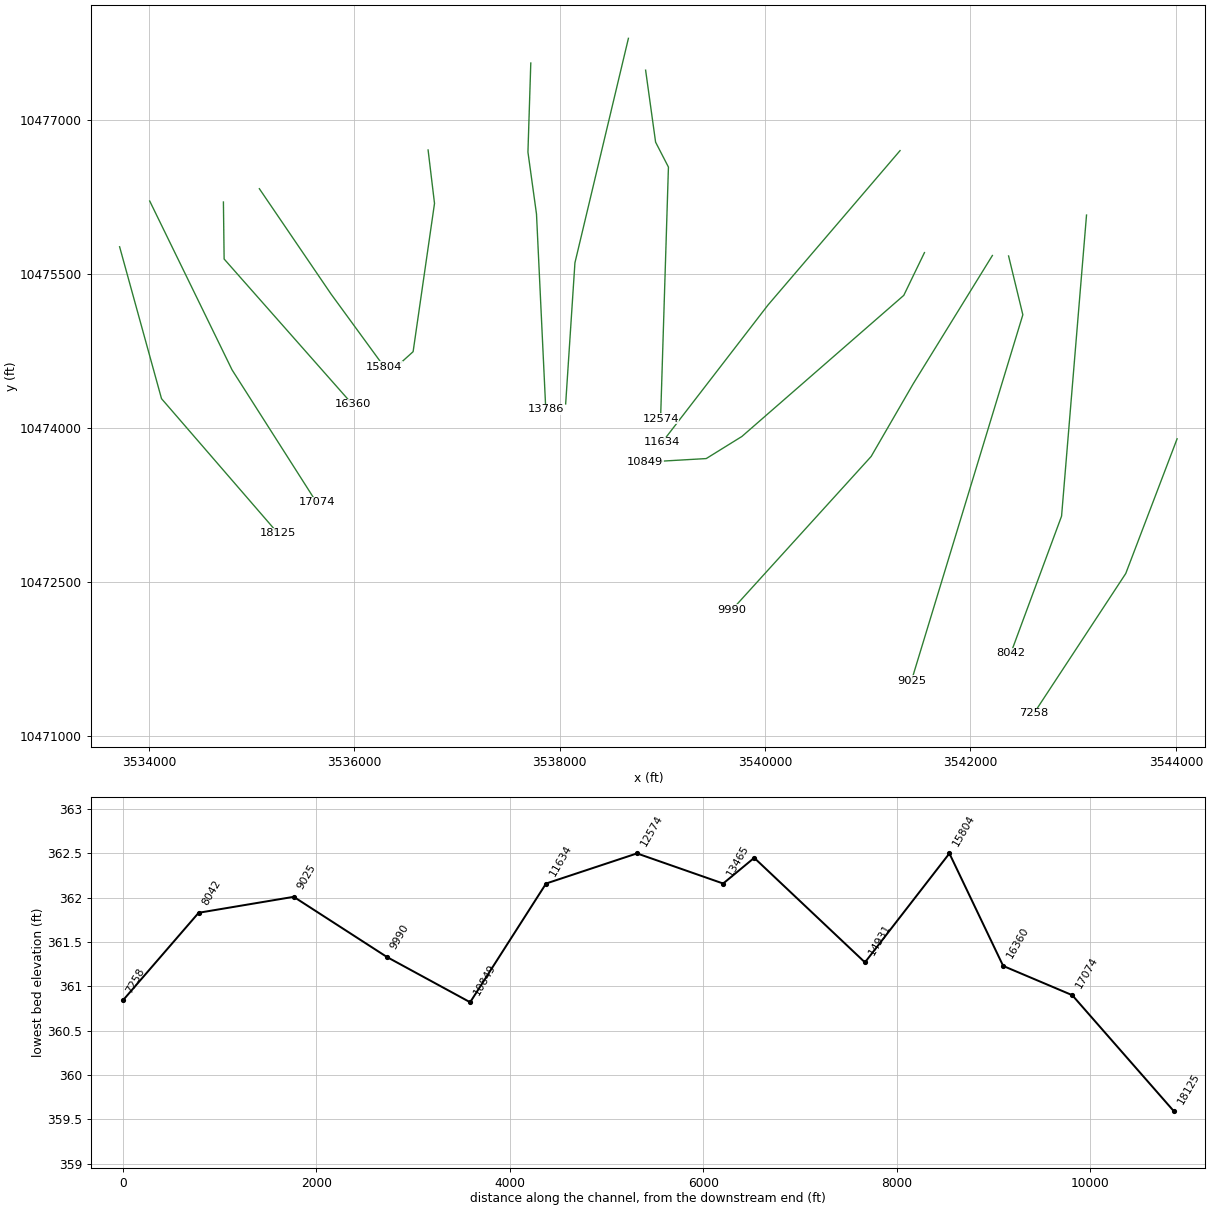
HEC-RAS study RUNNING BRANCH.prj: RUNNING BRANCH Base Level Engineering

--- RUNNING BRANCH.g01 (geometry) --- (continued)

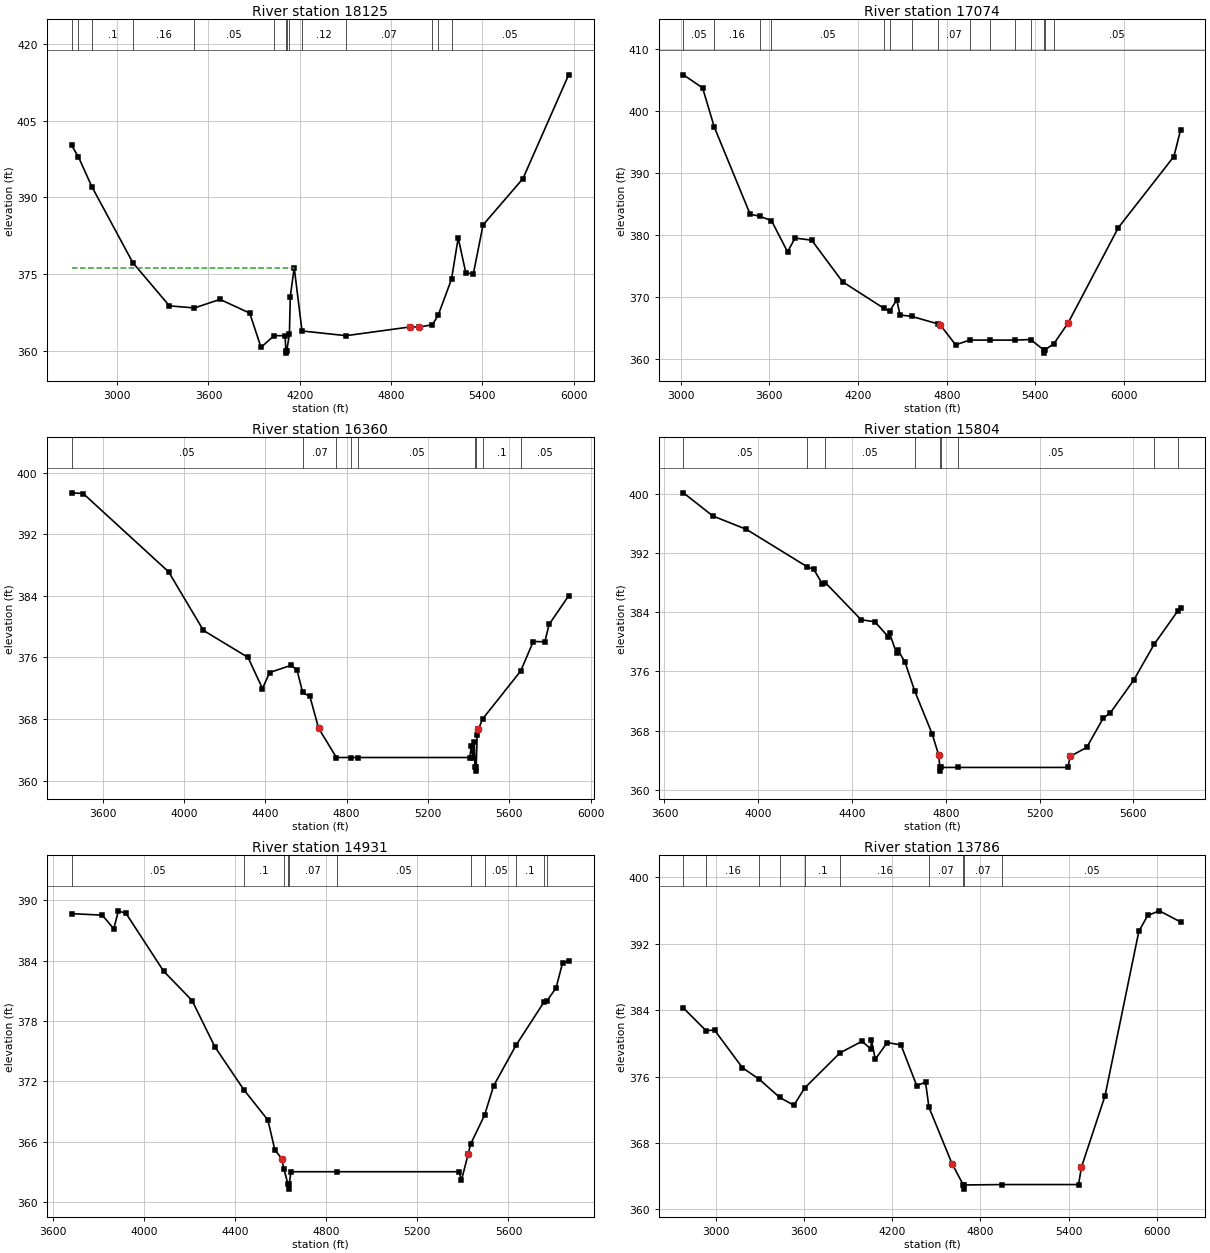
Type RM Length L Ch R = 1 ,18125   ,1051,1051,1051
BEGIN DESCRIPTION:
RUNNING BRANCH 28.0
END DESCRIPTION:
XS GIS Cut Line= 3
      3533714.92     10475762.77       3534122.9     10474282.76
      3535255.74     10472971.96
#Sta/Elev= 30
  2699.7   400.2  2745.2  397.92  2832.9  392.13  3102.7  377.26  3343.2  368.82
  3507.9  368.42  3675.9  370.09  3871.1   367.4  3945.1  360.72  4031.2     363
  4103.3     363  4108.6  360.09  4111.3  359.59  4114.6  360.09  4131.9  363.27
  4137.7  370.65  4163.5   376.3  4214.7  363.92  4504.4     363  4923.3   364.7
  4986.9   364.7  5072.2  365.13    5110  367.02  5197.4  374.03  5241.4   382.1
  5291.9   375.2  5341.2  375.13  5404.9  384.64    5667  393.69  5967.4  413.96
#Mann= 14 ,-1 , 0
  2699.7      .1       0  2745.2     .05       0  2832.9      .1       0
  3102.7     .16       0  3507.9     .05       0  4031.2     .07       0
  4108.6     .07       0  4114.6     .07       0  4131.9     .16       0
  4214.7     .12       0  4504.4     .07       0  5072.2     .16       0
    5110      .1       0  5197.4     .05       0
#XS Ineff= 2 , 0
         4164.49  376.28
Permanent Ineff=
       F       F
Bank Sta=4923.3,4986.9
XS Rating Curve= 0 ,0
Exp/Cntr=0.3,0.1

Type RM Length L Ch R = 1 ,17074   ,714,714,714
BEGIN DESCRIPTION:
RUNNING BRANCH 27.0
END DESCRIPTION:
XS GIS Cut Line= 3
      3534007.98      10476208.7      3534810.07     10474562.85
      3535632.97     10473271.21
#Sta/Elev= 30
  3019.3  405.77  3149.1  403.66  3228.1  397.34  3470.2  383.31    3534  382.97
  3614.3  382.28  3723.7  377.23  3774.3  379.45    3887  379.11  4095.4  372.41
  4374.1  368.14  4413.3  367.66  4462.2  369.47  4484.4  367.05  4563.5  366.82
  4740.1  365.62  4754.5   365.5  4860.4  362.24  4955.7     363  5089.7     363
  5260.3     363  5367.1  363.09  5457.6   361.4  5460.3   360.9  5463.6   361.4
  5525.1  362.43  5621.4  365.77  5960.8  381.13  6336.6   392.6  6381.7  396.87
#Mann= 15 ,-1 , 0
  3019.3     .05       0  3228.1     .16       0    3534      .1       0
  3614.3     .05       0  4374.1      .1       0  4413.3     .05       0
  4563.5     .16       0  4740.1     .07       0  4955.7     .05       0
  5089.7      .1       0  5260.3     .12       0  5367.1     .07       0
  5457.6    .033       0  5463.6     .07       0  5525.1     .05       0
Bank Sta=4754.5,5621.4
XS Rating Curve= 0 ,0
Exp/Cntr=0.3,0.1

Type RM Length L Ch R = 1 ,16360   ,556,556,556
BEGIN DESCRIPTION:
RUNNING BRANCH 26.0
END DESCRIPTION:
XS GIS Cut Line= 3
      3534725.75     10476198.92      3534732.69     10475643.34
      3535982.68     10474226.69
#Sta/Elev= 30
    3447  397.39  3504.3   397.3  3924.3  387.13  4095.8  379.51  4314.9  376.01
  4386.1  371.96  4421.2  374.04  4527.4  374.98  4555.9  374.36  4583.9  371.45
  4619.4  370.93  4662.1  366.81  4749.7     363  4819.6     363  4857.2     363
  5405.8     363  5413.4   364.5  5420.1     363  5427.6  364.97  5431.3  361.73
    5434  361.23  5437.3  361.73  5441.8  365.88  5448.5   366.7  5469.1  368.02
  5656.3  374.25  5717.9  378.07  5774.8  378.04  5795.7  380.29  5891.9  384.01
#Mann= 9 ,-1 , 0
    3447     .05       0  4583.9     .07       0  4749.7     .16       0
  4819.6     .07       0  4857.2     .05       0  5431.3    .033       0
  5437.3     .05       0  5469.1      .1       0  5656.3     .05       0
Bank Sta=4662.1,5448.5
XS Rating Curve= 0 ,0
Exp/Cntr=0.3,0.1

Type RM Length L Ch R = 1 ,15804   ,873,873,873
BEGIN DESCRIPTION:
RUNNING BRANCH 25.0
END DESCRIPTION:
XS GIS Cut Line= 3
      3535075.69     10476328.48      3535773.61     10475302.43
      3536292.09     10474591.66
#Sta/Elev= 30
    3681  400.19  3806.1  397.06  3949.8  395.24  4208.7  390.18  4237.1  389.82
    4273  387.89  4285.9  388.04  4439.1     383  4497.5  382.73  4554.4  380.72
  4560.4  381.18  4590.3  378.44  4596.3  378.89  4626.2  377.26  4667.4  373.37
  4741.5  367.58  4769.9  364.69  4774.7     363  4777.5   362.5  4780.7     363
  4852.7     363  5321.6     363  5330.1  364.49  5401.2  365.71  5472.3   369.7
  5501.6  370.37    5602  374.83  5689.1  379.68    5789  384.15  5801.7  384.57
#Mann= 9 ,-1 , 0
    3681     .05       0  4208.7      .1       0  4285.9     .05       0
  4667.4     .07       0  4774.7    .033       0  4780.7     .07       0
  4852.7     .05       0  5689.1      .1       0    5789     .05       0
Bank Sta=4769.9,5330.1
XS Rating Curve= 0 ,0
Exp/Cntr=0.3,0.1

Type RM Length L Ch R = 1 ,14931   ,1145,1145,1145
BEGIN DESCRIPTION:
RUNNING BRANCH 23.0
END DESCRIPTION:
XS GIS Cut Line= 4
      3536718.81     10476705.81       3536781.3     10476185.01
      3536572.97     10474740.57      3536427.13     10474608.62
#Sta/Elev= 30
  3683.3  388.66  3818.4  388.51  3868.8  387.15  3888.9  388.94  3922.5  388.68
    4087  382.95  4212.1  380.02  4312.3  375.41  4439.2  371.15  4544.7  368.14
    4575  365.18  4605.3  364.31  4614.4  363.31  4632.6  361.77  4635.3  361.27
  4638.6  361.77  4645.7     363  4848.7     363  5383.2     363  5393.4  362.13
  5423.4  364.78  5433.5  365.73  5495.1  368.63  5534.8  371.54  5632.9  375.57
  5755.2  379.85  5767.6  379.96  5808.6  381.27    5837  383.75  5863.9  383.95
#Mann= 11 ,-1 , 0
  3683.3     .05       0  4439.2      .1       0  4614.4     .07       0
  4632.6    .033       0  4638.6     .07       0  4848.7     .05       0
  5433.5      .1       0  5495.1     .05       0  5632.9      .1       0
  5755.2     .05       0  5767.6      .1       0
Bank Sta=4605.3,5423.4
XS Rating Curve= 0 ,0
Exp/Cntr=0.3,0.1

Type RM Length L Ch R = 1 ,13786   ,321,321,321
BEGIN DESCRIPTION:
RUNNING BRANCH 21.0
END DESCRIPTION:
XS GIS Cut Line= 4
       3537718.8     10477553.05      3537691.03     10476685.01
      3537774.36     10476080.84      3537864.64     10474178.05
#Sta/Elev= 30
  2778.9  384.24  2932.5  381.52  2990.4  381.59  3180.5  377.06  3295.4  375.66
  3434.4  373.48  3530.7  372.54  3603.7  374.61  3844.8  378.85    3994  380.24
  4053.7  379.33  4058.7  380.34  4084.9  378.08  4165.6  380.09  4259.4   379.8
  4366.6   374.9  4426.7  375.32  4449.6  372.31  4606.9  365.51    4684  362.95
  4686.7  362.45    4690  362.95  4949.4     363  5467.8     363  5487.9  365.11
    5648  373.67  5878.3  393.47  5938.4  395.38  6018.4  395.94  6162.2   394.6
#Mann= 10 ,-1 , 0
  2778.9      .1       0  2932.5     .16       0  3295.4     .05       0
  3434.4     .16       0  3603.7      .1       0  3844.8     .16       0
  4449.6     .07       0    4684    .033       0    4690     .07       0
  4949.4     .05       0
Bank Sta=4606.9,5487.9
XS Rating Curve= 0 ,0
Exp/Cntr=0.3,0.1

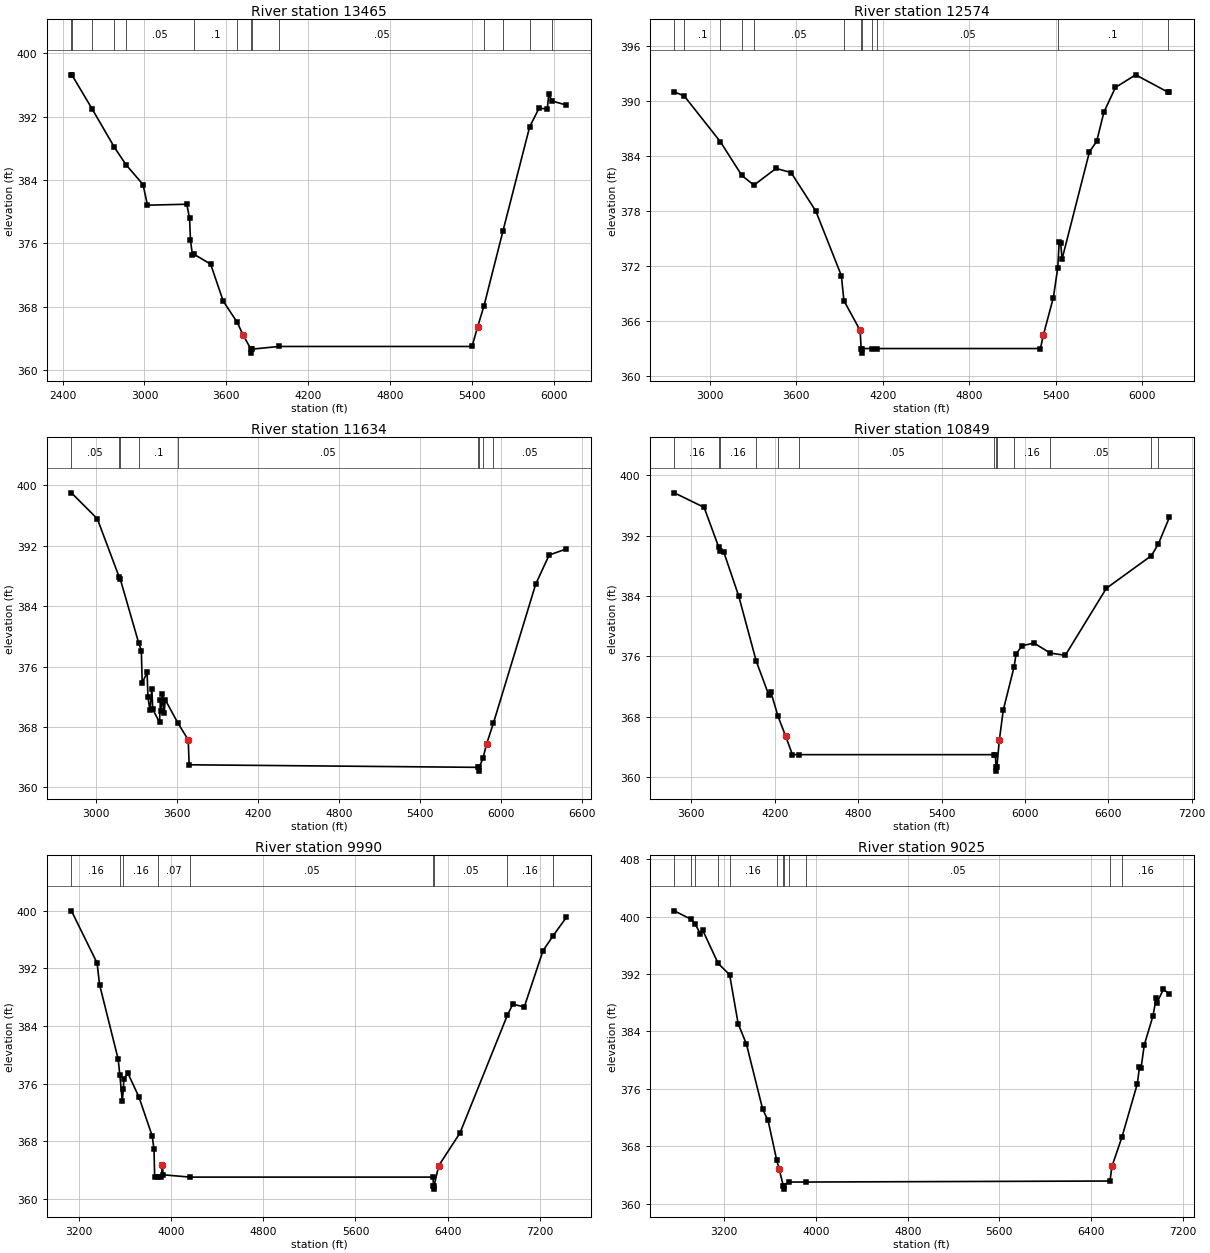
Type RM Length L Ch R = 1 ,13465   ,891,891,891
BEGIN DESCRIPTION:
RUNNING BRANCH 19.0
END DESCRIPTION:
XS GIS Cut Line= 3
      3538669.44     10477793.73      3538148.61     10475606.25
      3538058.34     10474231.23
#Sta/Elev= 30
  2465.2  397.26  2470.6  397.19  2615.5     393  2779.6  388.13  2864.9  385.93
  2989.9  383.42  3022.4  380.82  3310.3  380.94  3330.8  379.16  3337.4  376.39
  3351.4  374.59  3360.4  374.66    3485  373.38  3577.5  368.71  3679.6  366.05
  3721.4   364.5  3780.1  362.66  3782.9  362.16  3786.1  362.66  3985.1     363
  5399.9     363    5440  365.43  5487.2   368.1    5626  377.53    5822   390.7
    5891  393.06  5951.1  392.94    5962   394.8  5985.5  393.96  6091.8  393.44
#Mann= 14 ,-1 , 0
  2465.2     .05       0  2470.6     .16       0  2615.5     .05       0
  2779.6     .16       0  2864.9     .05       0  3360.4      .1       0
  3679.6     .07       0  3780.1    .033       0  3786.1     .07       0
  3985.1     .05       0  5487.2     .16       0    5626     .05       0
    5822     .16       0  5985.5     .05       0
Bank Sta=3721.4,5440
XS Rating Curve= 0 ,0
Exp/Cntr=0.3,0.1

Type RM Length L Ch R = 1 ,12574   ,940,940,940
BEGIN DESCRIPTION:
RUNNING BRANCH 18.0
END DESCRIPTION:
XS GIS Cut Line= 4
      3538836.86      10477483.6      3538934.08     10476782.23
      3539059.08     10476539.18      3538982.69     10474087.76
#Sta/Elev= 30
    2754  390.97  2822.8  390.53  3074.4  385.52  3222.5  381.86  3306.5  380.81
  3459.9  382.63  3563.9  382.18  3735.4  377.99    3913  370.94  3930.4  368.22
  4043.1  364.98  4050.1     363  4052.8   362.5  4056.1     363    4127     363
    4161     363  5293.7     363  5313.7  364.46  5383.7  368.56  5413.8  371.81
  5423.7  374.56  5433.8  374.54  5443.8  372.75  5633.8  384.44  5683.9  385.58
  5733.9  388.76  5813.9  391.45    5954  392.83  6179.8  390.93    6188  390.94
#Mann= 12 ,-1 , 0
    2754     .05       0  2822.8      .1       0  3074.4     .05       0
  3222.5      .1       0  3306.5     .05       0  3930.4      .1       0
  4050.1    .033       0  4056.1      .1       0    4127     .07       0
    4161     .05       0  5413.8      .1       0  6179.8     .05       0
Bank Sta=4043.1,5313.7
XS Rating Curve= 0 ,0
Exp/Cntr=0.3,0.1

Type RM Length L Ch R = 1 ,11634   ,785,785,785
BEGIN DESCRIPTION:
RUNNING BRANCH 15.0
END DESCRIPTION:
XS GIS Cut Line= 3
      3541314.41     10476699.56      3540027.95     10475194.36
      3538997.24     10473856.51
#Sta/Elev= 30
  2819.2  399.01  3011.2  395.57  3172.7  387.88  3181.4  387.58  3318.1  379.11
  3337.2  378.13  3343.8  373.84    3380  375.22  3386.6  371.94  3400.9  370.23
  3415.2   373.1  3421.7  370.34  3472.2  368.63  3478.8  371.57  3486.5   370.1
  3493.1  372.42  3507.4  369.92  3513.9  371.63    3609   368.5  3684.7  366.31
  3691.8     363  5835.5  362.66  5838.3  362.16  5841.5  362.66  5869.5  363.89
  5896.5  365.78  5946.8  368.53  6259.8  386.91  6359.5  390.77  6488.1  391.59
#Mann= 9 ,-1 , 0
  2819.2     .05       0  3172.7      .1       0  3181.4     .05       0
  3318.1      .1       0    3609     .05       0  5835.5    .033       0
  5841.5     .05       0  5869.5      .1       0  5946.8     .05       0
Bank Sta=3684.7,5896.5
XS Rating Curve= 0 ,0
Exp/Cntr=0.3,0.1

Type RM Length L Ch R = 1 ,10849   ,859,859,859
BEGIN DESCRIPTION:
RUNNING BRANCH 13.0
END DESCRIPTION:
XS GIS Cut Line= 5
      3541552.15     10475705.86      3541350.75     10475289.18
      3539774.36     10473914.18      3539427.14      10473698.9
      3538829.89     10473664.18
#Sta/Elev= 30
  3477.7  397.65    3692  395.73  3797.3  390.46  3805.2  390.01  3833.1  389.84
  3940.5  384.03  4067.1  375.38  4157.5  370.89  4171.7  371.34  4224.2  368.06
  4278.1  365.48  4327.4     363  4376.5     363    5781     363  5787.5     363
  5792.1  361.32  5794.8  360.82  5798.1  361.32    5816  364.92  5844.4  368.91
    5922  374.61  5936.5  376.33  5979.2  377.41    6065  377.77    6183  376.44
  6290.6  376.15  6586.1  385.02  6909.7  389.33  6958.9  390.84  7039.1  394.39
#Mann= 13 ,-1 , 0
  3477.7     .16       0  3797.3     .05       0  3805.2     .16       0
  4067.1      .1       0  4224.2     .07       0  4376.5     .05       0
    5781      .1       0  5792.1    .033       0  5798.1      .1       0
    5922     .16       0    6183     .05       0  6909.7     .16       0
  6958.9      .1       0
Bank Sta=4278.1,5816
XS Rating Curve= 0 ,0
Exp/Cntr=0.3,0.1

Type RM Length L Ch R = 1 ,9990    ,965,965,965
BEGIN DESCRIPTION:
RUNNING BRANCH 12.0
END DESCRIPTION:
XS GIS Cut Line= 4
      3542213.57     10475677.67      3541442.75     10474427.69
      3541033.02     10473719.36      3539679.01     10472226.47
#Sta/Elev= 30
  3131.5  399.99  3354.7  392.74  3375.9  389.75    3538  379.37  3552.2  377.18
  3573.3  373.61  3583.6  375.25  3586.5  376.65  3623.1   377.4  3717.7  374.15
  3833.6  368.71    3849  366.87  3855.2     363  3884.7     363    3914  363.08
  3922.4  364.75  3928.3  363.32  4162.6     363  6274.1     363  6277.8  361.83
  6280.6  361.33  6283.8  361.83  6323.4  364.58  6507.9  369.12  6919.8  385.48
  6967.8  387.03  7066.8  386.63  7229.6  394.44  7317.2  396.52  7433.8  399.11
#Mann= 9 ,-1 , 0
  3131.5     .16       0  3552.2     .05       0  3583.6     .16       0
  3884.7     .07       0  4162.6     .05       0  6277.8    .033       0
  6283.8     .05       0  6919.8     .16       0  7317.2     .05       0
Bank Sta=3922.4,6323.4
XS Rating Curve= 0 ,0
Exp/Cntr=0.3,0.1

Type RM Length L Ch R = 1 ,9025    ,983,983,983
BEGIN DESCRIPTION:
RUNNING BRANCH 10.0
END DESCRIPTION:
XS GIS Cut Line= 3
      3542371.23     10475673.03      3542510.12     10475100.08
      3541425.06     10471532.38
#Sta/Elev= 30
  2763.7  400.82  2908.7  399.65  2946.2     399  2991.5  397.58  3012.1   398.1
  3146.3  393.48  3246.3  391.91  3320.8  385.08  3393.1  382.23    3535  373.13
  3581.6   371.6  3657.5  366.02  3676.9  364.88  3714.4  362.51  3717.2  362.01
  3720.4  362.51  3761.3     363  3916.7     363  6564.3  363.14  6581.4  365.18
  6668.2  369.24  6803.2  376.72  6821.8  379.11  6836.1  378.95  6863.6  382.13
  6939.9  386.18  6967.5  388.73  6972.7  387.94  7030.8   389.9  7082.3  389.19
#Mann= 12 ,-1 , 0
  2763.7     .16       0  2908.7     .05       0  2946.2     .16       0
  3146.3     .05       0  3246.3     .16       0  3657.5      .1       0
  3714.4    .033       0  3720.4      .1       0  3761.3     .07       0
  3916.7     .05       0  6564.3     .07       0  6668.2     .16       0
Bank Sta=3676.9,6581.4
XS Rating Curve= 0 ,0
Exp/Cntr=0.3,0.1

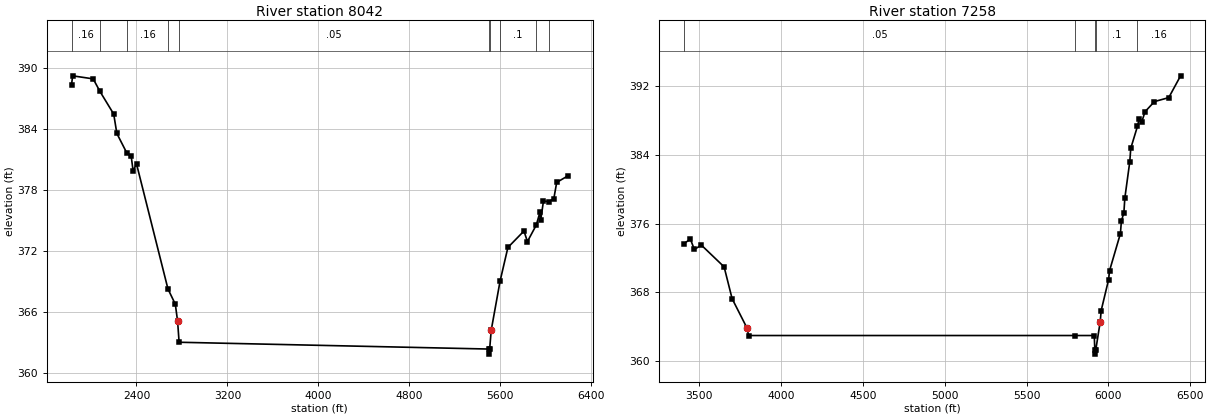
Type RM Length L Ch R = 1 ,8042    ,784,784,784
BEGIN DESCRIPTION:
RUNNING BRANCH 9.0
END DESCRIPTION:
XS GIS Cut Line= 3
      3543130.25     10476071.78      3542887.19     10473137.76
       3542392.4     10471800.96
#Sta/Elev= 30
  1828.6  388.36  1838.8  389.25  2019.4  388.95    2079  387.71    2200  385.48
  2227.6  383.57    2317  381.61  2353.4  381.35  2370.6  379.89  2400.7  380.57
  2677.2  368.25  2741.9  366.75  2761.9  365.08  2775.3     363  5501.3  362.33
    5504  361.83  5507.3  362.33  5521.1  364.19    5599  369.03  5667.8  372.34
  5809.1  373.96  5839.5  372.92  5917.6  374.55  5950.4  375.84  5955.8     375
  5980.8  376.92  6027.7  376.85    6072  377.16  6097.1  378.75  6198.1  379.41
#Mann= 10 ,-1 , 0
  1828.6     .16       0    2079     .05       0    2317     .16       0
  2677.2      .1       0  2775.3     .05       0  5501.3    .033       0
  5507.3     .05       0    5599      .1       0  5917.6     .05       0
  6027.7     .16       0
Bank Sta=2761.9,5521.1
XS Rating Curve= 0 ,0
Exp/Cntr=0.3,0.1

Type RM Length L Ch R = 1 ,7258    ,812,812,812
BEGIN DESCRIPTION:
RUNNING BRANCH 7.0
END DESCRIPTION:
XS GIS Cut Line= 3
       3544012.2     10473891.25      3543512.19     10472578.73
      3542617.56     10471215.99
#Sta/Elev= 30
  3406.3  373.67    3446  374.19  3470.1  372.99  3512.9   373.5    3652  370.97
  3700.8  367.28  3791.1   363.9  3801.8     363  5797.2     363  5913.6     363
  5916.9  361.34  5919.6  360.84  5922.9  361.34  5949.8  364.58  5955.8   365.9
  6001.1  369.48    6007  370.53  6073.4  374.84  6079.4   376.3  6094.5  377.25
  6100.4  378.96  6130.6  383.18  6136.6  384.73  6177.7   387.3  6187.9  388.16
    6203  387.76    6224  388.99  6281.3  390.16  6368.7  390.62    6441  393.15
#Mann= 5 ,-1 , 0
  3406.3     .05       0  5797.2      .1       0  5916.9    .033       0
  5922.9      .1       0  6177.7     .16       0
Bank Sta=3791.1,5949.8
XS Rating Curve= 0 ,0
Exp/Cntr=0.3,0.1