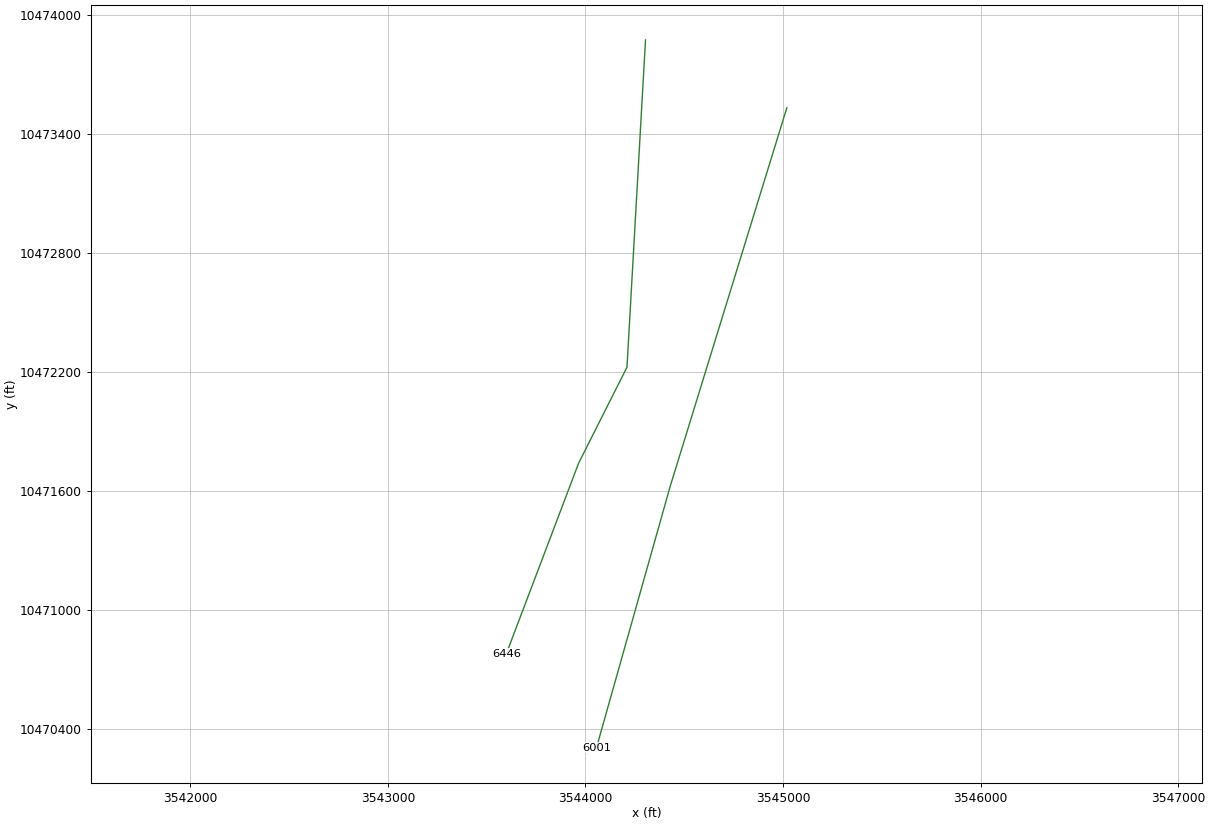
HEC-RAS study RUNNING BRANCH.prj: RUNNING BRANCH Base Level Engineering

--- RUNNING BRANCH.g01 (geometry) --- (continued)

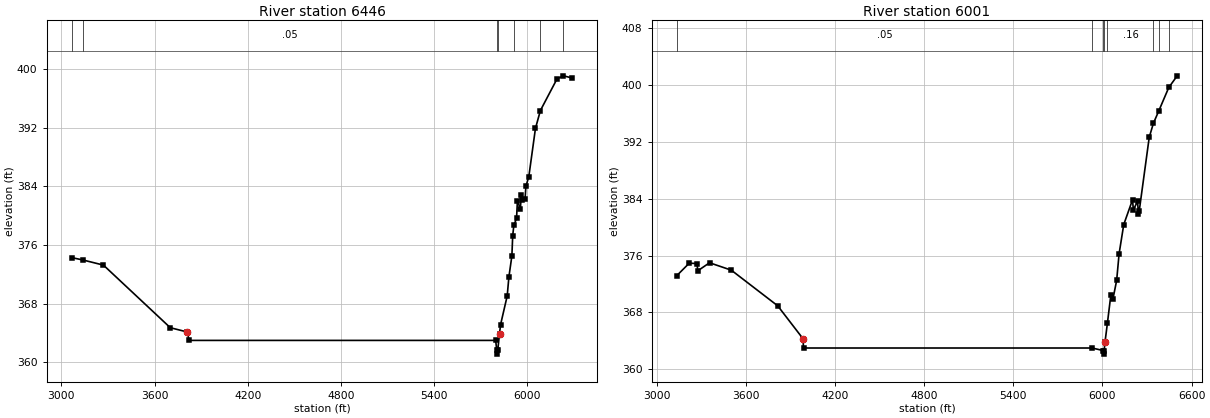
Type RM Length L Ch R = 1 ,6446    ,445,445,445
BEGIN DESCRIPTION:
RUNNING BRANCH 1.1
END DESCRIPTION:
XS GIS Cut Line= 4
      3544303.86     10473875.63      3544210.11     10472224.56
      3543965.32     10471740.19      3543599.86     10470779.71
#Sta/Elev= 30
  3066.4  374.28  3138.5  373.96  3270.7  373.26  3701.4  364.73  3811.6  364.14
  3821.6     363  5796.8     363    5804  361.63  5806.7  361.13    5810  361.63
  5821.6  363.91  5828.4  365.15  5871.1  369.06  5881.9  371.63  5901.2  374.51
  5906.6  377.28  5913.8  378.67  5931.3  379.62  5936.7  381.96  5956.1  380.95
  5961.5  382.77  5967.4  382.08  5986.2  382.28  5991.6  384.02  6010.2   385.3
    6053  391.88  6084.8  394.32  6192.1  398.64  6233.6  399.05  6290.5  398.75
#Mann= 7 ,-1 , 0
  3066.4     .16       0  3138.5     .05       0    5804    .033       0
    5810     .05       0  5913.8     .16       0  6084.8     .05       0
  6233.6     .16       0
Bank Sta=3811.6,5821.6
XS Rating Curve= 0 ,0
Exp/Cntr=0.3,0.1

Type RM Length L Ch R = 1 ,6001    ,0,0,0
BEGIN DESCRIPTION:
RUNNING BRANCH 1.0
END DESCRIPTION:
XS GIS Cut Line= 3
      3545019.12     10473533.55      3544428.86     10471623.87
      3544055.91     10470305.53
#Sta/Elev= 30
  3133.9  373.14  3219.6  374.93  3271.5  374.86  3276.7  373.85  3355.7  374.98
  3502.2  373.94  3814.5  368.93 3984.61  364.31  3988.1     363  5930.5     363
    6005  362.64  6007.7  362.14    6011  362.64    6017  363.83  6033.6  366.57
  6056.2  370.43  6070.4  369.89  6095.3  372.49  6111.9  376.26  6143.1  380.35
  6202.4  383.84  6207.6  382.42  6236.3  383.62  6241.5  381.84    6247  382.22
  6314.6  392.61    6343   394.6  6377.6  396.26  6446.1  399.61  6502.8  401.25
#Mann= 8 ,-1 , 0
  3133.9     .05       0  5930.5      .1       0    6005    .033       0
    6011      .1       0  6033.6     .16       0    6343     .05       0
  6377.6     .16       0  6446.1     .05       0
Bank Sta=3984.61,6017
XS Rating Curve= 0 ,0
Exp/Cntr=0.3,0.1

Chan Stop Cuts=-1
Use User Specified Reach Order=0
Composite Channel Slope=5