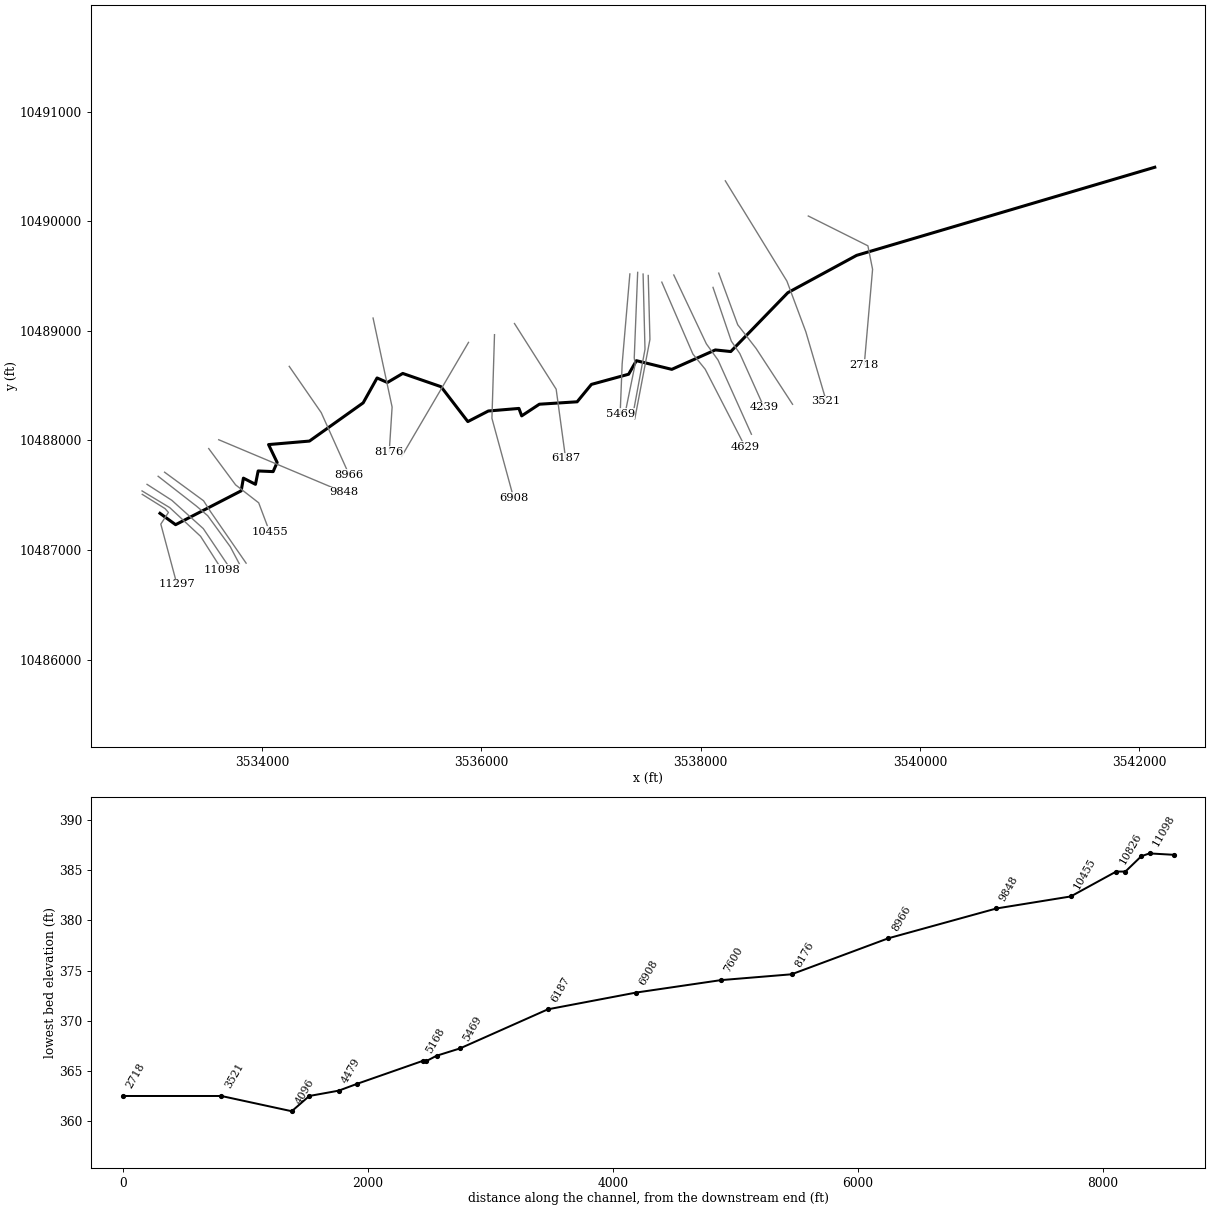
--- SANDBRANCH2.prj (project) ---

Proj Title=SAND BRANCH 2 Base Level Engineerin
Current Plan=p01
Default Exp/Contr=0.3,0.1
English Units
Geom File=g01
Flow File=f01
Plan File=p01
Y Axis Title=Elevation
X Axis Title(PF)=Main Channel Distance
X Axis Title(XS)=Station
BEGIN DESCRIPTION:
UNT0179 IN SAND CR
END DESCRIPTION:
DSS Export Rating Curves= 0
DSS Export Rating Curve Sorted= 0
DSS Export Volume Flow Curves= 0
DXF OffsetX= 0
DXF OffsetY= 0
DXF ScaleX= 1
DXF ScaleY= 10

--- SANDBRANCH2.p01 (plan) ---

Plan Title=Multiple Run
Short Identifier=Multiple
Geom File=g01
Flow File=f01
Subcritical Flow
K Sum by GR= 0
Std Step Tol= 0.01
Critical Tol= 0.01
Num of Std Step Trials= 20
Max Error Tol= 0.3
Flow Tol Ratio= 0.001
Split Flow NTrial= 30
Split Flow Tol= 0.02
Split Flow Ratio= 0.02
Log Output Level= 0
Friction Slope Method= 1
Unsteady Friction Slope Method= 2
Unsteady Bridges Friction Slope Method= 1
Parabolic Critical Depth
Global Vel Dist=  1 , 1 , 1
Global Log Level= 0
CheckData=True
Encroach Param= -1, 0, 0, 0
BEGIN DESCRIPTION:
Multiple Run
END DESCRIPTION:

--- SANDBRANCH2.f01 (steady flow) ---

Flow Title=Multiple
Program Version=4.10
Number of Profiles= 7
Profile Names=10-year,25-year,50-year,1pct_min,100-year,1pct_plu,500-year
River Rch & RM=UNT0179 IN SAND,Reach-1         ,11297
     860    1180    1444    1292    1747    2362    2546
River Rch & RM=UNT0179 IN SAND,Reach-1         ,10826
    1158    1609    1984    1786    2415    3266    3567
River Rch & RM=UNT0179 IN SAND,Reach-1         ,4239
    1189    1646    2025    1817    2457    3323    3607
River Rch & RM=SAND BRANCH 2,Reach-1         ,11297
     860    1180    1444    1292    1747    2362    2546
River Rch & RM=SAND BRANCH 2,Reach-1         ,10826
    1158    1609    1984    1786    2415    3266    3567
River Rch & RM=SAND BRANCH 2,Reach-1         ,4239
    1189    1646    2025    1817    2457    3323    3607
Boundary for River Rch & Prof#=SAND BRANCH 2,Reach-1         , 1
Up Type= 0
Dn Type= 3
Dn Slope=0.005
Boundary for River Rch & Prof#=SAND BRANCH 2,Reach-1         , 2
Up Type= 0
Dn Type= 3
Dn Slope=0.005
Boundary for River Rch & Prof#=SAND BRANCH 2,Reach-1         , 3
Up Type= 0
Dn Type= 3
Dn Slope=0.005
Boundary for River Rch & Prof#=SAND BRANCH 2,Reach-1         , 4
Up Type= 0
Dn Type= 3
Dn Slope=0.005
Boundary for River Rch & Prof#=SAND BRANCH 2,Reach-1         , 5
Up Type= 0
Dn Type= 3
Dn Slope=0.005
Boundary for River Rch & Prof#=SAND BRANCH 2,Reach-1         , 6
Up Type= 0
Dn Type= 3
Dn Slope=0.005
Boundary for River Rch & Prof#=SAND BRANCH 2,Reach-1         , 7
Up Type= 0
Dn Type= 3
Dn Slope=0.005
DSS Import GetInterval= 0
DSS Import GetPeak= 0
DSS Import FillOption= 0

--- SANDBRANCH2.g01 (geometry) ---

Geom Title=Existing Conditions
Program Version=4.10

River Reach=SAND BRANCH 2   ,Reach-1
Reach XY= 30
      3533067.64     10487334.75      3533210.22     10487231.25
      3533808.34     10487539.99      3533828.71     10487655.76
      3533938.79     10487599.38      3533963.18     10487721.27
      3534099.87     10487715.35      3534136.33     10487799.09
      3534058.09      10487961.9      3534431.15     10487993.88
      3534921.18     10488342.62      3535048.02     10488569.69
      3535141.86     10488528.21      3535282.17     10488610.82
      3535631.43     10488489.88      3535875.92     10488171.71
      3536063.18     10488268.28      3536342.11     10488291.64
      3536367.06     10488223.79      3536528.18     10488330.04
      3536872.97     10488352.26      3537003.18     10488510.95
      3537342.53     10488603.65      3537413.36     10488727.26
      3537736.28      10488648.1       3538133.5     10488825.18
      3538274.47      10488810.6       3538794.8     10489347.35
      3539422.31     10489687.93      3542142.11     10490491.64

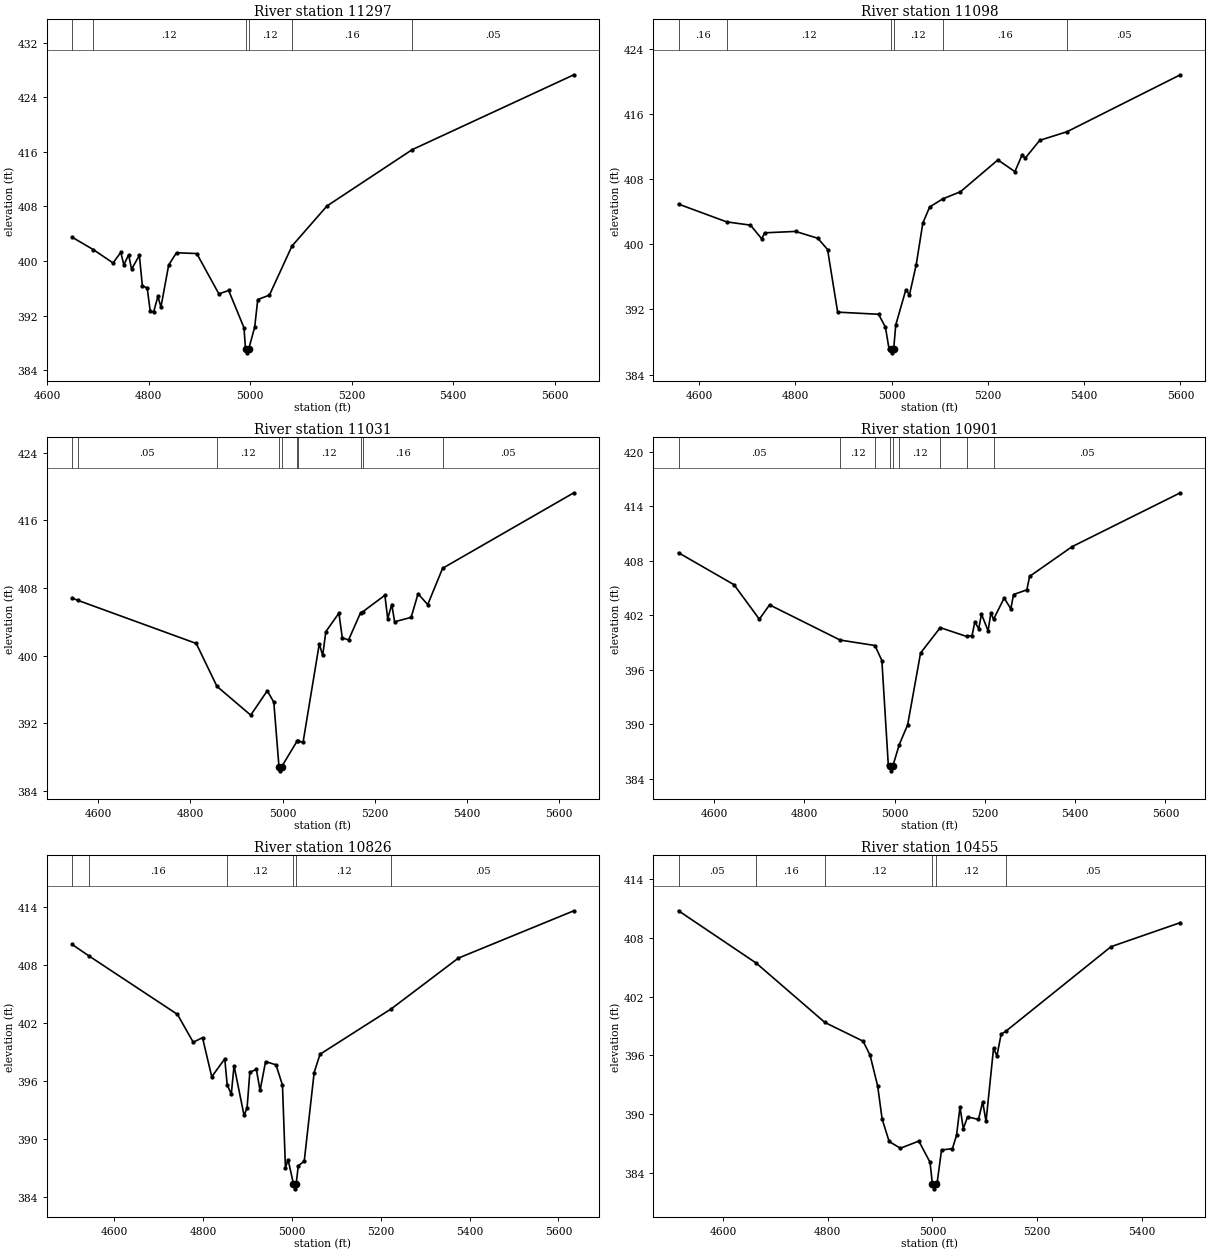
Type RM Length L Ch R = 1 ,11297   ,199,199,199
BEGIN DESCRIPTION:
UNT0179 IN SAND CR 21.03
END DESCRIPTION:
XS GIS Cut Line= 5
      3532906.03     10487507.82       3533114.4     10487377.59
      3533144.78     10487342.87      3533075.33     10487236.53
      3533222.73     10486685.98
#Sta/Elev= 30
  4648.9  403.49  4690.7  401.67  4729.7  399.71    4745  401.28  4750.9  399.42
  4760.3  400.91  4766.2   398.8  4781.5  400.82  4787.4  396.38  4796.9  396.04
  4802.8  392.73  4809.4  392.48  4818.1  394.82    4824  393.24  4839.3  399.42
  4854.7  401.21  4894.6  401.09  4938.2  395.18  4957.5  395.68  4987.7  390.21
  4990.7  387.04  4993.4  386.54  4996.7  387.04  5008.8  390.32  5014.8  394.35
  5037.8     395  5082.2  402.19  5151.2  408.06  5319.2  416.32  5637.7  427.29
#Mann= 6 ,-1 , 0
  4648.9     .16       0  4690.7     .12       0  4990.7     .07       0
  4996.7     .12       0  5082.2     .16       0  5319.2     .05       0
Bank Sta=4990.7,4996.7
XS Rating Curve= 0 ,0
Exp/Cntr=0.3,0.1

Type RM Length L Ch R = 1 ,11098   ,67,67,67
BEGIN DESCRIPTION:
UNT0179 IN SAND CR 21.02
END DESCRIPTION:
XS GIS Cut Line= 4
      3532904.17     10487539.18      3533156.75     10487386.85
        3533438.     10487125.13      3533633.34     10486819.11
#Sta/Elev= 30
  4557.6  404.92  4657.6  402.74    4707  402.34  4730.4  400.66  4736.5   401.4
  4800.6  401.57  4846.9  400.73  4867.1  399.35  4888.1  391.67  4973.1  391.41
  4987.3  389.83  4994.7   387.2  4998.5  387.18  5001.2  386.68  5004.5  387.18
  5008.8  390.11  5029.8  394.43  5037.2  393.78  5051.1  397.44    5065  402.59
  5079.2  404.57    5106  405.55  5143.2  406.44  5220.9  410.34  5256.2   408.9
  5271.4  410.98  5277.3  410.53  5307.8  412.74  5364.6   413.8  5599.8  420.78
#Mann= 6 ,-1 , 0
  4557.6     .16       0  4657.6     .12       0  4998.5     .07       0
  5004.5     .12       0    5106     .16       0  5364.6     .05       0
Bank Sta=4998.5,5004.5
XS Rating Curve= 0 ,0
Exp/Cntr=0.3,0.1

Type RM Length L Ch R = 1 ,11031   ,130,130,130
BEGIN DESCRIPTION:
UNT0179 IN SAND CR 21.01
END DESCRIPTION:
XS GIS Cut Line= 4
      3532949.71      10487599.1      3533176.28     10487453.26
      3533462.74     10487195.45      3533705.17     10486835.04
#Sta/Elev= 30
  4543.2  406.81  4555.4  406.55  4812.7  401.45  4857.7  396.38    4931  392.98
  4966.9  395.86  4981.1  394.51  4992.3   386.9    4995   386.4  4998.3   386.9
  5031.7  389.92    5034  389.89  5044.6  389.77  5079.8  401.39  5087.2  400.03
    5094  402.84  5122.4  405.03  5129.8   402.1  5143.4  401.87  5169.6   405.1
  5174.5  405.21  5222.2  407.14  5228.3  404.39  5237.2  406.05  5243.3  404.01
  5279.2  404.53  5294.2  407.32  5315.2  406.04  5347.5  410.33  5632.4  419.25
#Mann= 10 ,-1 , 0
  4543.2     .16       0  4555.4     .05       0  4857.7     .12       0
  4992.3     .07       0  4998.3     .12       0  5031.7     .05       0
    5034     .12       0  5169.6     .05       0  5174.5     .16       0
  5347.5     .05       0
Bank Sta=4992.3,4998.3
XS Rating Curve= 0 ,0
Exp/Cntr=0.3,0.1

Type RM Length L Ch R = 1 ,10901   ,75,75,75
BEGIN DESCRIPTION:
UNT0179 IN SAND CR 21.0
END DESCRIPTION:
XS GIS Cut Line= 5
      3533050.95     10487672.78      3533399.03     10487401.61
      3533503.19     10487313.07      3533708.92     10487030.08
      3533794.86     10486867.75
#Sta/Elev= 30
  4521.4   408.9  4644.3  405.38  4700.4  401.58    4723  403.16  4879.4  399.28
  4956.5  398.68  4971.8  397.02  4986.1  385.47  4989.9  385.37  4992.7  384.87
  4995.9  385.37  5010.4  387.77  5028.9  389.94  5057.5  397.85  5101.1  400.65
  5159.4  399.68  5171.6  399.78  5177.8   401.3  5186.3  400.51  5192.4  402.14
  5207.1   400.3  5213.3  402.27  5219.1  401.57  5242.7  403.91  5257.4  402.72
  5263.5   404.3  5292.9  404.81  5299.1   406.3  5393.4  409.58  5632.9  415.51
#Mann= 9 ,-1 , 0
  4521.4     .05       0  4879.4     .12       0  4956.5     .05       0
  4989.9     .04       0  4995.9     .05       0  5010.4     .12       0
  5101.1     .05       0  5159.4     .12       0  5219.1     .05       0
Bank Sta=4989.9,4995.9
XS Rating Curve= 0 ,0
Exp/Cntr=0.3,0.1

Type RM Length L Ch R = 1 ,10826   ,371,371,371
BEGIN DESCRIPTION:
UNT0179 IN SAND CR 21.04
END DESCRIPTION:
XS GIS Cut Line= 4
      3533109.84      10487709.8      3533465.35     10487449.35
      3533530.45     10487347.79      3533853.38     10486880.32
#Sta/Elev= 30
  4505.1  410.16    4544  408.94  4742.3  402.92  4777.8  400.04  4798.7  400.51
  4819.5  396.47  4848.8  398.32  4854.3  395.61  4863.5  394.67  4869.7  397.61
  4892.2  392.47    4899  393.22  4905.2  396.92  4919.9  397.24  4928.3  395.05
  4940.7  398.04  4964.2   397.7  4978.7  395.59  4985.4  387.04  4991.3   387.9
  5003.5  385.37  5006.3  384.87  5009.5  385.37  5014.3  387.26  5027.7  387.73
    5050   396.9  5063.3   398.8  5224.1  403.51  5374.5  408.74  5634.6  413.64
#Mann= 6 ,-1 , 0
  4505.1     .05       0    4544     .16       0  4854.3     .12       0
  5003.5     .07       0  5009.5     .12       0  5224.1     .05       0
Bank Sta=5003.5,5009.5
XS Rating Curve= 0 ,0
Exp/Cntr=0.3,0.1

Type RM Length L Ch R = 1 ,10455   ,607,607,607
BEGIN DESCRIPTION:
UNT0179 IN SAND CR 19.0
END DESCRIPTION:
XS GIS Cut Line= 4
      3533512.42     10487925.39      3533757.19     10487594.69
      3533968.13     10487430.62      3534067.09     10487167.58
#Sta/Elev= 30
  4514.5  410.75  4662.9  405.42  4794.4  399.36  4867.5  397.45  4880.8  396.02
  4895.4  392.86  4903.8  389.53  4917.3  387.22  4938.8  386.53  4974.1  387.26
  4995.5   385.1    5000  382.89  5002.8  382.39    5006  382.89  5009.3  383.09
  5017.5  386.35  5038.3  386.49  5046.2  387.85  5052.8  390.74  5059.1  388.53
  5067.3  389.73  5088.1  389.47  5096.2  391.26  5102.6  389.26    5117  396.74
  5123.4  395.94  5131.5  398.17  5139.9  398.44  5341.7  407.09  5474.2  409.54
#Mann= 6 ,-1 , 0
  4514.5     .05       0  4662.9     .16       0  4794.4     .12       0
    5000     .07       0    5006     .12       0  5139.9     .05       0
Bank Sta=5000,5006
XS Rating Curve= 0 ,0
Exp/Cntr=0.3,0.1

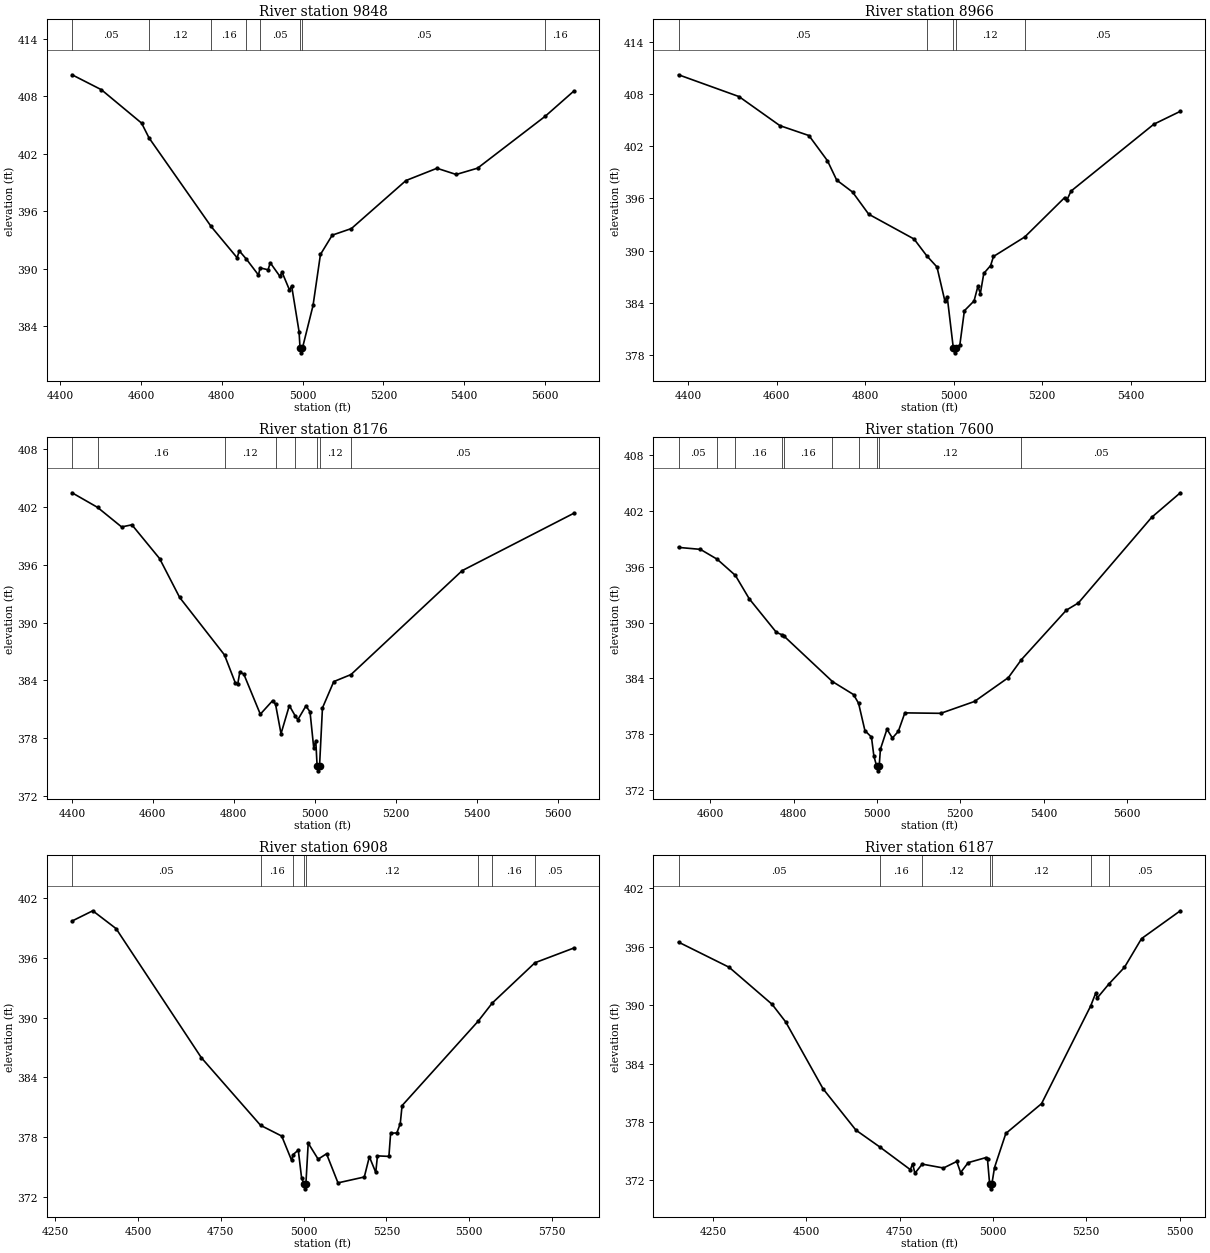
Type RM Length L Ch R = 1 ,9848    ,882,882,882
BEGIN DESCRIPTION:
UNT0179 IN SAND CR 17.0
END DESCRIPTION:
XS GIS Cut Line= 2
      3533603.57     10488006.13      3534748.21     10487524.87
#Sta/Elev= 30
  4429.6  410.25  4502.1  408.69  4601.6   405.2  4620.1  403.65  4773.6   394.4
    4838  391.13  4843.4  391.85  4861.2  390.97  4890.9  389.32  4894.8  390.07
  4914.6  389.87    4920   390.6  4943.8  389.19  4949.2  389.62  4967.5  387.77
    4973  388.17  4991.3  383.41  4993.7  381.69  4996.5  381.19  4999.7  381.69
  5025.9  386.14  5044.2  391.47  5073.4  393.49  5120.9  394.18  5255.9   399.2
  5332.6  400.48  5380.1  399.83    5433  400.49  5600.6  405.92  5671.3  408.55
#Mann= 8 ,-1 , 0
  4429.6     .05       0  4620.1     .12       0  4773.6     .16       0
  4861.2     .12       0  4894.8     .05       0  4993.7    .035       0
  4999.7     .05       0  5600.6     .16       0
Bank Sta=4993.7,4999.7
XS Rating Curve= 0 ,0
Exp/Cntr=0.3,0.1

Type RM Length L Ch R = 1 ,8966    ,790,790,790
BEGIN DESCRIPTION:
UNT0179 IN SAND CR 16.0
END DESCRIPTION:
XS GIS Cut Line= 3
      3534246.78     10488675.41      3534538.44     10488253.54
      3534793.48      10487686.2
#Sta/Elev= 30
  4377.7  410.25  4514.4  407.74    4607  404.39  4672.6  403.25  4714.5  400.35
  4735.4  398.12  4771.3  396.74  4807.8  394.19  4910.4  391.33  4938.9  389.41
  4962.2  388.11  4979.9  384.23  4985.4  384.67  4999.3  378.72    5002  378.22
  5005.3  378.72    5014  379.16  5024.2  383.07  5046.1   384.2  5054.8  385.89
  5060.3  385.05  5068.1  387.37  5083.5  388.27    5090  389.32  5160.8  391.57
  5251.1  396.11  5256.6  395.88  5265.4  396.85  5452.8  404.56  5512.6  406.04
#Mann= 5 ,-1 , 0
  4377.7     .05       0  4938.9     .12       0  4999.3     .07       0
  5005.3     .12       0  5160.8     .05       0
Bank Sta=4999.3,5005.3
XS Rating Curve= 0 ,0
Exp/Cntr=0.3,0.1

Type RM Length L Ch R = 1 ,8176    ,576,576,576
BEGIN DESCRIPTION:
UNT0179 IN SAND CR 15.0
END DESCRIPTION:
XS GIS Cut Line= 3
      3535011.49     10489116.06      3535185.11      10488304.4
      3535159.08     10487896.55
#Sta/Elev= 30
  4400.6  403.45  4463.4  401.94  4522.9  399.91  4548.3  400.13  4616.7  396.63
  4666.2   392.6  4776.9  386.64  4803.9  383.71  4809.5  383.62  4814.6  384.84
  4824.4  384.67  4865.3   380.5    4896  381.92  4902.9  381.53  4916.4  378.48
  4936.9  381.39  4951.5  380.32  4957.9  379.93  4977.8  381.35    4988  380.75
  4997.1  377.03  5002.2  377.76  5005.5  375.13  5008.2  374.63  5011.5  375.13
  5018.7  381.15  5046.6  383.88  5089.2  384.61  5363.6  395.38  5639.3  401.33
#Mann= 8 ,-1 , 0
  4400.6     .05       0  4463.4     .16       0  4776.9     .12       0
  4902.9      .1       0  4951.5     .12       0  5005.5     .07       0
  5011.5     .12       0  5089.2     .05       0
Bank Sta=5005.5,5011.5
XS Rating Curve= 0 ,0
Exp/Cntr=0.3,0.1

Type RM Length L Ch R = 1 ,7600    ,692,692,692
BEGIN DESCRIPTION:
UNT0179 IN SAND CR 13.0
END DESCRIPTION:
XS GIS Cut Line= 2
       3535882.2     10488894.19      3535273.27     10487855.88
#Sta/Elev= 30
  4524.2   398.1  4576.6  397.89  4616.8  396.83  4660.5  395.09  4693.8  392.57
    4759  388.95    4773  388.68    4777  388.56  4893.4  383.66    4944  382.26
  4956.1  381.32  4971.3  378.38    4987  377.68  4992.8  375.64  4999.5  374.55
  5002.2  374.05  5005.5  374.55  5008.5  376.39  5024.2  378.53  5037.2  377.58
  5051.4   378.3  5067.1  380.29  5153.2  380.24  5234.3  381.52  5315.5  384.09
  5346.7  386.02  5454.6  391.35  5483.3  392.12  5659.2  401.34  5727.9  403.98
#Mann= 10 ,-1 , 0
  4524.2     .05       0  4616.8      .1       0  4660.5     .16       0
    4773      .1       0    4777     .16       0  4893.4      .1       0
  4956.1     .12       0  4999.5     .07       0  5005.5     .12       0
  5346.7     .05       0
Bank Sta=4999.5,5005.5
XS Rating Curve= 0 ,0
Exp/Cntr=0.3,0.1

Type RM Length L Ch R = 1 ,6908    ,721,721,721
BEGIN DESCRIPTION:
UNT0179 IN SAND CR 12.0
END DESCRIPTION:
XS GIS Cut Line= 3
      3536119.17     10488964.49      3536095.73     10488201.46
       3536293.4      10487475.8
#Sta/Elev= 30
  4300.7  399.71  4363.2  400.74  4433.6  398.95  4691.2  385.98    4870  379.19
  4933.9  378.11  4963.9  375.66  4968.3  376.25  4983.9   376.7  4993.9  373.91
  5000.9  373.31  5003.6  372.81  5006.9  373.31  5013.9   377.4  5043.9  375.79
  5069.2  376.33  5103.8  373.41  5183.3     374  5198.6  376.03  5217.9  374.46
    5223  376.12  5257.6  376.07  5262.8  378.39  5281.6  378.43  5291.9  379.36
  5297.4  381.17  5526.9  389.64  5569.7  391.47  5698.7  395.52  5816.2     397
#Mann= 8 ,-1 , 0
  4300.7     .05       0    4870     .16       0  4968.3     .12       0
  5000.9     .07       0  5006.9     .12       0  5526.9      .1       0
  5569.7     .16       0  5698.7     .05       0
Bank Sta=5000.9,5006.9
XS Rating Curve= 0 ,0
Exp/Cntr=0.3,0.1

Type RM Length L Ch R = 1 ,6187    ,718,718,718
BEGIN DESCRIPTION:
UNT0179 IN SAND CR 10.0
END DESCRIPTION:
XS GIS Cut Line= 3
      3536301.46     10489066.04      3536681.67     10488467.08
      3536767.35     10487838.73
#Sta/Elev= 30
  4158.2  396.48  4293.6   393.9  4408.8  390.09  4445.2  388.28  4545.1  381.42
  4633.2  377.17  4697.1  375.44  4778.9  373.11  4784.9  373.71  4791.2  372.74
  4810.5  373.68  4867.6  373.28  4903.1  373.95  4913.5  372.81  4933.7  373.83
  4980.5  374.34  4985.5  374.16  4991.2  371.64    4994  371.14  4997.2  371.64
  5004.3  373.33  5034.6  376.83  5130.2  379.89  5261.6  389.91  5274.9  391.21
  5279.9  390.77  5310.5  392.18  5352.2  393.89  5397.9  396.84  5501.8   399.7
#Mann= 7 ,-1 , 0
  4158.2     .05       0  4697.1     .16       0  4810.5     .12       0
  4991.2     .07       0  4997.2     .12       0  5261.6      .1       0
  5310.5     .05       0
Bank Sta=4991.2,4997.2
XS Rating Curve= 0 ,0
Exp/Cntr=0.3,0.1

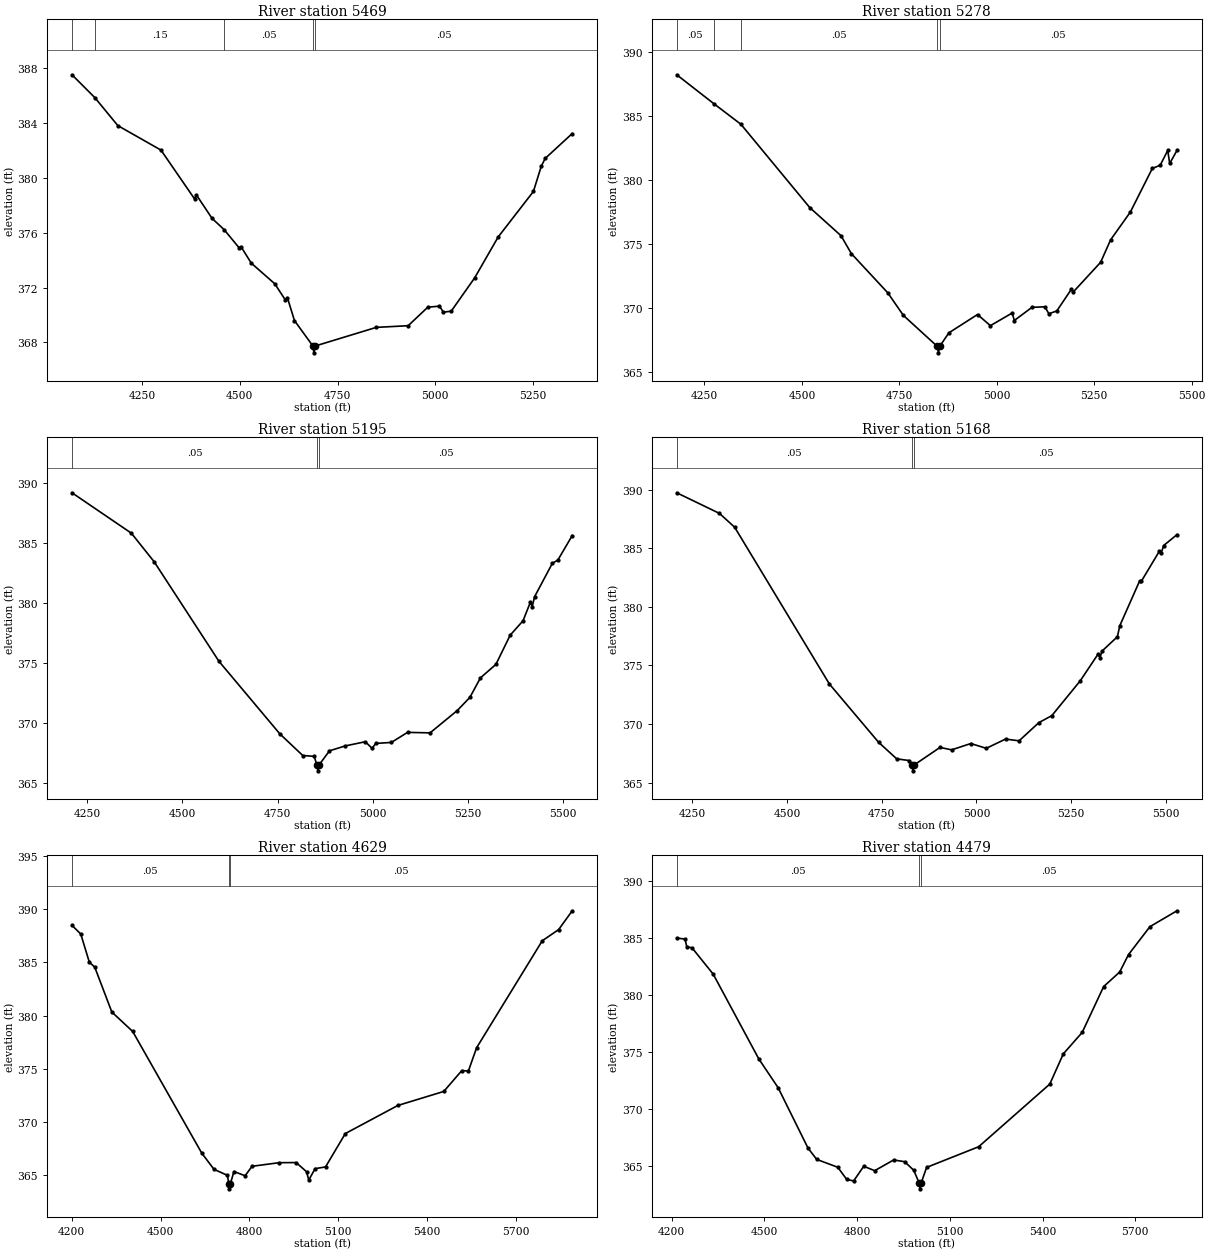
Type RM Length L Ch R = 1 ,5469    ,191,191,191
BEGIN DESCRIPTION:
UNT0179 IN SAND CR 9.03
END DESCRIPTION:
XS GIS Cut Line= 3
       3537353.9     10489518.45      3537283.59     10488698.15
      3537265.36     10488242.42
#Sta/Elev= 30
  4070.7  387.54  4129.5  385.86  4187.9  383.83  4298.3  382.04  4384.1  378.48
  4389.1  378.76  4428.8  377.06  4459.6  376.24  4497.8  374.92  4502.8     375
  4529.2  373.79  4589.4  372.28  4616.6  371.09  4621.6  371.27  4639.6   369.6
  4686.8  367.74  4689.5  367.24  4692.8  367.74  4849.1   369.1  4930.5  369.22
  4980.6  370.57  5010.6  370.65  5020.6  370.21  5040.6  370.28  5100.7  372.72
  5160.7   375.7  5250.8  379.02  5270.8  380.85  5280.8  381.43  5350.1  383.25
#Mann= 5 ,-1 , 0
  4070.7     .05       0  4129.5     .15       0  4459.6     .05       0
  4686.8     .03       0  4692.8     .05       0
Bank Sta=4686.8,4692.8
XS Rating Curve= 0 ,0
Exp/Cntr=0.3,0.1

Type RM Length L Ch R = 1 ,5278    ,83,83,83
BEGIN DESCRIPTION:
UNT0179 IN SAND CR 9.0
END DESCRIPTION:
XS GIS Cut Line= 4
      3537425.08     10489532.71      3537393.83      10488751.8
      3537402.51     10488697.11       3537313.1     10488259.57
#Sta/Elev= 30
  4178.9   388.2  4274.3  385.94  4343.5  384.34  4520.2  377.84  4600.3  375.65
  4626.9  374.25  4720.4  371.19  4760.4  369.43  4847.5  367.01  4850.3  366.51
  4853.5  367.01  4877.1  368.07  4950.6   369.5  4983.6  368.63  5039.8  369.62
  5044.9  369.03  5090.3  370.06  5123.5   370.1  5133.7  369.56  5154.1  369.78
  5191.2  371.46  5196.3  371.26  5266.4  373.57  5292.2  375.33  5342.7  377.49
    5399  380.89  5419.5  381.15  5438.6   382.3  5443.7  381.28  5462.4   382.3
#Mann= 5 ,-1 , 0
  4178.9     .05       0  4274.3     .15       0  4343.5     .05       0
  4847.5     .03       0  4853.5     .05       0
Bank Sta=4847.5,4853.5
XS Rating Curve= 0 ,0
Exp/Cntr=0.3,0.1

Type RM Length L Ch R = 1 ,5195    ,27,27,27
BEGIN DESCRIPTION:
UNT0179 IN SAND CR 9.02
END DESCRIPTION:
XS GIS Cut Line= 3
      3537474.56     10489517.38      3537491.92     10488830.79
       3537377.7      10488214.7
#Sta/Elev= 30
  4210.2  389.19    4366  385.82    4426  383.43  4596.1  375.12  4756.1  369.06
  4816.1  367.26  4846.1  367.19  4853.1  366.48  4855.9  365.98  4859.1  366.48
  4886.2  367.65  4927.6  368.06  4980.4  368.41  4997.9  367.86    5008  368.27
  5048.7  368.35  5091.2  369.19  5150.4  369.15  5221.6  371.01  5254.9  372.11
  5282.6  373.74  5323.3  374.87  5360.6   377.3  5394.5  378.51  5413.5  380.04
  5418.5  379.69    5425  380.53  5471.4   383.3    5486  383.58  5523.6  385.62
#Mann= 3 ,-1 , 0
  4210.2     .05       0  4853.1     .03       0  4859.1     .05       0
Bank Sta=4853.1,4859.1
XS Rating Curve= 0 ,0
Exp/Cntr=0.3,0.1

Type RM Length L Ch R = 1 ,5168    ,539,539,539
BEGIN DESCRIPTION:
UNT0179 IN SAND CR 9.01
END DESCRIPTION:
XS GIS Cut Line= 3
      3537521.44     10489504.44      3537537.06     10488921.07
      3537399.04     10488197.09
#Sta/Elev= 30
    4209  389.73  4321.8  387.97  4361.9  386.79  4611.9  373.42    4742  368.44
  4789.8  367.03  4822.5  366.89  4829.7  366.51  4832.5  366.01  4835.7  366.51
  4904.1  368.01  4934.5   367.8  4985.4  368.34  5026.1  367.93    5077  368.72
  5112.7  368.57  5164.8  370.12  5199.2  370.72  5274.2  373.69  5321.3  375.97
  5326.4  375.66  5331.5  376.22  5372.3  377.45  5378.5  378.38  5430.7  382.19
  5435.8   382.2  5482.8  384.73  5487.9  384.59  5494.4  385.23  5529.6  386.16
#Mann= 3 ,-1 , 0
    4209     .05       0  4829.7     .03       0  4835.7     .05       0
Bank Sta=4829.7,4835.7
XS Rating Curve= 0 ,0
Exp/Cntr=0.3,0.1

Type RM Length L Ch R = 1 ,4629    ,150,150,150
BEGIN DESCRIPTION:
UNT0179 IN SAND CR 8.0
END DESCRIPTION:
XS GIS Cut Line= 4
      3537645.21     10489443.63      3537929.06     10488787.39
      3538041.04     10488649.37      3538405.63     10487941.02
#Sta/Elev= 30
  4200.8  388.49  4230.5  387.67  4259.4  385.02  4277.5  384.57  4335.3  380.34
  4405.8  378.51    4639  367.07  4680.5  365.54  4725.9  364.98    4730  364.21
  4732.7  363.71    4736  364.21  4747.7  365.34  4785.4  364.94  4808.9  365.83
  4900.3  366.17  4957.8  366.18    4993  365.32  5000.5  364.54  5021.8  365.61
    5057  365.77  5123.9  368.91  5301.2  371.55  5456.4  372.87  5517.3  374.83
  5539.5  374.79  5567.3  376.98    5789  387.04  5844.3  388.09  5890.2  389.86
#Mann= 3 ,-1 , 0
  4200.8     .05       0    4730     .03       0    4736     .05       0
Bank Sta=4730,4736
XS Rating Curve= 0 ,0
Exp/Cntr=0.3,0.1

Type RM Length L Ch R = 1 ,4479    ,240,240,240
BEGIN DESCRIPTION:
UNT0179 IN SAND CR 7.0
END DESCRIPTION:
XS GIS Cut Line= 4
      3537754.59     10489508.73      3538051.46     10488881.14
      3538158.23     10488732.71      3538462.67     10488056.16
#Sta/Elev= 30
  4216.2  385.01  4243.1  384.92  4248.6  384.25  4265.8  384.15  4334.1  381.85
  4481.7  374.42  4544.4  371.89    4641   366.6  4669.2  365.61  4737.5  364.92
  4766.1  363.86  4788.6  363.72  4821.4  365.01  4856.8  364.62  4918.1  365.56
  4953.7  365.41  4983.1  364.66    5001  363.53  5003.7  363.03    5007  363.53
  5024.9  364.91  5193.3  366.72  5423.5  372.21  5467.3  374.86  5528.4  376.74
  5597.9  380.76  5649.7  382.03  5678.3  383.56  5747.7  386.01  5835.2   387.4
#Mann= 3 ,-1 , 0
  4216.2     .05       0    5001     .03       0    5007     .05       0
Bank Sta=5001,5007
XS Rating Curve= 0 ,0
Exp/Cntr=0.3,0.1

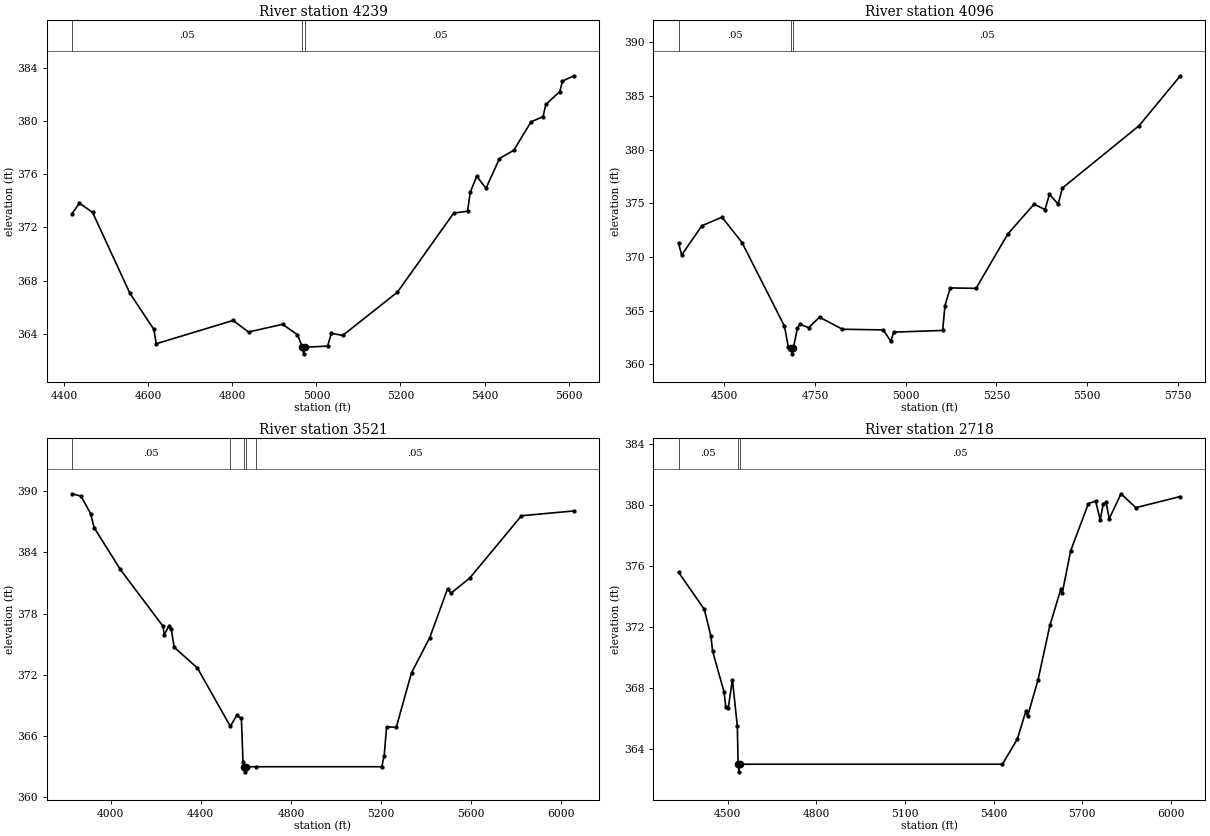
Type RM Length L Ch R = 1 ,4239    ,143,143,143
BEGIN DESCRIPTION:
UNT0179 IN SAND CR 6.0
END DESCRIPTION:
XS GIS Cut Line= 4
      3538112.39     10489395.74      3538279.06     10488906.14
      3538357.19     10488791.56      3538577.83     10488300.97
#Sta/Elev= 30
  4418.7  373.03  4436.1  373.83  4467.5  373.13  4556.3  367.05  4613.2  364.34
    4619  363.26  4801.9  365.01  4838.5  364.14  4919.5  364.72  4954.8  363.94
  4966.8     363  4969.5   362.5  4972.8     363  5026.6  363.08  5035.5  364.05
  5062.5  363.88  5192.9  367.14  5326.7  373.08  5359.6  373.22    5366  374.65
  5381.5  375.85  5403.4  374.94  5435.5  377.18  5469.6   377.8  5510.4  379.93
    5539  380.33    5546  381.25  5578.9  382.21  5585.4     383  5612.5   383.4
#Mann= 3 ,-1 , 0
  4418.7     .05       0  4966.8     .03       0  4972.8     .05       0
Bank Sta=4966.8,4972.8
XS Rating Curve= 0 ,0
Exp/Cntr=0.3,0.1

Type RM Length L Ch R = 1 ,4096    ,575,575,575
BEGIN DESCRIPTION:
UNT0179 IN SAND CR 5.0
END DESCRIPTION:
XS GIS Cut Line= 4
      3538164.49      10489525.9      3538337.59      10489055.2
      3538505.63     10488838.44      3538838.03     10488329.45
#Sta/Elev= 30
  4373.7  371.29  4382.4  370.19    4438  372.91  4493.6  373.71  4548.7  371.35
  4665.8  363.56  4676.6   361.6  4684.2  361.48    4687  360.98  4690.2  361.48
  4701.6   363.4  4708.5  363.74  4732.1  363.42  4762.5  364.39  4825.7  363.27
  4938.2  363.21    4959  362.15  4967.2     363    5102  363.16  5108.4  365.47
  5122.9  367.12  5194.1  367.08  5281.6  372.14    5354  374.92  5384.3  374.42
  5396.5  375.84  5420.4  374.93  5432.4  376.43  5643.7  382.23  5757.4  386.88
#Mann= 3 ,-1 , 0
  4373.7     .05       0  4684.2    .033       0  4690.2     .05       0
Bank Sta=4684.2,4690.2
XS Rating Curve= 0 ,0
Exp/Cntr=0.3,0.1

Type RM Length L Ch R = 1 ,3521    ,803,803,803
BEGIN DESCRIPTION:
UNT0179 IN SAND CR 4.0
END DESCRIPTION:
XS GIS Cut Line= 4
      3538224.61     10490367.71      3538786.51     10489452.84
      3538958.95     10488991.11      3539145.22      10488358.7
#Sta/Elev= 30
  3829.1  389.72  3868.8  389.49  3911.4  387.78  3926.8  386.41  4042.8  382.32
  4232.2  376.76  4238.1  375.92  4259.4  376.82    4269  376.49  4282.2  374.69
    4385  372.67  4531.2  366.95    4559  368.02  4580.2  367.73  4587.3  363.45
  4592.7     363  4595.4   362.5  4598.7     363  4643.6     363  5202.9     363
  5213.6  364.09  5224.3  366.92    5267  366.85  5334.8   372.2  5415.9  375.65
  5494.7  380.42  5509.7  379.99  5593.1  381.47  5822.5  387.57  6054.9  388.04
#Mann= 5 ,-1 , 0
  3829.1     .05       0  4531.2     .07       0  4592.7    .033       0
  4598.7     .07       0  4643.6     .05       0
Bank Sta=4592.7,4598.7
XS Rating Curve= 0 ,0
Exp/Cntr=0.3,0.1

Type RM Length L Ch R = 1 ,2718    ,0,0,0
BEGIN DESCRIPTION:
UNT0179 IN SAND CR 3.0
END DESCRIPTION:
XS GIS Cut Line= 4
       3538981.5     10490046.95      3539525.25     10489775.07
      3539567.94     10489560.37       3539492.1     10488691.61
#Sta/Elev= 30
    4333  375.59  4420.3  373.16  4442.7  371.39  4448.3  370.42  4487.4  367.72
    4493  366.73  4501.4  366.69  4515.4  368.55  4532.1  365.48  4534.7     363
  4537.5   362.5  4540.7     363  5429.6     363  5479.8  364.64  5509.6  366.52
  5514.6  366.14    5550  368.52  5590.2   372.1  5627.3  374.48  5632.4  374.25
  5660.5  376.99  5720.7   380.1  5745.1  380.26  5760.8  379.02  5770.9  380.09
  5780.9  380.18    5791   379.1  5831.1  380.74  5881.3  379.83  6031.9  380.56
#Mann= 3 ,-1 , 0
    4333     .05       0  4534.7    .033       0  4540.7     .05       0
Bank Sta=4534.7,4540.7
XS Rating Curve= 0 ,0
Exp/Cntr=0.3,0.1

Chan Stop Cuts=-1
Use User Specified Reach Order=0
Composite Channel Slope=5