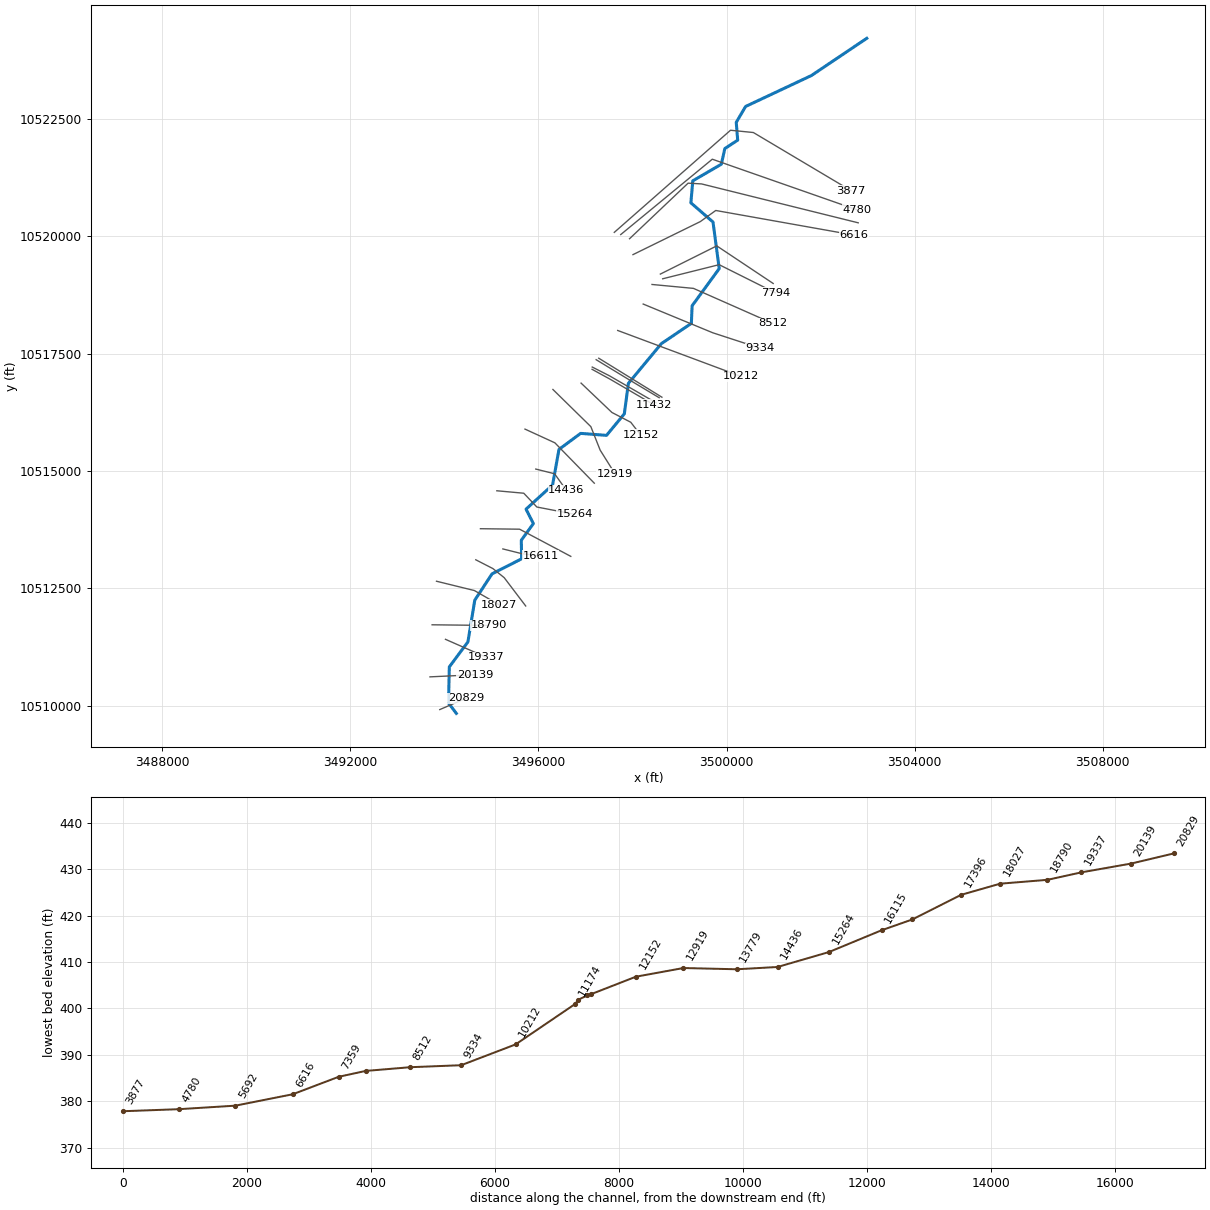
--- SANDBRANCH3.prj (project) ---

Proj Title=SAND BRANCH 3 Base Level Engineerin
Current Plan=p01
Default Exp/Contr=0.3,0.1
English Units
Geom File=g01
Flow File=f01
Plan File=p01
Y Axis Title=Elevation
X Axis Title(PF)=Main Channel Distance
X Axis Title(XS)=Station
BEGIN DESCRIPTION:
UNT0103 IN SAND CR
END DESCRIPTION:
DSS Export Rating Curves= 0
DSS Export Rating Curve Sorted= 0
DSS Export Volume Flow Curves= 0
DXF Filename=UNT0103 IN SAND CR.
DXF OffsetX= 0
DXF OffsetY= 0
DXF ScaleX= 1
DXF ScaleY= 10

--- SANDBRANCH3.p01 (plan) ---

Plan Title=Multiple Run
Short Identifier=Multiple
Geom File=g01
Flow File=f01
Subcritical Flow
K Sum by GR= 0
Std Step Tol= 0.01
Critical Tol= 0.01
Num of Std Step Trials= 20
Max Error Tol= 0.3
Flow Tol Ratio= 0.001
Split Flow NTrial= 30
Split Flow Tol= 0.02
Split Flow Ratio= 0.02
Log Output Level= 0
Friction Slope Method= 1
Unsteady Friction Slope Method= 2
Unsteady Bridges Friction Slope Method= 1
Parabolic Critical Depth
Global Vel Dist=  1 , 1 , 1
Global Log Level= 0
CheckData=True
Encroach Param= -1, 0, 0, 0
BEGIN DESCRIPTION:
Multiple Run
END DESCRIPTION:

--- SANDBRANCH3.f01 (steady flow) ---

Flow Title=Multiple
Program Version=4.10
Number of Profiles= 7
Profile Names=10-year,25-year,50-year,1pct_min,100-year,1pct_plu,500-year
River Rch & RM=UNT0103 IN SAND,Reach-1         ,20829
    1497    2104    2615    2368    3203    4331    4793
River Rch & RM=UNT0103 IN SAND,Reach-1         ,16611
    1963    2789    3492    3183    4304    5821    6524
River Rch & RM=UNT0103 IN SAND,Reach-1         ,11225
    2111    3008    3774    3444    4658    6299    7084
River Rch & RM=UNT0103 IN SAND,Reach-1         ,10212
    3736    5443    6929    6406    8663   11715   13519
River Rch & RM=SAND BRANCH 3,Reach-1         ,20829
    1497    2104    2615    2368    3203    4331    4793
River Rch & RM=SAND BRANCH 3,Reach-1         ,16611
    1963    2789    3492    3183    4304    5821    6524
River Rch & RM=SAND BRANCH 3,Reach-1         ,11225
    2111    3008    3774    3444    4658    6299    7084
River Rch & RM=SAND BRANCH 3,Reach-1         ,10212
    3736    5443    6929    6406    8663   11715   13519
Boundary for River Rch & Prof#=SAND BRANCH 3,Reach-1         , 1
Up Type= 0
Dn Type= 3
Dn Slope=0.005
Boundary for River Rch & Prof#=SAND BRANCH 3,Reach-1         , 2
Up Type= 0
Dn Type= 3
Dn Slope=0.005
Boundary for River Rch & Prof#=SAND BRANCH 3,Reach-1         , 3
Up Type= 0
Dn Type= 3
Dn Slope=0.005
Boundary for River Rch & Prof#=SAND BRANCH 3,Reach-1         , 4
Up Type= 0
Dn Type= 3
Dn Slope=0.005
Boundary for River Rch & Prof#=SAND BRANCH 3,Reach-1         , 5
Up Type= 0
Dn Type= 3
Dn Slope=0.005
Boundary for River Rch & Prof#=SAND BRANCH 3,Reach-1         , 6
Up Type= 0
Dn Type= 3
Dn Slope=0.005
Boundary for River Rch & Prof#=SAND BRANCH 3,Reach-1         , 7
Up Type= 0
Dn Type= 3
Dn Slope=0.005
DSS Import GetInterval= 0
DSS Import GetPeak= 0
DSS Import FillOption= 0

--- SANDBRANCH3.g01 (geometry) ---

Geom Title=Existing Conditions
Program Version=4.10

River Reach=SAND BRANCH 3   ,Reach-1
Reach XY= 30
      3494252.11     10509841.64      3494086.25     10510062.24
      3494103.38     10510831.35      3494498.75     10511362.89
      3494644.63     10512250.66      3495012.11     10512811.64
      3495642.11     10513131.64      3495634.32     10513525.73
      3495891.26     10513881.14      3495734.98     10514188.05
      3496299.88     10514702.56      3496435.72     10515459.51
      3496895.97       10515801.      3497447.17     10515758.54
        3497826.     10516216.96      3497912.62     10516866.04
      3498613.17     10517710.59      3499251.49     10518142.32
      3499268.51     10518517.89      3499844.46     10519307.86
      3499712.51     10520298.75      3499241.75     10520708.23
      3499282.37     10521176.45      3499889.62     10521529.87
       3499964.1     10521862.56      3500237.22     10522042.24
      3500206.69     10522420.57      3500405.37     10522758.72
      3501804.95     10523417.03      3502982.31      10524209.1

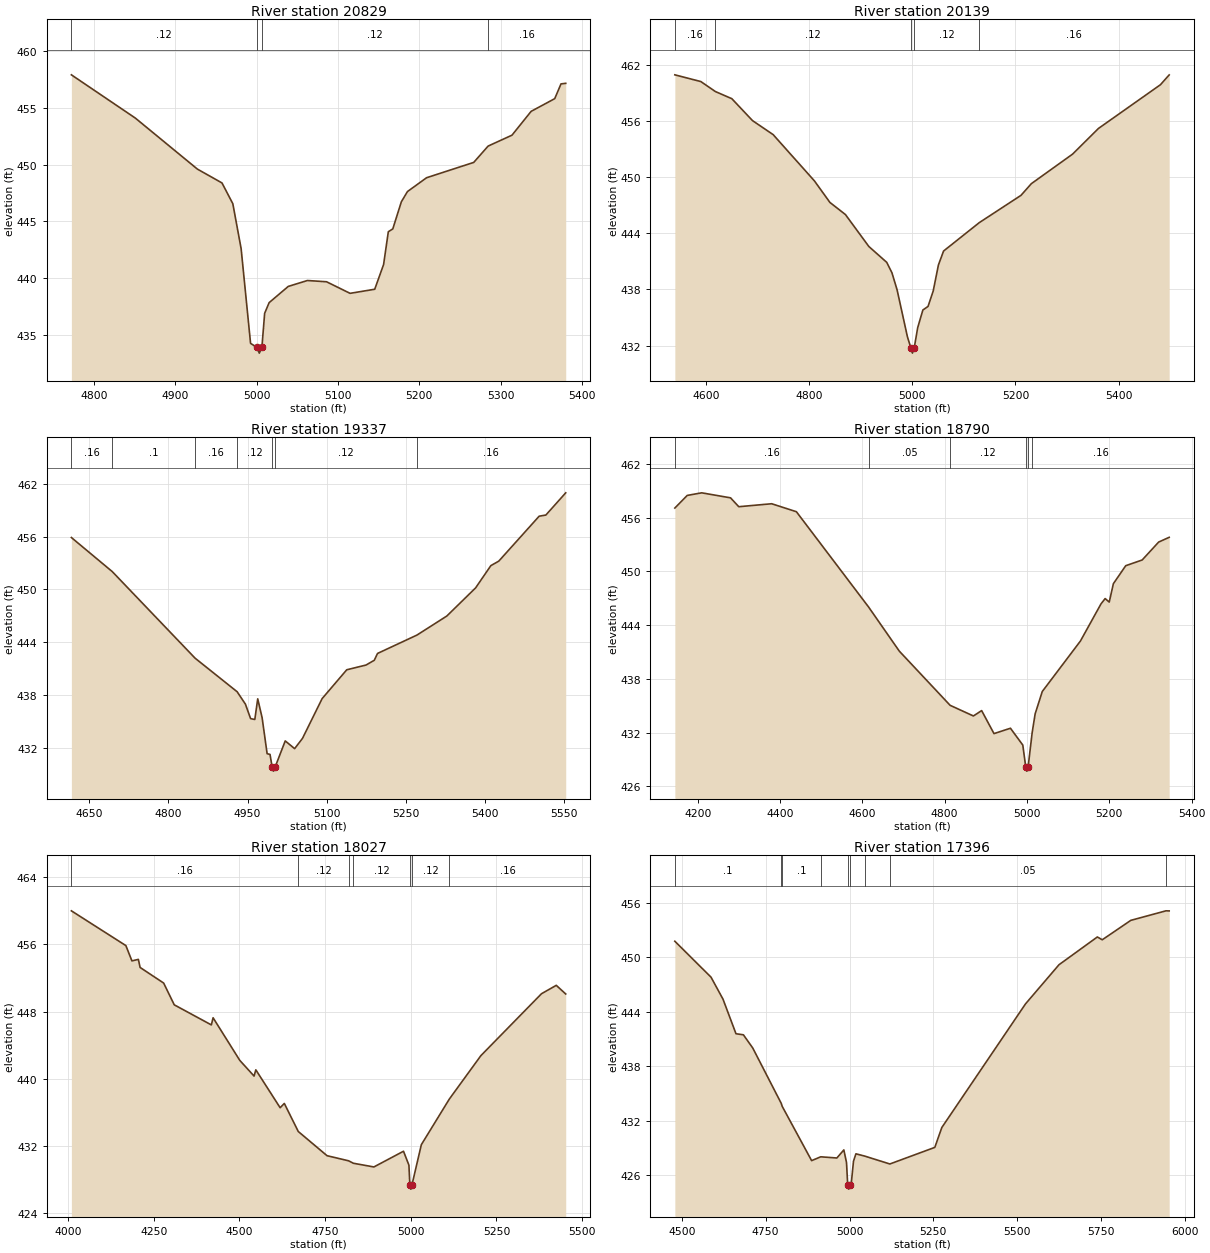
Type RM Length L Ch R = 1 ,20829   ,690,690,690
BEGIN DESCRIPTION:
UNT0103 IN SAND CR 30.0
END DESCRIPTION:
XS GIS Cut Line= 2
      3493900.02     10509922.14      3494457.45     10510162.89
#Sta/Elev= 30
  4772.6  457.92  4851.1  454.11  4927.4  449.61  4957.6  448.39  4970.9  446.56
  4981.1   442.6  4992.7  434.25  5000.6  433.89  5003.4  433.39  5006.6  433.89
    5010   436.9  5015.5  437.84    5039  439.27  5062.5  439.79    5086  439.68
  5114.9  438.66  5145.2  439.02  5156.1   441.2  5161.9  444.09  5167.4  444.34
  5177.9  446.73  5185.4  447.63  5208.9  448.85  5266.8   450.2  5284.5  451.64
  5313.8   452.6  5337.3   454.7  5366.3  455.82    5374  457.12  5379.8  457.17
#Mann= 4 ,-1 , 0
  4772.6     .12       0  5000.6     .07       0  5006.6     .12       0
  5284.5     .16       0
Bank Sta=5000.6,5006.6
XS Rating Curve= 0 ,0
Exp/Cntr=0.3,0.1

Type RM Length L Ch R = 1 ,20139   ,802,802,802
BEGIN DESCRIPTION:
UNT0103 IN SAND CR 29.0
END DESCRIPTION:
XS GIS Cut Line= 2
      3493691.73     10510618.77      3494649.05     10510664.25
#Sta/Elev= 30
  4539.6  460.94    4590  460.22  4618.3  459.15  4650.1  458.39  4690.1  456.05
  4730.2  454.55  4810.3   449.6  4840.3   447.3  4870.3  446.01  4915.8  442.59
  4950.4   440.9  4960.5  439.79  4970.5  437.96  4990.5  432.95  4997.5   431.7
  5000.2   431.2  5003.5   431.7  5010.5  433.94  5020.5  435.81  5030.5  436.19
  5040.5  437.84  5050.6  440.62  5060.6  442.11  5129.7  445.14  5210.7  448.06
  5230.8  449.31  5310.8  452.47  5360.9  455.21    5481  459.88    5498  460.93
#Mann= 5 ,-1 , 0
  4539.6     .16       0  4618.3     .12       0  4997.5     .07       0
  5003.5     .12       0  5129.7     .16       0
Bank Sta=4997.5,5003.5
XS Rating Curve= 0 ,0
Exp/Cntr=0.3,0.1

Type RM Length L Ch R = 1 ,19337   ,547,547,547
BEGIN DESCRIPTION:
UNT0103 IN SAND CR 27.0
END DESCRIPTION:
XS GIS Cut Line= 2
      3494021.63     10511417.94      3494878.14     10511039.97
#Sta/Elev= 30
  4616.4  455.91    4694  452.02  4850.7  442.17  4930.3  438.35    4946  436.94
  4955.8  435.29  4963.8  435.19  4969.3  437.54  4977.6   435.4  4987.1   431.3
  4992.6  431.21  4996.5  429.81  4999.2  429.31  5002.5  429.81  5021.4  432.75
  5039.2  431.87  5054.1  433.04  5091.3  437.57  5137.9  440.85  5174.4  441.39
    5190  441.93  5196.2  442.71  5270.8   444.8  5327.4  446.97    5382  450.18
  5410.8  452.71  5425.8  453.22  5502.3  458.34    5515  458.47  5552.6     461
#Mann= 7 ,-1 , 0
  4616.4     .16       0    4694      .1       0  4850.7     .16       0
  4930.3     .12       0  4996.5     .07       0  5002.5     .12       0
  5270.8     .16       0
Bank Sta=4996.5,5002.5
XS Rating Curve= 0 ,0
Exp/Cntr=0.3,0.1

Type RM Length L Ch R = 1 ,18790   ,763,763,763
BEGIN DESCRIPTION:
UNT0103 IN SAND CR 26.0
END DESCRIPTION:
XS GIS Cut Line= 2
      3493736.84     10511726.99      3494937.65     10511713.11
#Sta/Elev= 30
  4144.5  457.08  4174.6  458.49  4209.8  458.78  4279.8  458.22  4299.8  457.23
  4379.8  457.56  4439.8  456.67  4615.3  446.02  4689.8   441.1  4813.2  435.05
  4869.8  433.86  4889.8  434.46  4919.8  431.89  4959.8  432.49  4989.8  430.61
  4996.8   428.2  4999.6   427.7  5002.8   428.2  5012.5  431.98  5019.8   434.1
  5037.1  436.59  5129.8  442.23  5179.8  446.38  5189.8  446.97  5199.8  446.58
  5209.8  448.63  5239.8  450.64  5279.8  451.28  5319.8  453.28  5345.4  453.81
#Mann= 6 ,-1 , 0
  4144.5     .16       0  4615.3     .05       0  4813.2     .12       0
  4996.8     .07       0  5002.8     .12       0  5012.5     .16       0
Bank Sta=4996.8,5002.8
XS Rating Curve= 0 ,0
Exp/Cntr=0.3,0.1

Type RM Length L Ch R = 1 ,18027   ,631,631,631
BEGIN DESCRIPTION:
UNT0103 IN SAND CR 24.0
END DESCRIPTION:
XS GIS Cut Line= 3
      3493830.65     10512654.06      3494636.17     10512456.15
      3495167.22     10512150.71
#Sta/Elev= 30
  4009.9     460  4168.9  455.86  4186.5  454.04  4205.3  454.22  4210.4  453.26
  4279.1   451.4    4310  448.81  4418.2  446.42  4423.3  447.27  4501.3  442.19
  4542.8  440.33    4548  441.07  4618.9  436.56  4631.1  437.07  4671.8  433.73
  4755.7  430.85  4818.7  430.24  4832.5  429.95  4892.4  429.51  4978.8  431.38
  4994.6  429.72  4997.4  427.37  5000.2  426.87  5003.4  427.37  5030.8  432.16
  5112.6   437.6  5204.5  442.76  5381.3  450.13  5424.4  451.13    5452   450.1
#Mann= 7 ,-1 , 0
  4009.9     .16       0  4671.8     .12       0  4818.7     .16       0
  4832.5     .12       0  4997.4     .07       0  5003.4     .12       0
  5112.6     .16       0
Bank Sta=4997.4,5003.4
XS Rating Curve= 0 ,0
Exp/Cntr=0.3,0.1

Type RM Length L Ch R = 1 ,17396   ,785,785,785
BEGIN DESCRIPTION:
UNT0103 IN SAND CR 23.0
END DESCRIPTION:
XS GIS Cut Line= 4
      3494666.19     10513110.64       3495030.8     10512923.13
      3495270.38     10512730.42      3495727.74     10512127.54
#Sta/Elev= 30
  4479.1  451.77    4587  447.81  4622.7  445.39  4661.4  441.58  4683.6  441.46
  4711.4  440.01  4796.5   433.9  4799.4  433.57    4887   427.6  4914.2  428.02
  4962.3  427.89  4983.1  428.78  4991.1  427.38  4994.5  424.96  4997.3  424.46
  5000.5  424.96  5005.5  425.19  5011.9  427.54  5019.1  428.35  5045.3   428.1
  5120.3  427.23  5254.4  429.06  5275.3  431.25  5524.9  444.87  5624.7  449.18
  5739.1  452.24  5753.7  451.93  5838.9  454.07  5943.7  455.12  5953.3  455.11
#Mann= 9 ,-1 , 0
  4479.1      .1       0  4796.5     .05       0  4799.4      .1       0
  4914.2     .05       0  4994.5     .03       0  5000.5     .05       0
  5045.3      .1       0  5120.3     .05       0  5943.7     .16       0
Bank Sta=4994.5,5000.5
XS Rating Curve= 0 ,0
Exp/Cntr=0.3,0.1

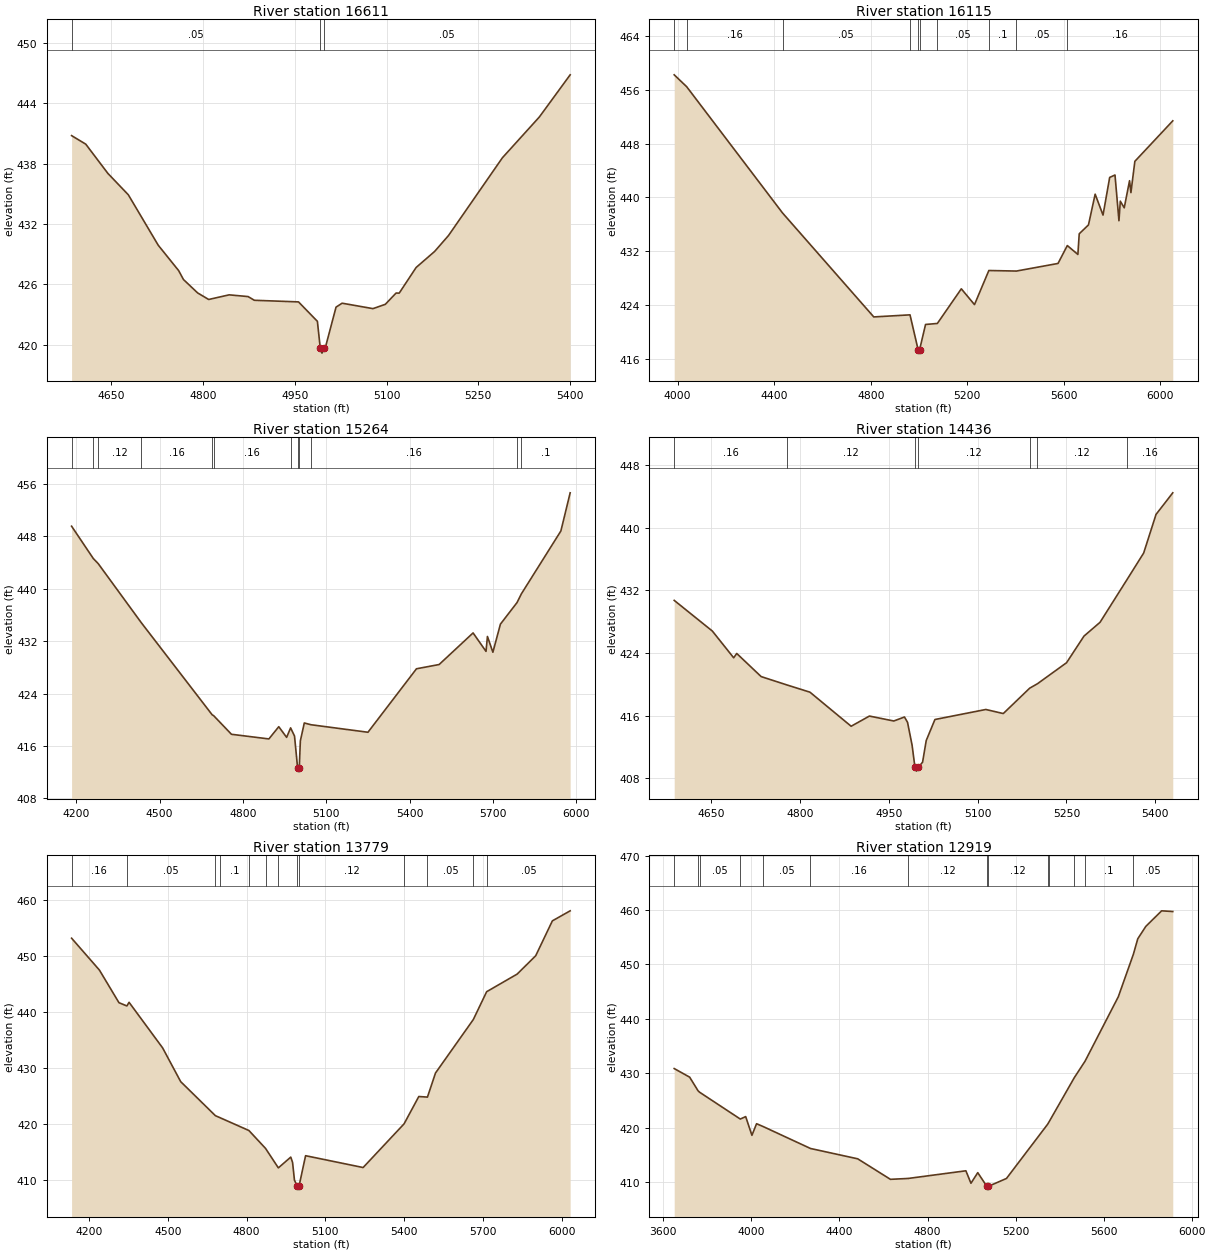
Type RM Length L Ch R = 1 ,16611   ,496,496,496
BEGIN DESCRIPTION:
UNT0103 IN SAND CR 21.0
END DESCRIPTION:
XS GIS Cut Line= 3
       3495242.1     10513341.64      3495642.11     10513241.64
      3496042.08     10513191.65
#Sta/Elev= 30
  4584.8  440.78    4608  439.93  4644.1  437.03  4677.6   434.9  4726.5  429.89
    4760  427.36  4767.8  426.48    4791  425.15    4809   424.5  4842.5  424.96
  4873.4  424.79  4883.7  424.42  4955.9  424.26  4986.8  422.33  4991.5  419.67
  4994.3  419.17  4997.5  419.67  4999.6  419.67  5017.3  423.74  5027.3  424.13
  5077.7  423.59  5097.9  424.02  5115.5  425.14  5120.6  425.13  5148.3  427.68
  5178.5  429.27  5201.2  430.85  5289.4  438.58  5349.8  442.63  5400.2  446.82
#Mann= 3 ,-1 , 0
  4584.8     .05       0  4991.5     .03       0  4997.5     .05       0
Bank Sta=4991.5,4997.5
XS Rating Curve= 0 ,0
Exp/Cntr=0.3,0.1

Type RM Length L Ch R = 1 ,16115   ,851,851,851
BEGIN DESCRIPTION:
UNT0103 IN SAND CR 20.0
END DESCRIPTION:
XS GIS Cut Line= 3
      3494765.16     10513772.09       3495598.5     10513761.67
      3496687.01     10513183.57
#Sta/Elev= 30
  3985.7  458.21  4037.5  456.44  4434.5  437.68  4812.7  422.22  4962.8  422.53
  4996.5  417.34  4999.3  416.84  5002.5  417.34  5027.2   421.1  5076.1  421.25
  5175.4   426.4    5230  424.05  5289.5  429.12  5403.8  429.04  5576.1  430.17
  5614.6  432.83  5658.4  431.51    5664  434.58  5702.3   435.9    5730  440.47
  5762.6  437.36  5790.2  442.96  5812.2  443.32  5828.6  436.52  5834.2  439.43
  5850.5  438.44  5872.5  442.47  5878.2   440.7  5894.5  445.35  6051.6  451.37
#Mann= 10 ,-1 , 0
  3985.7     .05       0  4037.5     .16       0  4434.5     .05       0
  4962.8      .1       0  4996.5     .07       0  5002.5      .1       0
  5076.1     .05       0  5289.5      .1       0  5403.8     .05       0
  5614.6     .16       0
Bank Sta=4996.5,5002.5
XS Rating Curve= 0 ,0
Exp/Cntr=0.3,0.1

Type RM Length L Ch R = 1 ,15264   ,828,828,828
BEGIN DESCRIPTION:
UNT0103 IN SAND CR 18.0
END DESCRIPTION:
XS GIS Cut Line= 4
      3495114.16     10514579.38      3495687.05      10514527.3
      3495965.38     10514233.78      3496765.16     10514079.38
#Sta/Elev= 30
  4183.4  449.57  4261.7  444.62  4278.9  443.87  4434.5  434.81  4689.3  420.75
    4695   420.6  4758.7  417.77  4893.5  417.06    4929  418.93  4957.3   417.3
  4971.6  418.75  4985.7   417.5  4996.8  412.64  4999.6  412.14  5002.8  412.64
  5006.7  416.77  5020.9   419.5    5045  419.23    5250  418.08  5424.6  427.78
  5506.1  428.43  5628.3  433.26  5674.9  430.44    5680  432.72  5699.6  430.31
  5726.7   434.6  5786.5   437.9  5802.1  439.23  5944.3  448.84  5977.7  454.67
#Mann= 12 ,-1 , 0
  4183.4     .12       0  4261.7     .16       0  4278.9     .12       0
  4434.5     .16       0  4689.3      .1       0    4695     .16       0
  4971.6     .05       0  4996.8     .04       0  5002.8     .05       0
    5045     .16       0  5786.5     .05       0  5802.1      .1       0
Bank Sta=4996.8,5002.8
XS Rating Curve= 0 ,0
Exp/Cntr=0.3,0.1

Type RM Length L Ch R = 1 ,14436   ,657,657,657
BEGIN DESCRIPTION:
UNT0103 IN SAND CR 16.0
END DESCRIPTION:
XS GIS Cut Line= 3
      3495942.08     10515041.65      3496342.11     10514941.64
      3496592.13     10514591.61
#Sta/Elev= 30
  4587.1  430.73  4651.6  426.81  4687.6   423.4  4692.8  423.95    4734     421
  4777.7  419.93  4816.5  419.01  4886.1  414.66    4917  415.96  4958.2  415.33
  4976.2  415.84  4981.4  415.16  4989.1  412.24  4993.9  409.43  4996.6  408.93
  4999.9  409.43  5006.8  410.07    5013  412.84  5027.7  415.52  5113.7   416.8
  5143.2  416.28  5187.8  419.52  5200.8  420.08  5250.1  422.77  5279.6  426.17
  5306.7  427.93  5352.5  433.41  5380.4  436.77  5401.3   441.7  5429.6  444.46
#Mann= 7 ,-1 , 0
  4587.1     .16       0  4777.7     .12       0  4993.9     .07       0
  4999.9     .12       0  5187.8     .05       0  5200.8     .12       0
  5352.5     .16       0
Bank Sta=4993.9,4999.9
XS Rating Curve= 0 ,0
Exp/Cntr=0.3,0.1

Type RM Length L Ch R = 1 ,13779   ,860,860,860
BEGIN DESCRIPTION:
UNT0103 IN SAND CR 15.0
END DESCRIPTION:
XS GIS Cut Line= 3
      3495713.05      10515891.9       3496348.5     10515600.21
      3497187.05     10514740.84
#Sta/Elev= 30
    4133  453.18    4239   447.5  4313.5  441.68  4343.7   441.1    4352  441.75
  4479.9  433.62  4548.8   427.6  4681.1  421.53  4697.9  421.19  4808.7  418.89
  4872.1   415.7  4920.9  412.23  4968.2  414.15  4975.1   413.2  4982.3  410.03
  4993.5  408.94  4996.2  408.44  4999.5  408.94  5024.7   414.4  5243.9  412.29
    5400  420.08  5456.1  424.95  5489.1  424.85  5519.7  429.14  5663.9  438.68
  5714.7  443.64  5830.9  446.78  5901.6  450.05  5965.1  456.27  6032.9  458.06
#Mann= 13 ,-1 , 0
    4133     .16       0  4343.7     .05       0  4681.1     .16       0
  4697.9      .1       0  4808.7     .16       0  4872.1      .1       0
  4920.9     .12       0  4993.5     .07       0  4999.5     .12       0
    5400     .16       0  5489.1     .05       0  5663.9     .16       0
  5714.7     .05       0
Bank Sta=4993.5,4999.5
XS Rating Curve= 0 ,0
Exp/Cntr=0.3,0.1

Type RM Length L Ch R = 1 ,12919   ,767,767,767
BEGIN DESCRIPTION:
UNT0103 IN SAND CR 13.0
END DESCRIPTION:
XS GIS Cut Line= 4
      3496306.85     10516735.62      3497114.13     10515943.96
      3497312.05     10515443.96      3497629.74     10514938.77
#Sta/Elev= 30
    3649  430.87  3719.2  429.29  3757.5  426.78  3764.4  426.52  3949.3  421.59
  3973.8  422.04  4002.1   418.6  4023.2  420.73  4054.3  420.19  4268.2  416.18
  4482.8  414.28  4631.4  410.51  4711.8  410.67  4974.2  412.08  4997.3  409.79
  5028.2  411.74  5069.6  409.21  5072.3  408.71  5075.6  409.21  5158.6  410.67
  5345.6  420.63  5353.6  421.18  5466.7  429.19  5515.6  432.22  5666.8  444.07
    5735  451.85  5755.2  454.72  5791.7     457  5863.6  459.86  5914.2  459.73
#Mann= 14 ,-1 , 0
    3649      .1       0  3757.5     .12       0  3764.4     .05       0
  3949.3     .16       0  4054.3     .05       0  4268.2     .16       0
  4711.8     .12       0  5069.6     .07       0  5075.6     .12       0
  5345.6     .05       0  5353.6      .1       0  5466.7     .05       0
  5515.6      .1       0    5735     .05       0
Bank Sta=5069.6,5075.6
XS Rating Curve= 0 ,0
Exp/Cntr=0.3,0.1

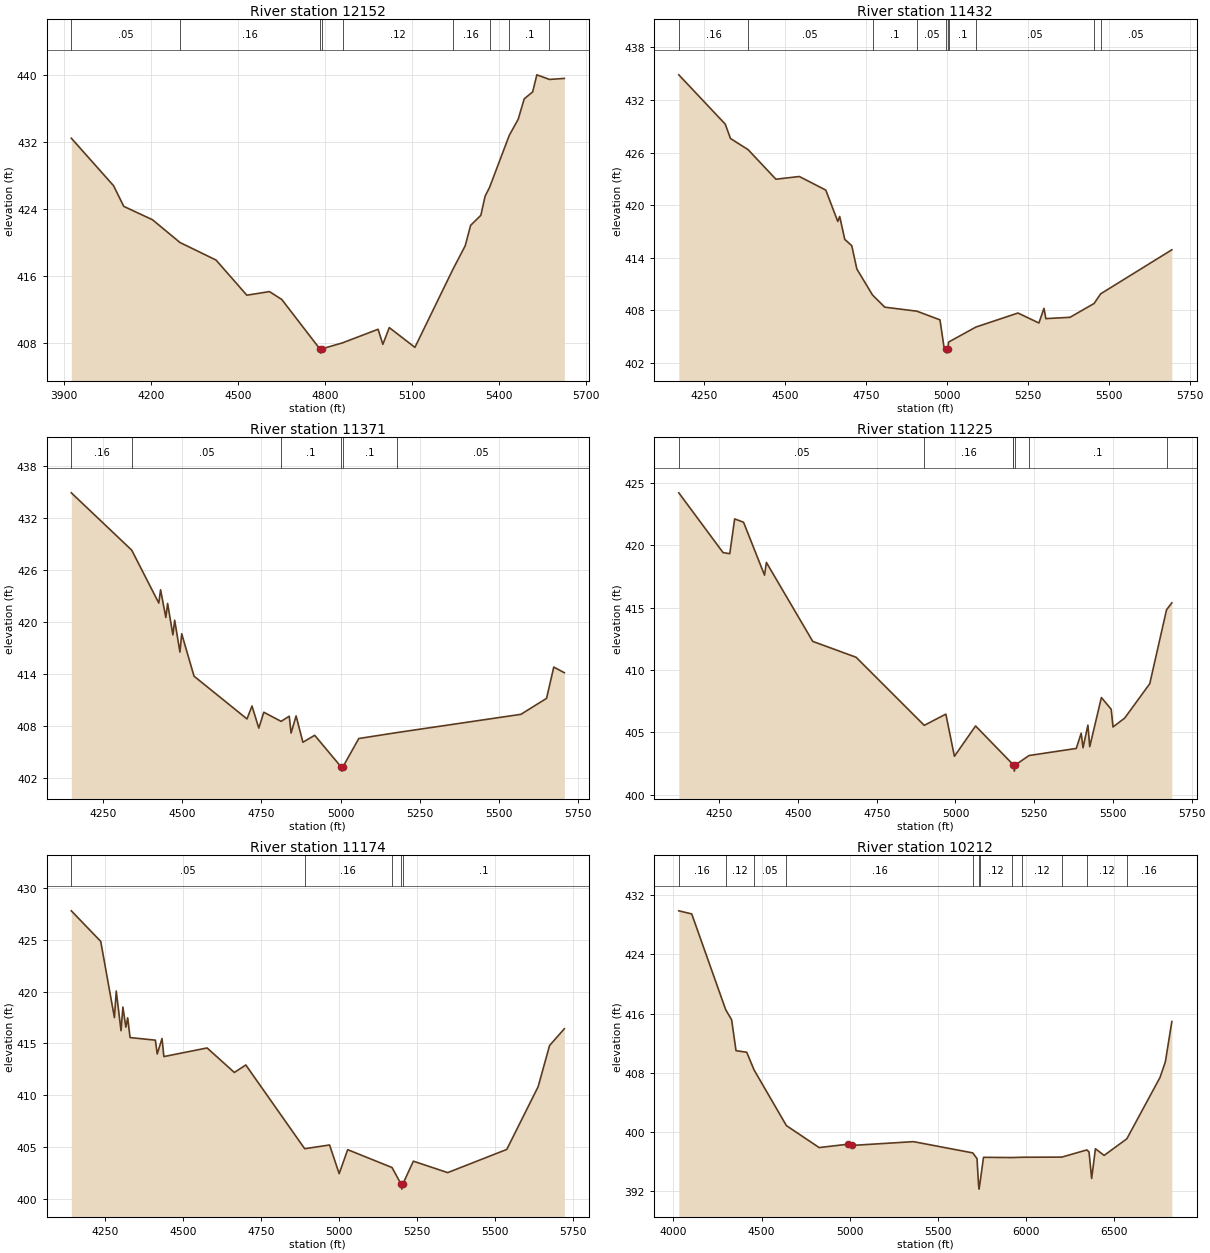
Type RM Length L Ch R = 1 ,12152   ,720,720,720
BEGIN DESCRIPTION:
UNT0103 IN SAND CR 11.0
END DESCRIPTION:
XS GIS Cut Line= 4
      3496905.82     10516871.02      3497562.05     10516246.05
      3497963.09     10516037.71       3498171.4     10515766.91
#Sta/Elev= 30
  3924.8  432.51  4070.4  426.84  4105.6  424.37  4204.7  422.77  4299.5  420.05
  4423.7  417.96  4529.9  413.76  4607.9  414.19  4650.4  413.25  4781.7  407.34
  4784.5  406.84  4787.7  407.34    4860  408.07  4982.4  409.69  4998.9  407.89
    5021  409.89  5109.4  407.53    5240  416.82  5282.9  419.67  5301.4   422.1
  5336.7   423.3  5351.3  425.58  5366.8  426.64  5434.7  432.85  5465.4  434.77
  5486.2  437.21  5515.3  438.04  5529.8  440.08  5573.3  439.53  5624.6  439.65
#Mann= 9 ,-1 , 0
  3924.8     .05       0  4299.5     .16       0  4781.7     .07       0
  4787.7     .16       0    4860     .12       0    5240     .16       0
  5366.8     .05       0  5434.7      .1       0  5573.3     .05       0
Bank Sta=4781.7,4787.7
XS Rating Curve= 0 ,0
Exp/Cntr=0.3,0.1

Type RM Length L Ch R = 1 ,11432   ,61,61,61
BEGIN DESCRIPTION:
UNT0103 IN SAND CR 9.1
END DESCRIPTION:
XS GIS Cut Line= 3
      3497139.63     10517164.49      3497532.01     10516949.21
      3498458.07     10516408.14
#Sta/Elev= 30
  4173.1  434.87  4316.3  429.24  4332.4   427.6  4386.6  426.33  4472.5  422.95
  4544.7  423.26  4626.2  421.71  4663.3  418.12  4669.1   418.7  4684.8  416.08
  4706.3  415.36    4722   412.7  4770.3  409.73    4808  408.34  4907.1  407.88
  4978.3  406.89  4991.4  403.61  4996.8  403.59  4999.5  403.09  5002.8  403.59
  5004.8  404.35  5089.2  406.07  5218.8  407.67  5283.3  406.53    5299  408.21
  5304.8  407.03  5379.2  407.18  5453.5  408.76  5473.7  409.86  5693.2  414.89
#Mann= 10 ,-1 , 0
  4173.1     .16       0  4386.6     .05       0  4770.3      .1       0
  4907.1     .05       0  4996.8     .04       0  5002.8     .05       0
  5004.8      .1       0  5089.2     .05       0  5453.5     .16       0
  5473.7     .05       0
Bank Sta=4996.8,5002.8
XS Rating Curve= 0 ,0
Exp/Cntr=0.3,0.1

Type RM Length L Ch R = 1 ,11371   ,146,146,146
BEGIN DESCRIPTION:
UNT0103 IN SAND CR 9.0
END DESCRIPTION:
XS GIS Cut Line= 3
      3497143.13     10517213.09      3497511.17      10517025.6
      3498500.75     10516452.69
#Sta/Elev= 30
  4149.9   434.9  4340.6  428.29  4426.1  422.19  4431.7  423.72  4448.3  420.53
  4453.9  422.15  4470.6  418.52  4476.2  420.21  4492.8  416.54  4498.4  418.65
  4537.3  413.76  4704.5  408.83  4720.3  410.32  4741.8  407.77  4757.6   409.6
  4812.2  408.55  4837.9  409.14  4843.7   407.2  4859.5  409.18    4881  406.14
  4918.3  406.94  5001.4  403.31  5004.2  402.81  5007.4  403.31  5057.5  406.57
  5178.7  407.26  5569.3  409.36  5650.2   411.2    5673  414.81  5706.4  414.16
#Mann= 6 ,-1 , 0
  4149.9     .16       0  4340.6     .05       0  4812.2      .1       0
  5001.4     .07       0  5007.4      .1       0  5178.7     .05       0
Bank Sta=5001.4,5007.4
XS Rating Curve= 0 ,0
Exp/Cntr=0.3,0.1

Type RM Length L Ch R = 1 ,11225   ,51,51,51
BEGIN DESCRIPTION:
UNT0103 IN SAND CR 8.1
END DESCRIPTION:
XS GIS Cut Line= 3
      3497226.49     10517369.33       3497882.7     10516970.04
      3498566.73     10516560.32
#Sta/Elev= 30
  4121.6  424.21  4262.1  419.42  4283.4  419.33  4298.9  422.12  4327.2  421.85
  4393.8  417.61  4399.7  418.63  4546.9   412.3  4684.4  411.03  4900.9  405.57
  4969.5  406.47  4996.7  403.09  5063.9  405.52    5184   402.4  5184.3   402.4
    5187   401.9  5190.3   402.4  5233.6  403.15  5383.7  403.72  5399.2  404.94
  5405.1  403.77  5420.6  405.59  5426.4  403.86  5463.4   407.8  5494.5  406.86
  5500.3  405.44  5537.3  406.15    5617  408.91  5670.2  414.83  5687.1  415.39
#Mann= 7 ,-1 , 0
  4121.6     .05       0  4900.9     .16       0    5184     .05       0
  5184.3     .07       0  5190.3     .05       0  5233.6      .1       0
  5670.2     .05       0
Bank Sta=5184.3,5190.3
XS Rating Curve= 0 ,0
Exp/Cntr=0.3,0.1

Type RM Length L Ch R = 1 ,11174   ,962,962,962
BEGIN DESCRIPTION:
UNT0103 IN SAND CR 8.0
END DESCRIPTION:
XS GIS Cut Line= 2
      3497281.97     10517400.62      3498625.76     10516570.73
#Sta/Elev= 30
  4143.1  427.77  4237.3  424.83  4281.2  417.49    4287  420.05  4302.4  416.23
  4308.3  418.51  4317.8  416.57  4323.7  417.47  4331.3  415.57  4412.4  415.32
  4418.3  413.99  4433.7  415.48  4439.6  413.74  4578.1  414.57  4665.4  412.21
  4702.1  412.93  4890.7  404.87  4970.4  405.23  5001.2  402.47  5028.4  404.78
  5170.5  403.06  5199.2  401.48  5201.9  400.98  5205.2  401.48  5238.8  403.67
  5348.8  402.57    5538   404.8  5638.5  410.84  5675.1   414.8  5722.5  416.42
#Mann= 5 ,-1 , 0
  4143.1     .05       0  4890.7     .16       0  5170.5      .1       0
  5199.2     .07       0  5205.2      .1       0
Bank Sta=5199.2,5205.2
XS Rating Curve= 0 ,0
Exp/Cntr=0.3,0.1

Type RM Length L Ch R = 1 ,10212   ,878,878,878
BEGIN DESCRIPTION:
UNT0103 IN SAND CR 7.0
END DESCRIPTION:
XS GIS Cut Line= 2
      3497685.44     10517991.24      3500308.78     10517012.69
#Sta/Elev= 30
  4030.2  429.89  4103.6  429.47  4296.5  416.52  4330.1  415.16  4355.1  410.98
  4415.8  410.77  4457.8  408.37  4641.2  400.85  4827.1  397.88  4990.1  398.33
    5015  398.17  5362.8  398.68  5699.2  397.16  5723.7  396.39  5732.6  392.76
  5735.3  392.26  5738.6  392.76  5760.6  396.56  5921.6  396.53  5979.2  396.57
  6205.3  396.59  6347.3  397.56  6359.8  397.29  6374.7   393.7  6396.1  397.72
  6445.5  396.82  6574.3  399.06  6762.9  407.36  6793.2  409.47  6830.1  414.92
#Mann= 12 ,-1 , 0
  4030.2     .16       0  4296.5     .12       0  4457.8     .05       0
  4641.2     .16       0  5699.2     .12       0  5732.6     .07       0
  5738.6     .12       0  5921.6     .16       0  5979.2     .12       0
  6205.3     .16       0  6347.3     .12       0  6574.3     .16       0
Bank Sta=4990.1,5015
XS Rating Curve= 0 ,0
Exp/Cntr=0.3,0.1

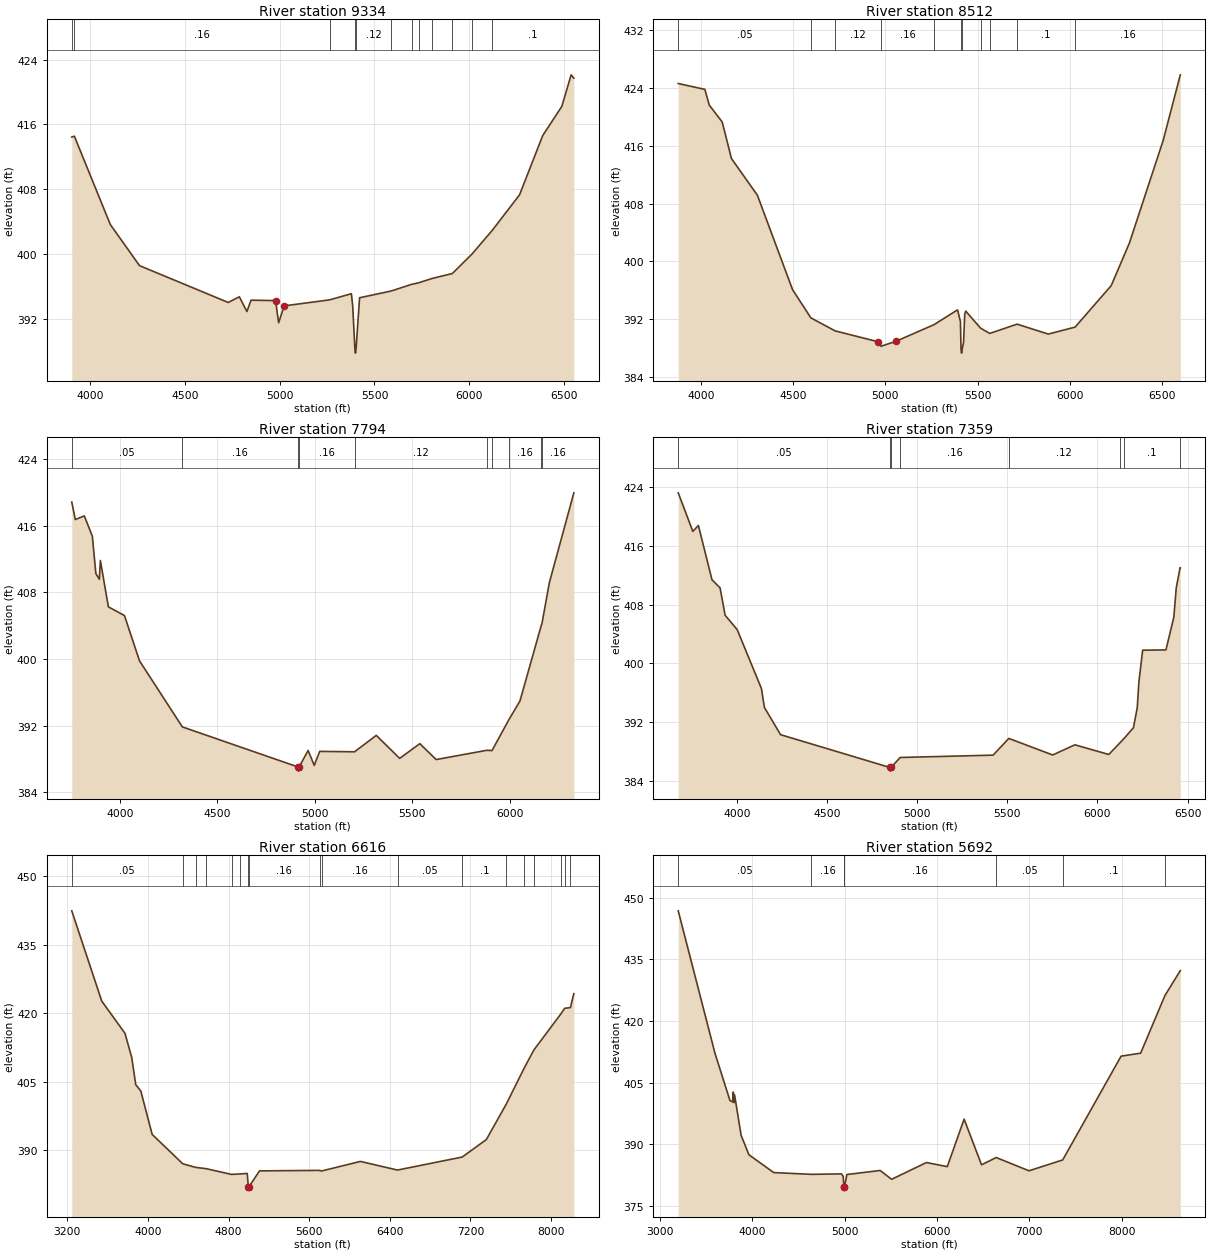
Type RM Length L Ch R = 1 ,9334    ,822,822,822
BEGIN DESCRIPTION:
UNT0103 IN SAND CR 6.0
END DESCRIPTION:
XS GIS Cut Line= 3
      3498227.15     10518553.72      3499706.31     10517942.61
       3500705.7     10517616.42
#Sta/Elev= 30
  3901.3  414.43    3915  414.54    4105  403.64  4259.3  398.57  4727.6  394.03
  4786.3  394.73  4826.3  392.91    4848  394.31  4977.8  394.26  4993.8  391.52
  5023.1  393.61    5263  394.35  5378.2  395.11    5385  393.61  5396.8  388.28
  5399.5  387.78  5402.8  388.28  5421.4  394.61  5589.5  395.45  5696.8  396.27
  5732.6  396.45    5806     397  5911.3   397.6  6014.6  399.99  6122.1  402.92
  6266.3  407.31  6388.7  414.62  6489.6  418.22  6538.7  422.11    6553   421.7
#Mann= 12 ,-1 , 0
  3901.3     .05       0    3915     .16       0    5263     .12       0
  5396.8     .07       0  5402.8     .12       0  5589.5     .16       0
  5696.8     .12       0  5732.6     .16       0    5806     .12       0
  5911.3      .1       0  6014.6     .16       0  6122.1      .1       0
Bank Sta=4977.8,5023.1
XS Rating Curve= 0 ,0
Exp/Cntr=0.3,0.1

Type RM Length L Ch R = 1 ,8512    ,718,718,718
BEGIN DESCRIPTION:
UNT0103 IN SAND CR 5.0
END DESCRIPTION:
XS GIS Cut Line= 3
      3498414.64     10518970.39      3499296.59     10518887.06
      3500977.17     10518143.99
#Sta/Elev= 30
  3876.5  424.56  4021.1  423.75  4044.7  421.59    4115  419.25  4165.2  414.21
  4305.9  409.14  4496.7  396.11  4595.8  392.22  4727.6  390.42  4960.5  388.92
  4976.5   388.3  5059.2     389  5263.2  391.27  5391.6  393.32  5407.2  391.72
  5410.5  387.85  5413.3  387.35  5416.5  387.85  5424.4  388.86  5430.5  392.71
    5436  393.15  5516.9  390.79  5566.3  390.07  5714.4  391.35  5883.7  389.98
  6029.2  390.94  6225.2  396.67  6323.9  402.55  6506.9   416.7  6599.9  425.76
#Mann= 11 ,-1 , 0
  3876.5     .05       0  4595.8     .16       0  4727.6     .12       0
  4976.5     .16       0  5263.2     .12       0  5410.5     .07       0
  5416.5     .12       0  5516.9     .16       0  5566.3     .12       0
  5714.4      .1       0  6029.2     .16       0
Bank Sta=4960.5,5059.2
XS Rating Curve= 0 ,0
Exp/Cntr=0.3,0.1

Type RM Length L Ch R = 1 ,7794    ,435,435,435
BEGIN DESCRIPTION:
UNT0103 IN SAND CR 4.0
END DESCRIPTION:
XS GIS Cut Line= 3
      3498642.09     10519091.64      3499842.11     10519391.64
      3501042.12     10518791.64
#Sta/Elev= 30
  3751.6  418.85  3769.7  416.75    3816  417.19  3857.3  414.75  3875.3  410.27
  3893.3  409.59  3898.5  411.84  3939.7  406.27  4022.2  405.23  4099.5  399.79
  4319.5  391.86  4913.4  387.05  4916.1  386.55  4919.4  387.05  4965.4  389.03
  4996.9  387.24  5024.9  388.92    5204  388.87  5315.6  390.84  5435.8  388.08
  5539.2  389.85    5623  387.94  5883.1  389.05    5910  389.02  5995.9   392.7
  6053.5  394.97  6163.6   404.1    6166   404.2  6204.4  409.17  6330.2  419.96
#Mann= 10 ,-1 , 0
  3751.6     .05       0  4319.5     .16       0  4913.4     .07       0
  4919.4     .16       0    5204     .12       0  5883.1     .16       0
    5910      .1       0  5995.9     .16       0  6163.6      .1       0
    6166     .16       0
Bank Sta=4913.4,4919.4
XS Rating Curve= 0 ,0
Exp/Cntr=0.3,0.1

Type RM Length L Ch R = 1 ,7359    ,743,743,743
BEGIN DESCRIPTION:
UNT0103 IN SAND CR 3.0
END DESCRIPTION:
XS GIS Cut Line= 3
      3498592.13     10519191.65      3499792.11     10519791.64
      3500992.08     10518991.66
#Sta/Elev= 30
  3675.9  423.24  3756.9  417.98  3787.7  418.79  3863.1  411.38  3907.9  410.28
  3935.8  406.55  4002.9  404.58  4137.1  396.56  4153.8  393.97  4243.3  390.26
  4849.6  385.79  4852.4  385.29  4855.6  385.79  4906.7  387.15  5421.6  387.47
  5508.9  389.75  5752.1  387.49  5875.3  388.88  6063.1  387.56  6124.4  389.13
  6149.9   389.8  6199.8  391.21  6220.9  393.93  6229.9  397.42  6250.9  401.78
  6380.1  401.82  6423.7  406.28  6437.2  410.28  6458.3  413.03  6459.7  413.03
#Mann= 8 ,-1 , 0
  3675.9     .05       0  4849.6     .07       0  4855.6     .05       0
  4906.7     .16       0  5508.9     .12       0  6124.4     .16       0
  6149.9      .1       0  6458.3     .16       0
Bank Sta=4849.6,4855.6
XS Rating Curve= 0 ,0
Exp/Cntr=0.3,0.1

Type RM Length L Ch R = 1 ,6616    ,924,924,924
BEGIN DESCRIPTION:
UNT0103 IN SAND CR 2.0
END DESCRIPTION:
XS GIS Cut Line= 4
        3498010.     10519605.44      3499442.25     10520308.55
      3499770.75     10520545.16      3502707.48     10520022.16
#Sta/Elev= 30
  3243.8   442.4  3541.4  422.65  3771.9  415.61  3839.3  410.28  3878.7  404.38
  3929.3  402.97  4041.7  393.49  4345.1  387.07  4472.7  386.28  4578.8  385.99
  4829.5  384.74  4911.2  384.84  4985.5  384.95  4996.4  382.02  4999.1  381.52
  5002.4  382.02    5107  385.51  5702.8  385.62  5722.5  385.48  6108.9  387.58
  6477.1  385.69  7119.1  388.54  7358.3  392.35  7558.6  400.21  7732.4  407.92
    7830  411.94  8095.5  419.77  8136.4  421.08    8193  421.23  8227.1  424.27
#Mann= 18 ,-1 , 0
  3243.8     .05       0  4345.1     .16       0  4472.7     .05       0
  4578.8     .16       0  4829.5     .05       0  4911.2     .16       0
  4996.4     .07       0  5002.4     .16       0  5702.8     .05       0
  5722.5     .16       0  6477.1     .05       0  7119.1      .1       0
  7558.6     .16       0  7732.4     .05       0    7830     .16       0
  8095.5      .1       0  8136.4     .16       0    8193     .05       0
Bank Sta=4996.4,5002.4
XS Rating Curve= 0 ,0
Exp/Cntr=0.3,0.1

Type RM Length L Ch R = 1 ,5692    ,912,912,912
BEGIN DESCRIPTION:
UNT0103 IN SAND CR 4.1
END DESCRIPTION:
XS GIS Cut Line= 4
      3497937.05     10519943.96      3499181.84     10521126.25
       3499468.3     10521110.63      3502801.61     10520282.51
#Sta/Elev= 30
  3197.3  446.82  3595.3  412.14  3757.9  400.61  3786.2  400.31  3793.5  402.71
  3800.4  400.11  3807.6  402.01  3878.4  392.18    3963  387.43    4232   383.1
  4639.6  382.67  4964.4  382.78  4984.4   382.2  4991.5  379.57  4994.2  379.07
  4997.5  379.57  5024.5  382.63  5384.3  383.61  5508.3  381.46  5885.6  385.54
  6111.6  384.55  6293.9  396.11  6482.6  384.99  6641.9  386.76  6996.8  383.53
  7361.8  386.18  7994.2  411.44  8206.1  412.17  8469.2   426.2  8635.6  432.27
#Mann= 7 ,-1 , 0
  3197.3     .05       0  4639.6     .16       0  4991.5     .07       0
  4997.5     .16       0  6641.9     .05       0  7361.8      .1       0
  8469.2     .16       0
Bank Sta=4991.5,4997.5
XS Rating Curve= 0 ,0
Exp/Cntr=0.3,0.1

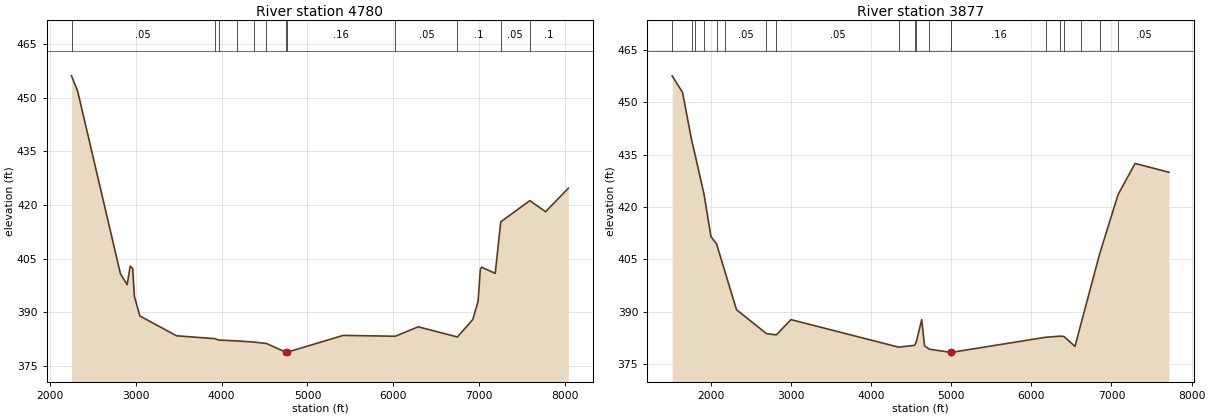
Type RM Length L Ch R = 1 ,4780    ,903,903,903
BEGIN DESCRIPTION:
UNT0103 IN SAND CR 3.1
END DESCRIPTION:
XS GIS Cut Line= 4
      3497749.56     10520032.52      3499697.46     10521636.67
       3500155.8     10521475.21       3502775.6     10520558.54
#Sta/Elev= 30
  2252.5  456.13  2324.5   451.8  2822.3  400.77  2900.5  397.74  2935.7  402.91
  2964.3  402.31  2985.2  394.39    3049  388.98  3475.1  383.44  3919.4  382.64
  3967.9  382.25  4182.6     382  4374.7  381.69  4520.6   381.3  4751.8  378.81
  4754.6  378.31  4757.8  378.81  5416.9  383.55  6023.4  383.31    6289  385.95
  6745.7  383.11  6924.7  387.98  6986.8  393.08  7012.5  401.98  7027.2  402.62
  7186.1   400.9  7250.5   415.3    7589  421.23  7772.4  418.14  8037.4  424.69
#Mann= 12 ,-1 , 0
  2252.5     .05       0  3919.4     .16       0  3967.9     .05       0
  4182.6     .16       0  4374.7     .05       0  4520.6     .16       0
  4751.8     .07       0  4757.8     .16       0  6023.4     .05       0
  6745.7      .1       0  7250.5     .05       0    7589      .1       0
Bank Sta=4751.8,4757.8
XS Rating Curve= 0 ,0
Exp/Cntr=0.3,0.1

Type RM Length L Ch R = 1 ,3877    ,0,0,0
BEGIN DESCRIPTION:
UNT0103 IN SAND CR 1.0
END DESCRIPTION:
XS GIS Cut Line= 4
      3497612.38     10520079.36      3500084.62     10522252.99
      3500570.73     10522204.38       3502647.1     10520968.28
#Sta/Elev= 30
  1520.6  457.62  1649.8  452.84  1762.7  439.24  1801.1  435.48  1918.3  423.63
  2003.7  411.56  2073.9  409.48  2182.8  401.21  2322.5  390.61  2696.3  383.75
  2818.8  383.39  3002.8  387.75  4345.5  379.87  4544.2  380.39  4564.3  381.31
  4632.8  387.75    4668  380.26  4727.1  379.29  4997.9  378.37  5000.7  377.87
  5003.9  378.37    6177   382.7  6363.4  383.02  6405.9  382.94  6544.9  380.08
  6622.5  386.82  6853.9  406.73  7082.6  423.61  7294.6  432.51  7717.5  429.98
#Mann= 20 ,-1 , 0
  1520.6     .05       0  1762.7     .16       0  1801.1     .05       0
  1918.3     .16       0  2073.9     .16       0  2182.8     .05       0
  2696.3     .16       0  2818.8     .05       0  4345.5     .16       0
  4544.2      .1       0  4564.3     .16       0  4727.1     .16       0
  4997.9     .07       0  5003.9     .16       0    6177     .12       0
  6363.4     .05       0  6405.9     .16       0  6622.5     .05       0
  6853.9      .1       0  7082.6     .05       0
Bank Sta=4997.9,5003.9
XS Rating Curve= 0 ,0
Exp/Cntr=0.3,0.1

Chan Stop Cuts=-1
Use User Specified Reach Order=0
Composite Channel Slope=5