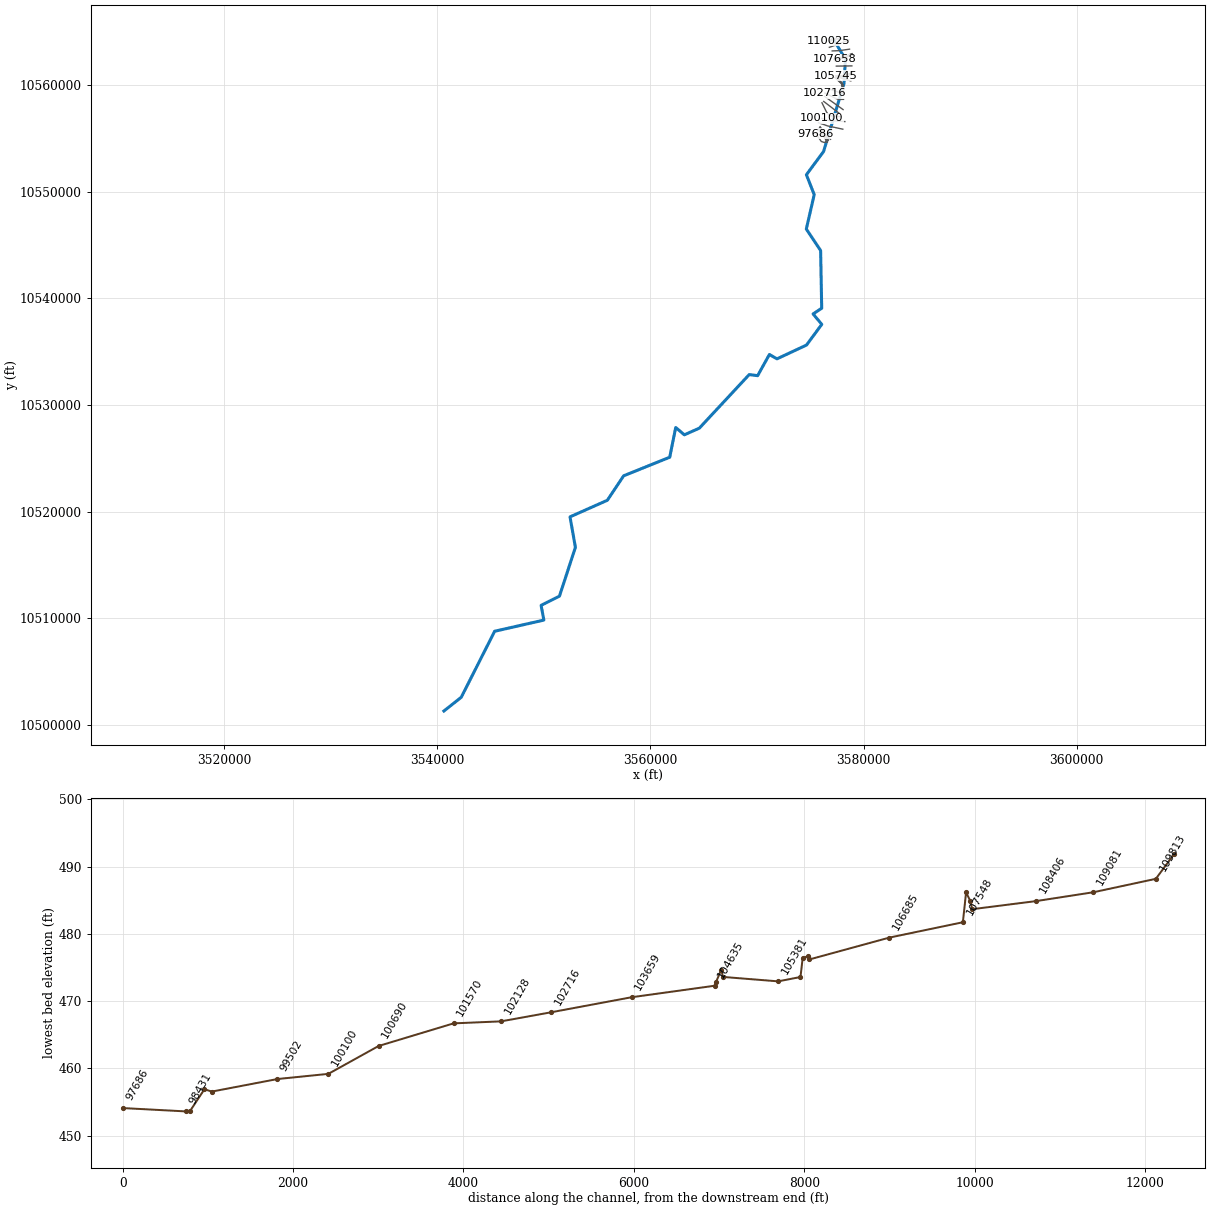
--- SANDERS CREEK.prj (project) ---

Proj Title=SANDERS CREEK Base Level Engineering
Current Plan=p01
Default Exp/Contr=0.3,0.1
English Units
Geom File=g01
Flow File=f01
Plan File=p01
Y Axis Title=Elevation
X Axis Title(PF)=Main Channel Distance
X Axis Title(XS)=Station
BEGIN DESCRIPTION:
SANDERS CREEK
END DESCRIPTION:
DSS Export Rating Curves= 0
DSS Export Rating Curve Sorted= 0
DSS Export Volume Flow Curves= 0
DXF OffsetX= 0
DXF OffsetY= 0
DXF ScaleX= 1
DXF ScaleY= 10

--- SANDERS CREEK.p01 (plan) ---

Plan Title=Multiple Run
Short Identifier=Multiple
Geom File=g01
Flow File=f01
Subcritical Flow
K Sum by GR= 0
Std Step Tol= 0.01
Critical Tol= 0.01
Num of Std Step Trials= 20
Max Error Tol= 0.3
Flow Tol Ratio= 0.001
Split Flow NTrial= 30
Split Flow Tol= 0.02
Split Flow Ratio= 0.02
Log Output Level= 0
Friction Slope Method= 1
Unsteady Friction Slope Method= 2
Unsteady Bridges Friction Slope Method= 1
Parabolic Critical Depth
Global Vel Dist=  1 , 1 , 1
Global Log Level= 0
CheckData=True
Encroach Param= -1, 0, 0, 0
BEGIN DESCRIPTION:
Multiple Run
END DESCRIPTION:

--- SANDERS CREEK.f01 (steady flow) ---

Flow Title=Multiple
Program Version=4.10
Number of Profiles= 7
Profile Names=10-year,25-year,50-year,1pct_min,100-year,1pct_plu,500-year
River Rch & RM=SANDERS CREEK,Reach-1         ,110025
    1420    1967    2421    2169    2934    3967    4298
River Rch & RM=SANDERS CREEK,Reach-1         ,100100
    1739    2429    3005    2705    3659    4948    5411
River Rch & RM=SANDERS CREEK,Reach-1         ,97453
    2443    3469    4340    3946    5337    7217    8054
River Rch & RM=SANDERS CREEK,Reach-1         ,93335
    2730    3884    4864    4425    5985    8094    9043
River Rch & RM=SANDERS CREEK,Reach-1         ,91785
    3171    4547    5724    5234    7078    9572   10801
River Rch & RM=SANDERS CREEK,Reach-1         ,89337
    3327    4773    6012    5499    7436   10057   11354
River Rch & RM=SANDERS CREEK,Reach-1         ,86567
    3500    5020    6322    5778    7814   10567   11914
River Rch & RM=SANDERS CREEK,Reach-1         ,82121
    3736    5374    6781    6209    8397   11355   12850
River Rch & RM=SANDERS CREEK,Reach-1         ,78304
    4031    5791    7299    6674    9025   12206   13772
River Rch & RM=SANDERS CREEK,Reach-1         ,66914
    4099    5881    7406    6763    9147   12370   13924
River Rch & RM=SANDERS CREEK,Reach-1         ,60687
    4463    6422    8105    7416   10029   13563   15327
River Rch & RM=SANDERS CREEK,Reach-1         ,58827
    5156    7465    9461    8692   11754   15896   18106
River Rch & RM=SANDERS CREEK,Reach-1         ,53994
    6318    9203   11711   10798   14603   19749   22656
River Rch & RM=SANDERS CREEK,Reach-1         ,51792
    6336    9217   11718   10793   14597   19741   22598
River Rch & RM=SANDERS CREEK,Reach-1         ,44171
    6557    9528   12104   11138   15063   20370   23272
River Rch & RM=SANDERS CREEK,Reach-1         ,40778
    7750   11325   14442   13338   18037   24394   28066
River Rch & RM=SANDERS CREEK,Reach-1         ,36894
    8258   12093   15445   14284   19317   26124   30140
River Rch & RM=SANDERS CREEK,Reach-1         ,34430
    8083   11804   15046   13886   18779   25397   29181
River Rch & RM=SANDERS CREEK,Reach-1         ,29791
    8216   12016   15333   14167   19159   25910   29837
River Rch & RM=SANDERS CREEK,Reach-1         ,28797
    8152   11888   15140   13958   18877   25528   29271
River Rch & RM=SANDERS CREEK,Reach-1         ,23271
    8506   12423   15838   14616   19766   26732   30710
River Rch & RM=SANDERS CREEK,Reach-1         ,21595
    8519   12430   15836   14603   19749   26709   30638
River Rch & RM=SANDERS CREEK,Reach-1         ,19263
    8696   12687   16162   14902   20153   27255   31256
River Rch & RM=SANDERS CREEK,Reach-1         ,13594
    8915   12989   16531   15225   20590   27845   31859
Boundary for River Rch & Prof#=SANDERS CREEK,Reach-1         , 1
Up Type= 0
Dn Type= 3
Dn Slope=0.0001
Boundary for River Rch & Prof#=SANDERS CREEK,Reach-1         , 2
Up Type= 0
Dn Type= 3
Dn Slope=0.0001
Boundary for River Rch & Prof#=SANDERS CREEK,Reach-1         , 3
Up Type= 0
Dn Type= 3
Dn Slope=0.0001
Boundary for River Rch & Prof#=SANDERS CREEK,Reach-1         , 4
Up Type= 0
Dn Type= 3
Dn Slope=0.0001
Boundary for River Rch & Prof#=SANDERS CREEK,Reach-1         , 5
Up Type= 0
Dn Type= 3
Dn Slope=0.0001
Boundary for River Rch & Prof#=SANDERS CREEK,Reach-1         , 6
Up Type= 0
Dn Type= 3
Dn Slope=0.0001
Boundary for River Rch & Prof#=SANDERS CREEK,Reach-1         , 7
Up Type= 0
Dn Type= 3
Dn Slope=0.0001
DSS Import GetInterval= 0
DSS Import GetPeak= 0
DSS Import FillOption= 0

--- SANDERS CREEK.g01 (geometry) ---

Geom Title=Existing Conditions
Program Version=4.10

River Reach=SANDERS CREEK   ,Reach-1
Reach XY= 30
      3577131.03      10564388.6       3578300.1     10562446.12
      3578161.89     10560159.53      3576242.71     10553781.04
      3574632.05     10551607.84      3575367.42     10549742.79
      3574624.73     10546508.25      3575968.81     10544493.82
      3576069.59     10539082.87      3575262.71     10538541.99
      3576077.09     10537569.01       3574645.1     10535626.07
      3571873.26     10534331.32      3571161.66     10534738.47
      3570055.45     10532752.81      3569265.87     10532855.11
      3564585.19     10527828.39      3563178.07     10527203.65
      3562366.44     10527889.42      3561806.06     10525100.11
      3557479.64     10523356.38      3555951.17     10521061.95
      3552445.13     10519505.09      3552952.38     10516644.01
      3551455.49     10512063.69      3549733.03      10511198.6
      3549992.41      10509817.3       3545372.7      10508769.9
      3542238.34     10502574.43      3540612.11     10501287.04

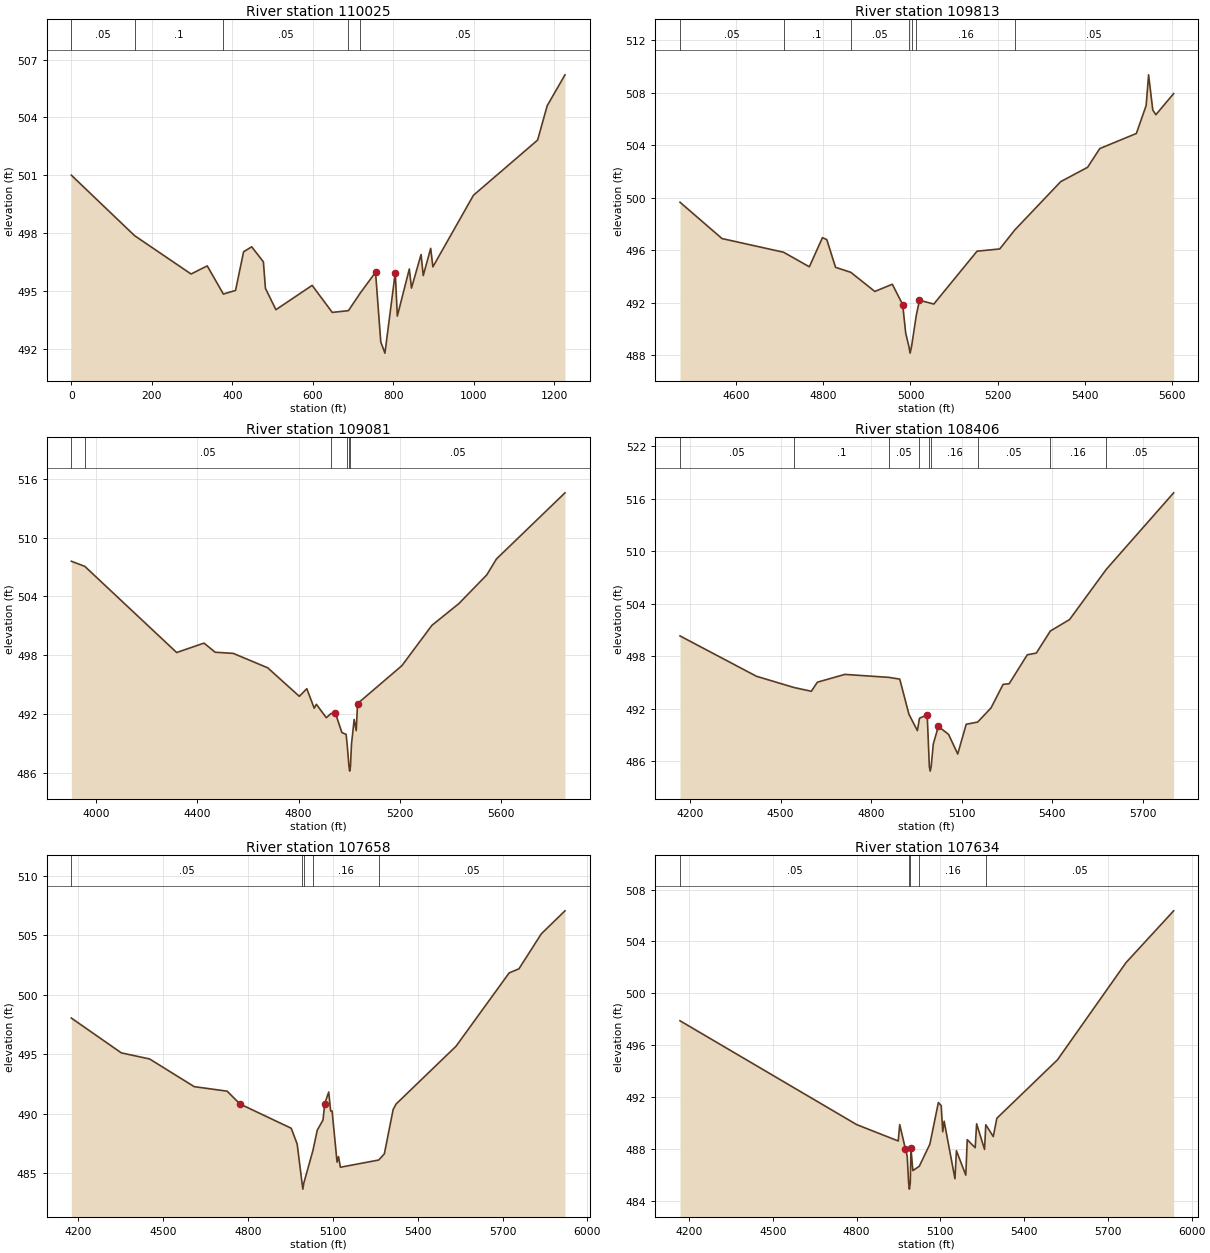
Type RM Length L Ch R = 1 ,110025  ,212,212,212
BEGIN DESCRIPTION:
SANDERS CREEK 152.0
END DESCRIPTION:
XS GIS Cut Line= 5
      3577918.46     10564417.98      3577421.72     10564375.14
      3577171.72     10564368.63      3577088.39      10564350.4
      3576725.11     10564199.36
#Sta/Elev= 30
       0  501.01   156.9  497.88   297.4  495.89   337.6  496.31   377.7  494.85
   407.9  495.04   427.9  497.04     448   497.3   477.1  496.52   482.1  495.15
   508.2  494.04   598.2   495.3   648.2   493.9   688.3  493.99   718.3  494.92
   755.7  495.98   768.7  492.37     779  491.79   804.7  495.96   809.8  493.71
   839.6  496.15     845  495.16   868.8   496.9   874.2  495.81   892.7  497.22
   898.1  496.26   998.9  499.97  1158.3  502.83  1182.1  504.61  1226.3  506.21
#Mann= 5 ,-1 , 0
       0     .05       0   156.9      .1       0   377.7     .05       0
   688.3     .03       0   718.3     .05       0
Bank Sta=755.7,804.7
XS Rating Curve= 0 ,0
Exp/Cntr=0.3,0.1

Type RM Length L Ch R = 1 ,109813  ,732,732,732
BEGIN DESCRIPTION:
SANDERS CREEK 152.1
END DESCRIPTION:
XS GIS Cut Line= 4
      3577838.39     10564345.19      3577337.09     10564338.68
      3577266.78     10564317.85      3576769.36     10564069.14
#Sta/Elev= 30
    4472  499.67  4568.3   496.9  4709.2  495.86  4768.3  494.75  4798.3  496.97
  4808.3  496.82  4828.3  494.71  4863.2  494.33  4918.3  492.87  4958.3  493.42
  4982.1  491.87    4989   489.7  4996.4  488.67  4999.1  488.17  5002.4  488.67
  5013.4  491.08  5020.6   492.2  5053.4  491.91  5152.5  495.94  5204.4  496.11
    5239  497.56  5344.1  501.24  5405.6  502.33  5433.6  503.76  5517.4  504.91
  5539.8  507.04  5545.4  509.38    5555   506.7  5562.1  506.34  5602.8  507.95
#Mann= 7 ,-1 , 0
    4472     .05       0  4709.2      .1       0  4863.2     .05       0
  4996.4     .03       0  5002.4     .05       0  5013.4     .16       0
    5239     .05       0
Bank Sta=4982.1,5020.6
XS Rating Curve= 0 ,0
Exp/Cntr=0.3,0.1

Type RM Length L Ch R = 1 ,109081  ,675,675,675
BEGIN DESCRIPTION:
SANDERS CREEK 151.0
END DESCRIPTION:
XS GIS Cut Line= 3
       3578606.6     10564261.49      3577666.49     10563873.47
      3576786.66     10563563.71
#Sta/Elev= 30
  3902.1  507.59  3955.2  507.07  4318.1  498.28  4426.2  499.24  4470.1  498.31
  4541.8  498.19  4677.7  496.72  4802.7  493.81  4832.1  494.59  4861.4   492.6
  4869.8     493  4909.2  491.63  4927.9  492.06    4945   492.1  4970.6  490.12
  4987.4  489.93  4991.6  488.89  4998.6  486.68  5001.4  486.18  5004.6  486.68
  5008.6  488.94  5019.2  491.45  5027.3  490.31  5032.6  493.07  5207.7  496.94
  5326.2  501.05  5432.7  503.27    5543   506.2  5581.1  507.82  5851.9  514.57
#Mann= 6 ,-1 , 0
  3902.1     .08       0  3955.2     .05       0  4927.9     .16       0
  4991.6     .05       0  4998.6     .03       0  5004.6     .05       0
Bank Sta=4945,5032.6
XS Rating Curve= 0 ,0
Exp/Cntr=0.3,0.1

Type RM Length L Ch R = 1 ,108406  ,748,748,748
BEGIN DESCRIPTION:
SANDERS CREEK 149.0
END DESCRIPTION:
XS GIS Cut Line= 3
      3578682.54     10563391.91      3577741.54     10563253.01
       3577057.5     10563225.24
#Sta/Elev= 30
  4166.9  500.32    4420  495.71  4544.7  494.42    4602  493.99  4622.2  495.03
  4713.2  495.92  4858.9  495.58  4895.1  495.38  4925.5  491.37  4953.5  489.49
  4960.5  490.91  4986.1  491.29  4993.2  485.36    4996  484.86  4999.2  485.36
  5006.3  487.98  5023.1  489.97  5056.9  489.06  5087.2  486.82  5115.3  490.22
  5153.3  490.47  5197.6  492.09  5237.6  494.78  5257.6  494.85  5317.7  498.16
  5347.7  498.36  5394.1  500.88  5457.8  502.19  5579.7  507.94  5802.7  516.68
#Mann= 9 ,-1 , 0
  4166.9     .05       0  4544.7      .1       0  4858.9     .05       0
  4960.5     .16       0  4993.2     .07       0  4999.2     .16       0
  5153.3     .05       0  5394.1     .16       0  5579.7     .05       0
Bank Sta=4986.1,5023.1
XS Rating Curve= 0 ,0
Exp/Cntr=0.3,0.1

Type RM Length L Ch R = 1 ,107658  ,24,24,24
BEGIN DESCRIPTION:
SANDERS CREEK 146.3
END DESCRIPTION:
XS GIS Cut Line= 4
      3578911.71      10562968.3      3578168.63     10562693.99
      3578043.63     10562673.15      3577246.03     10562454.68
#Sta/Elev= 30
    4175  498.05  4351.8  495.12  4451.7  494.61  4609.6  492.28    4726   491.9
  4771.5  490.82  4952.7  488.78  4973.7  487.45    4991  484.16  4993.7  483.66
    4997  484.16  5029.5  486.92  5044.7  488.62    5065  489.47  5071.3  490.86
  5085.2  491.83  5092.1  490.23  5097.2  490.23  5114.7  485.93  5119.9   486.4
  5126.5   485.5  5262.2  486.11    5282  486.63  5313.1  490.36  5323.5  490.82
  5535.5  495.68  5723.4  501.85  5757.9  502.19  5837.2  505.14  5920.8  507.07
#Mann= 5 ,-1 , 0
    4175     .05       0    4991     .03       0    4997     .05       0
  5029.5     .16       0  5262.2     .05       0
Bank Sta=4771.5,5071.3
XS Rating Curve= 0 ,0
Exp/Cntr=0.3,0.1

Type RM Length L Ch R = 1 ,107634  ,48,48,48
BEGIN DESCRIPTION:
SANDERS CREEK 146.1
END DESCRIPTION:
XS GIS Cut Line= 4
        3578929.      10562940.5      3578168.63     10562669.68
       3578008.9      10562641.9      3577241.52     10562419.67
#Sta/Elev= 30
  4167.3  497.89  4800.2  489.89    4949  488.63  4954.3  489.89  4974.5  488.04
  4981.1  487.47  4986.2  485.42  4988.9  484.92  4992.2  485.42  4994.3  488.08
  5001.4  486.35  5024.3  486.68  5062.3  488.38  5092.7  491.59  5102.9  491.35
  5108.4  489.34  5113.5  490.15  5152.2  485.72  5157.4  487.88    5191     486
  5196.2  488.73  5224.6  488.11  5229.8  489.95  5258.2  487.98  5262.6  489.88
  5289.4  488.97  5302.2  490.38  5519.3  494.88  5764.9  502.37  5935.5  506.36
#Mann= 5 ,-1 , 0
  4167.3     .05       0  4986.2     .03       0  4992.2     .05       0
  5024.3     .16       0  5262.6     .05       0
Bank Sta=4974.5,4994.3
XS Rating Curve= 0 ,0
Exp/Cntr=0.3,0.1

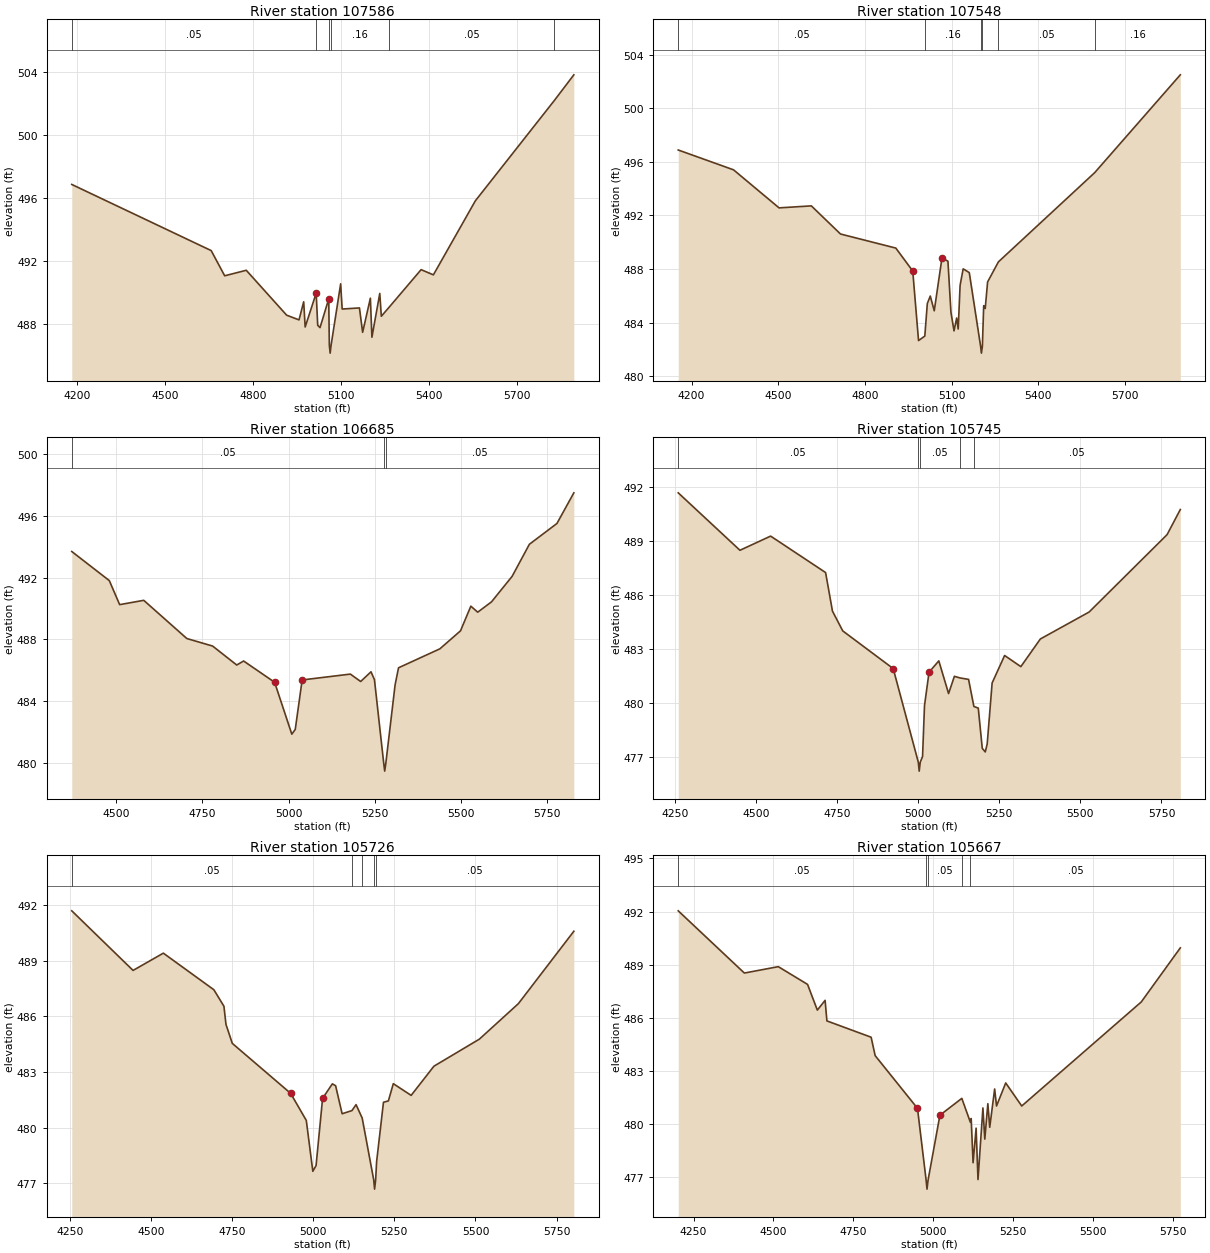
Type RM Length L Ch R = 1 ,107586  ,38,38,38
BEGIN DESCRIPTION:
SANDERS CREEK 144.2
END DESCRIPTION:
XS GIS Cut Line= 4
      3578936.03      10562881.5      3578206.82     10562631.49
       3578071.4     10562600.24       3577305.6     10562354.21
#Sta/Elev= 30
    4181  496.87    4657  492.67  4703.1  491.07  4776.8  491.42  4914.6  488.57
  4956.9  488.27  4972.8  489.42  4977.9  487.82  5015.5  489.97  5016.4  489.62
  5020.7  487.93  5028.6  487.78  5058.3   489.6  5060.4  486.66  5063.2  486.16
  5066.4  486.66    5099  490.56  5104.2  488.96  5163.2  489.03  5174.1  487.48
  5200.5  489.65  5205.8  487.17  5232.6  489.95  5237.9   488.5  5264.8  489.08
  5373.7  491.46  5415.7  491.13  5558.9  495.83  5828.6   502.2  5895.2  503.83
#Mann= 6 ,-1 , 0
    4181     .05       0  5016.4     .16       0  5060.4     .03       0
  5066.4     .16       0  5264.8     .05       0  5828.6     .16       0
Bank Sta=5015.5,5058.3
XS Rating Curve= 0 ,0
Exp/Cntr=0.3,0.1

Type RM Length L Ch R = 1 ,107548  ,863,863,863
BEGIN DESCRIPTION:
SANDERS CREEK 144.3
END DESCRIPTION:
XS GIS Cut Line= 4
      3578974.16     10562839.81      3578206.82     10562589.82
      3578085.29     10562568.99      3577321.42      10562305.1
#Sta/Elev= 30
  4153.7  496.88  4345.2   495.4  4502.9  492.56  4614.6  492.71  4715.6  490.61
  4907.1  489.56  4965.7  487.85  4985.8  482.66  5007.5  482.99  5016.2  485.42
  5026.4  485.98  5040.2  484.88    5067  488.83  5087.6  488.58    5098  484.77
  5108.6  483.38  5117.8  484.34  5123.1  483.52  5129.7  486.78  5140.3  488.01
  5161.5  487.73  5200.8  482.22  5203.5  481.72  5206.8  482.22  5211.4  485.26
  5216.7  485.05  5224.9  487.03  5262.3  488.53  5595.8  495.19  5892.2  502.49
#Mann= 6 ,-1 , 0
  4153.7     .05       0  5007.5     .16       0  5200.8     .03       0
  5206.8     .16       0  5262.3     .05       0  5595.8     .16       0
Bank Sta=4965.7,5067
XS Rating Curve= 0 ,0
Exp/Cntr=0.3,0.1

Type RM Length L Ch R = 1 ,106685  ,940,940,940
BEGIN DESCRIPTION:
SANDERS CREEK 143.1
END DESCRIPTION:
XS GIS Cut Line= 2
      3578901.22     10561821.42      3577442.97     10561800.58
#Sta/Elev= 30
  4370.4   493.7  4479.5  491.81  4509.5  490.25  4579.5  490.53  4704.6  488.05
  4779.6  487.56  4849.6  486.33  4869.6  486.59  4959.6  485.21  5009.6  481.84
  5019.6  482.15  5039.6  485.36  5179.6  485.74  5209.6  485.26  5239.6  485.89
  5249.6  485.38  5276.6  479.94  5279.4  479.44  5282.6  479.94  5309.6  485.04
  5319.6  486.15  5439.6  487.38  5499.6  488.55  5529.6  490.15  5549.6  489.76
  5589.6  490.43  5649.6  492.09  5699.7  494.17  5779.7  495.52  5828.8  497.51
#Mann= 3 ,-1 , 0
  4370.4     .05       0  5276.6     .03       0  5282.6     .05       0
Bank Sta=4959.6,5039.6
XS Rating Curve= 0 ,0
Exp/Cntr=0.3,0.1

Type RM Length L Ch R = 1 ,105745  ,19,19,19
BEGIN DESCRIPTION:
SANDERS CREEK 146.4
END DESCRIPTION:
XS GIS Cut Line= 5
      3578911.03     10561167.61      3578341.54     10560969.68
      3578091.54     10560948.85      3577973.49     10560872.46
      3577421.37     10560900.24
#Sta/Elev= 30
  4260.8  491.69    4451  488.49  4545.5  489.28  4714.9  487.25  4736.1   485.1
  4767.8     484  4923.3   481.9  5000.6  476.69  5003.4  476.19  5006.6  476.69
  5013.7     477  5019.7  479.84  5033.7   481.7  5063.8  482.33  5093.9  480.51
  5111.8  481.47  5129.3  481.38  5155.5   481.3  5171.9  479.79  5185.4   479.7
  5197.7  477.46  5206.9  477.26  5212.9   477.7  5228.1   481.1  5266.6  482.63
  5316.6  482.01  5376.7  483.55  5526.9  485.05  5767.2  489.36    5808  490.76
#Mann= 5 ,-1 , 0
  4260.8     .05       0  5000.6     .03       0  5006.6     .05       0
  5129.3     .16       0  5171.9     .05       0
Bank Sta=4923.3,5033.7
XS Rating Curve= 0 ,0
Exp/Cntr=0.3,0.1

Type RM Length L Ch R = 1 ,105726  ,59,59,59
BEGIN DESCRIPTION:
SANDERS CREEK 146.2
END DESCRIPTION:
XS GIS Cut Line= 5
        3578911.     10561150.24      3578341.54     10560952.32
      3578091.54     10560931.49      3577973.49      10560855.1
      3577421.44     10560882.87
#Sta/Elev= 30
  4256.1  491.68    4445  488.47  4538.3   489.4  4693.9  487.43    4725  486.54
  4731.3  485.56  4750.8  484.54  4930.5  481.85  4978.8  480.39  4998.9  477.65
  5008.9  477.96    5029  481.58  5059.1  482.36  5069.1  482.26  5089.2  480.75
  5119.4  480.92  5132.1  481.24    5151  480.52  5186.5  477.19  5189.2  476.69
  5192.5  477.19  5195.4  478.16  5216.6  481.37  5231.7  481.44  5246.9  482.37
  5301.9  481.74    5372  483.31  5512.2  484.77  5632.3  486.68  5803.2  490.58
#Mann= 5 ,-1 , 0
  4256.1     .05       0  5119.4     .16       0    5151     .05       0
  5186.5     .03       0  5192.5     .05       0
Bank Sta=4930.5,5029
XS Rating Curve= 0 ,0
Exp/Cntr=0.3,0.1

Type RM Length L Ch R = 1 ,105667  ,25,25,25
BEGIN DESCRIPTION:
SANDERS CREEK 146.0
END DESCRIPTION:
XS GIS Cut Line= 6
      3578956.16     10561125.94      3578404.04     10560910.65
      3578338.07     10560889.82      3578101.96     10560875.93
      3578011.68     10560820.38      3577446.41     10560841.18
#Sta/Elev= 30
  4202.2  492.04    4409  488.53  4515.2  488.89  4606.7  487.89  4637.3  486.44
  4661.6  486.99  4667.2  485.83  4805.5  484.91  4818.2  483.87  4950.5   480.9
  4977.6  476.84  4980.3  476.34  4983.6  476.84  5020.7  480.51  5089.2  481.46
    5116  480.11  5118.5  480.32  5124.4  477.83  5133.9  479.78  5139.8  476.88
  5155.2  480.92  5161.1  479.16  5170.6  481.16  5176.5  479.83  5191.9  481.99
  5197.8  481.03  5226.5  482.33  5276.6  481.03  5650.5   486.9  5772.6  489.95
#Mann= 5 ,-1 , 0
  4202.2     .05       0  4977.6     .03       0  4983.6     .05       0
  5089.2     .16       0    5116     .05       0
Bank Sta=4950.5,5020.7
XS Rating Curve= 0 ,0
Exp/Cntr=0.3,0.1

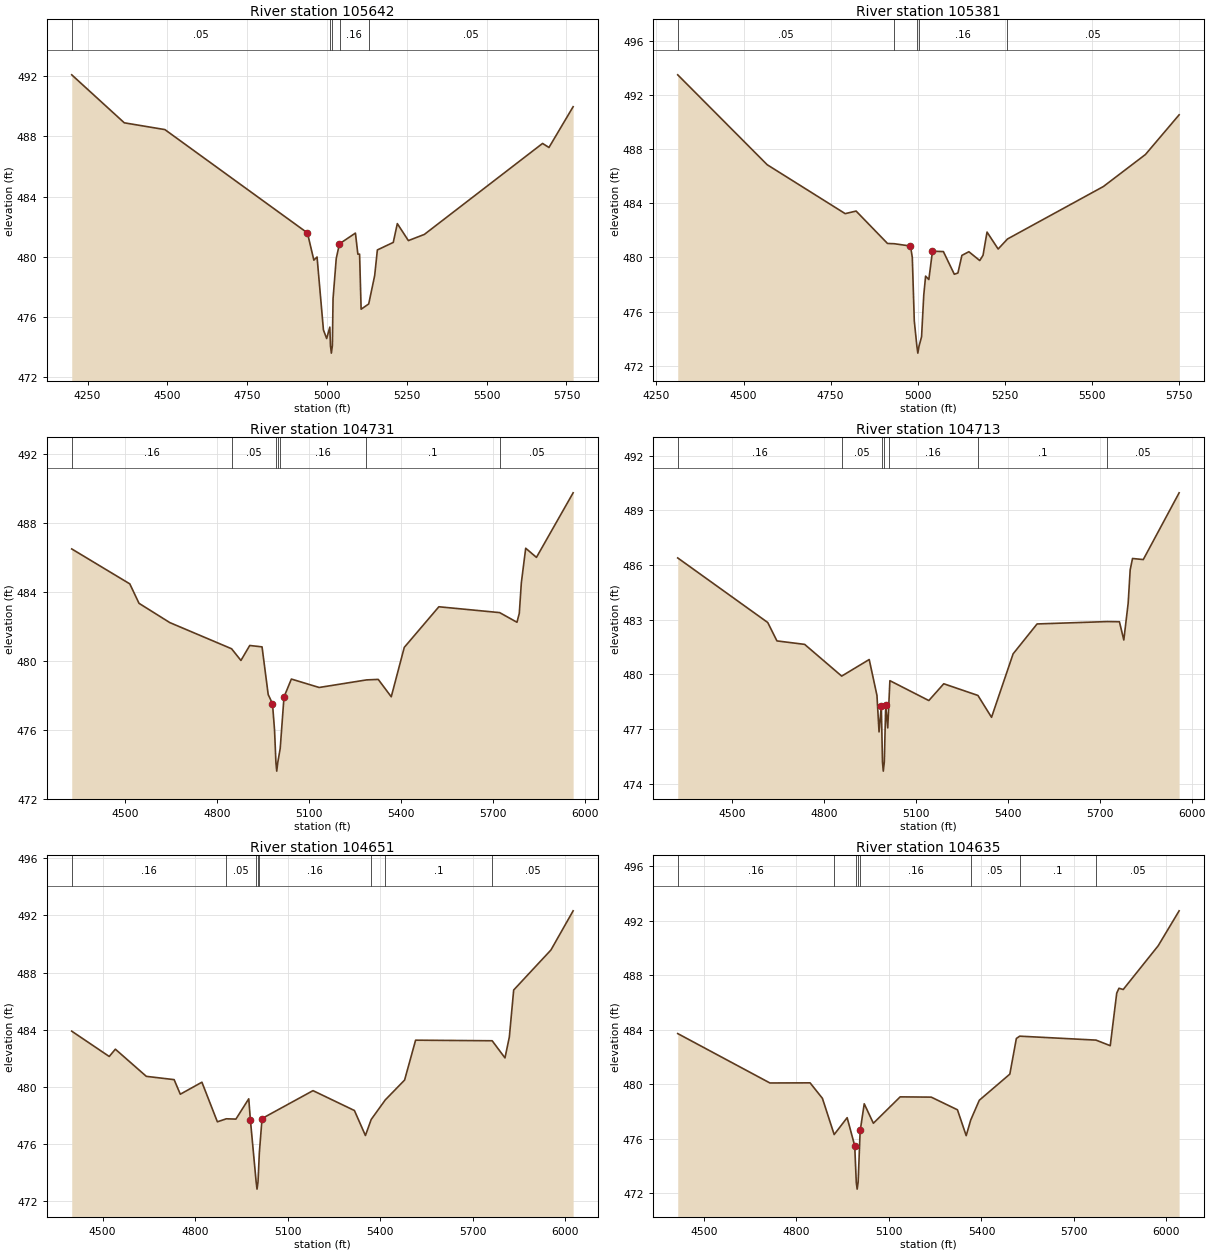
Type RM Length L Ch R = 1 ,105642  ,261,261,261
BEGIN DESCRIPTION:
SANDERS CREEK 146.5
END DESCRIPTION:
XS GIS Cut Line= 6
      3578956.09     10561101.61      3578404.04     10560886.35
      3578338.07     10560865.51      3578101.96     10560851.63
      3578011.68     10560796.07      3577446.44     10560816.88
#Sta/Elev= 30
  4200.6  492.09  4365.2   488.9  4492.3  488.45  4938.8  481.58  4958.9  479.77
  4968.9  479.98  4988.9  475.13    4999  474.56  5008.9  475.32  5010.9  474.09
  5013.7  473.59  5016.9  474.09    5019  477.21    5029  479.88    5039  480.85
    5040  480.87  5089.1  481.57  5096.7  480.17  5102.1  480.17  5106.9  476.51
  5130.7  476.86  5149.4  478.75  5157.8  480.45  5207.6  480.95  5220.3   482.2
  5254.9  481.07  5304.9  481.48  5675.2  487.53  5695.2  487.26  5770.9  489.97
#Mann= 5 ,-1 , 0
  4200.6     .05       0  5010.9     .03       0  5016.9     .05       0
    5040     .16       0  5130.7     .05       0
Bank Sta=4938.8,5039
XS Rating Curve= 0 ,0
Exp/Cntr=0.3,0.1

Type RM Length L Ch R = 1 ,105381  ,650,650,650
BEGIN DESCRIPTION:
SANDERS CREEK 143.3
END DESCRIPTION:
XS GIS Cut Line= 3
      3578802.51     10560412.38      3577621.93     10560768.29
      3577415.37      10560776.9
#Sta/Elev= 30
    4311  493.47  4567.8  486.84  4791.9  483.23  4823.2  483.42  4913.4  481.03
  4933.1  481.01  4979.3  480.84  4984.6     480  4990.3  475.32  4997.8  473.44
  5000.5  472.94  5003.8  473.44  5011.2  474.15  5017.5  477.22  5022.8  478.62
  5032.1  478.37  5042.5  480.46  5073.9  480.43  5105.2  478.76  5115.6  478.85
    5127  480.15    5147  480.42  5178.3  479.77  5187.7  480.16  5199.2  481.87
  5231.1  480.62  5257.9  481.36  5533.3  485.23    5654  487.59  5750.8  490.52
#Mann= 5 ,-1 , 0
    4311     .05       0  4933.1     .16       0  4997.8     .07       0
  5003.8     .16       0  5257.9     .05       0
Bank Sta=4979.3,5042.5
XS Rating Curve= 0 ,0
Exp/Cntr=0.3,0.1

Type RM Length L Ch R = 1 ,104731  ,18,18,18
BEGIN DESCRIPTION:
SANDERS CREEK 144.1
END DESCRIPTION:
XS GIS Cut Line= 6
      3578114.12     10559382.85      3578058.56     10560028.71
      3578023.83     10560059.96      3578008.21      10560186.7
       3577671.4     10560549.54      3577431.79     10560759.63
#Sta/Elev= 30
    4326  486.51  4515.5  484.48  4545.6  483.35  4646.1  482.23  4847.7  480.71
  4878.2  480.03  4906.9   480.9  4947.1  480.82  4967.2  478.05  4981.2  477.52
  4987.9  475.99  4992.4   474.1  4995.1   473.6  4998.4   474.1  5006.4  474.92
  5018.8  477.91  5042.8  478.95  5133.5  478.46    5288   478.9  5326.3  478.93
  5368.8  477.92  5411.3  480.79  5524.2  483.15  5722.6  482.81  5779.1  482.25
  5786.7  482.77  5793.4  484.55  5807.6  486.55  5842.7  486.02  5962.4  489.77
#Mann= 7 ,-1 , 0
    4326     .16       0  4847.7     .05       0  4992.4    .035       0
  4998.4     .05       0  5006.4     .16       0    5288      .1       0
  5722.6     .05       0
Bank Sta=4981.2,5018.8
XS Rating Curve= 0 ,0
Exp/Cntr=0.3,0.1

Type RM Length L Ch R = 1 ,104713  ,62,62,62
BEGIN DESCRIPTION:
SANDERS CREEK 144.0
END DESCRIPTION:
XS GIS Cut Line= 6
      3578103.69     10559369.01      3578048.14     10560014.82
      3578013.42     10560046.07      3577997.79     10560172.81
      3577660.99     10560535.65      3577421.41     10560745.72
#Sta/Elev= 30
    4323  486.39  4616.7  482.85  4646.8  481.84  4737.2  481.65  4858.1  479.91
  4947.9  480.82  4973.2  478.85    4980  476.85  4987.4  478.29  4991.2   475.2
  4993.9   474.7  4997.2   475.2  5001.7   478.3  5008.4  477.07    5011  478.03
  5015.4  479.66  5142.5  478.57  5191.2  479.49  5302.7  478.85  5347.1  477.65
  5417.5  481.13  5495.7  482.77  5724.7   482.9  5764.5  482.89  5778.8  481.89
    5793  483.91  5799.6  485.74  5807.2  486.36  5842.3   486.3  5959.3  489.96
#Mann= 7 ,-1 , 0
    4323     .16       0  4858.1     .05       0  4991.2    .035       0
  4997.2     .05       0    5011     .16       0  5302.7      .1       0
  5724.7     .05       0
Bank Sta=4987.4,5001.7
XS Rating Curve= 0 ,0
Exp/Cntr=0.3,0.1

Type RM Length L Ch R = 1 ,104651  ,16,16,16
BEGIN DESCRIPTION:
SANDERS CREEK 143.0
END DESCRIPTION:
XS GIS Cut Line= 5
       3578046.4     10559400.26      3578009.95     10559973.15
      3577956.13     10560002.67      3577961.33     10560146.76
      3577339.81     10560721.42
#Sta/Elev= 30
  4400.2   483.9  4521.8  482.13  4541.7  482.64  4642.1  480.74  4732.3  480.51
  4752.3  479.49  4822.4  480.33  4872.5  477.56  4901.4  477.77  4932.7  477.75
  4974.3  479.17  4979.5  477.72  4998.3  473.35  5001.1  472.85  5004.3  473.35
  5008.7  475.41  5017.4  477.79  5182.7  479.74    5317  478.35  5352.7   476.6
  5371.3  477.72    5417  479.09  5479.7  480.48  5515.4  483.27  5763.7  483.23
  5805.3  482.03  5819.4  483.49  5833.5  486.78  5954.3  489.58  6026.3  492.32
#Mann= 8 ,-1 , 0
  4400.2     .16       0  4901.4     .05       0  4998.3    .035       0
  5004.3     .05       0  5008.7     .16       0  5371.3     .05       0
    5417      .1       0  5763.7     .05       0
Bank Sta=4979.5,5017.4
XS Rating Curve= 0 ,0
Exp/Cntr=0.3,0.1

Type RM Length L Ch R = 1 ,104635  ,976,976,976
BEGIN DESCRIPTION:
SANDERS CREEK 143.2
END DESCRIPTION:
XS GIS Cut Line= 5
      3578025.57     10559393.25      3577989.11     10559966.21
      3577935.29     10559995.72       3577940.5     10560139.82
      3577318.95     10560714.49
#Sta/Elev= 30
  4414.9  483.72  4713.9  480.09  4844.2   480.1  4884.2  478.96  4922.3   476.3
  4964.4  477.54    4989  475.47    4994  472.79  4996.8  472.29    5000  472.79
  5006.7  476.64  5007.4  476.69  5019.8  478.56  5049.4  477.13  5136.4  479.07
  5237.1  479.05  5322.1  478.12  5350.5  476.22  5365.2  477.37    5393  478.82
    5492  480.74  5513.2  483.36    5524  483.53  5771.6  483.24  5817.7  482.83
  5838.7  486.69    5846  487.05  5859.8  486.96  5973.1  490.17  6041.1  492.74
#Mann= 8 ,-1 , 0
  4414.9     .16       0  4922.3     .05       0    4994    .035       0
    5000     .05       0  5007.4     .16       0  5365.2     .05       0
    5524      .1       0  5771.6     .05       0
Bank Sta=4989,5006.7
XS Rating Curve= 0 ,0
Exp/Cntr=0.3,0.1

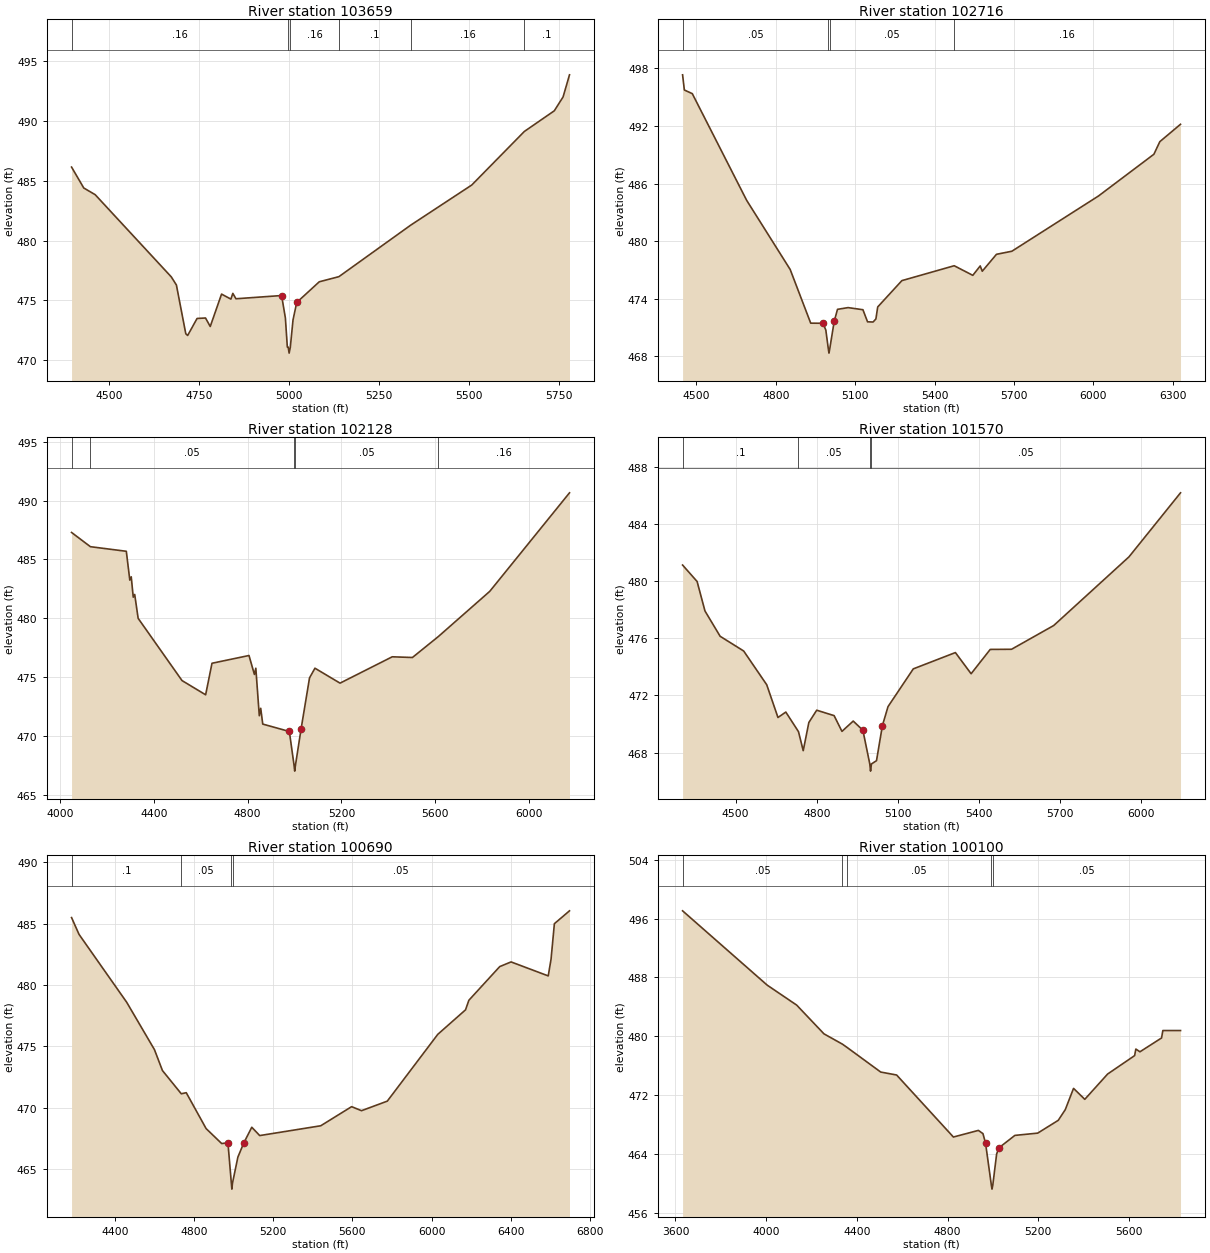
Type RM Length L Ch R = 1 ,103659  ,943,943,943
BEGIN DESCRIPTION:
SANDERS CREEK 141.0
END DESCRIPTION:
XS GIS Cut Line= 2
      3578034.24     10559223.16      3576725.27     10559669.59
#Sta/Elev= 30
  4395.4  486.15  4429.3   484.4    4461  483.84  4672.4  476.96  4686.6  476.28
  4712.7   472.2  4717.9  472.06    4744  473.48  4767.4  473.52  4780.6  472.81
    4812  475.52    4838   475.1  4843.3  475.58    4852  475.13  4978.8   475.4
  4989.3  473.52  4994.7  471.09    4997  471.08  4999.7  470.58    5003  471.08
  5010.5  473.36  5020.8  474.82  5083.4  476.55    5138  476.98  5336.9  481.28
    5507  484.65    5653  489.13  5736.2  490.86  5760.6  492.02  5778.4  493.87
#Mann= 6 ,-1 , 0
  4395.4     .16       0    4997     .07       0    5003     .16       0
    5138      .1       0  5336.9     .16       0    5653      .1       0
Bank Sta=4978.8,5020.8
XS Rating Curve= 0 ,0
Exp/Cntr=0.3,0.1

Type RM Length L Ch R = 1 ,102716  ,588,588,588
BEGIN DESCRIPTION:
SANDERS CREEK 140.0
END DESCRIPTION:
XS GIS Cut Line= 4
      3578118.77     10558680.21      3577676.04      10558673.7
      3577393.92     10558764.85      3576372.17     10559276.81
#Sta/Elev= 30
  4447.8  497.33  4454.5  495.75  4484.5  495.37    4690  484.26  4854.5  477.06
  4932.1  471.47  4978.8  471.46  4989.3  470.74  4998.4  468.85  5001.1  468.35
  5004.4  468.85  5020.8  471.65  5033.4  472.91  5073.4  473.09  5129.5  472.87
  5146.9  471.61  5167.9  471.59  5178.5  471.91  5185.4  473.16  5276.7   475.9
  5474.5  477.45  5544.8  476.45  5572.8  477.43  5580.6  476.88  5634.2  478.64
  5692.4  478.96  6019.7  484.71  6229.3  489.06  6251.7  490.37  6329.9  492.18
#Mann= 4 ,-1 , 0
  4447.8     .05       0  4998.4     .03       0  5004.4     .05       0
  5474.5     .16       0
Bank Sta=4978.8,5020.8
XS Rating Curve= 0 ,0
Exp/Cntr=0.3,0.1

Type RM Length L Ch R = 1 ,102128  ,558,558,558
BEGIN DESCRIPTION:
SANDERS CREEK 138.0
END DESCRIPTION:
XS GIS Cut Line= 2
      3578077.65     10557721.42      3576350.24     10558954.05
#Sta/Elev= 30
  4049.7  487.29  4130.1  486.08  4283.1  485.69  4297.9  483.24    4304  483.52
  4312.6  481.79  4318.8  482.02  4333.5  479.99  4520.4   474.7  4621.1  473.49
  4648.2  476.17  4805.9  476.83  4828.9  475.22    4835  475.75  4849.8  471.71
  4855.9  472.34  4864.5     471  4977.9  470.37  4997.9   467.5  5000.7     467
  5003.9   467.5    5028   470.6  5063.9  474.93    5087  475.75  5193.9  474.48
  5416.4  476.72  5502.4  476.66  5612.8  478.44  5831.8  482.28  6171.8  490.66
#Mann= 5 ,-1 , 0
  4049.7      .1       0  4130.1     .05       0  4997.9     .03       0
  5003.9     .05       0  5612.8     .16       0
Bank Sta=4977.9,5028
XS Rating Curve= 0 ,0
Exp/Cntr=0.3,0.1

Type RM Length L Ch R = 1 ,101570  ,880,880,880
BEGIN DESCRIPTION:
SANDERS CREEK 137.0
END DESCRIPTION:
XS GIS Cut Line= 2
      3577721.75     10557365.52      3576259.08     10558485.31
#Sta/Elev= 30
  4303.7  481.11  4357.4  479.96  4386.5   477.9  4442.6  476.13  4529.7   475.1
    4615  472.74  4656.6  470.45  4685.6  470.83  4732.5  469.46    4750  468.13
  4770.8   470.1  4799.9  470.96  4864.3  470.58  4893.3  469.48    4935   470.2
  4970.7  469.56  4996.3   467.2  4999.1   466.7  5002.3   467.2  5021.1  467.43
  5042.9  469.88  5063.7  471.21  5157.2  473.85    5313  474.99  5371.1  473.51
  5441.8  475.21  5520.7  475.22  5676.6  476.88    5955  481.68  6145.8  486.16
#Mann= 4 ,-1 , 0
  4303.7      .1       0  4732.5     .05       0  4996.3     .03       0
  5002.3     .05       0
Bank Sta=4970.7,5042.9
XS Rating Curve= 0 ,0
Exp/Cntr=0.3,0.1

Type RM Length L Ch R = 1 ,100690  ,590,590,590
BEGIN DESCRIPTION:
SANDERS CREEK 136.0
END DESCRIPTION:
XS GIS Cut Line= 4
      3577899.65     10557048.68      3576784.25      10557148.5
      3576515.15      10557504.4      3576094.81     10558358.09
#Sta/Elev= 30
    4180   485.5  4217.7  484.13  4458.7  478.59  4599.2  474.72  4639.4  473.02
  4734.8  471.12  4759.9  471.21  4860.3  468.28    4939  467.06  4970.7  467.12
  4987.8  463.84  4990.5  463.34  4993.8  463.84  5020.9  465.95  5050.3  467.09
  5091.2  468.39  5131.3  467.71  5439.9  468.51    5596  470.07  5645.9  469.74
  5776.4  470.52  6031.6  475.97  6171.9  477.97  6188.8  478.75  6344.9   481.5
  6402.2  481.88  6590.1  480.74  6604.3   482.1  6621.2     485  6697.6  486.05
#Mann= 4 ,-1 , 0
    4180      .1       0  4734.8     .05       0  4987.8     .03       0
  4993.8     .05       0
Bank Sta=4970.7,5050.3
XS Rating Curve= 0 ,0
Exp/Cntr=0.3,0.1

Type RM Length L Ch R = 1 ,100100  ,598,598,598
BEGIN DESCRIPTION:
SANDERS CREEK 135.0
END DESCRIPTION:
XS GIS Cut Line= 4
      3578244.64     10556594.71      3576957.88     10556671.91
      3576608.33     10556709.73      3576083.13     10556892.03
#Sta/Elev= 30
  3631.3  497.07  4004.5  486.96  4134.7  484.24    4255  480.33  4336.3  478.93
  4356.1   478.5  4505.4  475.13  4575.5  474.73    4826  466.29  4936.2  467.19
  4956.4  466.75  4967.9  465.44  4993.6   459.7  4996.3   459.2  4999.6   459.7
  5016.7  463.98  5026.8  464.82  5097.2  466.51  5197.8  466.82  5288.5  468.56
  5319.6  470.02    5356  472.91  5405.6  471.42  5506.3  474.86  5625.5  477.37
  5630.8  478.26    5649  477.89  5744.3  479.77    5750  480.78  5827.9  480.78
#Mann= 5 ,-1 , 0
  3631.3     .05       0  4336.3      .1       0  4356.1     .05       0
  4993.6     .03       0  4999.6     .05       0
Bank Sta=4967.9,5026.8
XS Rating Curve= 0 ,0
Exp/Cntr=0.3,0.1

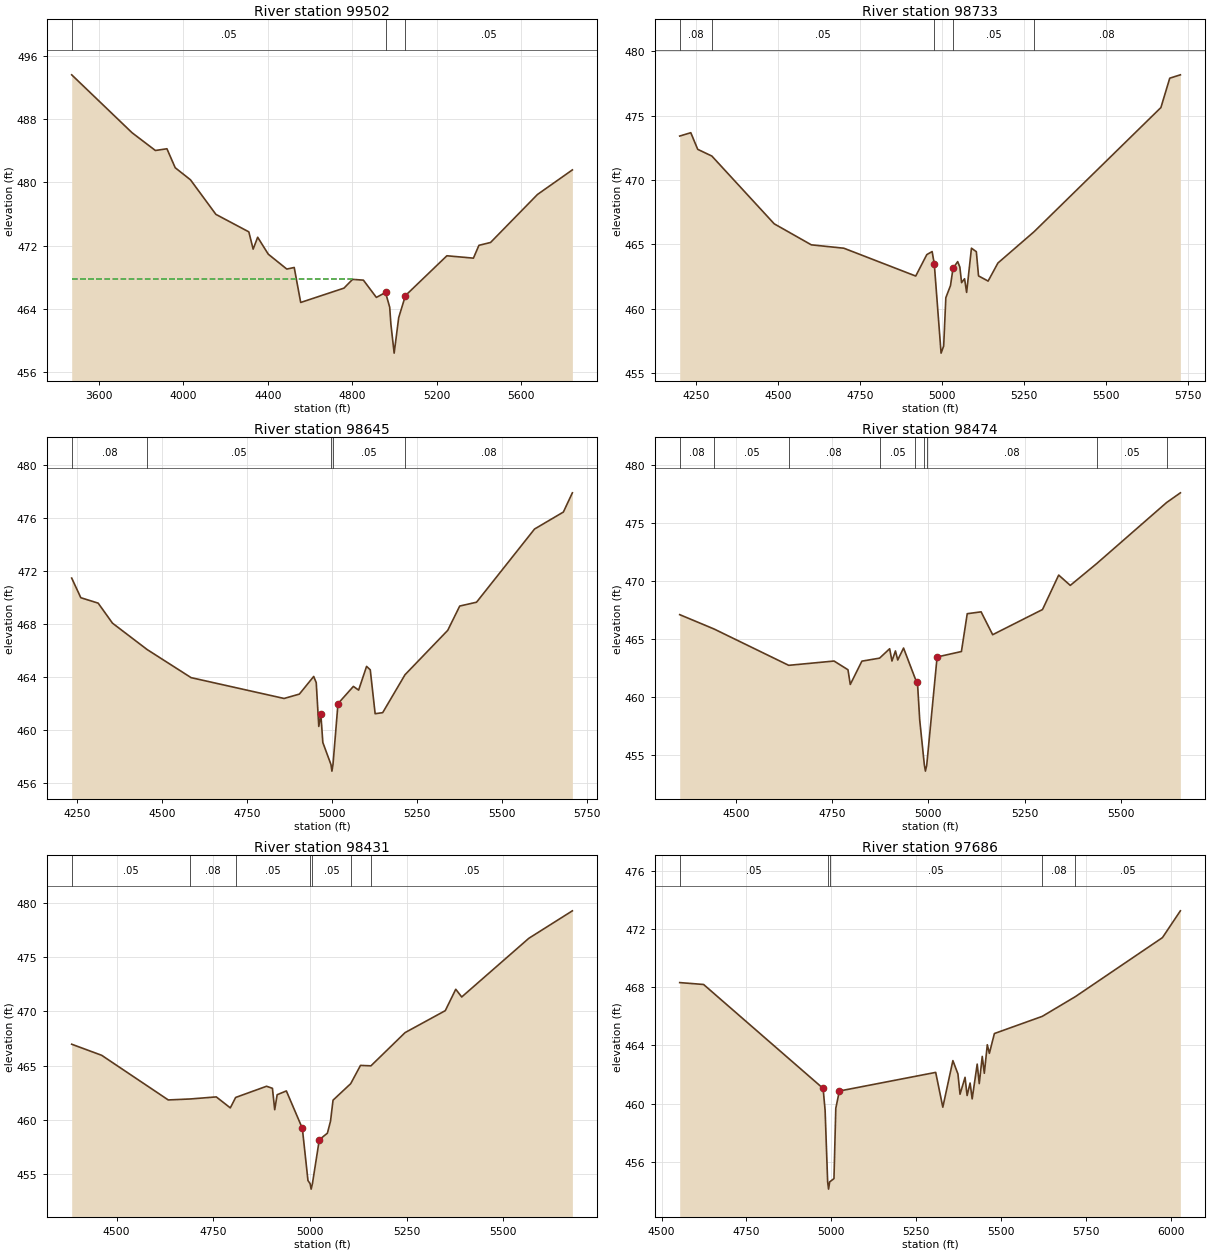
Type RM Length L Ch R = 1 ,99502   ,769,769,769
BEGIN DESCRIPTION:
SANDERS CREEK 134.0
END DESCRIPTION:
XS GIS Cut Line= 4
      3578051.51     10555882.89      3576625.69     10556188.89
      3576326.21      10556297.4       3575765.6     10556487.88
#Sta/Elev= 30
  3472.2  493.59    3758  486.27  3868.3  484.03  3922.8  484.25    3962  481.85
  4034.1  480.33  4154.5  475.96  4310.3  473.75  4330.7  471.57  4352.1  473.07
  4402.3  470.93    4490  469.05    4525  469.25  4555.7  464.83  4760.3  466.64
  4801.2  467.75  4852.3  467.65  4913.7  465.47  4957.1  466.09  4976.8  464.23
  4982.4   462.1  4997.9  458.43  5019.4  462.92  5051.3   465.7  5247.4  470.73
  5372.9  470.43    5399  472.05    5454  472.41  5675.8  478.47  5841.1  481.58
#Mann= 3 , 0 , 0
  3472.2     .05       0  4957.1     .03       0  5051.3     .05       0
#XS Ineff= 2 , 0
         4811.21  467.77
Permanent Ineff=
       F       F
Bank Sta=4957.1,5051.3
XS Rating Curve= 0 ,0
Exp/Cntr=0.3,0.1

Type RM Length L Ch R = 1 ,98733   ,88,88,88
BEGIN DESCRIPTION:
SANDERS CREEK 132.0
END DESCRIPTION:
XS GIS Cut Line= 4
      3576894.77     10554936.74      3576369.62     10555481.43
      3576300.17     10555561.72      3575927.02     10556110.61
#Sta/Elev= 30
  4201.2  473.41    4235  473.67  4256.1  472.38  4299.2  471.86  4489.4   466.6
  4602.6  464.97  4701.6  464.71  4920.8  462.55  4954.5  464.21  4970.8  464.45
  4977.4  463.49  4998.1  456.57    5006  457.12  5012.6  460.87  5026.8  461.81
  5034.5  463.15  5048.7  463.67  5055.3  463.25  5060.6  462.04  5069.7  462.34
    5076  461.28  5090.7  464.71  5105.6  464.44  5112.3  462.56  5141.5  462.16
  5171.4  463.56  5281.7  465.99  5668.3  475.62  5695.3   477.9  5727.7  478.16
#Mann= 5 ,-1 , 0
  4201.2     .08       0  4299.2     .05       0  4977.4     .03       0
  5034.5     .05       0  5281.7     .08       0
Bank Sta=4977.4,5034.5
XS Rating Curve= 0 ,0
Exp/Cntr=0.3,0.1

Type RM Length L Ch R = 1 ,98645   ,171,171,171
BEGIN DESCRIPTION:
SANDERS CREEK 132.1
END DESCRIPTION:
XS GIS Cut Line= 4
       3576690.8     10554832.55      3576280.64     10555448.87
      3576261.11     10555574.74      3575875.98      10556042.1
#Sta/Elev= 30
  4234.5  471.47  4261.3  469.99  4312.4  469.58  4354.5  468.07  4456.5  466.08
  4585.9  463.96  4859.5  462.39  4904.5  462.72  4946.6  464.05  4954.1  463.58
  4961.6  460.28  4967.7  461.19  4973.5  459.07  4997.4  457.41  5000.2  456.91
  5003.4  457.41  5018.1     462  5063.4   463.3  5078.8  463.02  5102.2  464.81
  5113.1  464.55  5127.4  461.24  5149.6  461.32  5215.3  464.18  5341.1  467.53
  5376.3  469.36  5425.8  469.65  5596.5  475.17  5681.3  476.45  5707.8   477.9
#Mann= 5 ,-1 , 0
  4234.5     .08       0  4456.5     .05       0  4997.4     .03       0
  5003.4     .05       0  5215.3     .08       0
Bank Sta=4967.7,5018.1
XS Rating Curve= 0 ,0
Exp/Cntr=0.3,0.1

Type RM Length L Ch R = 1 ,98474   ,43,43,43
BEGIN DESCRIPTION:
SANDERS CREEK 131.0
END DESCRIPTION:
XS GIS Cut Line= 3
      3576540.66     10554825.36       3576108.8     10555474.24
      3575820.72     10555907.44
#Sta/Elev= 30
  4354.4  467.12  4443.7  465.88  4637.4  462.75  4755.1  463.12  4791.2  462.37
  4797.2   461.1  4827.3  463.11  4873.3  463.37  4899.4  464.18  4905.4  463.12
  4914.4  463.99  4920.4  463.21  4935.5  464.24  4966.2  461.57  4971.5  461.31
  4977.5  458.02  4989.6  454.13  4992.3  453.63  4995.6  454.13  5022.6  463.47
  5085.7  463.94  5100.8   467.2  5136.8  467.36  5166.8  465.39  5296.2  467.56
  5338.2  470.53  5368.3  469.64  5436.5  471.51  5618.2  476.78  5654.1  477.62
#Mann= 9 ,-1 , 0
  4354.4     .08       0  4443.7     .05       0  4637.4     .08       0
  4873.3     .05       0  4966.2     .08       0  4989.6     .07       0
  4995.6     .08       0  5436.5     .05       0  5618.2     .08       0
Bank Sta=4971.5,5022.6
XS Rating Curve= 0 ,0
Exp/Cntr=0.3,0.1

Type RM Length L Ch R = 1 ,98431   ,745,745,745
BEGIN DESCRIPTION:
SANDERS CREEK 131.1
END DESCRIPTION:
XS GIS Cut Line= 4
       3576501.6     10554825.35      3576193.43      10555302.8
      3576037.18     10555417.82      3575756.08     10555869.74
#Sta/Elev= 30
  4383.9  466.96  4461.4  465.94  4633.6  461.83  4690.5  461.92  4757.7  462.11
    4794   461.1  4807.8  462.06  4887.7  463.09  4902.9   462.9  4908.8  460.93
  4915.1  462.31  4938.9  462.66  4980.2  459.22  4994.8  454.41  5000.3  454.12
    5003  453.62  5006.3  454.12  5024.1  458.17    5045  458.77  5053.1  459.88
  5059.6  461.81  5105.3  463.33  5130.6  465.01  5157.6  464.97  5245.9  468.03
  5349.8  470.05  5376.9  472.02  5392.3  471.31  5565.8  476.71  5678.4  479.24
#Mann= 7 ,-1 , 0
  4383.9     .05       0  4690.5     .08       0  4807.8     .05       0
  5000.3     .03       0  5006.3     .05       0  5105.3     .08       0
  5157.6     .05       0
Bank Sta=4980.2,5024.1
XS Rating Curve= 0 ,0
Exp/Cntr=0.3,0.1

Type RM Length L Ch R = 1 ,97686   ,233,233,233
BEGIN DESCRIPTION:
SANDERS CREEK 130.0
END DESCRIPTION:
XS GIS Cut Line= 4
      3576601.91     10554678.88      3576302.48     10554639.82
      3576033.38     10554726.63      3575526.34     10555459.02
#Sta/Elev= 30
  4553.5  468.31  4623.9  468.18  4976.1  461.04    4982  459.53  4989.5  454.62
  4992.2  454.12  4995.5  454.62  5008.1  454.84  5013.5  459.67    5024  460.86
  5307.9  462.14  5328.9  459.75  5358.6  462.95  5373.5  462.03  5379.6  460.64
  5394.4   461.8  5400.5  460.55  5409.3  461.41  5415.4  460.32  5430.2  462.71
  5436.3  461.37  5445.1  463.24  5451.2  462.08    5460  464.04  5466.1  463.45
  5480.9  464.81    5622  465.99  5719.9  467.35  5976.2   471.4    6029  473.24
#Mann= 5 ,-1 , 0
  4553.5     .05       0  4989.5     .03       0  4995.5     .05       0
    5622     .08       0  5719.9     .05       0
Bank Sta=4976.1,5024
XS Rating Curve= 0 ,0
Exp/Cntr=0.3,0.1