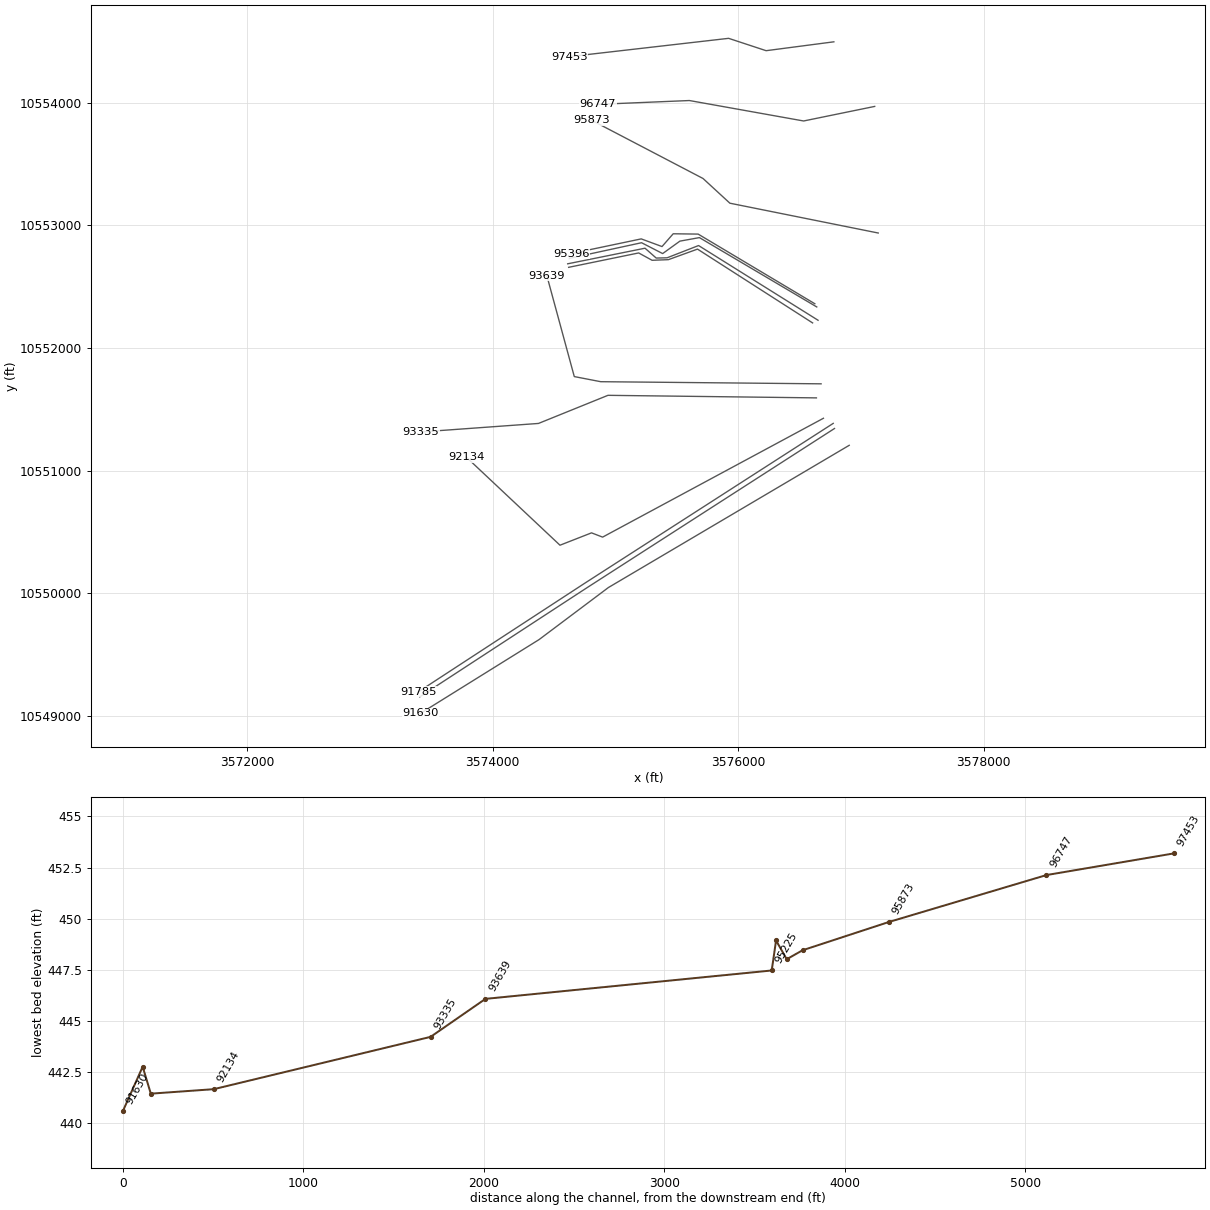
HEC-RAS study SANDERS CREEK.prj: SANDERS CREEK Base Level Engineering

--- SANDERS CREEK.g01 (geometry) --- (continued)

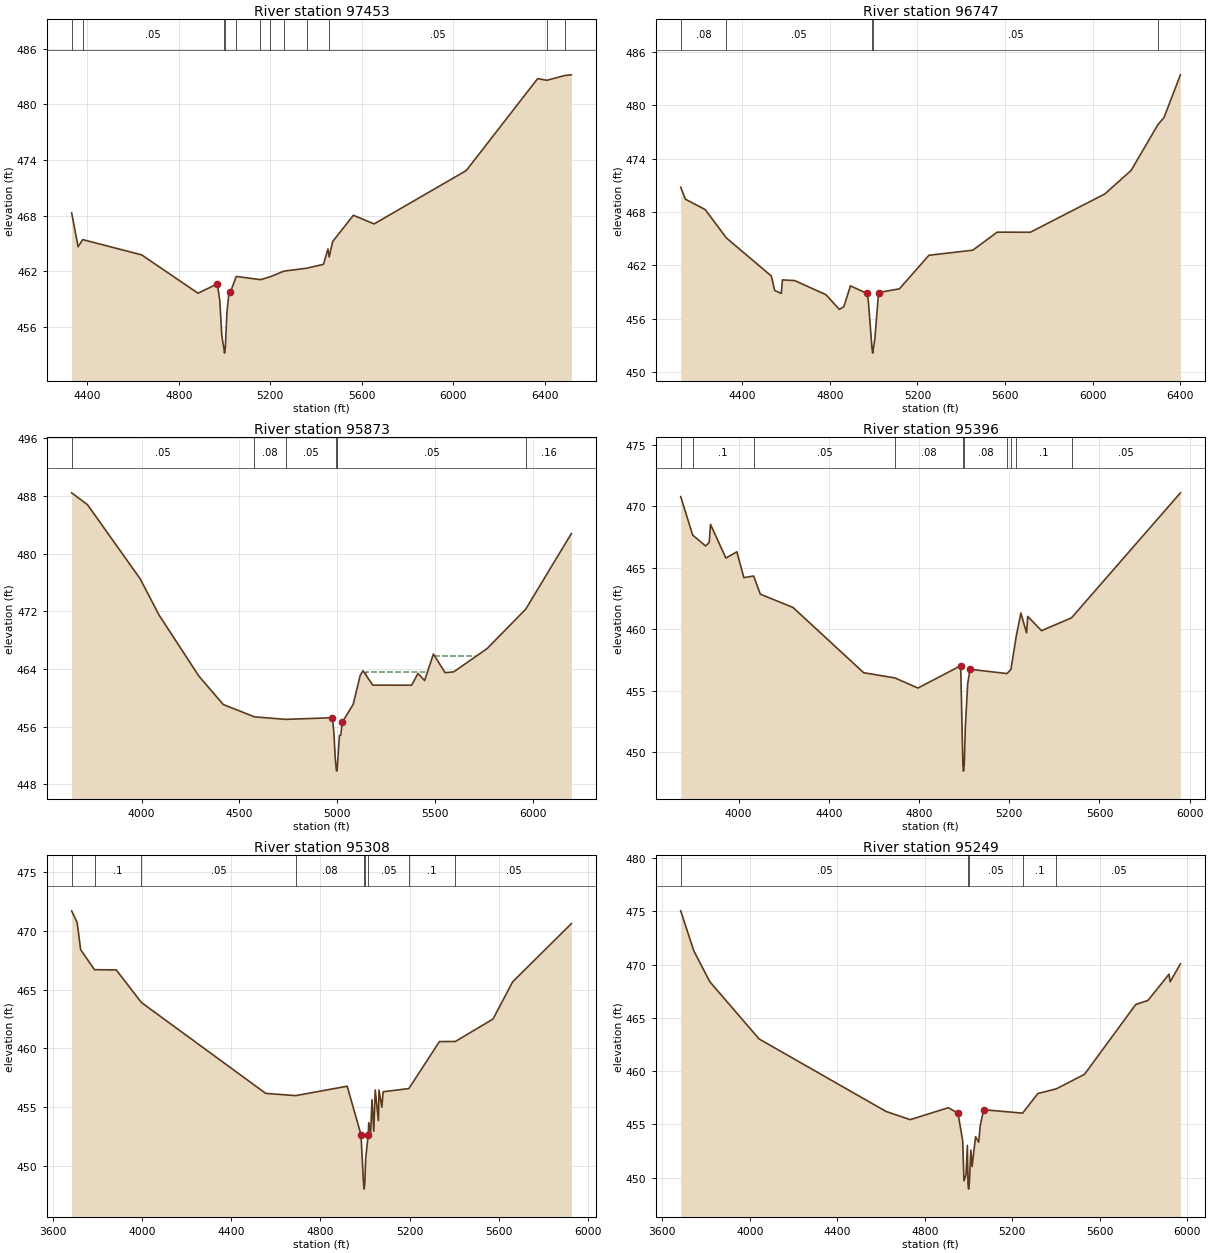
Type RM Length L Ch R = 1 ,97453   ,706,706,706
BEGIN DESCRIPTION:
SANDERS CREEK 129.0
END DESCRIPTION:
XS GIS Cut Line= 4
      3576780.18     10554496.45      3576228.41     10554424.14
      3575922.86     10554524.83      3574625.71     10554375.69
#Sta/Elev= 30
  4331.9  468.31  4360.2  464.65  4379.9  465.43  4637.9  463.78    4884  459.65
  4968.7  460.65  4979.3  458.86  4988.4  455.01  4997.3  453.69  5000.1  453.19
  5003.3  453.69  5010.8  457.67  5020.2  459.86  5025.4  459.76  5051.4  461.46
  5156.9  461.11  5199.5  461.42  5259.6  462.03  5358.3  462.34  5432.3  462.76
  5452.2  464.41  5457.4  463.56  5472.6  465.22  5563.2  468.05  5653.8  467.12
  6056.4  472.87  6368.4  482.78  6408.6   482.6  6487.6  483.12  6515.8  483.19
#Mann= 12 ,-1 , 0
  4331.9     .08       0  4379.9     .05       0  4997.3     .03       0
  5003.3     .05       0  5051.4     .08       0  5156.9      .1       0
  5199.5     .08       0  5259.6      .1       0  5358.3     .08       0
  5457.4     .05       0  6408.6     .16       0  6487.6     .05       0
Bank Sta=4968.7,5025.4
XS Rating Curve= 0 ,0
Exp/Cntr=0.3,0.1

Type RM Length L Ch R = 1 ,96747   ,874,874,874
BEGIN DESCRIPTION:
SANDERS CREEK 128.0
END DESCRIPTION:
XS GIS Cut Line= 4
       3577112.8     10553969.92      3576533.97     10553851.22
      3575603.41     10554017.89      3574857.11     10553986.64
#Sta/Elev= 30
  4118.2   470.8  4139.5  469.45  4230.1  468.28  4326.9  465.09  4532.5   460.8
  4547.6  459.18  4577.8  458.84  4582.9  460.37  4639.5  460.29  4782.1   458.7
    4843  457.05  4863.4  457.35  4893.8   459.7  4968.4  458.85  4975.1  458.12
  4992.4  452.63  4995.2  452.13  4998.4  452.63  5005.6   453.8  5022.1  458.95
  5117.3  459.36  5252.4  463.14  5452.6  463.71  5564.3  465.74  5715.8  465.73
  6056.1  470.04  6176.2  472.69  6298.9  477.85  6326.3  478.63  6401.4  483.44
#Mann= 5 ,-1 , 0
  4118.2     .08       0  4326.9     .05       0  4992.4     .03       0
  4998.4     .05       0  6298.9     .16       0
Bank Sta=4968.4,5022.1
XS Rating Curve= 0 ,0
Exp/Cntr=0.3,0.1

Type RM Length L Ch R = 1 ,95873   ,477,477,477
BEGIN DESCRIPTION:
SANDERS CREEK 126.0
END DESCRIPTION:
XS GIS Cut Line= 4
       3577141.6     10552938.02      3575933.27     10553181.08
      3575714.52     10553382.47      3574807.42     10553856.79
#Sta/Elev= 30
  3642.5  488.44  3723.6  486.79  3992.2  476.53  4088.8   471.5  4292.2  463.03
  4417.2  459.07  4576.7  457.36  4735.4  457.01  4975.2  457.24  4982.6  455.13
  4989.4  451.62  4993.8  450.33  4996.5  449.83  4999.8  450.33  5010.9  454.78
  5017.7  454.82  5025.1  456.61  5081.2   459.1    5117  463.12  5131.2  463.76
  5181.1  461.76  5379.7  461.75  5412.1  463.38    5446   462.4  5491.1  466.08
  5550.7  463.49  5594.8   463.6  5765.8  466.84  5962.5  472.29    6196  482.79
#Mann= 6 ,-1 , 0
  3642.5     .05       0  4576.7     .08       0  4735.4     .05       0
  4993.8     .03       0  4999.8     .05       0  5962.5     .16       0
#XS Ineff= 2 ,-1
  5144.9 5460.47  463.52 5500.94 5703.15  465.85
Permanent Ineff=
       F       F
Bank Sta=4975.2,5025.1
XS Rating Curve= 0 ,0
Exp/Cntr=0.3,0.1

Type RM Length L Ch R = 1 ,95396   ,88,88,88
BEGIN DESCRIPTION:
SANDERS CREEK 123.1
END DESCRIPTION:
XS GIS Cut Line= 6
      3576625.19     10552361.56       3575674.7     10552929.25
      3575471.58     10552931.86      3575380.43     10552827.69
      3575211.16     10552890.19      3574640.84      10552770.4
#Sta/Elev= 30
  3743.3  470.79  3796.4  467.66  3854.1  466.77  3869.7  467.07  3875.5  468.53
  3943.7  465.79  3992.3   466.3  4023.4   464.2  4066.5  464.33  4096.3  462.85
  4241.3  461.77  4554.6  456.46  4693.9  456.03  4795.2  455.21  4984.8  457.03
  4994.5  448.95  4997.2  448.45  5000.5  448.95  5005.4  452.04  5015.7  455.54
    5026  456.74  5189.8  456.39  5207.5  456.72  5231.8  459.51  5251.7  461.32
  5276.8   459.7  5282.1  461.04  5343.3  459.88  5476.4  460.93  5959.1   471.1
#Mann= 10 ,-1 , 0
  3743.3     .05       0  3796.4      .1       0  4066.5     .05       0
  4693.9     .08       0  4994.5     .07       0  5000.5     .08       0
  5189.8     .05       0  5207.5     .08       0  5231.8      .1       0
  5476.4     .05       0
Bank Sta=4984.8,5026
XS Rating Curve= 0 ,0
Exp/Cntr=0.3,0.1

Type RM Length L Ch R = 1 ,95308   ,59,59,59
BEGIN DESCRIPTION:
SANDERS CREEK 123.0
END DESCRIPTION:
XS GIS Cut Line= 6
      3576640.86     10552335.49      3575685.12     10552900.61
      3575526.27     10552871.96      3575385.64      10552770.4
      3575213.77     10552858.94      3574626.16     10552731.54
#Sta/Elev= 30
    3683   471.7  3707.8   470.7  3723.4  468.39  3785.6  466.69  3883.3  466.67
    3996   463.9  4554.2  456.16  4689.3  455.97    4920  456.77  4981.9  452.65
  4993.2  448.51    4996  448.01  4999.2  448.51  5002.7  450.54  5014.2  452.66
    5017  453.67    5025   452.7  5031.4  455.63  5039.3  452.93  5045.8  456.45
  5060.2  453.85  5062.8  456.45  5075.6  454.98  5081.4   456.3  5196.9  456.57
    5334  460.57  5405.8  460.58  5574.7  462.49  5662.9  465.66  5926.4  470.61
#Mann= 9 ,-1 , 0
    3683     .05       0  3785.6      .1       0    3996     .05       0
  4689.3     .08       0  4993.2     .07       0  4999.2     .08       0
  5014.2     .05       0  5196.9      .1       0  5405.8     .05       0
Bank Sta=4981.9,5014.2
XS Rating Curve= 0 ,0
Exp/Cntr=0.3,0.1

Type RM Length L Ch R = 1 ,95249   ,24,24,24
BEGIN DESCRIPTION:
SANDERS CREEK 124.0
END DESCRIPTION:
XS GIS Cut Line= 6
      3576651.45     10552227.01      3575678.18     10552835.94
       3575422.1     10552736.11      3575333.12     10552733.94
      3575241.98     10552814.23      3574612.18     10552687.06
#Sta/Elev= 30
  3683.9  475.04  3743.9  471.28    3817  468.39  4042.2  463.02  4623.4  456.21
    4733  455.45  4907.7  456.57  4951.5  456.05    4973  453.49  4978.8  449.71
  4988.3  450.28  4994.5  453.04  4997.3  449.43    5000  448.93  5003.3  449.43
  5010.3   452.6    5016  451.05  5031.8  453.85  5046.1  453.33  5053.3  454.89
    5069  456.38  5246.8  456.06  5316.8   457.9  5401.2  458.34  5529.9   459.7
    5764  466.25  5819.8  466.63  5916.3  469.09  5921.4  468.38  5968.5  470.07
#Mann= 5 ,-1 , 0
  3683.9     .05       0  4997.3     .03       0  5003.3     .05       0
  5246.8      .1       0  5401.2     .05       0
Bank Sta=4951.5,5069
XS Rating Curve= 0 ,0
Exp/Cntr=0.3,0.1

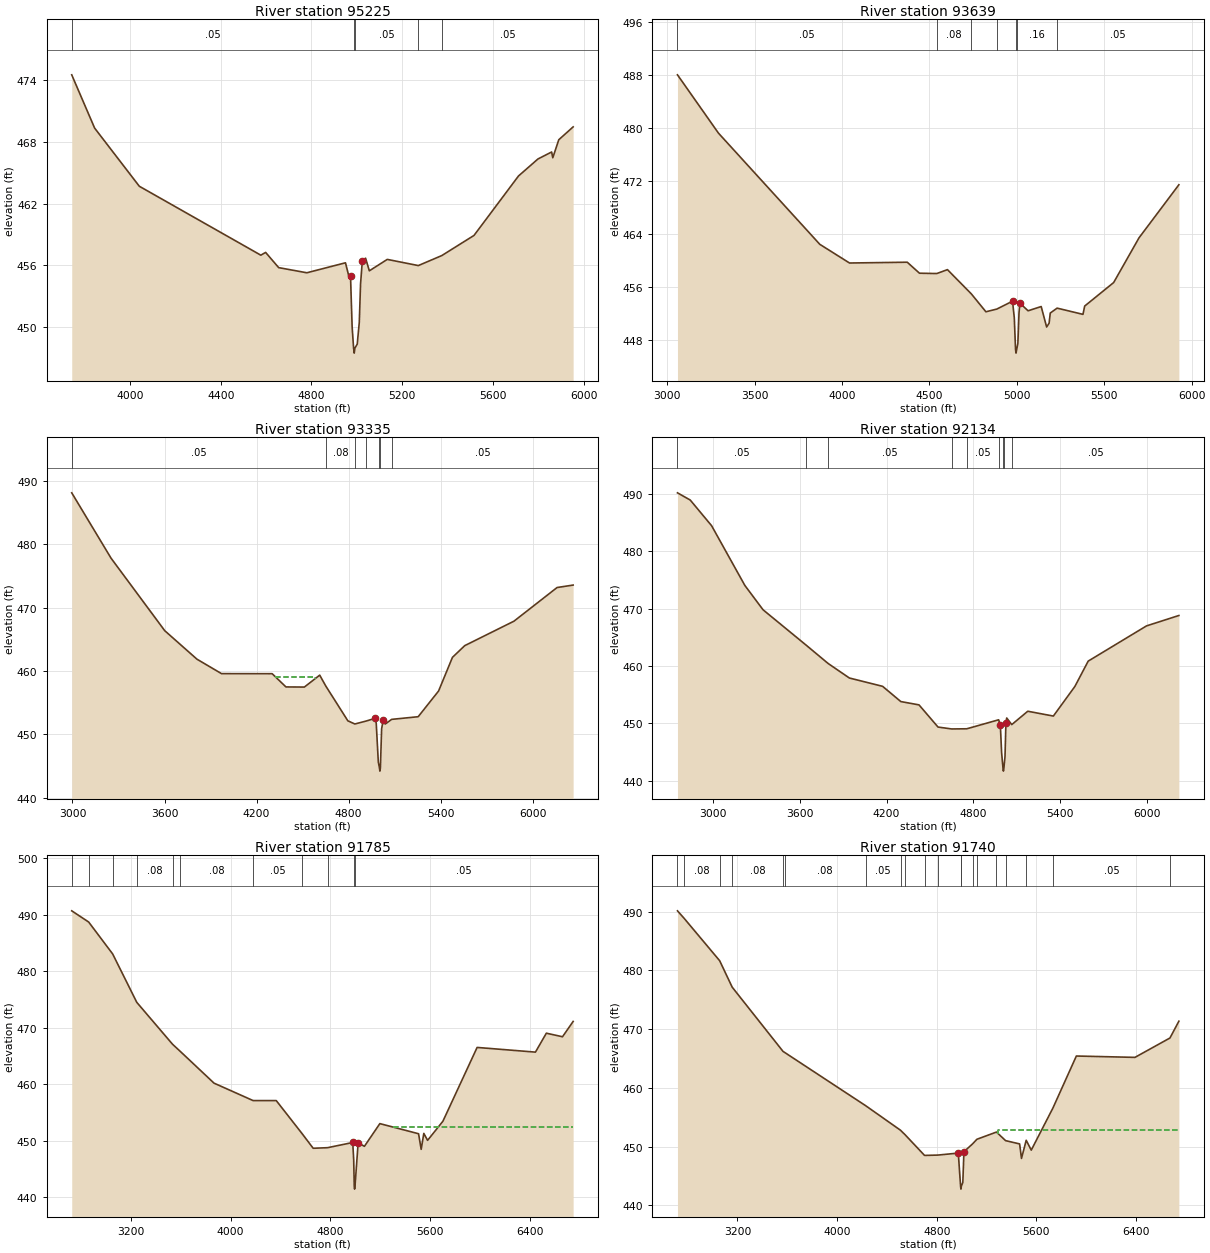
Type RM Length L Ch R = 1 ,95225   ,1586,1586,1586
BEGIN DESCRIPTION:
SANDERS CREEK 124.1
END DESCRIPTION:
XS GIS Cut Line= 6
      3576607.02     10552205.28      3575669.49     10552806.86
      3575432.52     10552720.92       3575299.7     10552715.71
      3575190.33     10552775.61      3574620.06     10552658.43
#Sta/Elev= 30
  3743.3  474.51  3844.3  469.33  4041.2  463.68    4577  456.98  4598.1  457.25
  4655.6  455.77  4779.8  455.27  4950.1  456.24  4966.7  454.79  4972.3  454.98
  4979.4  450.05  4985.8  447.96  4988.6  447.46  4991.8  447.96  5001.9  448.33
    5011  450.45  5016.6  454.19  5024.4  456.44  5038.7  456.69  5055.3  455.46
  5134.4  456.57  5271.2  455.97  5374.6  456.94  5516.7   458.9    5713  464.68
  5798.6  466.33    5859  467.01  5864.1  466.45  5890.5   468.2  5953.8  469.45
#Mann= 5 ,-1 , 0
  3743.3     .05       0  4985.8     .03       0  4991.8     .05       0
  5271.2      .1       0  5374.6     .05       0
Bank Sta=4972.3,5024.4
XS Rating Curve= 0 ,0
Exp/Cntr=0.3,0.1

Type RM Length L Ch R = 1 ,93639   ,304,304,304
BEGIN DESCRIPTION:
SANDERS CREEK 121.0
END DESCRIPTION:
XS GIS Cut Line= 4
      3576676.31     10551708.86      3574881.19     10551726.22
      3574665.91     10551767.89       3574442.1     10552591.65
#Sta/Elev= 30
  3059.1  488.07  3293.3  479.28  3873.3  462.49  4043.3  459.67  4373.4  459.79
  4443.4  458.13  4542.5  458.08  4603.4  458.67  4740.4     455  4823.4  452.31
    4886  452.72  4975.6  453.91  4985.8   451.4    4993  446.57  4995.7  446.07
    4999  446.57  5006.2  447.53  5012.8  452.18  5017.9  453.61  5064.6  452.46
  5139.6   453.1  5170.7  450.01  5184.9  450.59  5191.5  452.12  5230.8  452.86
  5378.7  451.92  5388.3  453.17  5554.1  456.72  5699.2  463.47  5927.2  471.48
#Mann= 7 ,-1 , 0
  3059.1     .05       0  4542.5     .08       0  4740.4      .1       0
    4886     .16       0    4993     .07       0    4999     .16       0
  5230.8     .05       0
Bank Sta=4975.6,5017.9
XS Rating Curve= 0 ,0
Exp/Cntr=0.3,0.1

Type RM Length L Ch R = 1 ,93335   ,1201,1201,1201
BEGIN DESCRIPTION:
SANDERS CREEK 120.0
END DESCRIPTION:
XS GIS Cut Line= 4
      3576638.17     10551594.27      3574940.22     10551615.11
      3574374.25     10551385.94      3573417.54     10551316.61
#Sta/Elev= 30
  2995.3  488.14  3251.4  477.83  3601.4  466.38  3811.4  461.88  3971.4   459.6
  4301.5  459.59  4391.5   457.5  4511.5  457.48  4611.5  459.36  4651.4  457.63
  4794.9  452.15  4840.6  451.65  4916.2  452.13  4971.8  452.54  4979.8  451.78
  4993.4  445.66  5000.9  444.71  5003.7  444.21  5006.9  444.71    5015   450.9
  5025.8  452.33  5038.8  451.65  5080.4  452.38  5253.3   452.8  5386.3  456.86
  5476.6  462.17  5556.8  464.02  5877.6  467.88  6158.4  473.19  6263.2  473.58
#Mann= 7 ,-1 , 0
  2995.3     .05       0  4651.4     .08       0  4840.6     .16       0
  4916.2     .08       0  5000.9     .07       0  5006.9     .08       0
  5080.4     .05       0
#XS Ineff= 1 ,-1
 4319.64 4581.79  459.14
Permanent Ineff=
       F
Bank Sta=4971.8,5025.8
XS Rating Curve= 0 ,0
Exp/Cntr=0.3,0.1

Type RM Length L Ch R = 1 ,92134   ,349,349,349
BEGIN DESCRIPTION:
SANDERS CREEK 118.0
END DESCRIPTION:
XS GIS Cut Line= 5
      3576695.28     10551428.18      3574896.63     10550459.41
      3574806.35     10550494.13      3574549.41     10550393.44
      3573786.33     10551111.42
#Sta/Elev= 30
  2755.4  490.22  2843.6  488.96  2991.2  484.48  3220.8  474.06  3346.5  469.81
  3643.5  463.65  3795.9  460.44  3942.8   457.9  4172.3  456.45  4298.1  453.79
  4423.8  453.21  4555.2  449.34  4649.4  449.01    4754  449.04  4973.9  450.61
  4985.6   449.7  4994.4  444.85    5004  442.15  5006.8  441.65    5010  442.15
  5017.8  444.19  5024.2  450.12  5029.6  450.92  5064.5  449.77    5175   452.1
  5351.8  451.26  5500.3  456.42  5592.5  460.85  5995.5     467  6218.8  468.81
#Mann= 9 ,-1 , 0
  2755.4     .05       0  3643.5     .08       0  3795.9     .05       0
  4649.4      .1       0    4754     .05       0  4973.9     .16       0
    5004     .07       0    5010     .16       0  5064.5     .05       0
Bank Sta=4985.6,5024.2
XS Rating Curve= 0 ,0
Exp/Cntr=0.3,0.1

Type RM Length L Ch R = 1 ,91785   ,45,45,45
BEGIN DESCRIPTION:
SANDERS CREEK 119.1
END DESCRIPTION:
XS GIS Cut Line= 3
       3576775.1     10551386.49      3574757.74     10550087.88
      3573396.83     10549199.13
#Sta/Elev= 30
  2724.6  490.67  2860.5  488.69  3053.2  483.04  3246.6  474.48  3533.9  467.06
  3591.5  465.89  3866.8  460.18  4180.1   457.1    4366   457.1  4573.2  451.26
  4662.5  448.66  4777.6  448.76  4980.1  449.68  4987.8  446.64  4992.2  441.93
    4995  441.43  4998.2  441.93  5023.5  449.65  5073.8     449  5197.7  453.02
  5508.4  451.23  5529.5  448.47  5550.6  451.29  5580.8  450.06  5703.8  453.44
  5978.5   466.5  6446.6  465.67  6534.1  469.02  6663.8  468.39  6749.2   471.1
#Mann= 11 ,-1 , 0
  2724.6     .05       0  2860.5     .08       0  3053.2     .05       0
  3246.6     .08       0  3533.9     .05       0  3591.5     .08       0
  4180.1     .05       0  4573.2      .1       0  4777.6     .05       0
  4992.2     .03       0  4998.2     .05       0
#XS Ineff= 2 , 0
                         5306.17           452.5
Permanent Ineff=
       F       F
Bank Sta=4980.1,5023.5
XS Rating Curve= 0 ,0
Exp/Cntr=0.3,0.1

Type RM Length L Ch R = 1 ,91740   ,110,110,110
BEGIN DESCRIPTION:
SANDERS CREEK 119.0
END DESCRIPTION:
XS GIS Cut Line= 3
      3576785.52     10551344.83      3574768.16     10550046.22
      3573407.09     10549157.36
#Sta/Elev= 30
  2718.7  490.15  2771.9  488.88  3057.5  481.65  3157.9  477.15  3566.3   466.2
  3578.3  466.04  4228.7  456.97  4509.1  452.78  4548.7  451.95  4702.1  448.49
  4810.2  448.55  4972.9  448.89  4991.3  443.25    4994  442.75  4997.3  443.25
  5009.2  443.89  5018.1  449.12  5088.1  450.47  5122.2  451.24  5279.3  452.47
  5352.5  451.01  5465.1  450.45  5480.2  447.98    5518  451.07  5558.6  449.39
  5732.4  456.56  5920.6  465.42  6391.1  465.19  6671.8  468.49  6743.5  471.35
#Mann= 20 ,-1 , 0
  2718.7     .05       0  2771.9     .08       0  3057.5     .05       0
  3157.9     .08       0  3566.3     .05       0  3578.3     .08       0
  4228.7     .05       0  4509.1     .08       0  4548.7      .1       0
  4702.1     .08       0  4810.2     .05       0  4991.3     .03       0
  4997.3     .05       0  5088.1     .08       0  5122.2     .05       0
  5279.3     .08       0  5352.5     .05       0    5518     .08       0
  5732.4     .05       0  6671.8     .08       0
#XS Ineff= 2 , 0
                         5292.33          452.75
Permanent Ineff=
       F       F
Bank Sta=4972.9,5018.1
XS Rating Curve= 0 ,0
Exp/Cntr=0.3,0.1

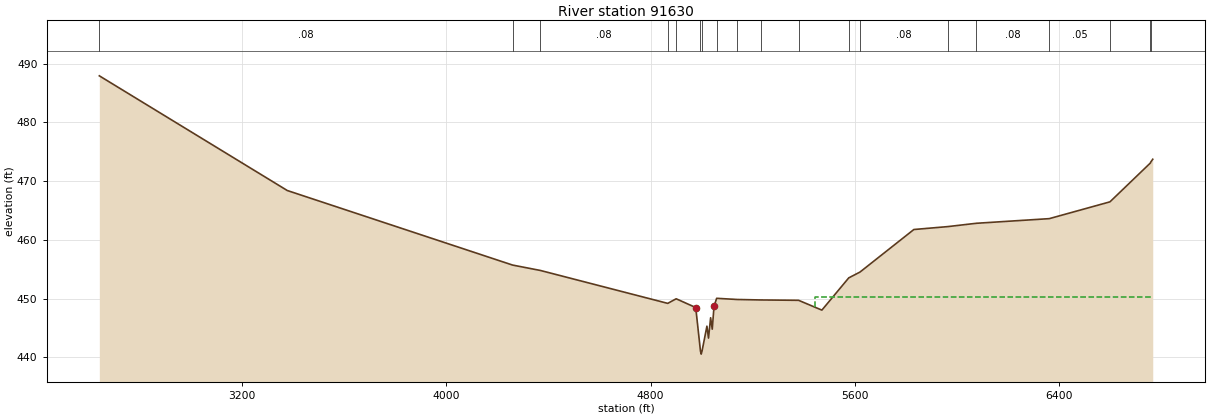
Type RM Length L Ch R = 1 ,91630   ,154,154,154
BEGIN DESCRIPTION:
SANDERS CREEK 118.1
END DESCRIPTION:
XS GIS Cut Line= 4
      3576905.32     10551207.68      3574944.37     10550048.82
      3574379.27     10549624.34       3573413.1     10549022.77
#Sta/Elev= 30
  2642.3  487.94  3377.8  468.42  4259.5  455.73  4368.6  454.81  4866.8  449.21
  4899.9  449.99  4976.4   448.5    4995  441.07  4997.7  440.57    5001  441.07
  5020.2  445.33  5026.4   443.3  5034.7  446.76    5041  444.82    5048  448.69
  5058.3  450.07  5138.8  449.87  5230.6  449.79    5379  449.73  5470.1  448.06
  5575.3  453.55  5619.3  454.54  5830.1  461.78  5963.8  462.28  6074.5  462.84
    6360  463.63  6597.5  466.49  6756.2  473.12  6756.8  473.23    6765  473.74
#Mann= 19 ,-1 , 0
  2642.3     .08       0  4259.5      .1       0  4368.6     .08       0
  4866.8     .05       0  4899.9     .08       0    4995     .07       0
    5001     .08       0  5058.3     .05       0  5138.8     .08       0
  5230.6     .05       0    5379     .08       0  5575.3     .05       0
  5619.3     .08       0  5963.8     .05       0  6074.5     .08       0
    6360     .05       0  6597.5     .08       0  6756.2     .15       0
  6756.8     .05       0
#XS Ineff= 2 , 0
                         5441.75          450.22
Permanent Ineff=
       F       F
Bank Sta=4976.4,5048
XS Rating Curve= 0 ,0
Exp/Cntr=0.3,0.1