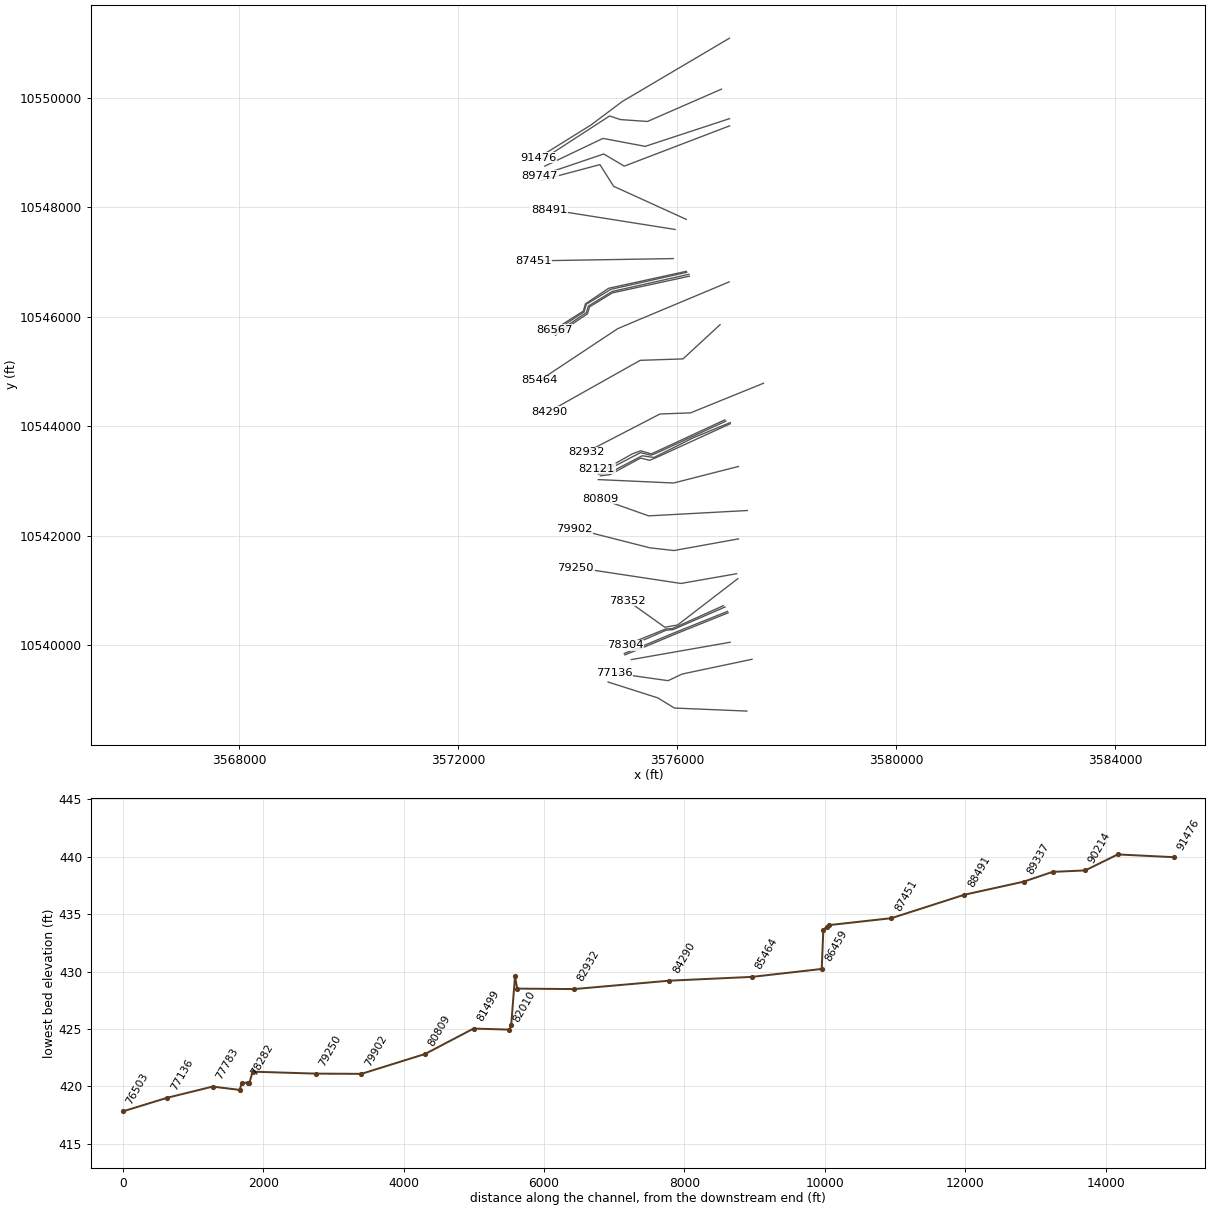
HEC-RAS study SANDERS CREEK.prj: SANDERS CREEK Base Level Engineering

--- SANDERS CREEK.g01 (geometry) --- (continued)

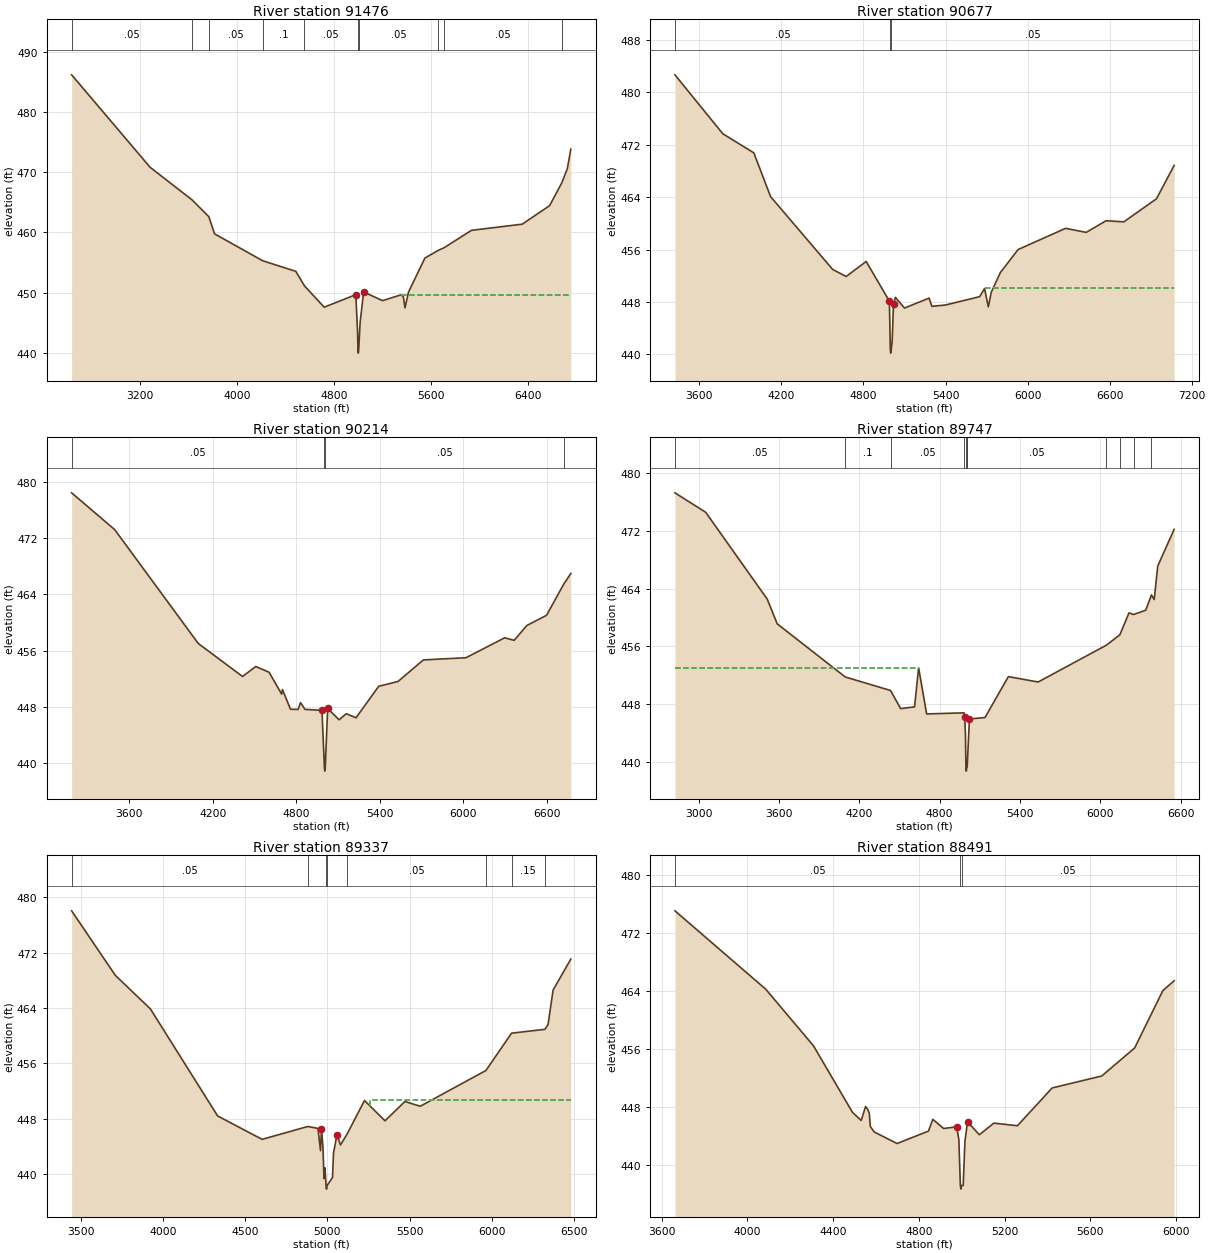
Type RM Length L Ch R = 1 ,91476   ,799,799,799
BEGIN DESCRIPTION:
SANDERS CREEK 118.2
END DESCRIPTION:
XS GIS Cut Line= 4
      3576952.23     10551087.91      3574991.25     10549929.03
      3574426.14     10549504.55        3573460.     10548902.99
#Sta/Elev= 30
  2632.6  486.18  3280.6  470.83  3627.4  465.41  3765.7  462.62  3813.1  459.77
  4209.7  455.31  4484.1  453.54  4555.3  451.14  4718.2  447.59  4979.6  449.67
  4994.1  443.52  4997.4  440.46  5000.1  439.96  5003.4  440.46    5015  445.02
  5044.1  450.12  5200.3  448.68  5350.3  449.62  5372.1  449.38  5385.7  447.48
  5414.9  450.11  5550.3  455.75  5658.5  457.01  5708.5  457.46  5934.5  460.35
  6354.6  461.38  6580.1  464.46  6681.9  468.29  6726.4  470.59  6755.3  473.84
#Mann= 10 ,-1 , 0
  2632.6     .05       0  3627.4     .08       0  3765.7     .05       0
  4209.7      .1       0  4555.3     .05       0  4997.4     .03       0
  5003.4     .05       0  5658.5     .08       0  5708.5     .05       0
  6681.9     .15       0
#XS Ineff= 2 , 0
                         5349.94          449.65
Permanent Ineff=
       F       F
Bank Sta=4979.6,5044.1
XS Rating Curve= 0 ,0
Exp/Cntr=0.3,0.1

Type RM Length L Ch R = 1 ,90677   ,463,463,463
BEGIN DESCRIPTION:
SANDERS CREEK 117.0
END DESCRIPTION:
XS GIS Cut Line= 5
      3576806.34     10550157.32      3575455.66     10549567.05
       3574962.6     10549601.77      3574764.68     10549667.74
       3573529.3     10548866.13
#Sta/Elev= 30
  3421.9  482.68  3771.7  473.69  3998.7  470.77  4121.2  464.09  4575.1  452.97
  4674.1   451.9    4820  454.19  4989.7  448.14  4996.7   440.7  4999.5   440.2
  5002.7   440.7  5009.8  441.91  5019.8   447.7  5033.7  448.71    5100  447.08
  5280.4   448.6  5300.5  447.34  5400.8  447.55  5649.6  448.82  5685.4  450.07
  5713.1  447.26  5734.2  449.47  5800.8  452.49  5930.6  456.01    6278  459.25
    6429  458.63    6574  460.41  6703.9  460.24  6942.5  463.76  7071.5  468.85
#Mann= 3 ,-1 , 0
  3421.9     .05       0  4996.7     .03       0  5002.7     .05       0
#XS Ineff= 2 , 0
                         5685.27          450.08
Permanent Ineff=
       F       F
Bank Sta=4989.7,5019.8
XS Rating Curve= 0 ,0
Exp/Cntr=0.3,0.1

Type RM Length L Ch R = 1 ,90214   ,467,467,467
BEGIN DESCRIPTION:
SANDERS CREEK 116.0
END DESCRIPTION:
XS GIS Cut Line= 4
      3576955.69     10549619.15      3575413.99     10549112.19
      3574643.16     10549258.02      3573580.62     10548751.06
#Sta/Elev= 30
  3187.1  478.47  3496.2  473.23  4096.5     457  4414.4   452.3  4509.8  453.72
  4605.2   452.9  4695.3  449.78  4700.6  450.44  4758.9  447.63  4813.5   447.6
  4830.6  448.58  4862.8  447.61  4984.9  447.47  5002.3  439.31  5005.1  438.81
  5008.3  439.31  5025.7  447.74  5107.6  446.13  5159.9  446.99  5229.2  446.41
    5392   450.9  5531.4  451.59  5712.9  454.66    6019  454.97  6296.8  457.81
  6364.9  457.45  6455.7  459.56  6597.4  461.02  6719.5  465.41  6771.8  466.98
#Mann= 4 ,-1 , 0
  3187.1     .05       0  5002.3     .03       0  5008.3     .05       0
  6719.5     .15       0
Bank Sta=4984.9,5025.7
XS Rating Curve= 0 ,0
Exp/Cntr=0.3,0.1

Type RM Length L Ch R = 1 ,89747   ,410,410,410
BEGIN DESCRIPTION:
SANDERS CREEK 116.1
END DESCRIPTION:
XS GIS Cut Line= 4
      3576955.68      10549487.2      3575032.05     10548751.08
      3574657.05      10548973.3      3573490.34     10548577.45
#Sta/Elev= 30
  2823.8  477.31  3053.5  474.61  3512.9  462.56  3587.8  459.12  4095.4  451.75
  4434.2  449.87  4509.1  447.36  4613.2   447.6  4643.3  453.04  4703.4  446.62
  4982.9  446.77  4987.3  446.25  4993.1   443.8  4996.6  439.18  4999.4  438.68
  5002.6  439.18    5006  439.24  5022.9  445.92  5139.1  446.12  5313.5   451.8
  5535.8  451.05  6046.2  456.17  6146.1   457.6  6214.2  460.65  6248.2  460.42
  6339.8  461.02  6381.8  463.13  6402.6   462.5  6428.8  467.14  6551.4  472.24
#Mann= 11 ,-1 , 0
  2823.8     .05       0  4095.4      .1       0  4434.2     .05       0
  4982.9      .1       0  4996.6     .07       0  5002.6      .1       0
    5006     .05       0  6046.2      .1       0  6146.1     .05       0
  6248.2     .15       0  6381.8     .05       0
#XS Ineff= 2 , 0
         4643.05  453.06
Permanent Ineff=
       F       F
Bank Sta=4987.3,5022.9
XS Rating Curve= 0 ,0
Exp/Cntr=0.3,0.1

Type RM Length L Ch R = 1 ,89337   ,846,846,846
BEGIN DESCRIPTION:
SANDERS CREEK 115.0
END DESCRIPTION:
XS GIS Cut Line= 4
      3576164.02     10547778.84       3574837.6     10548383.02
       3574587.6     10548778.86      3573518.17     10548494.14
#Sta/Elev= 30
  3446.1  478.03  3711.9   468.7  3924.7  463.86  4333.1   448.4  4603.1  445.02
  4881.3  446.88  4942.7   446.6    4958  443.38  4963.9  446.56    4973   443.8
  4979.2  439.35  4985.1  440.91  4991.5  438.33  4994.2  437.83  4997.5  438.33
  5030.9  439.51  5036.8  443.05    5058  445.66  5079.4  444.21  5118.7  445.75
  5225.1  450.63  5349.8   447.7  5470.6  450.49  5563.8   449.8  5962.9  454.97
  6118.6  460.36    6321  460.91  6339.9  461.59  6370.9  466.59  6478.5  471.06
#Mann= 8 ,-1 , 0
  3446.1     .05       0  4881.3      .1       0  4991.5     .07       0
  4997.5      .1       0  5118.7     .05       0  5962.9      .1       0
  6118.6     .15       0    6321     .05       0
#XS Ineff= 2 , 0
                         5261.08          450.65
Permanent Ineff=
       F       F
Bank Sta=4963.9,5058
XS Rating Curve= 0 ,0
Exp/Cntr=0.3,0.1

Type RM Length L Ch R = 1 ,88491   ,1040,1040,1040
BEGIN DESCRIPTION:
SANDERS CREEK 114.0
END DESCRIPTION:
XS GIS Cut Line= 2
      3575960.35     10547594.35      3573660.06     10547958.93
#Sta/Elev= 30
  3661.7  475.06  4085.2  464.26  4307.9  456.46  4490.2  447.27  4530.7  446.16
  4550.9  448.07    4561  447.71  4568.4  447.17  4573.4  445.32  4591.4  444.57
  4698.1  442.98  4844.5  444.69  4864.8  446.31  4915.4  445.05  4976.1  445.28
  4986.3  443.52  4993.4  437.19  4996.1  436.69  4999.4  437.19  5006.5   437.2
  5014.7   443.3  5026.8  445.95  5082.1  444.19  5149.5  445.79  5259.6  445.43
  5421.6  450.64  5653.1  452.29  5806.4  456.15    5938  464.06  5990.7  465.42
#Mann= 3 ,-1 , 0
  3661.7     .05       0  4993.4     .03       0  4999.4     .05       0
Bank Sta=4976.1,5026.8
XS Rating Curve= 0 ,0
Exp/Cntr=0.3,0.1

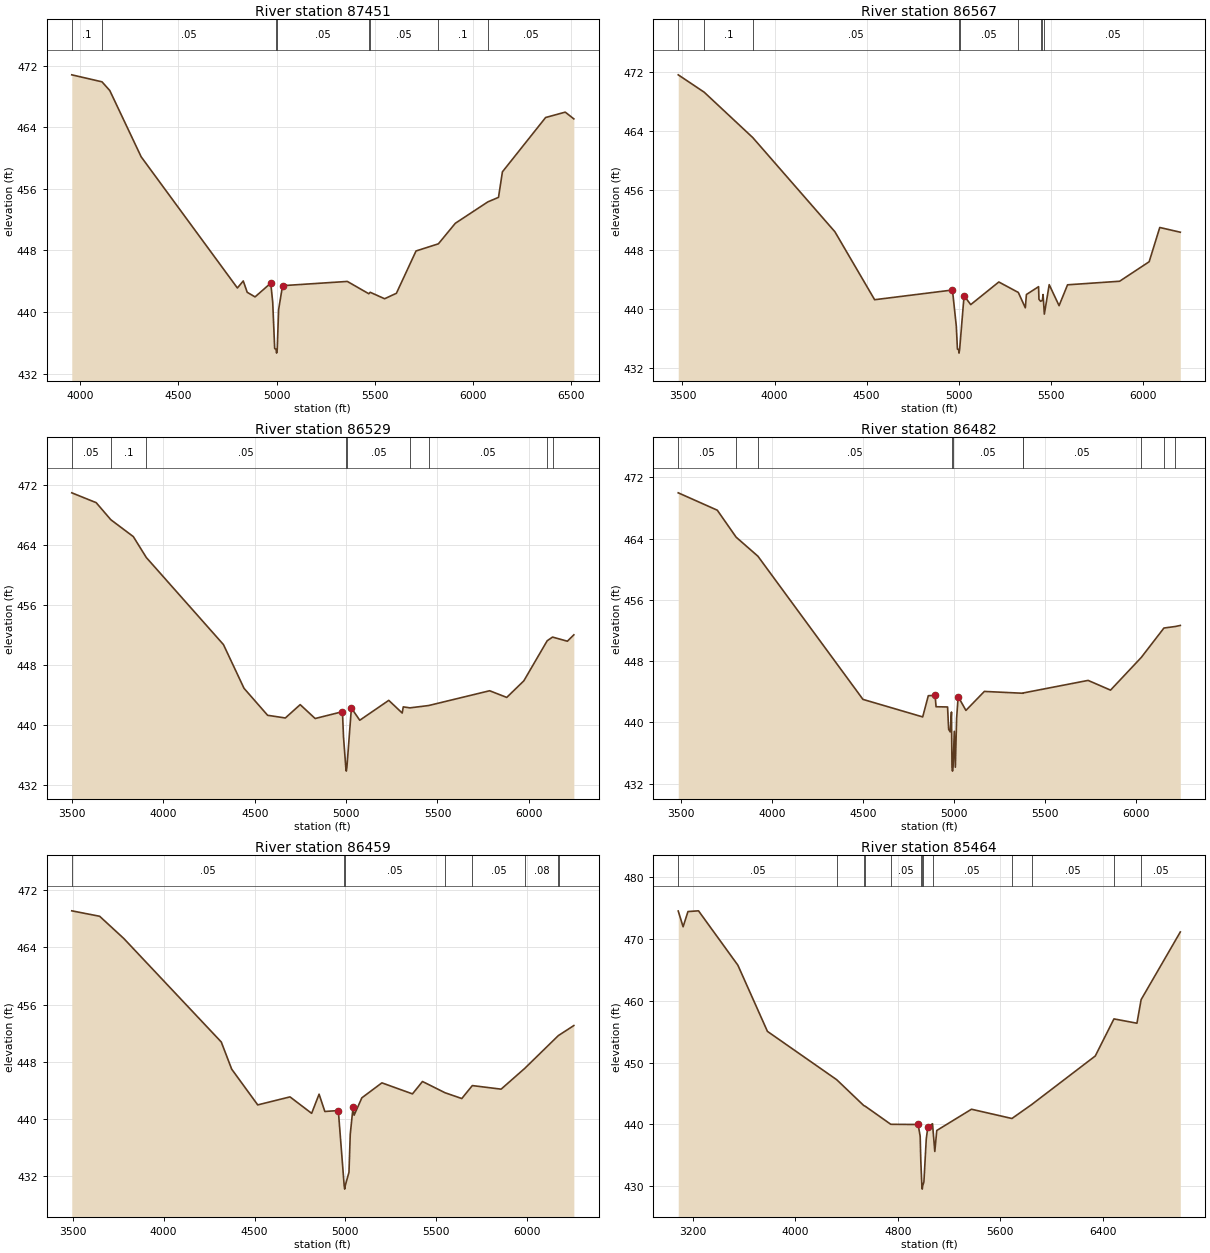
Type RM Length L Ch R = 1 ,87451   ,884,884,884
BEGIN DESCRIPTION:
SANDERS CREEK 113.0
END DESCRIPTION:
XS GIS Cut Line= 2
       3575925.7     10547062.23      3573368.34     10547020.56
#Sta/Elev= 30
    3957  470.83    4111  469.92  4150.6  468.79  4310.6  460.17  4800.7  443.12
  4830.7  444.03  4850.7  442.56  4890.7  441.96  4970.7  443.75  4980.7  441.26
  4990.7  435.25  4997.7  435.15  5000.5  434.65  5003.7  435.15  5010.7  440.29
  5030.7  443.42  5360.8  443.97  5470.2  442.37  5477.3  442.56  5550.8  441.72
  5610.8  442.43  5710.8  447.93  5824.7  448.86  5910.9  451.53  6076.4  454.31
  6130.9   454.9  6150.9  458.22  6370.9  465.28  6470.9  465.98  6514.7   465.1
#Mann= 8 ,-1 , 0
    3957      .1       0    4111     .05       0  4997.7     .03       0
  5003.7     .05       0  5470.2      .1       0  5477.3     .05       0
  5824.7      .1       0  6076.4     .05       0
Bank Sta=4970.7,5030.7
XS Rating Curve= 0 ,0
Exp/Cntr=0.3,0.1

Type RM Length L Ch R = 1 ,86567   ,38,38,38
BEGIN DESCRIPTION:
SANDERS CREEK 111.3
END DESCRIPTION:
XS GIS Cut Line= 5
      3576164.74     10546829.16      3574745.45     10546519.26
      3574323.57     10546235.41      3574284.51      10546102.6
      3573753.27     10545766.66
#Sta/Elev= 30
  3476.9  471.57  3617.8  469.23  3881.9  463.11  4328.3  450.41  4544.1  441.25
    4967  442.56    4988  437.67    4994  434.59    5000  434.55  5002.7  434.05
    5006  434.55  5030.1  441.79  5066.2  440.59  5218.9  443.64  5324.9  442.23
  5362.9  440.16  5368.9  441.95  5434.9  443.01    5437  441.31  5445.9  441.04
  5455.7  441.17  5459.4  441.95  5466.3  439.31  5492.7  443.28  5546.3  440.45
  5592.4  443.26  5875.2  443.74  6035.8  446.37  6093.5  450.99  6205.1  450.35
#Mann= 9 ,-1 , 0
  3476.9     .05       0  3617.8      .1       0  3881.9     .05       0
    5000     .03       0    5006     .05       0  5324.9     .16       0
  5445.9     .05       0  5455.7     .16       0  5466.3     .05       0
Bank Sta=4967,5030.1
XS Rating Curve= 0 ,0
Exp/Cntr=0.3,0.1

Type RM Length L Ch R = 1 ,86529   ,47,47,47
BEGIN DESCRIPTION:
SANDERS CREEK 111.2
END DESCRIPTION:
XS GIS Cut Line= 5
      3576172.55     10546810.93      3574787.12     10546501.03
       3574339.2      10546227.6      3574297.53     10546086.97
      3573746.26     10545728.12
#Sta/Elev= 30
  3497.9  470.97  3631.6  469.66  3711.6  467.39  3834.8  465.14  3906.1  462.35
  4328.4  450.75  4441.1  444.92  4570.2  441.33  4667.2  440.97  4748.5  442.75
  4830.5   440.9  4979.9  441.81  4985.7  438.46  4998.2  434.39  5000.9  433.89
  5004.2  434.39  5028.9  442.29  5074.7  440.67  5233.5  443.32    5307  441.63
  5312.9  442.45  5349.6  442.32  5451.8  442.63  5785.8   444.6  5879.4  443.71
    5973  445.92  6100.9  451.26  6130.1  451.75  6211.4   451.2  6246.8  452.05
#Mann= 9 ,-1 , 0
  3497.9     .05       0  3711.6      .1       0  3906.1     .05       0
  4998.2     .03       0  5004.2     .05       0  5349.6     .16       0
  5451.8     .05       0  6100.9     .08       0  6130.1     .05       0
Bank Sta=4979.9,5028.9
XS Rating Curve= 0 ,0
Exp/Cntr=0.3,0.1

Type RM Length L Ch R = 1 ,86482   ,23,23,23
BEGIN DESCRIPTION:
SANDERS CREEK 111.0
END DESCRIPTION:
XS GIS Cut Line= 5
      3576211.59     10546774.47      3574813.16     10546461.97
      3574378.26     10546196.35       3574339.2     10546073.95
      3573771.51     10545691.15
#Sta/Elev= 30
  3486.9  469.99  3701.3  467.72  3804.6   464.2  3924.3  461.71  4500.8  443.01
  4828.7  440.72  4859.4  443.49  4896.8  443.54    4902  442.05  4965.2  442.02
  4971.1   439.1  4979.6  438.77  4986.6  441.36  4989.4  434.14  4992.2  433.64
  4995.4  434.14    5002  438.84  5007.9  434.15  5014.8  440.52  5023.3  443.38
  5065.9  441.57  5167.1  444.05    5380  443.81  5380.6  443.85  5736.6  445.49
  5859.6  444.22  6028.4  448.49  6152.7  452.33  6214.7  452.53  6242.6  452.67
#Mann= 10 ,-1 , 0
  3486.9     .05       0  3804.6      .1       0  3924.3     .05       0
  4989.4     .03       0  4995.4     .05       0    5380     .16       0
  5380.6     .05       0  6028.4     .08       0  6152.7     .05       0
  6214.7     .08       0
Bank Sta=4896.8,5023.3
XS Rating Curve= 0 ,0
Exp/Cntr=0.3,0.1

Type RM Length L Ch R = 1 ,86459   ,995,995,995
BEGIN DESCRIPTION:
SANDERS CREEK 111.1
END DESCRIPTION:
XS GIS Cut Line= 5
      3576221.98     10546740.61      3574815.76     10546435.93
       3574399.1     10546180.72      3574357.43     10546050.51
      3573776.87     10545662.61
#Sta/Elev= 30
  3494.4  469.12  3647.8  468.36  3780.8  465.25    4317  450.79  4374.2     447
  4517.5     442  4695.1  443.12  4814.2  440.82  4855.1   443.5  4886.8  441.08
    4961  441.21  4993.2  430.73  4995.9  430.23  4999.2  430.73  5019.6  432.59
  5026.6   437.9    5042  441.67  5047.9  440.56  5090.4  442.99  5200.7  445.08
  5368.9  443.54    5424  445.27  5547.9   443.7  5640.3  442.89  5698.2   444.7
  5856.6   444.2  5986.1  447.09  6172.1   451.7  6173.8  451.72  6256.8  453.09
#Mann= 8 ,-1 , 0
  3494.4     .05       0  4993.2     .03       0  4999.2     .05       0
  5547.9      .1       0  5698.2     .05       0  5986.1     .08       0
  6172.1     .05       0  6173.8     .08       0
Bank Sta=4961,5042
XS Rating Curve= 0 ,0
Exp/Cntr=0.3,0.1

Type RM Length L Ch R = 1 ,85464   ,1174,1174,1174
BEGIN DESCRIPTION:
SANDERS CREEK 109.0
END DESCRIPTION:
XS GIS Cut Line= 4
      3576947.19     10546635.95      3575322.16     10545955.39
      3574912.44     10545781.77      3573488.81     10544837.32
#Sta/Elev= 30
  3087.9  474.55  3125.9     472  3163.8  474.46    3246  474.58  3553.1  465.78
  3783.5  455.07  4323.6  447.25  4534.5  443.07  4547.8  442.93  4745.5  440.03
  4958.4     440  4974.6   438.1  4979.6  434.07  4987.9  430.04  4990.7  429.54
  4993.9  430.04  5003.7  430.72    5022  437.65  5034.4  439.61  5070.7  440.12
  5088.7  435.63  5103.9  439.03  5374.7  442.47  5689.9  440.97  5845.6  443.25
  6340.1  451.09  6485.7  457.09  6664.9  456.39  6697.6  460.21  7003.1  471.16
#Mann= 13 ,-1 , 0
  3087.9     .05       0  4323.6     .08       0  4534.5     .05       0
  4547.8     .08       0  4745.5     .05       0  4979.6     .16       0
  4987.9     .07       0  4993.9     .16       0  5070.7     .05       0
  5689.9     .08       0  5845.6     .05       0  6485.7      .1       0
  6697.6     .05       0
Bank Sta=4958.4,5034.4
XS Rating Curve= 0 ,0
Exp/Cntr=0.3,0.1

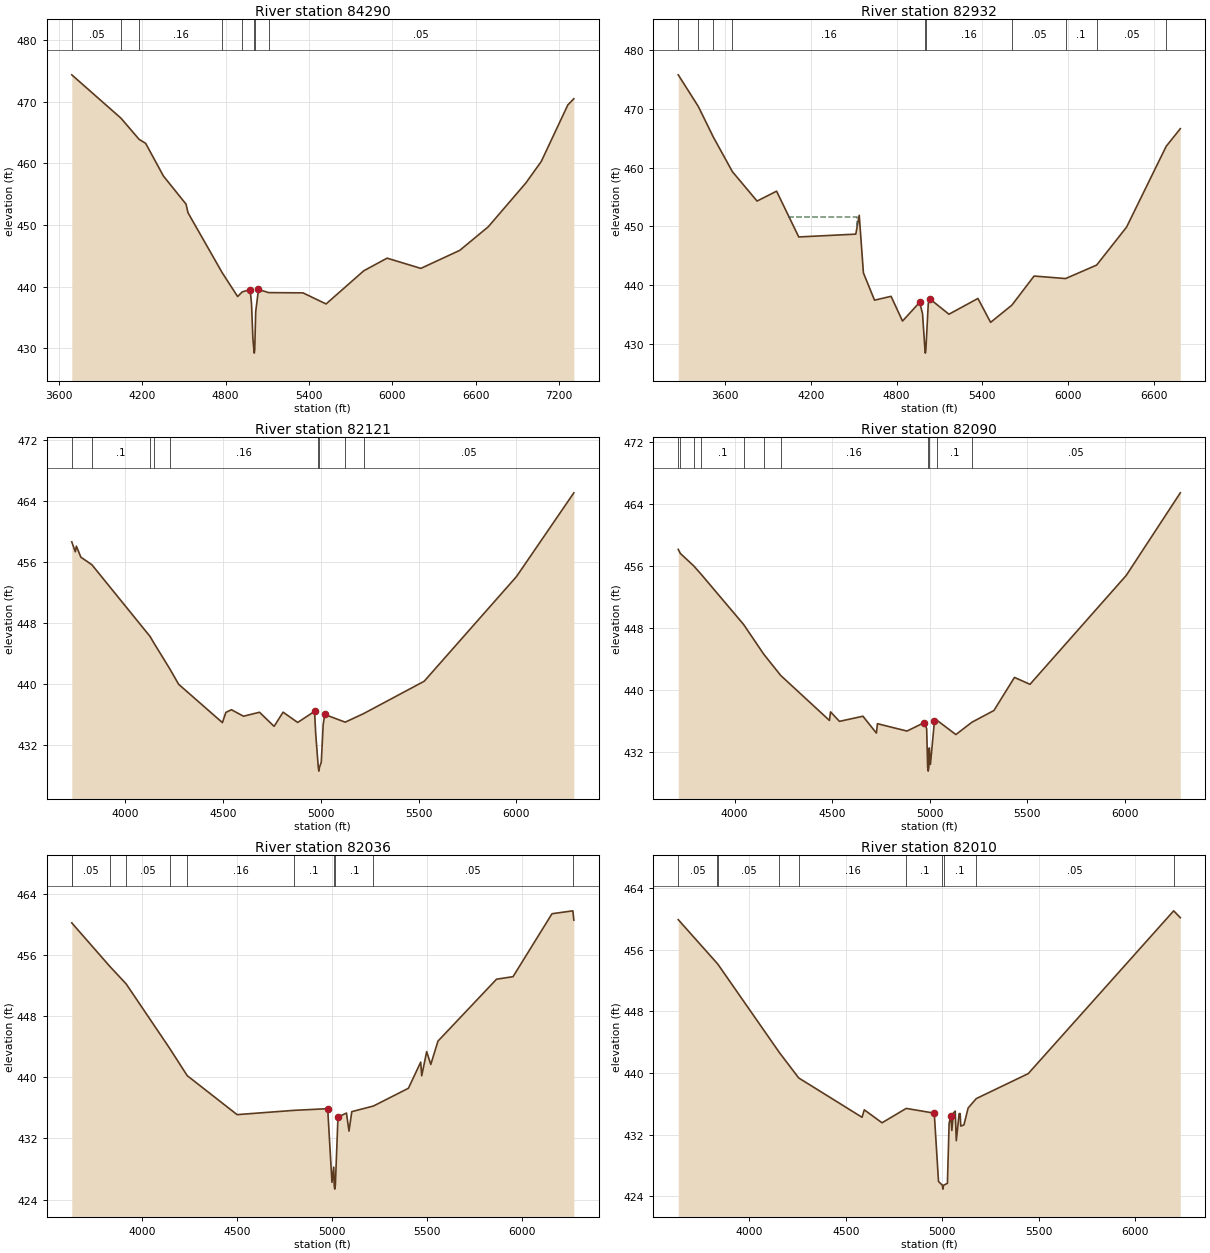
Type RM Length L Ch R = 1 ,84290   ,1358,1358,1358
BEGIN DESCRIPTION:
SANDERS CREEK 107.0
END DESCRIPTION:
XS GIS Cut Line= 4
      3576781.58     10545854.55      3576104.48     10545229.53
      3575323.23     10545203.49      3573657.43     10544266.48
#Sta/Elev= 30
  3692.6  474.37  4047.1  467.33    4177  463.91  4224.9  463.24  4352.4  457.95
  4515.2  453.39  4529.4  451.99  4775.6  442.26  4886.6  438.39  4919.3  439.14
  4976.6  439.53  4986.7  437.21  4996.3  431.69  5003.7  429.71  5006.4  429.21
  5009.7  429.71  5016.7  435.92  5036.7  439.55  5109.5  439.03  5356.9  438.99
  5523.3  437.19  5795.1  442.58  5962.7  444.62  6205.6  442.96    6486  445.89
  6691.3  449.72  6961.5  456.82  7072.2   460.3  7263.7  469.48    7307  470.49
#Mann= 8 ,-1 , 0
  3692.6     .05       0  4047.1      .1       0    4177     .16       0
  4775.6      .1       0  4919.3     .16       0  5003.7     .07       0
  5009.7     .16       0  5109.5     .05       0
Bank Sta=4976.6,5036.7
XS Rating Curve= 0 ,0
Exp/Cntr=0.3,0.1

Type RM Length L Ch R = 1 ,82932   ,811,811,811
BEGIN DESCRIPTION:
SANDERS CREEK 103.0
END DESCRIPTION:
XS GIS Cut Line= 4
      3577575.65     10544785.25       3576242.3     10544243.58
      3575683.27     10544222.75      3574338.33     10543526.01
#Sta/Elev= 30
  3272.2  475.77  3412.4  470.41  3517.5  465.21  3651.4  459.31  3823.8  454.32
  3960.4     456  4115.6  448.22  4514.6   448.7  4538.7  451.91  4568.1  442.11
  4645.8  437.48  4761.6  438.13  4841.7  433.93  4961.8  437.12  4981.8  435.16
  4998.8  428.98  5001.5  428.48  5004.8  428.98  5021.8  436.89  5031.8  437.72
  5166.5  435.09  5369.4  437.77    5458  433.71  5607.2  436.64  5762.2  441.58
  5982.6  441.15    6200  443.44  6409.3  449.89  6686.9  463.63  6785.5  466.62
#Mann= 10 ,-1 , 0
  3272.2     .16       0  3412.4     .05       0  3517.5      .1       0
  3651.4     .16       0  4998.8     .07       0  5004.8     .16       0
  5607.2     .05       0  5982.6      .1       0    6200     .05       0
  6686.9      .1       0
#XS Ineff= 1 ,-1
    4050    4525  451.61
Permanent Ineff=
       F
Bank Sta=4961.8,5031.8
XS Rating Curve= 0 ,0
Exp/Cntr=0.3,0.1

Type RM Length L Ch R = 1 ,82121   ,31,31,31
BEGIN DESCRIPTION:
SANDERS CREEK 102.2
END DESCRIPTION:
XS GIS Cut Line= 6
      3576869.27     10544116.07      3575525.48     10543493.65
      3575332.78     10543550.95      3575181.73     10543496.26
      3574705.17     10543228.03      3574530.73     10543222.82
#Sta/Elev= 30
  3728.9  458.62  3746.9  457.32  3752.4  458.06  3775.4  456.61  3831.7  455.62
  4128.8   446.2  4148.4  445.34  4230.2  441.92  4274.8  439.92  4498.3  434.89
  4515.8  436.23  4544.3  436.58  4605.9  435.73  4687.7  436.25  4762.2   434.4
  4808.2  436.26  4882.7  434.91  4968.9  436.37  4974.7  433.43  4987.9  429.02
  4990.7  428.52  4993.9  429.02  5003.2  429.71  5012.9  434.62  5020.7  435.96
  5125.4  434.95  5219.2  436.07  5528.7  440.32  6000.2  454.07    6293  465.06
#Mann= 9 ,-1 , 0
  3728.9     .16       0  3831.7      .1       0  4128.8     .05       0
  4148.4      .1       0  4230.2     .16       0  4987.9     .07       0
  4993.9     .16       0  5125.4      .1       0  5219.2     .05       0
Bank Sta=4968.9,5020.7
XS Rating Curve= 0 ,0
Exp/Cntr=0.3,0.1

Type RM Length L Ch R = 1 ,82090   ,54,54,54
BEGIN DESCRIPTION:
SANDERS CREEK 102.1
END DESCRIPTION:
XS GIS Cut Line= 6
      3576887.44      10544092.6      3575593.19     10543496.26
      3575515.07     10543470.22      3575327.57     10543517.09
      3574699.96     10543188.97      3574536.54     10543183.78
#Sta/Elev= 30
  3711.4  458.14  3722.1  457.62  3790.1  456.03    3829  454.93  4046.5  448.47
  4149.8  444.64  4237.2  441.89  4486.6  436.11  4492.1  437.21    4538  435.99
  4658.3  436.65  4727.2  434.48  4732.7  435.69  4884.3  434.74  4973.3  435.84
    4985  435.03  4990.1  430.08  4992.8  429.58  4996.1  430.08  4998.3  432.57
  5004.2  430.44  5025.1  436.09  5036.1  436.16  5134.8  434.29  5217.1  435.88
  5329.9  437.39  5435.1  441.65  5514.7  440.76    6008  454.78  6285.3  465.42
#Mann= 11 ,-1 , 0
  3711.4      .1       0  3722.1     .16       0  3790.1     .05       0
    3829      .1       0  4046.5     .05       0  4149.8      .1       0
  4237.2     .16       0  4990.1     .07       0  4996.1     .16       0
  5036.1      .1       0  5217.1     .05       0
Bank Sta=4973.3,5025.1
XS Rating Curve= 0 ,0
Exp/Cntr=0.3,0.1

Type RM Length L Ch R = 1 ,82036   ,26,26,26
BEGIN DESCRIPTION:
SANDERS CREEK 102.0
END DESCRIPTION:
XS GIS Cut Line= 6
      3576967.32      10544065.7      3576290.24     10543787.93
      3575574.96     10543428.55      3575358.82      10543459.8
      3574754.65      10543144.7      3574557.82     10543126.57
#Sta/Elev= 30
  3632.4   460.2  3632.6  460.19  3831.9  454.52  3918.5  452.21  4147.5  443.77
  4239.2  440.22  4501.4  435.12  4800.5  435.68  4977.7   435.9  5000.1  426.27
  5009.4  428.26  5011.9  425.88  5014.7  425.38  5017.9  425.88  5031.7   434.8
  5076.3  435.33  5089.6  432.97  5104.3  435.51  5218.3  436.25    5402  438.57
  5466.6  441.99  5471.9   440.2  5497.9  443.36  5519.6  441.68  5557.2  444.73
  5865.1  452.83  5951.8  453.16  6156.7  461.39  6266.4  461.77  6271.5  460.55
#Mann= 11 ,-1 , 0
  3632.4      .1       0  3632.6     .05       0  3831.9      .1       0
  3918.5     .05       0  4147.5      .1       0  4239.2     .16       0
  4800.5      .1       0  5011.9     .07       0  5017.9      .1       0
  5218.3     .05       0  6266.4     .08       0
Bank Sta=4977.7,5031.7
XS Rating Curve= 0 ,0
Exp/Cntr=0.3,0.1

Type RM Length L Ch R = 1 ,82010   ,511,511,511
BEGIN DESCRIPTION:
SANDERS CREEK 102.3
END DESCRIPTION:
XS GIS Cut Line= 6
      3576968.22     10544045.75      3575642.67     10543438.97
      3575496.84     10543376.47      3575330.17     10543418.13
      3574772.88     10543116.05      3574595.17     10543092.87
#Sta/Elev= 30
  3631.6  459.88  3834.4  454.18  3837.1   454.1  4154.9  442.68  4255.8  439.36
  4584.1  434.26  4595.6  435.23  4687.6  433.55  4812.8  435.41  4958.1   434.8
  4980.2  425.94  5000.2  425.45    5003  424.95  5006.2  425.45  5026.3   425.7
  5035.1  433.48  5043.8  434.46  5049.3  432.55  5057.1  434.81  5066.8  435.06
  5072.3  431.23    5087  434.74  5092.4  434.74  5095.4  433.12  5111.8  433.27
  5133.6  435.46  5175.5  436.68  5445.1  439.92  6198.7  461.02    6233  460.13
#Mann= 10 ,-1 , 0
  3631.6     .05       0  3834.4      .1       0  3837.1     .05       0
  4154.9      .1       0  4255.8     .16       0  4812.8      .1       0
  5000.2     .07       0  5006.2      .1       0  5175.5     .05       0
  6198.7     .08       0
Bank Sta=4958.1,5043.8
XS Rating Curve= 0 ,0
Exp/Cntr=0.3,0.1

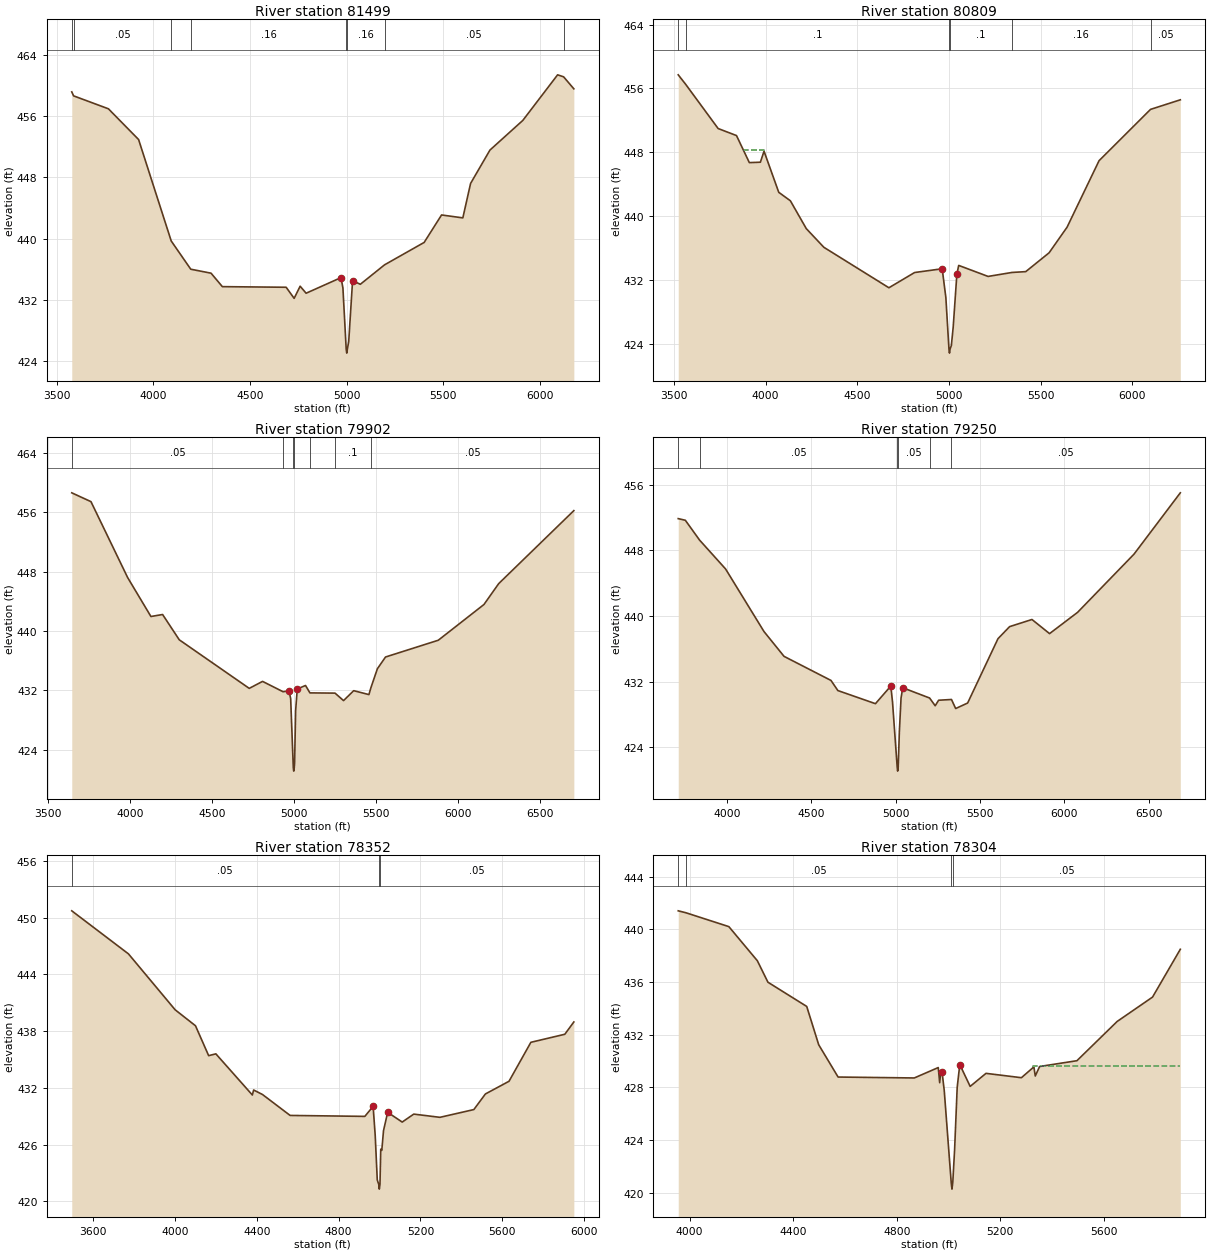
Type RM Length L Ch R = 1 ,81499   ,690,690,690
BEGIN DESCRIPTION:
SANDERS CREEK 100.0
END DESCRIPTION:
XS GIS Cut Line= 3
      3577117.28     10543264.41      3575933.27     10542962.33
      3574558.23     10543024.83
#Sta/Elev= 30
  3577.3  459.19  3586.8  458.67  3766.9  456.98  3923.2  452.96    4092   439.7
  4193.1  436.01  4298.1  435.49  4356.7  433.73  4686.9  433.65  4728.2   432.2
  4759.2  433.79  4790.1  432.87  4970.6  434.91  4980.6  433.56  4997.6  425.54
  5000.4  425.04  5003.6  425.54  5010.6  426.56  5030.6  434.51  5070.7  434.04
    5196  436.58    5401  439.51  5491.1   443.1  5601.2  442.72  5641.3  447.22
  5741.4  451.58  5911.6  455.46  6091.7  461.42  6122.7  461.16  6175.7  459.59
#Mann= 8 ,-1 , 0
  3577.3     .08       0  3586.8     .05       0    4092      .1       0
  4193.1     .16       0  4997.6     .07       0  5003.6     .16       0
    5196     .05       0  6122.7     .08       0
Bank Sta=4970.6,5030.6
XS Rating Curve= 0 ,0
Exp/Cntr=0.3,0.1

Type RM Length L Ch R = 1 ,80809   ,907,907,907
BEGIN DESCRIPTION:
SANDERS CREEK 99.0
END DESCRIPTION:
XS GIS Cut Line= 3
      3577279.37      10542459.6      3575476.42     10542362.04
      3574597.93     10542674.55
#Sta/Elev= 30
  3523.7   457.7  3564.6   456.5  3741.3  450.97  3841.4  450.09  3911.5   446.7
  3971.6  446.75  3991.6  448.13  4071.8  442.98  4135.2  441.92    4222  438.43
  4317.9  436.09  4672.6  431.02  4812.8  432.93  4963.1   433.4  4983.1  429.81
  5000.1  423.33  5002.9  422.83  5006.1  423.33  5013.1  423.78  5023.2   426.1
  5043.2  432.72  5053.2  433.82  5213.4  432.44  5344.4  432.94  5418.8  433.04
  5546.1   435.4  5644.2  438.61  5818.6  446.94  6099.3  453.37  6261.7  454.57
#Mann= 6 ,-1 , 0
  3523.7     .08       0  3564.6      .1       0  5000.1     .07       0
  5006.1      .1       0  5344.4     .16       0  6099.3     .05       0
#XS Ineff= 1 ,-1
 3881.82 3992.61  448.34
Permanent Ineff=
       F
Bank Sta=4963.1,5043.2
XS Rating Curve= 0 ,0
Exp/Cntr=0.3,0.1

Type RM Length L Ch R = 1 ,79902   ,652,652,652
BEGIN DESCRIPTION:
SANDERS CREEK 97.0
END DESCRIPTION:
XS GIS Cut Line= 4
      3577117.32      10541941.5      3575939.64     10541728.53
      3575499.25      10541778.3      3574120.74     10542129.01
#Sta/Elev= 30
  3644.8  458.63  3761.9  457.44  3985.5  447.21  4127.7  441.95  4198.9  442.22
  4300.5  438.81  4727.3  432.26  4808.6   433.2  4933.4  431.81  4969.9  431.91
    4980  430.88    4996   421.6  4998.7   421.1    5002   421.6    5004  422.23
  5010.2  429.23  5020.2  432.18  5070.6  432.65  5097.5  431.65  5250.6  431.62
  5302.5  430.61  5364.4  431.95  5457.2  431.42  5469.3  432.34  5508.8   434.9
  5558.6  436.49  5880.3  438.75  6158.9  443.57    6249  446.39  6707.2  456.23
#Mann= 7 ,-1 , 0
  3644.8     .05       0  4933.4      .1       0    4996     .07       0
    5002      .1       0  5097.5     .05       0  5250.6      .1       0
  5469.3     .05       0
Bank Sta=4969.9,5020.2
XS Rating Curve= 0 ,0
Exp/Cntr=0.3,0.1

Type RM Length L Ch R = 1 ,79250   ,898,898,898
BEGIN DESCRIPTION:
SANDERS CREEK 95.0
END DESCRIPTION:
XS GIS Cut Line= 3
      3577083.61     10541305.05      3576068.02      10541127.1
      3574146.14     10541417.77
#Sta/Elev= 30
  3712.6  451.86  3754.7  451.66  3838.9  449.25  3993.2  445.73  4220.8  438.11
  4339.6  435.09  4617.7  432.16  4658.3  430.93  4881.1  429.33  4972.1  431.48
  4982.3  429.52  5009.9  421.62  5012.6  421.12  5015.9  421.62  5022.7  425.88
  5032.8  430.03  5042.9  431.27  5201.9  430.02  5235.1  429.08  5255.3  429.75
  5331.6  429.84  5356.5  428.74  5427.3  429.41  5607.1  437.24  5675.9  438.71
  5808.5  439.58  5912.7  437.86  6078.8  440.45  6412.9  447.53  6687.4     455
#Mann= 6 ,-1 , 0
  3712.6     .08       0  3838.9     .05       0  5009.9     .03       0
  5015.9     .05       0  5201.9      .1       0  5331.6     .05       0
Bank Sta=4972.1,5042.9
XS Rating Curve= 0 ,0
Exp/Cntr=0.3,0.1

Type RM Length L Ch R = 1 ,78352   ,48,48,48
BEGIN DESCRIPTION:
SANDERS CREEK 93.0
END DESCRIPTION:
XS GIS Cut Line= 4
      3577106.87     10541215.79      3576006.19     10540368.58
      3575773.55     10540326.91      3575096.81     10540809.31
#Sta/Elev= 30
  3494.3  450.71  3771.6  446.16    4000  440.25  4099.6  438.56    4164   435.4
  4199.3  435.59  4377.8  431.24  4384.1  431.77  4427.6  431.29  4562.6  429.08
  4928.1  428.98  4968.7  430.04  4978.9  426.96    4989  422.25  4996.2  421.79
  4998.9  421.29  5002.2  421.79    5006  425.51  5011.1  425.39  5019.5  427.47
  5039.8  429.41  5110.9  428.38  5167.6  429.22  5295.5  428.88  5461.4   429.7
    5518  431.35  5633.5  432.69  5740.5  436.81  5906.4  437.66  5950.7  438.96
#Mann= 3 ,-1 , 0
  3494.3     .05       0  4996.2     .03       0  5002.2     .05       0
Bank Sta=4968.7,5039.8
XS Rating Curve= 0 ,0
Exp/Cntr=0.3,0.1

Type RM Length L Ch R = 1 ,78304   ,22,22,22
BEGIN DESCRIPTION:
SANDERS CREEK 92.2
END DESCRIPTION:
XS GIS Cut Line= 4
      3576840.47     10540719.99      3575913.79     10540303.31
      3575785.76     10540294.63      3575048.24     10539996.16
#Sta/Elev= 30
  3955.8   441.4    3986  441.25  4151.4   440.2  4261.5  437.61  4302.4  435.98
  4452.3  434.14  4498.6  431.23  4573.5  428.78  4867.9  428.71  4960.5   429.5
    4966  428.35    4970  429.16  4975.2  429.16  4983.6  427.77  5010.6  420.77
  5013.4  420.27  5016.6  420.77  5023.7  423.27  5033.7     428  5043.7  429.73
  5083.8  428.07    5145  429.06  5281.8  428.73    5330  429.55  5335.4  428.86
  5352.2  429.58  5496.3  430.02  5651.8     433  5788.5  434.85  5895.8  438.48
#Mann= 4 ,-1 , 0
  3955.8     .08       0    3986     .05       0  5010.6     .04       0
  5016.6     .05       0
#XS Ineff= 2 , 0
                         5328.12          429.64
Permanent Ineff=
       F       F
Bank Sta=4975.2,5043.7
XS Rating Curve= 0 ,0
Exp/Cntr=0.3,0.1

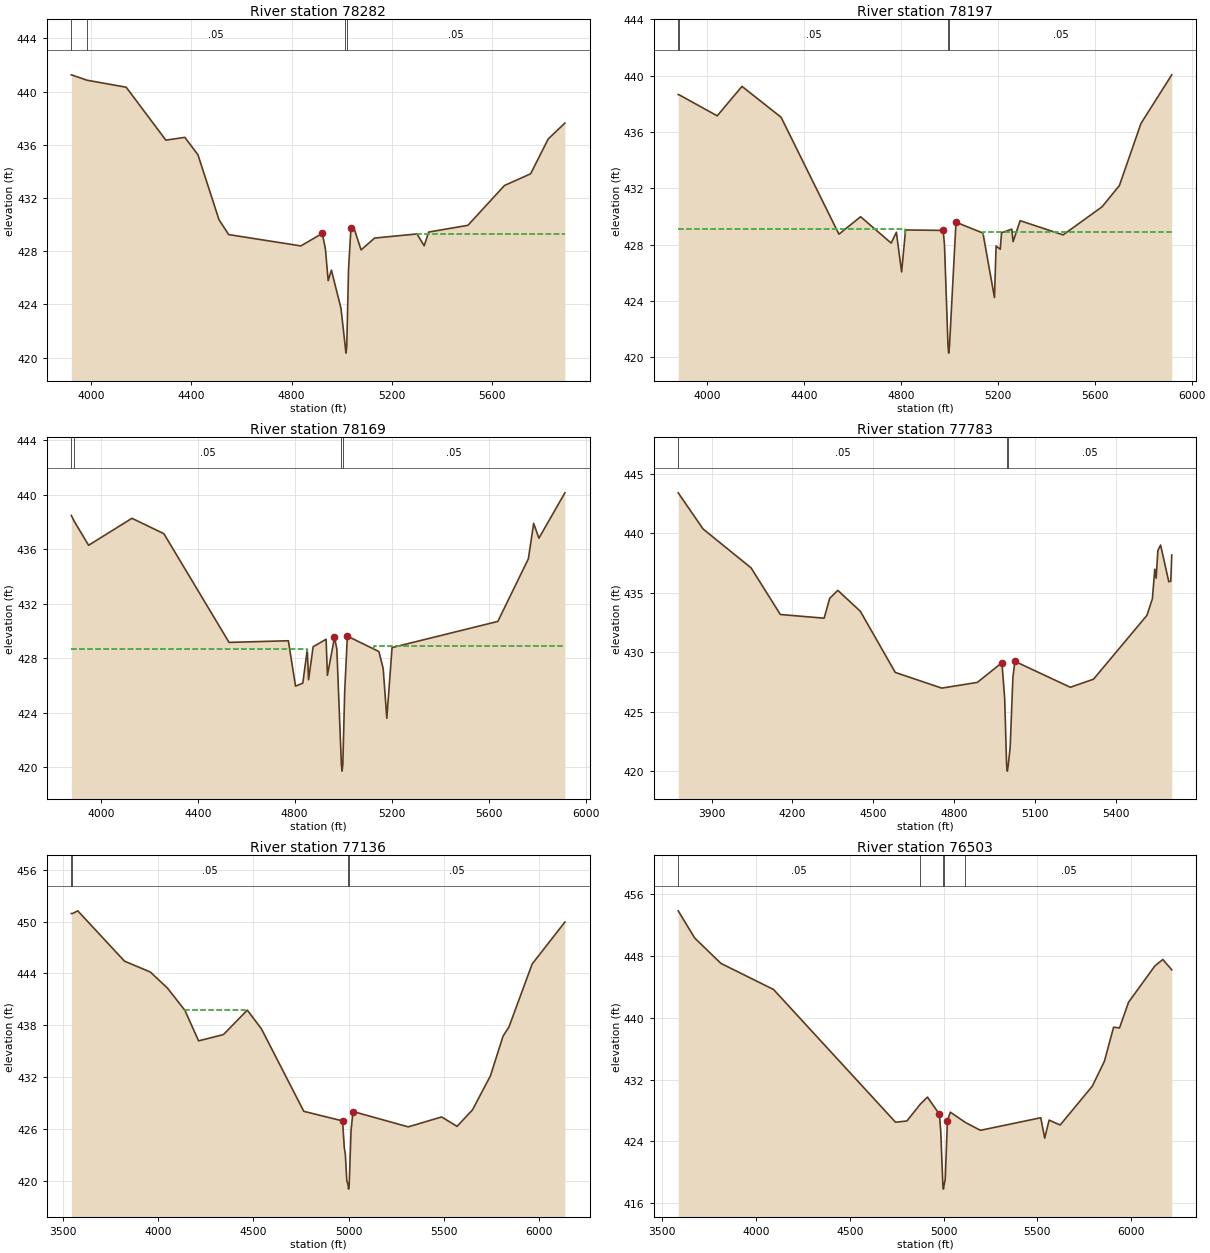
Type RM Length L Ch R = 1 ,78282   ,85,85,85
BEGIN DESCRIPTION:
SANDERS CREEK 92.1
END DESCRIPTION:
XS GIS Cut Line= 4
      3576872.99     10540696.97       3575920.3     10540283.78
      3575794.44     10540272.93      3575055.74     10539950.15
#Sta/Elev= 30
  3920.5  441.26  3984.4  440.85  4139.5  440.33  4297.9  436.35  4373.8  436.56
  4426.1  435.25  4510.1  430.37  4548.9  429.25  4837.1   428.4  4922.7  429.34
  4935.2  428.16  4946.1  425.79  4958.9  426.58  4997.3  423.71  5014.3  420.84
  5017.1  420.34  5020.3  420.84  5027.4  426.62  5037.2  429.78  5047.5  429.83
  5077.6   428.1  5131.5  428.99  5300.7   429.3  5329.5  428.41  5347.5  429.44
  5504.3  429.95  5650.1  432.94  5754.6  433.82  5824.8  436.44  5891.4  437.63
#Mann= 4 ,-1 , 0
  3920.5     .08       0  3984.4     .05       0  5014.3     .04       0
  5020.3     .05       0
#XS Ineff= 2 , 0
                         5302.56          429.32
Permanent Ineff=
       F       F
Bank Sta=4922.7,5037.2
XS Rating Curve= 0 ,0
Exp/Cntr=0.3,0.1

Type RM Length L Ch R = 1 ,78197   ,28,28,28
BEGIN DESCRIPTION:
SANDERS CREEK 92.0
END DESCRIPTION:
XS GIS Cut Line= 4
      3576917.31     10540616.26      3575951.12     10540228.22
      3575430.29     10540009.47      3575031.86     10539848.02
#Sta/Elev= 30
  3881.9  438.65  3883.9  438.65  4042.8  437.14    4145  439.23  4306.3  437.04
  4544.9  428.74  4634.3  429.98  4760.4  428.11  4781.9  428.88  4803.5  426.06
  4819.8  429.04  4974.8  429.01  4980.3  428.01    4995   420.8  4997.7   420.3
    5001   420.8  5027.8  429.59  5139.1  428.82  5186.6  424.24  5193.2   427.9
  5210.4  427.67  5215.8  428.84  5257.9   429.1  5263.3  428.21  5292.5   429.7
  5469.6  428.69  5630.2  430.68  5701.8  432.19    5791   436.6  5917.9  440.05
#Mann= 4 ,-1 , 0
  3881.9     .08       0  3883.9     .05       0    4995     .04       0
    5001     .05       0
#XS Ineff= 2 , 0
         4818.18  429.14 5140.62          428.89
Permanent Ineff=
       F       F
Bank Sta=4974.8,5027.8
XS Rating Curve= 0 ,0
Exp/Cntr=0.3,0.1

Type RM Length L Ch R = 1 ,78169   ,386,386,386
BEGIN DESCRIPTION:
SANDERS CREEK 92.3
END DESCRIPTION:
XS GIS Cut Line= 4
      3576928.09     10540590.19      3575961.97     10540202.18
      3575441.14     10539983.43      3575042.74     10539821.99
#Sta/Elev= 30
  3878.7  438.47    3891  438.03  3949.8  436.28  4128.7  438.26  4260.4  437.13
  4529.3  429.15  4773.9  429.27  4803.5  425.94  4833.5  426.16  4851.9  428.62
  4857.3  426.41  4876.1  428.83  4929.6  429.38    4935  426.73  4964.2  429.51
  4973.9  428.67  4992.6   420.2  4995.4   419.7  4998.6   420.2  5006.3  425.55
  5017.3  429.61  5147.4  428.48  5165.1  427.23    5180  423.58  5201.7  428.77
    5638  430.69    5764  435.29  5785.8  437.89  5807.4   436.8  5914.6  440.13
#Mann= 4 ,-1 , 0
  3878.7     .08       0    3891     .05       0  4992.6     .04       0
  4998.6     .05       0
#XS Ineff= 2 , 0
         4852.27  428.67 5127.84          428.89
Permanent Ineff=
       F       F
Bank Sta=4964.2,5017.3
XS Rating Curve= 0 ,0
Exp/Cntr=0.3,0.1

Type RM Length L Ch R = 1 ,77783   ,647,647,647
BEGIN DESCRIPTION:
SANDERS CREEK 91.1
END DESCRIPTION:
XS GIS Cut Line= 2
      3576965.58     10540053.02      3575161.35     10539736.41
#Sta/Elev= 30
  3776.3  443.39  3868.6  440.35  4046.8  437.08  4155.4  433.16  4317.9  432.85
  4338.6  434.52  4368.7  435.19  4452.3  433.43  4581.9  428.29  4754.5  426.97
  4886.5  427.45  4977.9  429.11    4988  426.09  4995.2  420.49  4997.9  419.99
  5001.2  420.49  5008.3  421.97  5018.5  427.86  5025.9  429.22  5231.7  427.04
  5317.7  427.72    5516  433.09  5536.3  434.49  5545.1  436.97  5550.2  436.21
  5556.6  438.54  5566.7     439  5597.2  435.91  5604.5  435.96  5608.1  438.16
#Mann= 3 ,-1 , 0
  3776.3     .05       0  4995.2     .03       0  5001.2     .05       0
Bank Sta=4977.9,5025.9
XS Rating Curve= 0 ,0
Exp/Cntr=0.3,0.1

Type RM Length L Ch R = 1 ,77136   ,633,633,633
BEGIN DESCRIPTION:
SANDERS CREEK 91.0
END DESCRIPTION:
XS GIS Cut Line= 4
        3577365.     10539741.68      3576089.52     10539472.75
      3575832.58     10539351.22      3574842.13     10539491.64
#Sta/Elev= 30
  3546.3  450.94  3551.4  450.93  3579.9  451.25  3825.2  445.42  3960.8  444.16
    4050  442.31    4142  439.72  4213.5  436.19  4343.8  436.92    4469  439.75
  4542.9  437.59  4765.4  428.03  4968.6  426.92  4977.6  423.83  4983.1  423.06
  4990.8  420.02  4997.4  419.52  5000.1  419.02  5003.4  419.52  5012.9  425.76
  5023.1  428.01  5313.2  426.23    5488  427.38  5568.8  426.29  5649.6  428.19
  5744.1  432.15    5810  436.73  5841.5  437.82  5962.7  445.09  6134.4  449.95
#Mann= 4 ,-1 , 0
  3546.3     .08       0  3551.4     .05       0  4997.4     .03       0
  5003.4     .05       0
#XS Ineff= 1 ,-1
 4144.32 4457.95  439.73
Permanent Ineff=
       F
Bank Sta=4968.6,5023.1
XS Rating Curve= 0 ,0
Exp/Cntr=0.3,0.1

Type RM Length L Ch R = 1 ,76503   ,1331,1331,1331
BEGIN DESCRIPTION:
SANDERS CREEK 91.2
END DESCRIPTION:
XS GIS Cut Line= 4
      3577270.06     10538795.66      3575947.16     10538851.22
      3575645.45     10539036.36      3574736.69     10539326.49
#Sta/Elev= 30
  3584.6  453.85  3672.6  450.33  3812.8  447.04    4093  443.67  4743.6  426.49
  4804.1  426.65  4875.4  428.82  4913.9  429.74  4977.8  427.51    4985  425.15
  4996.1  418.33  4998.8  417.83  5002.1  418.33  5008.5  419.08  5020.3  426.68
  5035.8  427.79  5116.1  426.46  5196.2  425.44  5518.1  427.07  5539.1  424.43
  5562.4  426.76  5621.5  426.13    5793  431.16  5857.3  434.37  5906.5  438.79
    5938  438.69  5986.1  442.01  6126.9  446.73  6168.9  447.55  6216.6  446.22
#Mann= 5 ,-1 , 0
  3584.6     .05       0  4875.4     .16       0  4996.1     .07       0
  5002.1     .16       0  5116.1     .05       0
Bank Sta=4977.8,5020.3
XS Rating Curve= 0 ,0
Exp/Cntr=0.3,0.1