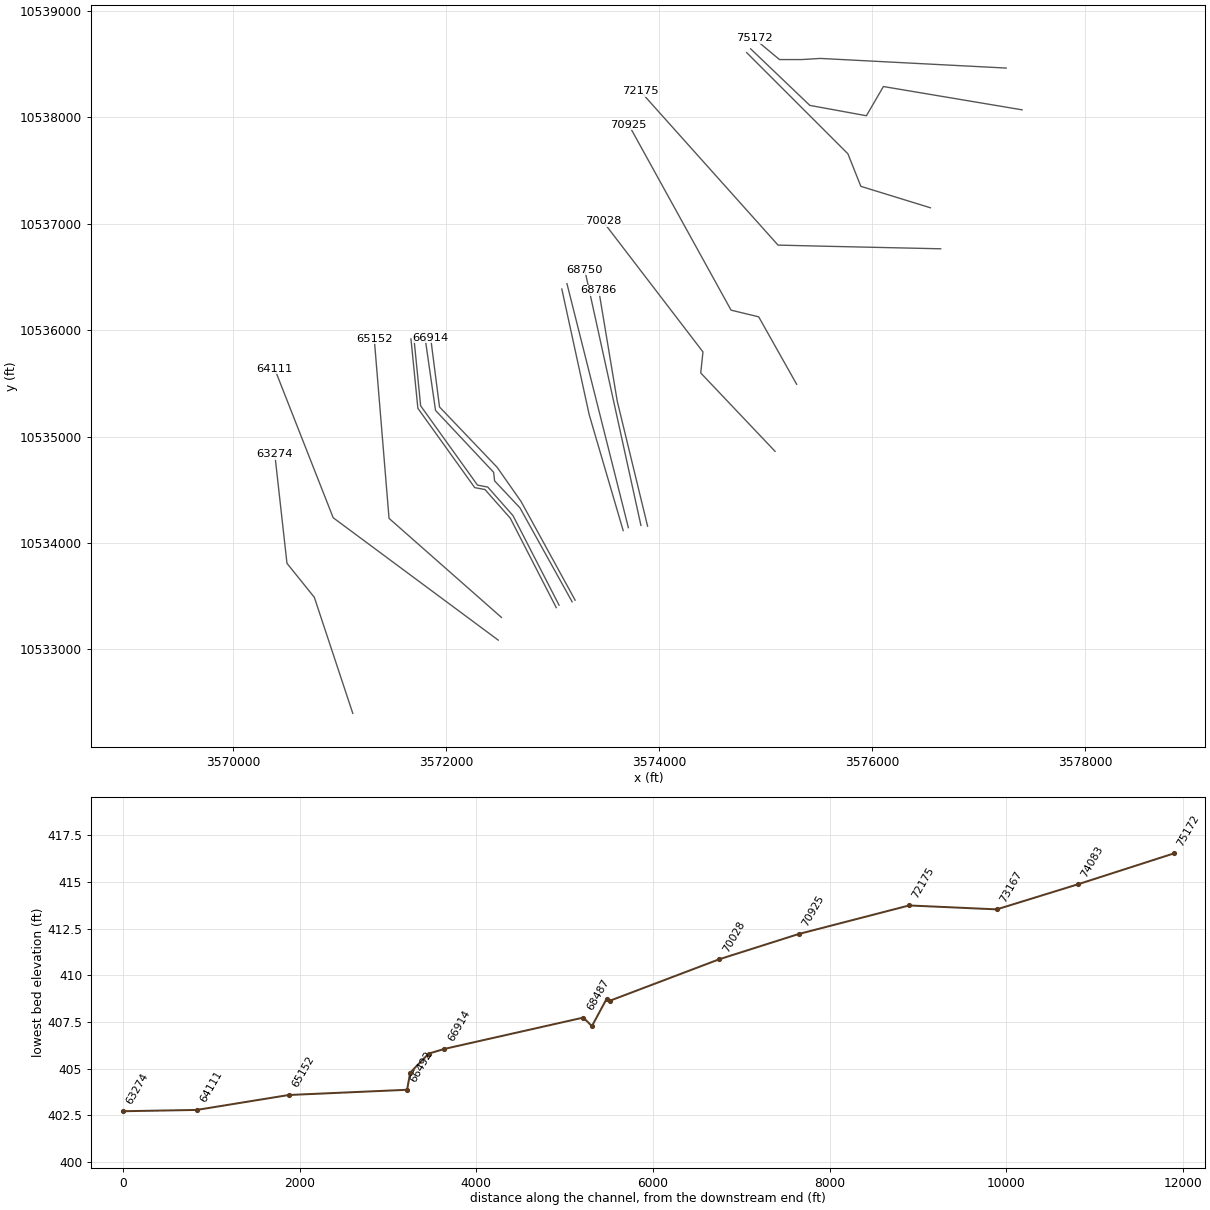
HEC-RAS study SANDERS CREEK.prj: SANDERS CREEK Base Level Engineering

--- SANDERS CREEK.g01 (geometry) --- (continued)

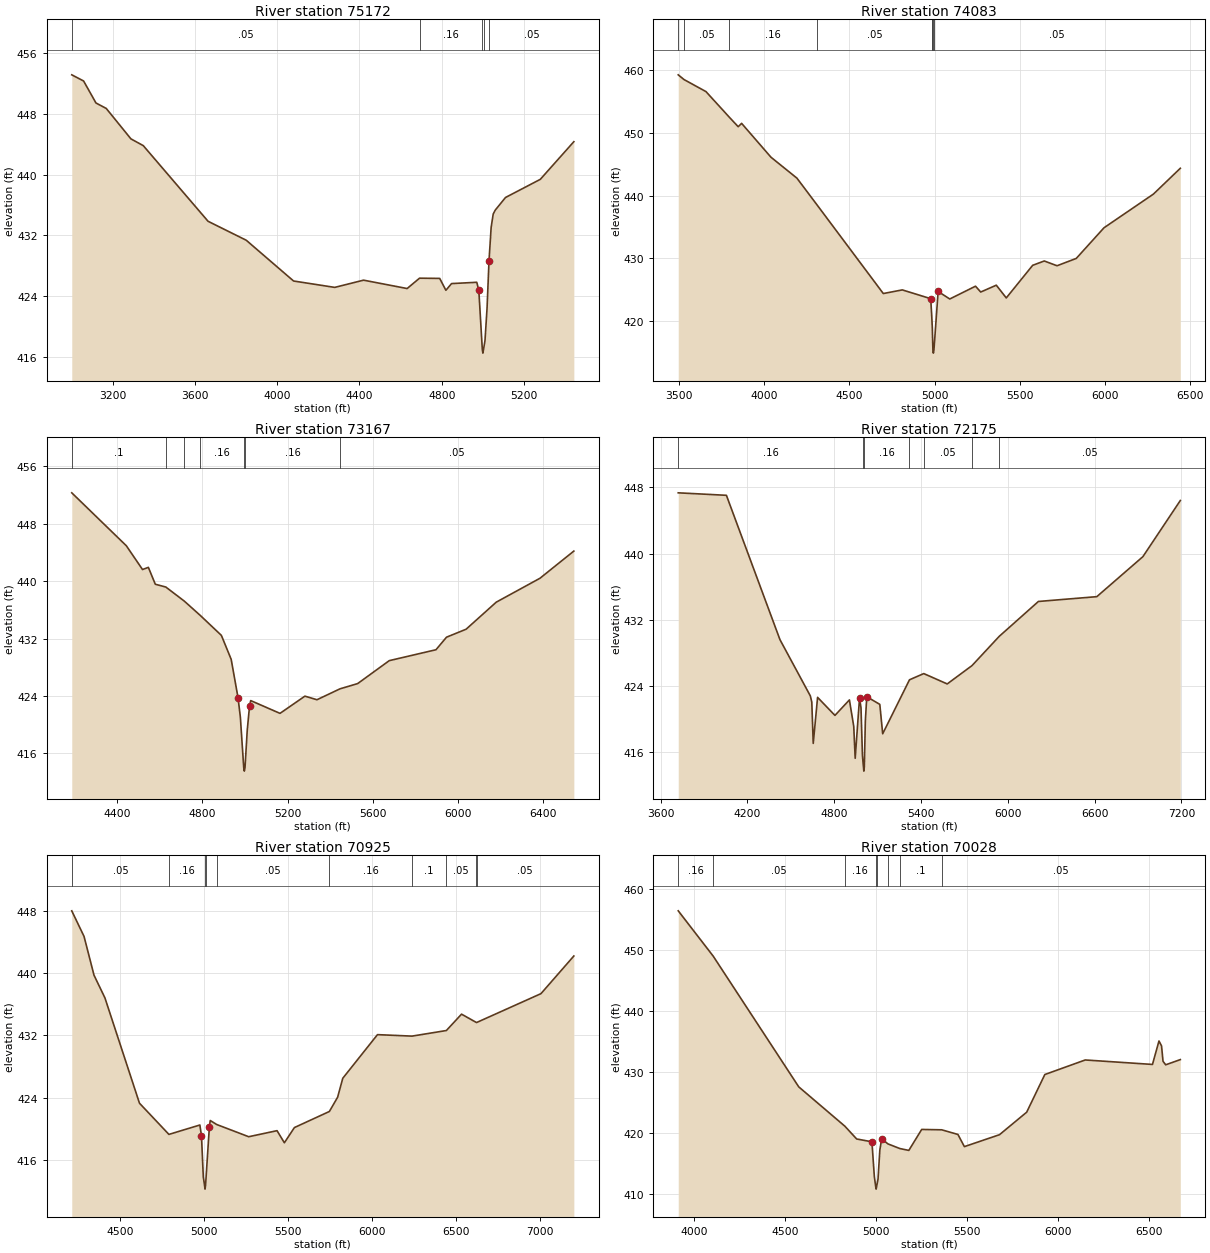
Type RM Length L Ch R = 1 ,75172   ,1089,1089,1089
BEGIN DESCRIPTION:
SANDERS CREEK 90.0
END DESCRIPTION:
XS GIS Cut Line= 5
      3577259.66     10538462.33      3575513.54     10538552.87
      3575339.52     10538542.19      3575131.19     10538542.19
       3574892.1     10538741.64
#Sta/Elev= 30
  3000.4  453.11    3058   452.3  3118.1  449.41  3168.2  448.69  3288.3  444.69
  3348.4   443.8  3663.4  433.86  3849.1  431.37  4079.4  426.01  4279.7  425.17
  4419.9  426.12  4631.9  425.02  4692.2  426.38  4790.4  426.35  4820.4  424.79
    4848  425.67  4970.6  425.84  4980.6   424.8  4997.6  417.03  5000.4  416.53
  5003.6  417.03  5010.6  418.17  5020.6  422.39  5030.2  428.65  5040.6  433.06
  5050.6  434.81  5060.6  435.33  5110.6  436.99  5279.6  439.37  5442.9  444.32
#Mann= 5 ,-1 , 0
  3000.4     .05       0  4692.2     .16       0  4997.6     .07       0
  5003.6     .16       0  5030.2     .05       0
Bank Sta=4980.6,5030.2
XS Rating Curve= 0 ,0
Exp/Cntr=0.3,0.1

Type RM Length L Ch R = 1 ,74083   ,916,916,916
BEGIN DESCRIPTION:
SANDERS CREEK 90.1
END DESCRIPTION:
XS GIS Cut Line= 5
        3577409.     10538069.96      3576106.89     10538288.72
      3575947.16     10538014.41      3575415.91     10538111.64
      3574860.38     10538642.86
#Sta/Elev= 30
  3495.8  459.24    3530  458.48  3658.4  456.57  3796.4  452.46  3847.6  450.97
  3867.8   451.5  4040.2   446.1  4192.3  442.77  4311.8  438.45  4699.3  424.37
  4810.9  424.95  4977.6  423.55  4983.7  420.69  4986.9  418.91  4990.4  415.37
  4993.1  414.87  4996.4  415.37  5021.1   424.7  5089.3   423.5  5240.4  425.54
  5270.9  424.61  5362.4   425.7    5421  423.67  5575.9  428.87  5643.9  429.56
  5718.9   428.8  5831.8  429.97  5994.7  434.86  6284.7  440.23  6442.3  444.34
#Mann= 8 ,-1 , 0
  3495.8     .08       0    3530     .05       0  3796.4     .16       0
  4311.8     .05       0  4983.7     .16       0  4986.9     .05       0
  4990.4     .03       0  4996.4     .05       0
Bank Sta=4977.6,5021.1
XS Rating Curve= 0 ,0
Exp/Cntr=0.3,0.1

Type RM Length L Ch R = 1 ,73167   ,992,992,992
BEGIN DESCRIPTION:
SANDERS CREEK 89.0
END DESCRIPTION:
XS GIS Cut Line= 4
      3576547.85     10537149.83      3575895.08     10537351.22
      3575773.55     10537656.77      3574822.89     10538607.43
#Sta/Elev= 30
  4186.9  452.32  4443.1  444.94  4518.9  441.63  4546.4  441.93    4579  439.58
  4628.2  439.19  4714.1  437.25  4789.4  435.25  4889.1  432.45  4935.1  429.11
  4967.3  423.75  4978.1  421.07    4994  414.03  4996.8  413.53    5000  414.03
  5010.4   419.2  5021.2  422.59  5026.7  423.36  5164.3  421.58  5281.1  423.98
  5337.7  423.48  5445.8     425  5528.6  425.73  5677.1  428.93  5896.3  430.45
  5945.8   432.2  6037.7  433.31  6179.1  437.08  6384.2  440.41  6543.3   444.2
#Mann= 7 ,-1 , 0
  4186.9      .1       0  4628.2     .16       0  4714.1      .1       0
  4789.4     .16       0    4994     .07       0    5000     .16       0
  5445.8     .05       0
Bank Sta=4967.3,5021.2
XS Rating Curve= 0 ,0
Exp/Cntr=0.3,0.1

Type RM Length L Ch R = 1 ,72175   ,1250,1250,1250
BEGIN DESCRIPTION:
SANDERS CREEK 87.0
END DESCRIPTION:
XS GIS Cut Line= 4
      3576645.04     10536764.41      3575547.86     10536788.72
       3575117.3     10536799.14      3573822.34     10538246.85
#Sta/Elev= 30
  3721.9  447.35  4054.9  447.05    4425  429.62  4635.1  422.82  4645.1  422.08
  4655.1  417.09  4685.1  422.65  4805.1  420.47  4905.1  422.34  4935.1  419.14
  4945.1  415.29  4975.1  422.58  4985.2  421.38  4995.2  415.63  5002.2  414.24
  5004.9  413.74  5008.2  414.24  5015.2  419.77  5025.2  422.73  5115.2   421.8
  5135.2  418.25  5320.4  424.77  5419.1  425.52  5581.2  424.27  5752.9  426.49
  5940.3  430.01  6211.5  434.23  6615.2  434.81  6933.7  439.64  7192.4  446.42
#Mann= 7 ,-1 , 0
  3721.9     .16       0  5002.2     .07       0  5008.2     .16       0
  5320.4      .1       0  5419.1     .05       0  5752.9     .16       0
  5940.3     .05       0
Bank Sta=4975.1,5025.2
XS Rating Curve= 0 ,0
Exp/Cntr=0.3,0.1

Type RM Length L Ch R = 1 ,70925   ,897,897,897
BEGIN DESCRIPTION:
SANDERS CREEK 85.0
END DESCRIPTION:
XS GIS Cut Line= 4
      3575292.09     10535491.67      3574935.74     10536125.18
      3574676.33     10536188.02      3573714.51      10537931.1
#Sta/Elev= 30
  4214.4  448.06  4287.4  444.76  4346.6  439.77  4411.6  436.84  4616.9  423.28
  4791.9  419.26  4975.9  420.47  4985.5  419.06  4996.4  413.76  5003.7  412.71
  5006.5  412.21  5009.7  412.71  5032.4  420.24  5037.6  421.05  5075.3  420.54
  5266.2  418.96  5434.6  419.74  5478.2  418.18  5537.8  420.14  5745.7  422.21
  5794.8  424.05  5825.4  426.49  6031.7  432.11  6237.1  431.92  6441.2  432.64
  6531.4  434.75  6614.5  433.74  6620.8  433.67  7003.5  437.39    7199  442.24
#Mann= 10 ,-1 , 0
  4214.4     .05       0  4791.9     .16       0  5003.7     .07       0
  5009.7     .16       0  5075.3     .05       0  5745.7     .16       0
  6237.1      .1       0  6441.2     .05       0  6614.5      .1       0
  6620.8     .05       0
Bank Sta=4985.5,5032.4
XS Rating Curve= 0 ,0
Exp/Cntr=0.3,0.1

Type RM Length L Ch R = 1 ,70028   ,1242,1242,1242
BEGIN DESCRIPTION:
SANDERS CREEK 82.0
END DESCRIPTION:
XS GIS Cut Line= 4
      3575089.49     10534861.67      3574391.61     10535597.75
      3574412.44     10535795.66      3573471.49     10537024.81
#Sta/Elev= 30
  3912.4  456.37  4104.5  448.97  4575.3  427.58  4828.9  421.15  4893.7  419.06
  4977.6   418.6    4991   412.9    4998  411.36  5000.8  410.86    5004  411.36
  5011.1  412.47  5021.1  417.22  5031.2  419.09  5065.5  418.26  5130.9   417.5
  5180.6  417.19  5251.3  420.62  5361.6  420.56  5450.7   419.8  5486.1  417.81
  5679.2  419.76  5828.8  423.44  5928.6   429.6  6150.8  431.98  6520.6  431.25
  6556.4  435.09  6570.5  434.28  6578.7  431.76  6593.3  431.19  6673.7  432.04
#Mann= 8 ,-1 , 0
  3912.4     .16       0  4104.5     .05       0  4828.9     .16       0
    4998     .07       0    5004     .16       0  5065.5     .05       0
  5130.9      .1       0  5361.6     .05       0
Bank Sta=4977.6,5031.2
XS Rating Curve= 0 ,0
Exp/Cntr=0.3,0.1

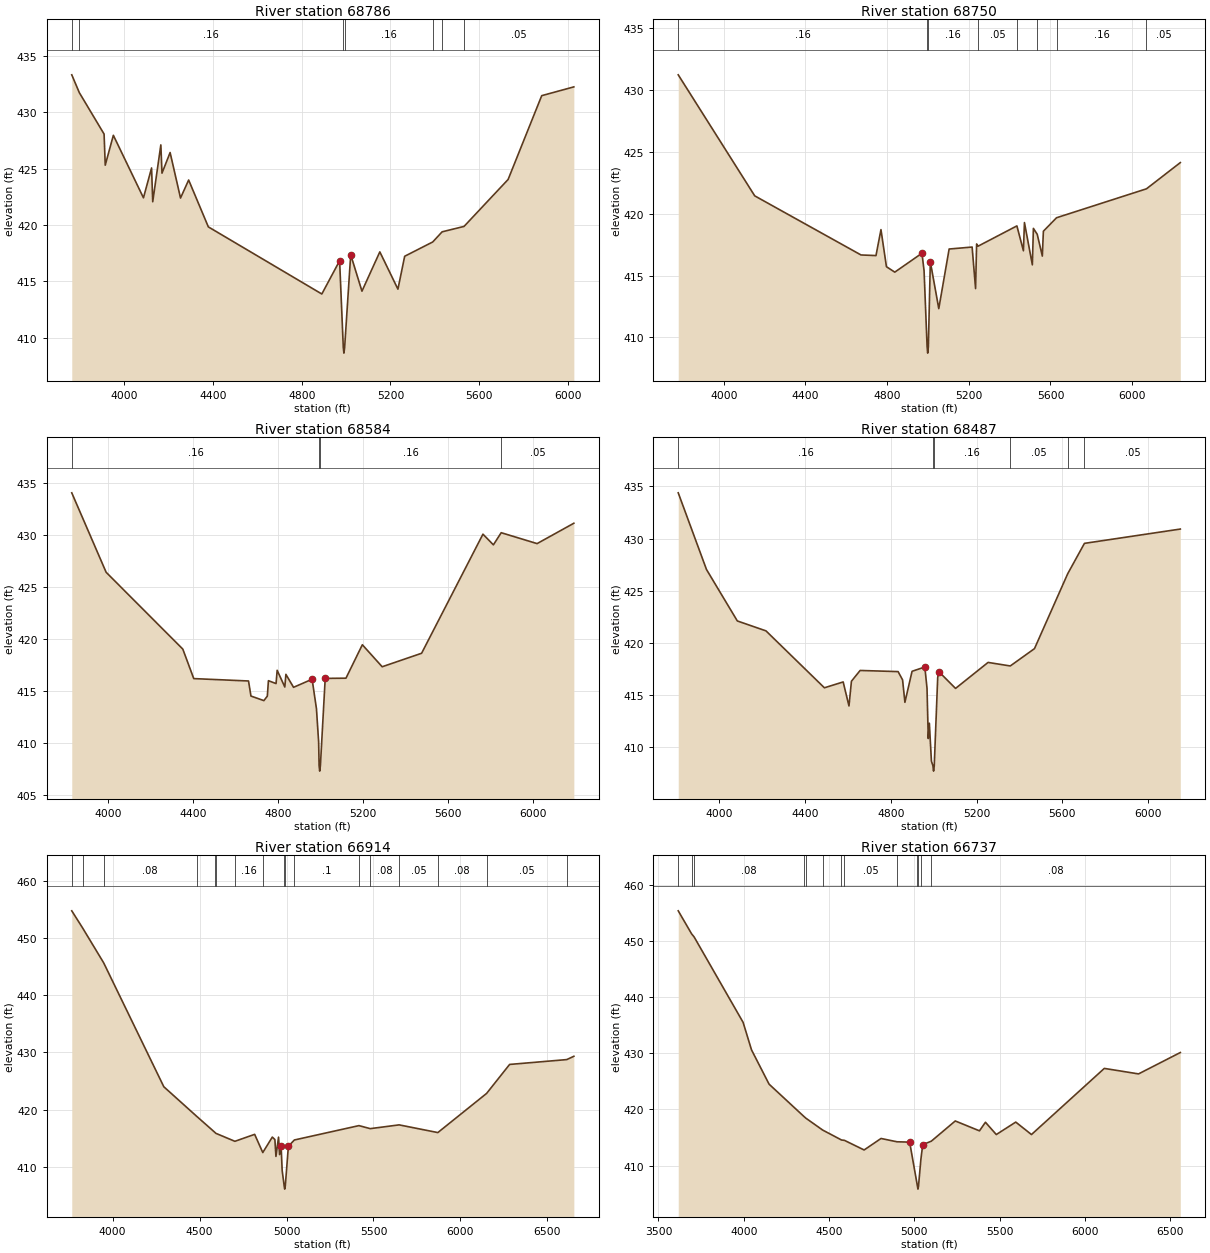
Type RM Length L Ch R = 1 ,68786   ,36,36,36
BEGIN DESCRIPTION:
SANDERS CREEK 81.1
END DESCRIPTION:
XS GIS Cut Line= 3
      3573892.37     10534158.75      3573607.66     10535332.33
      3573434.06     10536373.94
#Sta/Elev= 30
  3763.1  433.34  3797.1  431.76  3908.8  428.08    3914  425.32  3950.6  427.97
  4086.3  422.42  4122.9  425.07  4128.1  422.07  4164.7  427.12  4169.9  424.61
  4206.5  426.44  4253.4   422.4  4290.1     424  4378.8  419.84  4890.5  413.88
  4970.7  416.83  4987.3  409.13    4990  408.63  4993.3  409.13  5020.7  417.37
  5071.4  414.13    5152  417.62  5233.6  414.31    5264  417.23  5390.5   418.5
  5432.8   419.4  5531.6  419.88  5730.4  424.05  5881.9  431.49  6026.7  432.27
#Mann= 7 ,-1 , 0
  3763.1     .05       0  3797.1     .16       0  4987.3     .07       0
  4993.3     .16       0  5390.5     .05       0  5432.8     .16       0
  5531.6     .05       0
Bank Sta=4970.7,5020.7
XS Rating Curve= 0 ,0
Exp/Cntr=0.3,0.1

Type RM Length L Ch R = 1 ,68750   ,166,166,166
BEGIN DESCRIPTION:
SANDERS CREEK 81.0
END DESCRIPTION:
XS GIS Cut Line= 2
      3573829.89     10534165.63       3573302.3     10536567.56
#Sta/Elev= 30
  3776.8  431.24  4151.5  421.45    4672  416.67  4745.4  416.62  4769.8  418.72
  4796.6  415.72  4837.5  415.28  4970.6  416.81  4980.9   415.4  4995.9  409.23
  4998.7  408.73  5001.9  409.23  5011.6  416.12    5053  412.33  5103.7  417.15
  5216.3  417.31  5233.2  413.95  5238.3  417.56  5245.4  417.38  5435.6  419.02
  5467.5  417.01  5472.6  419.29  5511.3  415.87  5516.4  418.82  5535.2  418.34
  5560.2  416.58  5565.3  418.59  5629.8  419.68  6070.2  422.02    6236  424.14
#Mann= 8 ,-1 , 0
  3776.8     .16       0  4995.9     .07       0  5001.9     .16       0
  5245.4     .05       0  5435.6     .16       0  5535.2     .05       0
  5629.8     .16       0  6070.2     .05       0
Bank Sta=4970.6,5011.6
XS Rating Curve= 0 ,0
Exp/Cntr=0.3,0.1

Type RM Length L Ch R = 1 ,68584   ,97,97,97
BEGIN DESCRIPTION:
SANDERS CREEK 80.0
END DESCRIPTION:
XS GIS Cut Line= 2
      3573711.82     10534144.86      3573135.44     10536436.49
#Sta/Elev= 30
  3828.5  434.07  3990.2  426.42  4351.1  419.02  4402.6  416.18  4660.4  415.95
  4671.8   414.5  4732.6  414.06  4748.9  414.49  4754.1  415.98    4790   415.7
  4795.2  416.98  4831.2  415.37  4836.3  416.59  4872.3  415.34  4959.7  416.12
  4980.1  413.28  4990.4  410.07  4992.6  407.77  4995.4  407.27  4998.6  407.77
  5021.3   416.2    5119  416.22  5196.1  419.44  5289.4  417.32    5475  418.62
  5763.7  430.09  5812.9  429.06  5849.6  430.23  6018.5  429.18  6191.5  431.14
#Mann= 4 ,-1 , 0
  3828.5     .16       0  4992.6     .07       0  4998.6     .16       0
  5849.6     .05       0
Bank Sta=4959.7,5021.3
XS Rating Curve= 0 ,0
Exp/Cntr=0.3,0.1

Type RM Length L Ch R = 1 ,68487   ,1573,1573,1573
BEGIN DESCRIPTION:
SANDERS CREEK 79.0
END DESCRIPTION:
XS GIS Cut Line= 3
      3573663.22     10534117.02      3573343.77     10535207.33
      3573087.11     10536386.58
#Sta/Elev= 30
  3808.1  434.38  3939.9  427.04  4083.9  422.11  4217.6  421.16  4490.2  415.71
  4577.8  416.27  4604.9  413.97  4616.4  416.34    4657  417.37  4834.1  417.26
    4855  416.47  4865.9  414.32  4899.3  417.29  4958.9   417.7  4969.1  415.66
  4974.9  410.85    4980  412.32  4989.6  408.69  4996.8  408.23  4999.6  407.73
  5002.8  408.23  5018.9  416.68    5024  417.26  5102.2  415.65  5254.1  418.14
  5357.6   417.8  5470.6  419.46  5625.6  426.63  5703.7  429.54  6151.1  430.91
#Mann= 6 ,-1 , 0
  3808.1     .16       0  4996.8     .07       0  5002.8     .16       0
  5357.6     .05       0  5625.6     .16       0  5703.7     .05       0
Bank Sta=4958.9,5024
XS Rating Curve= 0 ,0
Exp/Cntr=0.3,0.1

Type RM Length L Ch R = 1 ,66914   ,177,177,177
BEGIN DESCRIPTION:
SANDERS CREEK 78.1
END DESCRIPTION:
XS GIS Cut Line= 5
      3573212.02     10533463.45      3572704.19     10534390.57
      3572480.23     10534710.89      3571938.56     10535278.59
      3571855.43      10535928.1
#Sta/Elev= 30
  3764.9  454.82    3827  451.83  3948.5   445.7  4294.3  423.99    4484  418.79
  4585.9  416.05  4593.5  415.83    4703  414.43  4816.7  415.65  4863.4  412.46
  4918.2  415.17    4933  414.74  4939.1  411.78    4954  415.16  4960.1   412.1
  4968.8  413.59  4974.9  409.32  4986.7  406.55  4989.5  406.05  4992.7  406.55
  5010.6  413.56  5044.9  414.66  5416.5  417.18  5481.4  416.65  5647.6  417.31
  5870.1  415.96  6150.5  422.82  6282.9   427.9  6611.6  428.75  6652.3  429.33
#Mann= 17 ,-1 , 0
  3764.9     .08       0    3827      .1       0  3948.5     .08       0
    4484      .1       0  4585.9     .08       0  4593.5     .05       0
    4703     .16       0  4863.4     .05       0  4986.7     .04       0
  4992.7     .05       0  5044.9      .1       0  5416.5     .05       0
  5481.4     .08       0  5647.6     .05       0  5870.1     .08       0
  6150.5     .05       0  6611.6     .08       0
Bank Sta=4968.8,5010.6
XS Rating Curve= 0 ,0
Exp/Cntr=0.3,0.1

Type RM Length L Ch R = 1 ,66737   ,210,210,210
BEGIN DESCRIPTION:
SANDERS CREEK 78.0
END DESCRIPTION:
XS GIS Cut Line= 6
      3573183.78     10533448.23      3572694.21     10534330.16
      3572455.92     10534584.06      3572446.81     10534664.79
      3571901.24     10535245.95      3571800.54     10535943.92
#Sta/Elev= 30
  3616.1  455.41  3694.2  451.32  3709.5  450.74  3996.2  435.53  4045.4  430.63
  4148.4  424.51    4353  418.74  4363.9  418.45  4462.9  416.32  4572.7  414.56
  4590.3  414.49  4705.3  412.78  4804.4  414.83  4897.8  414.24  4972.1  414.18
  5017.9   406.3  5020.6   405.8  5023.9   406.3    5038  411.14  5048.8  413.73
  5099.1  414.35  5239.4  417.95  5381.1  416.19  5416.2  417.72  5479.8  415.53
  5593.8  417.75  5685.9  415.53  6112.7  427.32  6313.3  426.34    6558  430.15
#Mann= 13 ,-1 , 0
  3616.1     .08       0  3694.2      .1       0  3709.5     .08       0
    4353      .1       0  4363.9     .08       0  4462.9     .05       0
  4572.7     .16       0  4590.3     .05       0  4897.8     .08       0
  5017.9     .07       0  5023.9     .08       0    5038      .1       0
  5099.1     .08       0
Bank Sta=4972.1,5048.8
XS Rating Curve= 0 ,0
Exp/Cntr=0.3,0.1

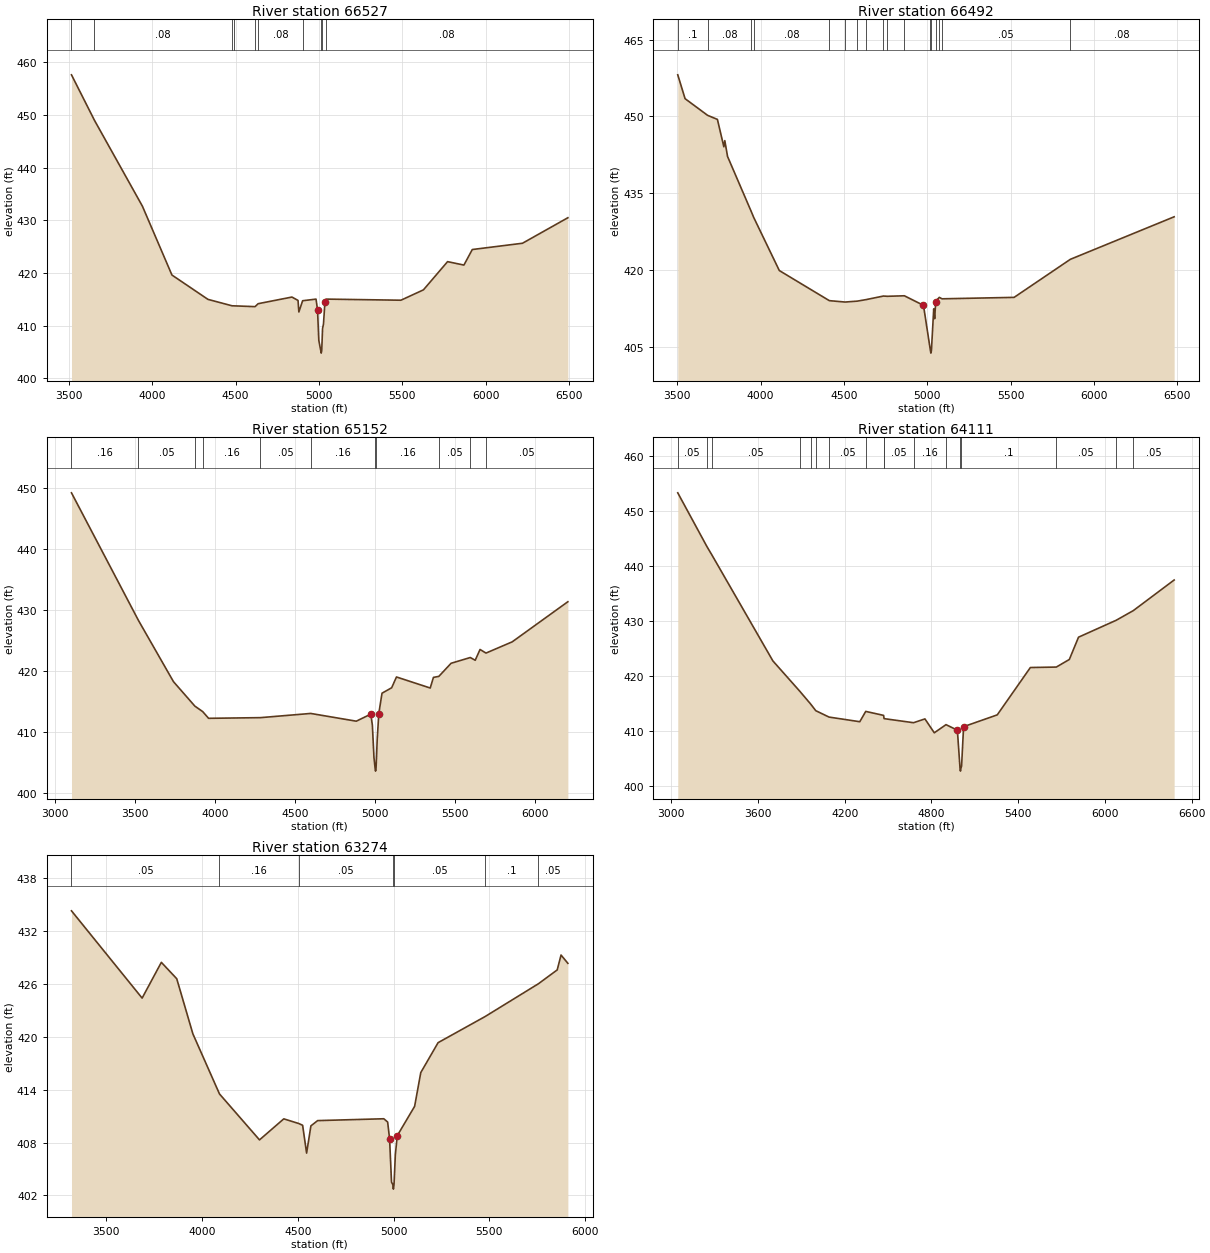
Type RM Length L Ch R = 1 ,66527   ,35,35,35
BEGIN DESCRIPTION:
SANDERS CREEK 77.0
END DESCRIPTION:
XS GIS Cut Line= 6
      3573060.95     10533416.64      3572628.67     10534257.76
      3572391.69     10534525.99      3572295.33     10534544.22
      3571761.48     10535289.01      3571696.38     10535942.66
#Sta/Elev= 30
  3514.4  457.59    3652  448.98  3940.1  432.67  4117.5   419.6  4333.7  414.98
  4478.6  413.76  4490.1  413.75  4616.6   413.6    4635  414.16    4838  415.42
  4874.5  414.78  4879.5  412.59  4902.1  414.72  4982.5  415.03  4991.5  413.02
  4999.3  407.18  5010.8  405.28  5013.6  404.78  5016.8  405.28  5021.7  409.43
  5027.3  410.32  5036.2  414.56  5043.4  415.03  5492.3  414.82  5627.5  416.79
  5772.3  422.14  5870.4  421.49  5920.7  424.44  6222.1  425.63  6494.5  430.47
#Mann= 10 ,-1 , 0
  3514.4      .1       0    3652     .08       0  4478.6     .05       0
  4490.1     .08       0  4616.6     .05       0    4635     .08       0
  4902.1     .16       0  5010.8     .07       0  5016.8     .16       0
  5043.4     .08       0
Bank Sta=4991.5,5036.2
XS Rating Curve= 0 ,0
Exp/Cntr=0.3,0.1

Type RM Length L Ch R = 1 ,66492   ,1340,1340,1340
BEGIN DESCRIPTION:
SANDERS CREEK 77.1
END DESCRIPTION:
XS GIS Cut Line= 6
       3573034.9     10533393.22      3572602.63     10534234.32
      3572365.65     10534502.55      3572269.29     10534520.78
      3571735.44     10535265.57      3571670.46     10535917.95
#Sta/Elev= 30
    3503  458.12  3546.9  453.47  3682.1  450.22  3740.9  449.43  3779.6  444.09
  3785.3  445.29  3801.8   442.2    3944  431.47  3958.4  430.34  4112.4  419.96
  4412.6  414.09  4507.6  413.82  4580.9     414  4634.1   414.3  4737.2  414.99
  4760.6  414.94    4863  415.04  4977.5  413.18  5019.2  404.36  5021.9  403.86
  5025.2  404.36    5039  412.49  5044.5  410.57    5051   413.9  5052.3  414.01
  5072.4  414.73    5089  414.45  5521.4  414.73    5859  422.15  6481.8  430.44
#Mann= 17 ,-1 , 0
    3503      .1       0  3682.1     .08       0    3944     .05       0
  3958.4     .08       0  4412.6     .05       0  4507.6     .08       0
  4580.9     .16       0  4634.1     .08       0  4737.2      .1       0
  4760.6     .08       0    4863     .16       0  5019.2     .07       0
  5025.2     .16       0  5052.3     .05       0  5072.4     .08       0
    5089     .05       0    5859     .08       0
Bank Sta=4977.5,5051
XS Rating Curve= 0 ,0
Exp/Cntr=0.3,0.1

Type RM Length L Ch R = 1 ,65152   ,1041,1041,1041
BEGIN DESCRIPTION:
SANDERS CREEK 76.0
END DESCRIPTION:
XS GIS Cut Line= 3
      3572520.15     10533301.39       3571464.6     10534231.94
      3571325.83     10535918.08
#Sta/Elev= 30
    3104  449.22    3522   428.3  3740.8  418.25  3874.3  414.24  3922.8  413.35
    3960  412.24  4283.9  412.35  4597.4  413.04  4882.1  411.77  4972.9  412.93
  4982.5  411.11  4992.5   405.8  4999.5  404.08  5002.3  403.58  5005.5  404.08
  5012.6  408.71  5022.6  413.03  5042.7  416.36  5102.9  417.25    5133  419.02
  5343.7  417.21  5363.7  418.95  5397.5  419.12  5474.1  421.27  5593.8  422.21
  5624.6  421.76  5654.7  423.53  5691.9  422.94  5855.4  424.78    6203  431.36
#Mann= 11 ,-1 , 0
    3104     .16       0    3522     .05       0  3874.3      .1       0
  3922.8     .16       0  4283.9     .05       0  4597.4     .16       0
  4999.5     .07       0  5005.5     .16       0  5397.5     .05       0
  5593.8     .08       0  5691.9     .05       0
Bank Sta=4972.9,5022.6
XS Rating Curve= 0 ,0
Exp/Cntr=0.3,0.1

Type RM Length L Ch R = 1 ,64111   ,837,837,837
BEGIN DESCRIPTION:
SANDERS CREEK 75.0
END DESCRIPTION:
XS GIS Cut Line= 3
      3572490.07     10533087.89      3570940.09     10534237.88
      3570390.33     10535637.26
#Sta/Elev= 30
  3045.5  453.25  3246.7  443.53  3284.1  441.87  3703.5  422.77  3890.1  417.25
  3965.2  414.93  4000.2  413.74    4092  412.58  4304.5  411.74  4345.7  413.61
  4469.3  412.89  4472.5   412.3  4676.4  411.56  4755.2  412.25  4819.9  409.73
    4901  411.21  4979.6   410.2    4998  403.28  5000.8  402.78    5004  403.28
  5008.7  403.68  5022.5  410.84  5255.3  412.98  5484.5  421.57    5664  421.65
    5754  423.03  5817.6  427.07  6078.3  430.14  6196.5  431.89    6479  437.44
#Mann= 17 ,-1 , 0
  3045.5     .05       0  3246.7     .16       0  3284.1     .05       0
  3890.1      .1       0  3965.2     .16       0  4000.2      .1       0
    4092     .05       0  4345.7      .1       0  4469.3     .16       0
  4472.5     .05       0  4676.4     .16       0    4901      .1       0
    4998     .07       0    5004      .1       0    5664     .05       0
  6078.3     .08       0  6196.5     .05       0
Bank Sta=4979.6,5022.5
XS Rating Curve= 0 ,0
Exp/Cntr=0.3,0.1

Type RM Length L Ch R = 1 ,63274   ,925,925,925
BEGIN DESCRIPTION:
SANDERS CREEK 77.2
END DESCRIPTION:
XS GIS Cut Line= 4
      3571124.24     10532399.83      3570763.14     10533490.11
      3570506.19     10533809.55      3570391.64     10534837.01
#Sta/Elev= 30
  3318.3  434.31  3687.2   424.4  3787.6  428.46    3868   426.6  3952.3  420.34
  4091.2  413.52  4300.2   408.3    4427  410.69  4505.1  410.16  4525.4  409.96
  4546.2   406.8  4568.6  409.89  4603.8  410.49  4949.3   410.7  4969.4  410.33
  4979.5  408.44  4989.6  403.51  4996.6  403.21  4999.4  402.71  5002.6  403.21
  5009.7  406.63  5019.7  408.78  5110.3  412.11  5142.4  415.94  5232.8  419.34
  5478.8  422.31  5756.9  426.03  5854.9   427.6    5875  429.29  5910.6  428.35
#Mann= 7 ,-1 , 0
  3318.3     .05       0  4091.2     .16       0  4505.1     .05       0
  4996.6    .035       0  5002.6     .05       0  5478.8      .1       0
  5756.9     .05       0
Bank Sta=4979.5,5019.7
XS Rating Curve= 0 ,0
Exp/Cntr=0.3,0.1