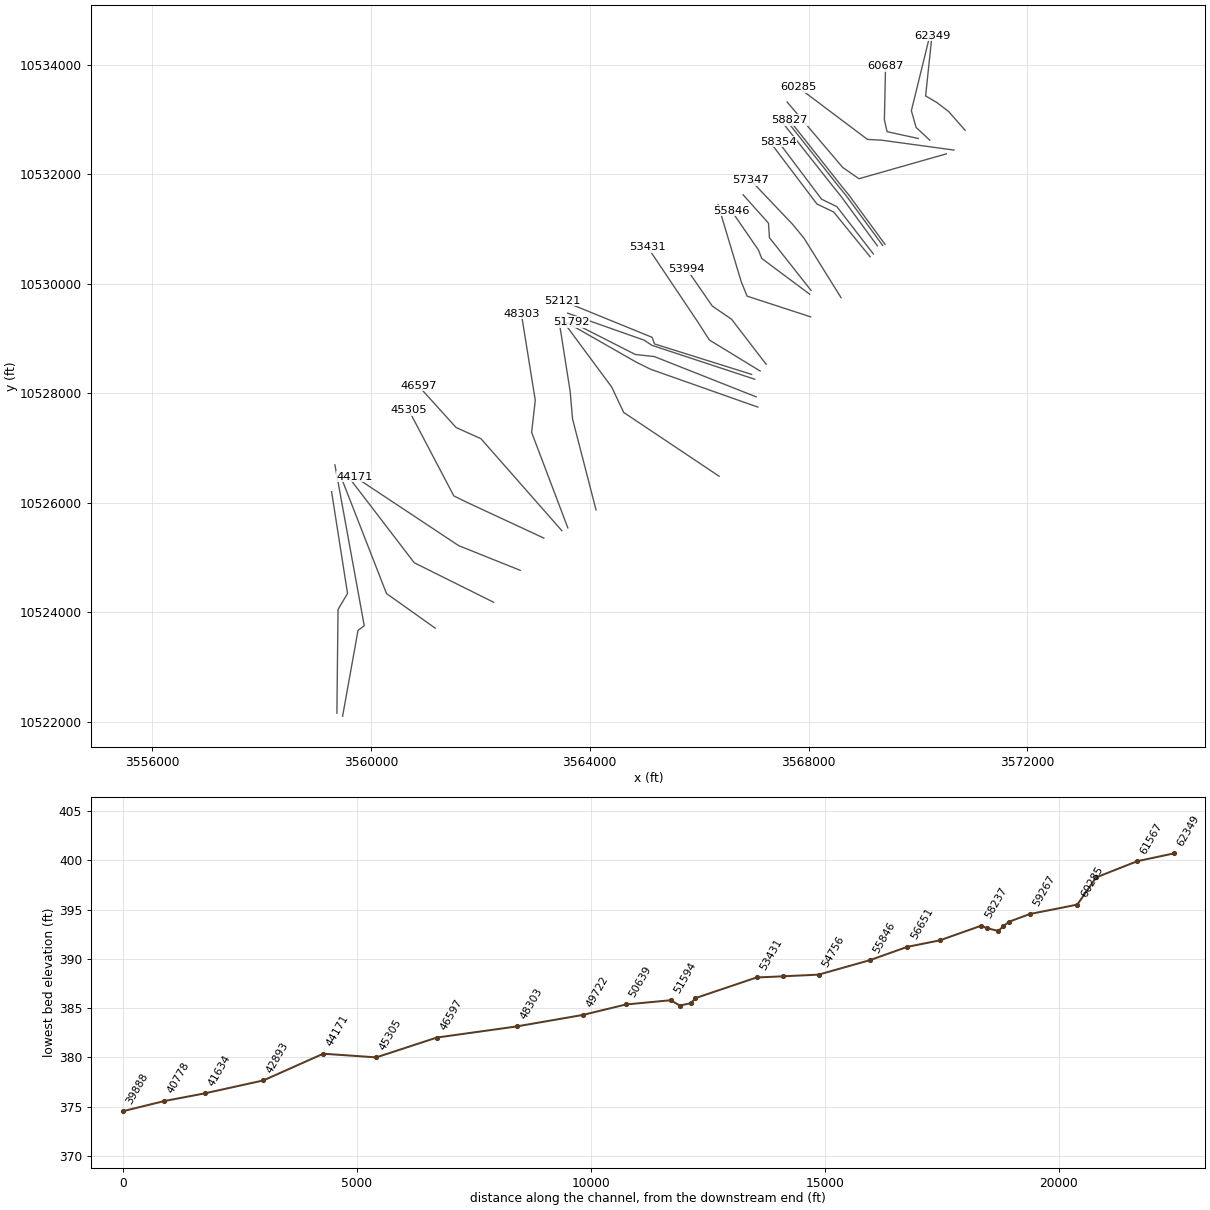
HEC-RAS study SANDERS CREEK.prj: SANDERS CREEK Base Level Engineering

--- SANDERS CREEK.g01 (geometry) --- (continued)

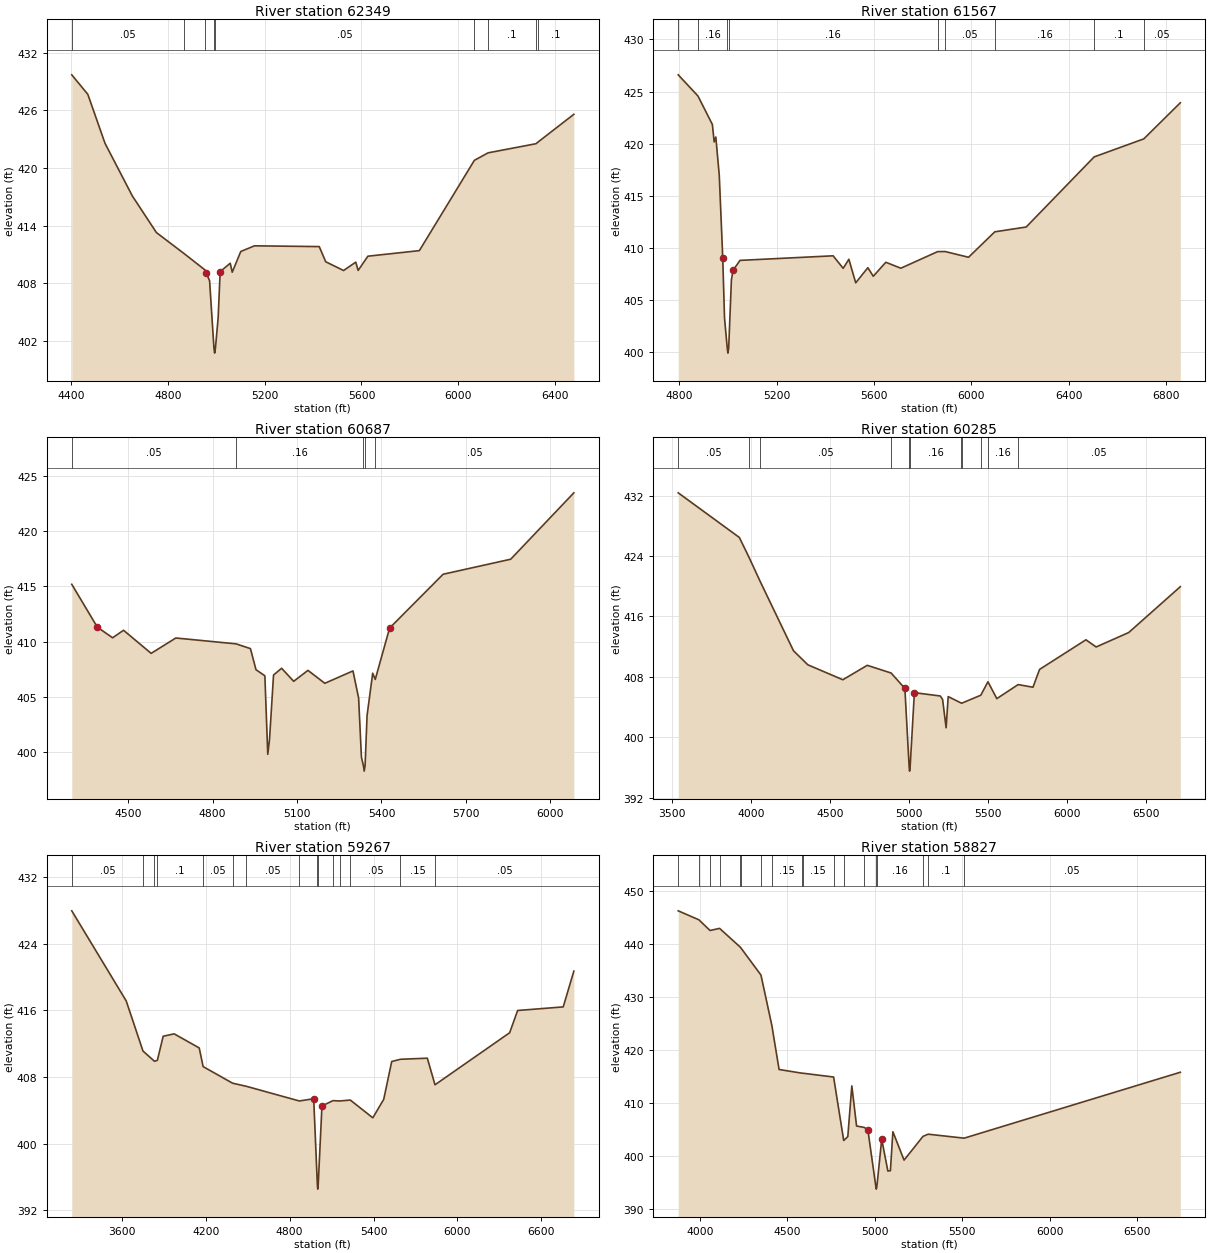
Type RM Length L Ch R = 1 ,62349   ,782,782,782
BEGIN DESCRIPTION:
SANDERS CREEK 76.1
END DESCRIPTION:
XS GIS Cut Line= 5
      3570860.33     10532806.12      3570558.27     10533149.83
      3570339.52      10533316.5      3570138.14     10533434.55
       3570254.3     10534538.63
#Sta/Elev= 30
  4402.1  429.69  4468.5  427.66  4539.6  422.56  4652.6  417.08  4752.2  413.27
  4866.2  411.09  4954.5  409.35  4957.6   409.1  4972.1  408.24  4990.1  401.22
  4992.9  400.72  4996.1  401.22  5007.5  404.43  5015.7   409.2  5057.4  410.08
  5065.6  409.14    5101   411.3  5157.7  411.89  5425.5  411.81  5452.3  410.23
  5526.1  409.32  5576.4  410.19  5586.4  409.33  5626.6  410.81  5839.5  411.39
    6067  420.79  6123.9  421.57    6322  422.52    6328  422.65  6478.3  425.58
#Mann= 9 ,-1 , 0
  4402.1     .05       0  4866.2     .16       0  4954.5     .05       0
  4990.1    .035       0  4996.1     .05       0    6067     .16       0
  6123.9      .1       0    6322     .05       0    6328      .1       0
Bank Sta=4957.6,5015.7
XS Rating Curve= 0 ,0
Exp/Cntr=0.3,0.1

Type RM Length L Ch R = 1 ,61567   ,880,880,880
BEGIN DESCRIPTION:
SANDERS CREEK 75.1
END DESCRIPTION:
XS GIS Cut Line= 4
      3570214.53     10532625.52      3569964.52     10532858.16
      3569877.72     10533163.72      3570212.49     10534526.45
#Sta/Elev= 30
    4796  426.61    4877  424.58  4936.2  421.85  4943.6  420.18  4950.4  420.65
  4964.6  416.96  4978.8  409.09  4986.1  403.31  4997.3  400.43    5000  399.93
  5003.3  400.43  5014.4  406.96  5021.3  407.87  5049.6  408.82  5432.2  409.26
  5473.6  408.06  5496.9  408.93  5525.1  406.67  5574.9  408.12  5597.2   407.3
  5648.7  408.64  5710.4  408.07  5861.4  409.66  5892.3  409.67  5988.5  409.12
  6096.4  411.56  6225.3  412.02  6504.4  418.74  6708.4  420.47  6858.4  423.93
#Mann= 9 ,-1 , 0
    4796     .05       0    4877     .16       0  4997.3     .07       0
  5003.3     .16       0  5861.4      .1       0  5892.3     .05       0
  6096.4     .16       0  6504.4      .1       0  6708.4     .05       0
Bank Sta=4978.8,5021.3
XS Rating Curve= 0 ,0
Exp/Cntr=0.3,0.1

Type RM Length L Ch R = 1 ,60687   ,402,402,402
BEGIN DESCRIPTION:
SANDERS CREEK 74.0
END DESCRIPTION:
XS GIS Cut Line= 4
      3570003.17     10532656.69       3569434.1     10532780.78
      3569384.66     10532997.05      3569405.73     10533975.93
#Sta/Elev= 30
  4299.9  415.19  4390.8  411.31  4444.9  410.35  4483.8  411.03  4581.9  408.94
  4669.5  410.33  4883.5   409.8  4934.5  409.37  4954.3  407.46  4985.8  406.91
  4996.1   399.8  5002.3  401.14  5016.6  406.98  5045.3  407.59  5088.2  406.41
  5138.8   407.4  5198.8  406.23  5298.8  407.35  5318.8   404.9  5328.8  399.54
  5335.8  398.78  5338.6  398.28  5341.8  398.78  5348.8  403.31  5368.8  407.14
  5377.9  406.58  5428.9  411.23  5618.9   416.1    5859  417.46  6083.3  423.47
#Mann= 5 ,-1 , 0
  4299.9     .05       0  4883.5     .16       0  5335.8     .07       0
  5341.8     .16       0  5377.9     .05       0
Bank Sta=4390.8,5428.9
XS Rating Curve= 0 ,0
Exp/Cntr=0.3,0.1

Type RM Length L Ch R = 1 ,60285   ,1018,1018,1018
BEGIN DESCRIPTION:
SANDERS CREEK 73.0
END DESCRIPTION:
XS GIS Cut Line= 4
      3570655.51     10532444.97      3569332.58     10532625.52
      3569075.64     10532639.41      3567805.98     10533593.35
#Sta/Elev= 30
  3538.1  432.37  3925.2  426.46  3983.8  423.95  4058.5  420.58  4268.2  411.46
    4359   409.6  4580.9  407.62  4735.6  409.53  4886.7  408.51  4973.9  406.47
    5001  396.02  5003.7  395.52    5007  396.02    5034  405.91  5198.2  405.47
  5212.8  405.01  5235.1  401.26  5248.2  405.39  5327.2  404.57  5333.7  404.51
  5454.7  405.57  5500.1  407.35  5556.4  405.12  5691.4  406.98  5785.4  406.63
  5827.2  408.99  6120.9  412.91  6185.5  411.96  6391.7  413.87  6718.7  419.94
#Mann= 11 ,-1 , 0
  3538.1     .05       0  3983.8     .08       0  4058.5     .05       0
  4886.7     .16       0    5001     .07       0    5007     .16       0
  5327.2     .05       0  5333.7     .16       0  5454.7     .05       0
  5500.1     .16       0  5691.4     .05       0
Bank Sta=4973.9,5034
XS Rating Curve= 0 ,0
Exp/Cntr=0.3,0.1

Type RM Length L Ch R = 1 ,59267   ,440,440,440
BEGIN DESCRIPTION:
SANDERS CREEK 72.0
END DESCRIPTION:
XS GIS Cut Line= 4
      3570516.62     10532375.53      3568919.39     10531920.66
      3568620.77       10532129.      3567607.01      10533323.3
#Sta/Elev= 30
  3241.4  427.93  3630.8  417.13  3750.8  411.12  3833.1  409.89  3853.5     410
  3895.2  412.89  3973.9  413.18    4153  411.49  4181.1  409.25    4392  407.26
    4490  406.89  4869.2  405.13    4972   405.4  4998.2  395.06    5001  394.56
  5004.2  395.06  5030.9  404.53  5109.9  405.17  5157.3  405.13  5233.9  405.24
  5394.9  403.11  5472.9  405.33  5530.1  409.86  5592.3  410.13  5784.8  410.26
  5839.6  407.07  6373.6  413.31  6430.7  415.98  6756.9  416.41  6832.8   420.7
#Mann= 15 ,-1 , 0
  3241.4     .05       0  3750.8     .08       0  3833.1     .05       0
  3853.5      .1       0  4181.1     .05       0    4392      .1       0
    4490     .05       0  4869.2     .16       0  4998.2     .07       0
  5004.2     .16       0  5109.9     .05       0  5157.3     .16       0
  5233.9     .05       0  5592.3     .15       0  5839.6     .05       0
Bank Sta=4972,5030.9
XS Rating Curve= 0 ,0
Exp/Cntr=0.3,0.1

Type RM Length L Ch R = 1 ,58827   ,129,129,129
BEGIN DESCRIPTION:
SANDERS CREEK 71.2
END DESCRIPTION:
XS GIS Cut Line= 4
      3569397.08     10530720.42      3568726.93     10531633.62
      3568601.93      10531786.4      3567647.06     10532994.74
#Sta/Elev= 30
  3876.2  446.26  3994.2  444.57    4058  442.55  4112.5  442.95  4230.8  439.42
  4234.6  439.26  4349.1  434.15  4411.2  424.68  4452.7  416.34  4585.6  415.63
  4587.8  415.64  4764.4  414.92  4822.2  402.95  4845.5  403.68  4868.6  413.25
  4895.7  405.68  4940.4  405.41  4960.5  404.91  5005.8  394.28  5008.5  393.78
  5011.8  394.28  5039.4   403.2  5074.6  397.19    5089  397.25  5103.3   404.6
  5167.2  399.25  5275.5  403.73    5305  404.14  5510.6  403.39  6746.4  415.82
#Mann= 18 ,-1 , 0
  3876.2     .05       0  3994.2     .08       0    4058     .05       0
  4112.5     .08       0  4230.8      .1       0  4234.6     .08       0
  4349.1      .1       0  4411.2     .15       0  4585.6      .1       0
  4587.8     .15       0  4764.4      .1       0  4822.2     .05       0
  4940.4     .16       0  5005.8     .07       0  5011.8     .16       0
  5275.5     .05       0    5305      .1       0  5510.6     .05       0
Bank Sta=4960.5,5039.4
XS Rating Curve= 0 ,0
Exp/Cntr=0.3,0.1

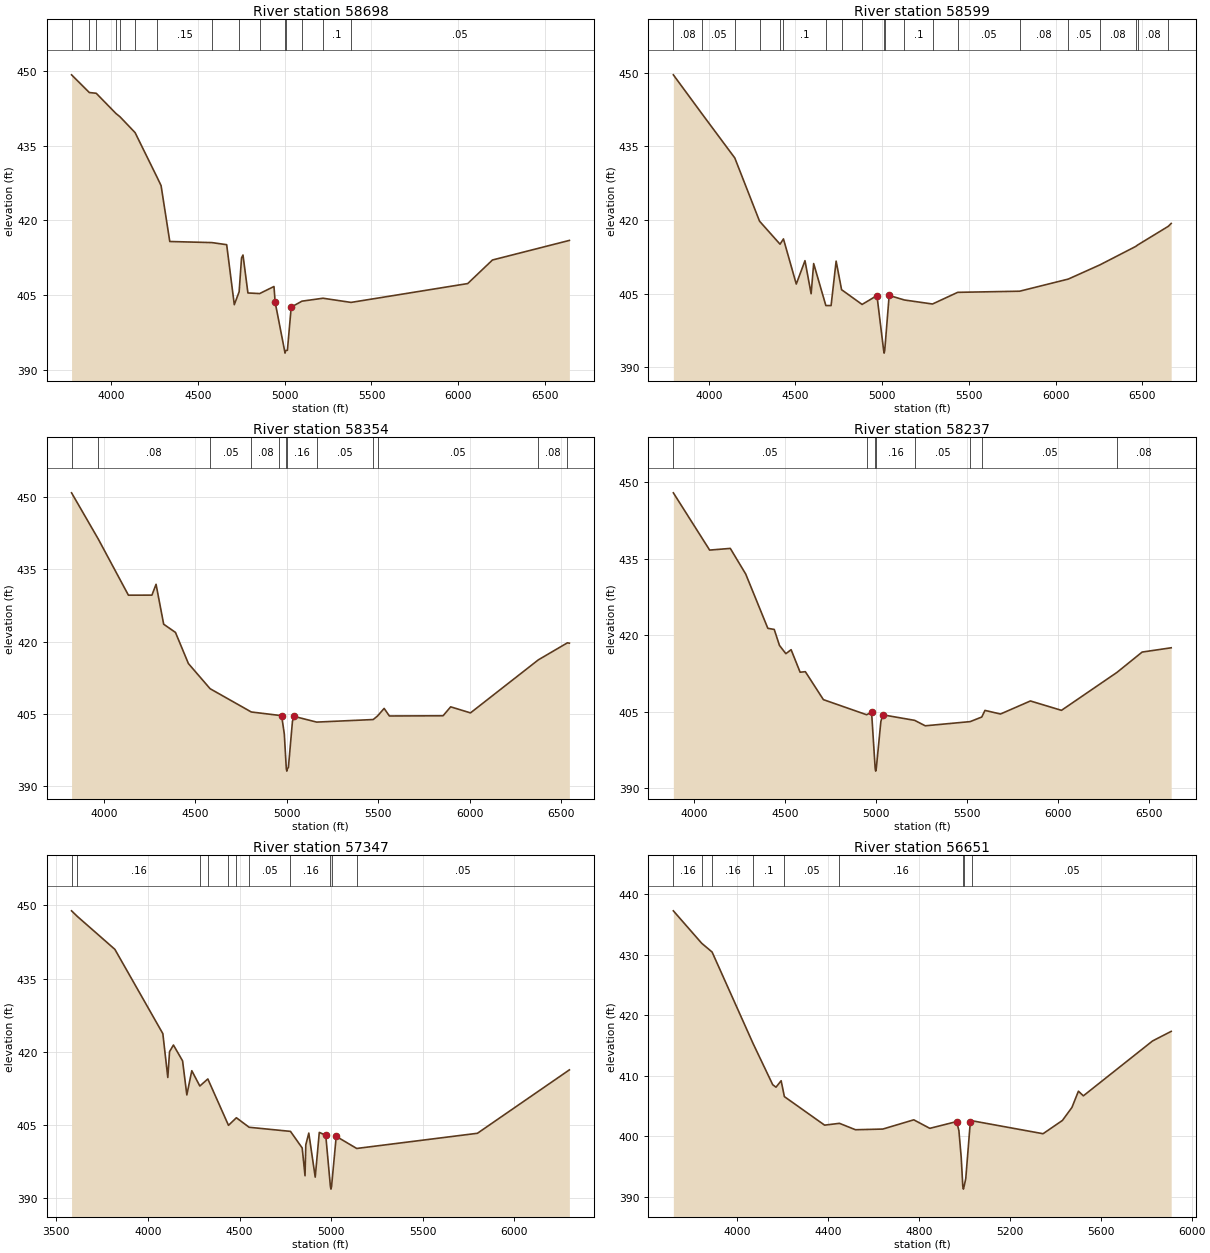
Type RM Length L Ch R = 1 ,58698   ,99,99,99
BEGIN DESCRIPTION:
SANDERS CREEK 71.1
END DESCRIPTION:
XS GIS Cut Line= 4
      3569353.43     10530701.89      3568683.27     10531615.11
      3568558.27     10531767.89      3567603.42     10532976.22
#Sta/Elev= 30
  3770.8  449.27  3873.3  445.71    3913  445.56  4027.4  441.47  4049.9  440.84
  4137.1  437.65  4263.9  428.67  4286.9     427  4337.1  415.75  4579.7  415.53
  4665.1  415.11  4709.1  403.04    4737  405.65  4750.8  412.45  4759.2  413.03
  4787.6   405.4  4855.3  405.28  4937.8   406.7  4944.6  403.55    4999   393.8
  5001.7   393.3    5005   393.8  5015.3  393.88  5037.2  402.56  5099.1  403.75
  5220.4  404.34  5382.2   403.5  6054.8  407.29  6197.5  412.03    6641  415.97
#Mann= 15 ,-1 , 0
  3770.8     .05       0  3873.3     .08       0    3913     .05       0
  4027.4     .08       0  4049.9     .05       0  4137.1     .08       0
  4263.9     .15       0  4579.7      .1       0    4737     .05       0
  4855.3     .16       0    4999     .07       0    5005     .16       0
  5099.1     .05       0  5220.4      .1       0  5382.2     .05       0
Bank Sta=4944.6,5037.2
XS Rating Curve= 0 ,0
Exp/Cntr=0.3,0.1

Type RM Length L Ch R = 1 ,58599   ,245,245,245
BEGIN DESCRIPTION:
SANDERS CREEK 71.0
END DESCRIPTION:
XS GIS Cut Line= 4
      3569256.19     10530694.97      3568586.05     10531608.16
      3568461.05     10531760.94      3567506.17      10532969.3
#Sta/Elev= 30
  3796.2  449.62  3961.3  441.67  4150.5  432.66  4293.1  419.77  4411.3  415.07
    4431  416.15  4504.9  406.94  4555.1  411.71  4590.6  404.96  4605.2  411.12
  4675.4  402.56  4705.6  402.55  4734.7  411.62  4766.1  405.79  4884.4  402.78
  4970.1  404.59  5008.8  393.35  5011.5  392.85  5014.8  393.35  5040.5  404.62
  5128.3  403.69  5290.4  402.87  5435.4  405.25  5792.7  405.48  6073.5  407.96
  6255.9  410.86  6462.3  414.62  6472.4  414.89  6649.4  418.71  6666.4   419.3
#Mann= 20 ,-1 , 0
  3796.2     .08       0  3961.3     .05       0  4150.5     .08       0
  4293.1      .1       0  4411.3     .15       0    4431      .1       0
  4675.4     .08       0  4766.1     .05       0  4884.4     .16       0
  5008.8     .07       0  5014.8     .16       0  5128.3      .1       0
  5290.4     .08       0  5435.4     .05       0  5792.7     .08       0
  6073.5     .05       0  6255.9     .08       0  6462.3     .05       0
  6472.4     .08       0  6649.4     .05       0
Bank Sta=4970.1,5040.5
XS Rating Curve= 0 ,0
Exp/Cntr=0.3,0.1

Type RM Length L Ch R = 1 ,58354   ,117,117,117
BEGIN DESCRIPTION:
SANDERS CREEK 70.0
END DESCRIPTION:
XS GIS Cut Line= 4
      3569183.25     10530545.69      3568516.61     10531410.25
      3568236.72     10531547.03       3567443.7      10532601.2
#Sta/Elev= 30
  3822.7   450.9  3969.2  441.28  4133.6  429.65  4262.2  429.66  4284.8  431.91
  4326.5  423.62  4390.9  421.92  4461.6  415.46  4580.4  410.23  4805.6   405.4
  4959.3  404.69    4972   404.5  4986.2  400.82  4997.1  393.62  4999.9  393.12
  5003.1  393.62  5008.5  393.87  5030.7  403.46  5039.6  404.49  5162.9   403.3
  5472.3  403.83  5496.2  404.58  5532.1  406.14  5560.7  404.57  5854.3  404.61
  5895.9  406.47  6004.2  405.21  6375.6  416.23  6534.4  419.76  6545.1  419.69
#Mann= 12 ,-1 , 0
  3822.7     .05       0  3969.2     .08       0  4580.4     .05       0
  4805.6     .08       0  4959.3     .16       0  4997.1     .07       0
  5003.1     .16       0  5162.9     .05       0  5472.3     .08       0
  5496.2     .05       0  6375.6     .08       0  6534.4     .05       0
Bank Sta=4972,5039.6
XS Rating Curve= 0 ,0
Exp/Cntr=0.3,0.1

Type RM Length L Ch R = 1 ,58237   ,890,890,890
BEGIN DESCRIPTION:
SANDERS CREEK 69.0
END DESCRIPTION:
XS GIS Cut Line= 4
      3569124.27     10530493.55      3568457.58     10531313.02
      3568152.02     10531458.86      3567343.64     10532527.45
#Sta/Elev= 30
  3887.5  447.97  4086.9  436.74  4200.4  437.07  4285.1  432.04  4406.5   421.4
  4441.7  421.18  4470.4  418.05  4505.6  416.42  4534.4  417.21  4583.9  412.79
  4612.7  412.89  4711.8  407.41    4949  404.45  4976.6  404.93  4996.3  393.89
    4999  393.39  5002.3  393.89  5027.5  403.13  5038.6  404.43  5213.1  403.35
  5271.3  402.28    5518   403.1  5581.9     404  5599.4   405.3  5684.7  404.59
  5849.1  407.15  6019.7  405.31  6324.4  412.75  6462.9  416.74  6622.4  417.58
#Mann= 8 ,-1 , 0
  3887.5     .05       0    4949     .16       0  4996.3     .07       0
  5002.3     .16       0  5213.1     .05       0    5518     .08       0
  5581.9     .05       0  6324.4     .08       0
Bank Sta=4976.6,5038.6
XS Rating Curve= 0 ,0
Exp/Cntr=0.3,0.1

Type RM Length L Ch R = 1 ,57347   ,696,696,696
BEGIN DESCRIPTION:
SANDERS CREEK 68.0
END DESCRIPTION:
XS GIS Cut Line= 4
      3568592.99     10529747.07      3567915.91     10530833.86
      3567704.11      10531090.8      3566942.09     10531891.66
#Sta/Elev= 30
  3582.7   448.9  3613.8  447.77  3819.3  441.01  4081.3  423.74  4108.4  414.76
  4117.9  420.05  4139.1  421.41    4189  418.17  4212.3  411.19  4239.4  416.15
  4283.3  413.01    4327  414.46  4439.8  404.96  4482.9  406.51  4552.6  404.56
  4778.3  403.72  4842.4  400.32  4857.8  394.63    4862  400.97  4878.4  403.37
  4913.5  394.35  4935.7  403.51  4970.9  402.93  4996.6  392.39  4999.3  391.89
  5002.6  392.39  5028.2   402.7    5140  400.22  5799.4  403.33  6301.6  416.32
#Mann= 11 ,-1 , 0
  3582.7      .1       0  3613.8     .16       0  4283.3     .05       0
    4327     .16       0  4439.8     .05       0  4482.9     .16       0
  4552.6     .05       0  4778.3     .16       0  4996.6     .07       0
  5002.6     .16       0    5140     .05       0
Bank Sta=4970.9,5028.2
XS Rating Curve= 0 ,0
Exp/Cntr=0.3,0.1

Type RM Length L Ch R = 1 ,56651   ,805,805,805
BEGIN DESCRIPTION:
SANDERS CREEK 67.0
END DESCRIPTION:
XS GIS Cut Line= 4
      3568044.37     10529879.01      3567283.95     10530843.82
      3567266.61     10531108.16      3566802.37     10531627.84
#Sta/Elev= 30
  3719.7  437.29  3844.7  431.91  3890.2  430.47  4070.1  415.36  4156.9  408.51
  4171.3   408.1  4193.9  409.17  4208.2  406.54  4385.1  401.82  4450.5  402.12
  4520.9  401.06  4641.1  401.17  4777.5   402.7    4848  401.29    4966  402.41
    4976  400.92  4986.1  396.51  4993.1  391.73  4995.8  391.23  4999.1  391.73
  5006.1  392.95  5026.1   402.3  5035.7  402.53  5346.3   400.4  5431.5   402.6
  5473.3  404.75  5501.8  407.44  5523.5  406.67  5827.8  415.75  5909.9  417.34
#Mann= 9 ,-1 , 0
  3719.7     .16       0  3844.7     .05       0  3890.2     .16       0
  4070.1      .1       0  4208.2     .05       0  4450.5     .16       0
  4993.1     .07       0  4999.1     .16       0  5035.7     .05       0
Bank Sta=4966,5026.1
XS Rating Curve= 0 ,0
Exp/Cntr=0.3,0.1

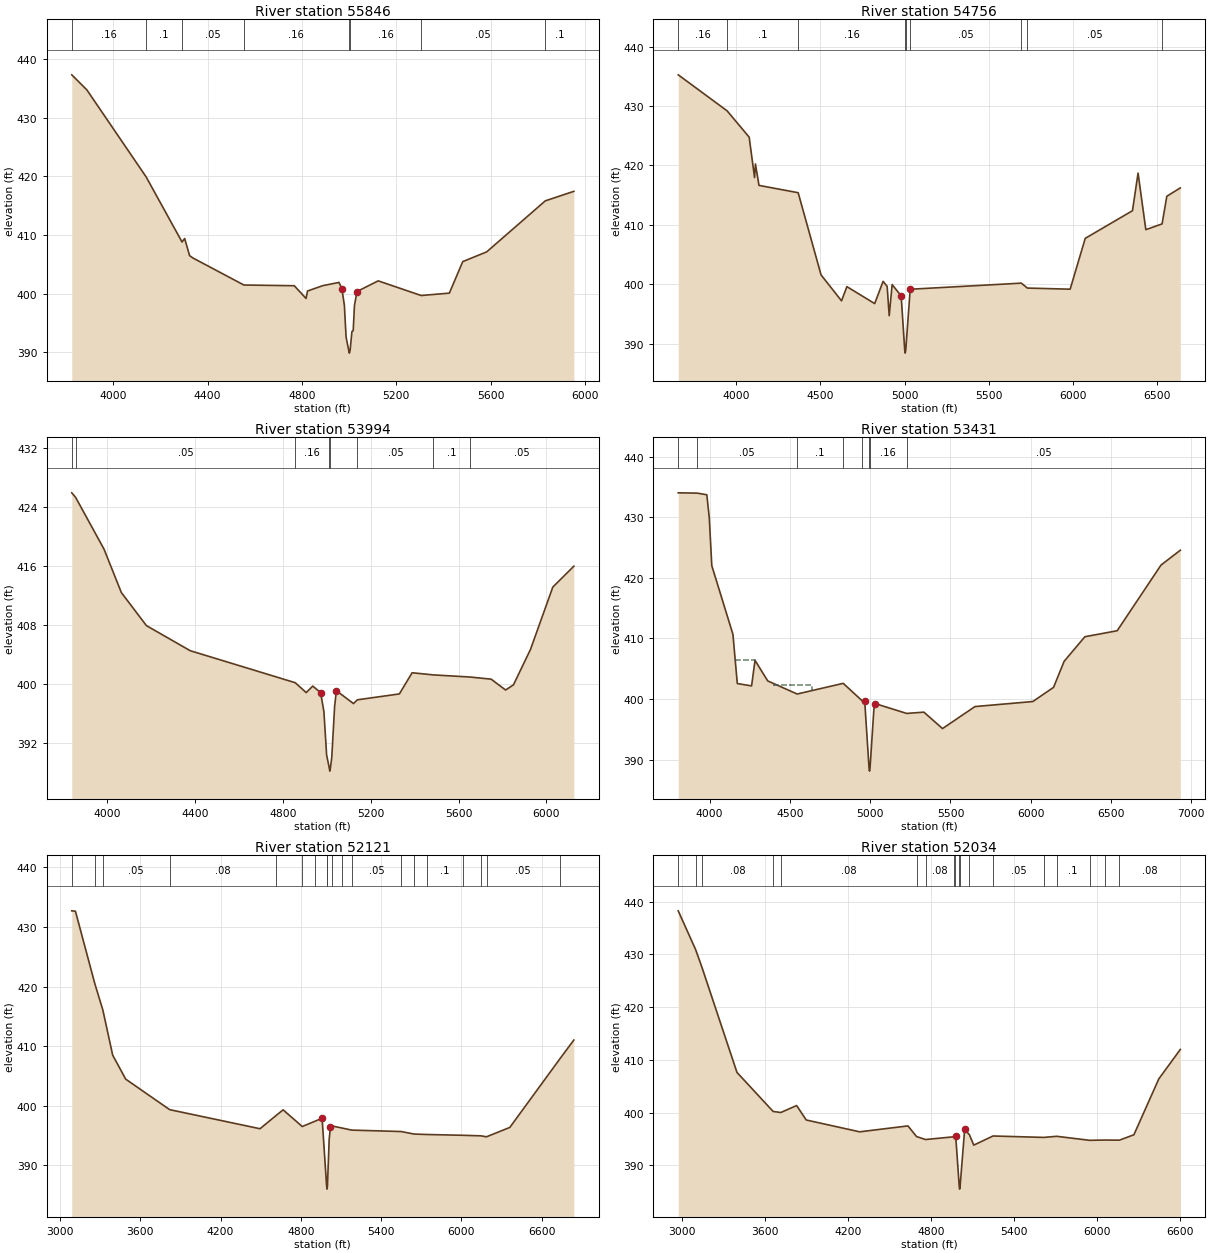
Type RM Length L Ch R = 1 ,55846   ,1090,1090,1090
BEGIN DESCRIPTION:
SANDERS CREEK 66.0
END DESCRIPTION:
XS GIS Cut Line= 4
      3568020.09     10529809.54      3567141.61      10530465.8
      3567084.96     10530614.79        3566590.     10531334.73
#Sta/Elev= 30
  3823.5  437.31  3887.6  434.74  4138.8  419.92  4291.3  408.81  4302.4  409.41
  4323.2  406.49  4337.8  406.08  4553.5  401.48  4767.2  401.36  4817.3  399.19
  4823.5  400.46  4888.1  401.37  4956.9  401.92  4969.1  400.88  4979.8  398.01
  4987.1   392.6  4998.2  390.37  5000.9  389.87  5004.2  390.37  5011.8  393.55
  5017.2  393.68  5022.6  398.01  5033.3  400.37  5123.3  402.19  5305.5  399.69
  5425.1   400.1  5481.9  405.47  5583.4  407.13  5832.1  415.83  5953.1  417.45
#Mann= 8 ,-1 , 0
  3823.5     .16       0  4138.8      .1       0  4291.3     .05       0
  4553.5     .16       0  4998.2     .07       0  5004.2     .16       0
  5305.5     .05       0  5832.1      .1       0
Bank Sta=4969.1,5033.3
XS Rating Curve= 0 ,0
Exp/Cntr=0.3,0.1

Type RM Length L Ch R = 1 ,54756   ,762,762,762
BEGIN DESCRIPTION:
SANDERS CREEK 64.0
END DESCRIPTION:
XS GIS Cut Line= 4
      3568037.48     10529396.34      3566874.54     10529775.42
       3566767.3     10530041.01      3566345.35      10531447.5
#Sta/Elev= 30
  3657.5  435.25  3947.4  429.19  4078.3  424.76  4110.2  417.96  4115.4  420.25
  4136.5  416.64  4368.9  415.41  4504.6  401.58    4626  397.21  4657.9   399.6
  4822.7  396.75  4872.7  400.49  4896.6  399.65  4908.9  394.71  4926.2  399.95
  4979.8  398.05    5001  388.91  5003.7  388.41    5007  388.91  5033.3  399.16
  5692.7  400.19  5728.4  399.36  5982.1  399.17  6071.7  407.73  6351.8  412.38
  6384.9  418.71    6431  409.19  6527.4  410.16  6555.4  414.81  6635.5  416.22
#Mann= 9 ,-1 , 0
  3657.5     .16       0  3947.4      .1       0  4368.9     .16       0
    5001     .07       0    5007     .16       0  5033.3     .05       0
  5692.7     .16       0  5728.4     .05       0  6527.4      .1       0
Bank Sta=4979.8,5033.3
XS Rating Curve= 0 ,0
Exp/Cntr=0.3,0.1

Type RM Length L Ch R = 1 ,53994   ,563,563,563
BEGIN DESCRIPTION:
SANDERS CREEK 63.0
END DESCRIPTION:
XS GIS Cut Line= 4
      3567224.95     10528528.29        3566593.     10529351.22
      3566238.83     10529594.27      3565774.01     10530267.22
#Sta/Elev= 30
  3839.5  425.98  3857.3  425.35  3986.2  418.35  4065.1  412.46  4179.3  407.97
  4378.7  404.57  4856.6  400.23  4906.4  398.89  4936.2  399.77  4972.1  398.89
    4987  396.31  4999.4  390.42    5011  388.74  5013.8  388.24    5017  388.74
  5022.8  390.14  5035.8  397.03  5043.8  399.15  5121.6   397.4  5139.1  397.91
  5330.5  398.71  5388.5  401.58  5485.1  401.29  5652.9     401  5748.3  400.71
  5813.9  399.24  5849.7  399.94  5927.4  404.76  6028.8   413.2  6124.5  416.03
#Mann= 8 ,-1 , 0
  3839.5     .16       0  3857.3     .05       0  4856.6     .16       0
    5011     .07       0    5017     .16       0  5139.1     .05       0
  5485.1      .1       0  5652.9     .05       0
Bank Sta=4972.1,5043.8
XS Rating Curve= 0 ,0
Exp/Cntr=0.3,0.1

Type RM Length L Ch R = 1 ,53431   ,1310,1310,1310
BEGIN DESCRIPTION:
SANDERS CREEK 62.1
END DESCRIPTION:
XS GIS Cut Line= 4
      3567113.85     10528406.76      3566186.75     10528972.75
      3565974.94     10529302.61      3565057.09     10530671.56
#Sta/Elev= 30
  3804.7  434.03  3922.4  433.98  3982.8  433.71  3998.2  429.87  4013.7  422.01
  4145.3  410.69  4172.5  402.57  4261.4  402.18  4282.8  406.39  4362.1     403
  4545.3  400.84    4832   402.6  4950.6  399.71  4965.6  399.77    4993  388.62
  4995.7  388.12    4999  388.62    5023  398.33  5032.2  399.25  5227.2  397.64
  5334.4  397.85  5450.3  395.14  5652.6  398.77  6012.7   399.6  6141.8  401.94
  6207.8  406.24  6336.9  410.29    6538  411.28  6811.1  422.12  6931.1  424.56
#Mann= 8 ,-1 , 0
  3804.7      .1       0  3922.4     .05       0  4545.3      .1       0
    4832     .05       0  4950.6     .16       0    4993     .07       0
    4999     .16       0  5227.2     .05       0
#XS Ineff= 2 ,-1
 4156.25 4283.52  406.43 4395.52 4638.51  402.39
Permanent Ineff=
       F       F
Bank Sta=4965.6,5032.2
XS Rating Curve= 0 ,0
Exp/Cntr=0.3,0.1

Type RM Length L Ch R = 1 ,52121   ,87,87,87
BEGIN DESCRIPTION:
SANDERS CREEK 62.0
END DESCRIPTION:
XS GIS Cut Line= 4
      3566958.35     10528344.84      3565182.35     10528902.12
      3565140.68     10529021.91      3563506.18     10529688.21
#Sta/Elev= 30
  3087.8   432.7  3115.3  432.63  3259.8  420.51  3320.2  416.06  3393.7  408.49
    3491  404.47  3819.8  399.35  4495.1  396.15  4611.9  398.31  4667.7  399.32
  4810.7  396.52    4903  397.38  4959.3  397.91    4993  386.52  4995.7  386.02
    4999  386.52  5012.2  394.42  5021.8  396.47  5035.4  396.61  5109.3  396.26
  5180.8  395.92  5550.1  395.68  5646.1  395.26  5743.9  395.18  6013.2  395.05
  6145.6  394.96  6188.5   394.8  6362.5  396.37  6737.2  407.89  6841.1  411.03
#Mann= 19 ,-1 , 0
  3087.8     .05       0  3259.8     .08       0  3320.2     .05       0
  3819.8     .08       0  4611.9     .05       0  4810.7     .08       0
    4903     .16       0    4993     .07       0    4999     .16       0
  5035.4      .1       0  5109.3     .08       0  5180.8     .05       0
  5550.1      .1       0  5646.1     .05       0  5743.9      .1       0
  6013.2     .05       0  6145.6      .1       0  6188.5     .05       0
  6737.2      .1       0
Bank Sta=4959.3,5021.8
XS Rating Curve= 0 ,0
Exp/Cntr=0.3,0.1

Type RM Length L Ch R = 1 ,52034   ,242,242,242
BEGIN DESCRIPTION:
SANDERS CREEK 61.0
END DESCRIPTION:
XS GIS Cut Line= 4
      3567015.72     10528256.28      3565135.47     10528876.08
      3564994.85     10528969.83      3563595.43     10529464.05
#Sta/Elev= 30
  2971.9  438.26  3097.6  430.92  3143.6  427.55  3396.9  407.64  3658.5  400.24
  3713.9  400.04  3828.6  401.36  3898.2  398.62  4284.6  396.38  4634.1   397.5
  4696.4  395.48  4761.4  394.92  4966.4  395.44  4975.6  395.39  4979.8  395.51
  5005.3  386.02    5008  385.52  5011.3  386.02  5044.3  396.82  5078.5  395.84
  5110.4  393.86  5249.6  395.59  5617.5  395.32  5710.2  395.53  5948.8  394.77
  6057.7  394.82  6164.1   394.8    6269  395.82  6449.2  406.41  6604.8  411.99
#Mann= 18 ,-1 , 0
  2971.9     .08       0  3097.6     .05       0  3143.6     .08       0
  3658.5     .05       0  3713.9     .08       0  4696.4     .05       0
  4761.4     .08       0  4966.4     .16       0  4975.6      .1       0
  5005.3     .07       0  5011.3      .1       0  5078.5     .08       0
  5249.6     .05       0  5617.5     .08       0  5710.2      .1       0
  5948.8     .05       0  6057.7      .1       0  6164.1     .08       0
Bank Sta=4979.8,5044.3
XS Rating Curve= 0 ,0
Exp/Cntr=0.3,0.1

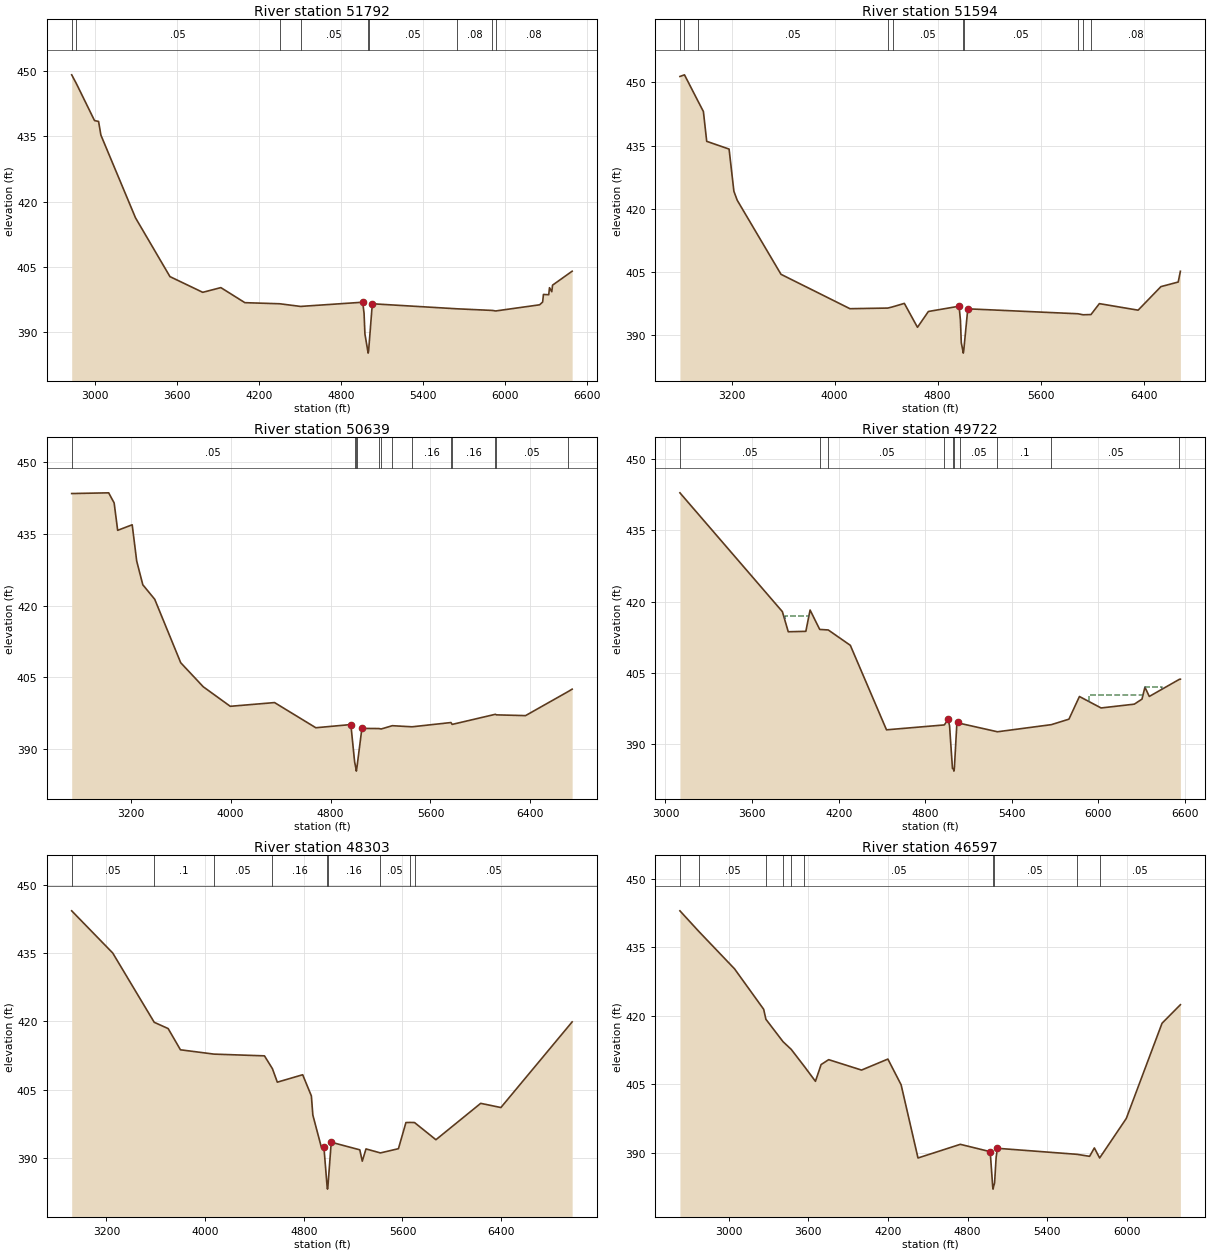
Type RM Length L Ch R = 1 ,51792   ,198,198,198
BEGIN DESCRIPTION:
SANDERS CREEK 60.0
END DESCRIPTION:
XS GIS Cut Line= 4
      3567040.89     10527934.56       3565179.8     10528670.66
      3564832.58     10528708.86      3563662.86     10529303.54
#Sta/Elev= 30
  2828.8  449.03    2863  447.03  2995.9  438.55  3025.6  438.35  3042.6  435.22
    3296  416.26    3548   402.8    3788   399.2  3920.5  400.28  4096.4  396.83
  4350.9  396.58  4503.9  395.97  4958.6  396.93  4968.7  394.39    4975  389.66
  4995.9  385.77  4998.6  385.27  5001.9  385.77  5029.1  396.58  5651.4  395.42
  5908.4  395.05  5931.9  394.93  6253.6  396.34  6275.8  396.97  6281.4  398.71
  6320.3  398.65  6325.9  400.26  6342.6  399.34  6348.2  400.84  6491.7  404.04
#Mann= 9 ,-1 , 0
  2828.8     .08       0    2863     .05       0  4350.9     .08       0
  4503.9     .05       0  4995.9     .03       0  5001.9     .05       0
  5651.4     .08       0  5908.4     .05       0  5931.9     .08       0
Bank Sta=4958.6,5029.1
XS Rating Curve= 0 ,0
Exp/Cntr=0.3,0.1

Type RM Length L Ch R = 1 ,51594   ,955,955,955
BEGIN DESCRIPTION:
SANDERS CREEK 59.0
END DESCRIPTION:
XS GIS Cut Line= 5
      3567072.14     10527747.06      3565113.83     10528438.02
      3564853.41      10528566.5      3563648.55       10529254.
       3563525.4      10529304.7
#Sta/Elev= 30
  2798.6  451.38  2833.9  451.77  2940.3  445.46  2980.9  443.08  3006.6  436.01
  3180.4  434.17  3217.8  424.17  3243.4  422.06  3583.7  404.49  4119.3  396.34
  4413.8  396.49  4451.1  396.78  4541.8   397.6  4643.8  391.93  4728.6  395.68
  4967.2  396.93  4977.5  393.56  4984.1  388.27  4996.8  386.31  4999.6  385.81
  5002.8  386.31  5034.6  396.31  5890.1  395.14  5930.5   394.9  5991.5  394.95
  6056.6  397.54  6357.6  395.99  6534.7  401.57  6669.1  402.66    6686  405.21
#Mann= 10 ,-1 , 0
  2798.6     .05       0  2833.9     .08       0  2940.3     .05       0
  4413.8      .1       0  4451.1     .05       0  4996.8     .03       0
  5002.8     .05       0  5890.1     .08       0  5930.5     .05       0
  5991.5     .08       0
Bank Sta=4967.2,5034.6
XS Rating Curve= 0 ,0
Exp/Cntr=0.3,0.1

Type RM Length L Ch R = 1 ,50639   ,917,917,917
BEGIN DESCRIPTION:
SANDERS CREEK 58.0
END DESCRIPTION:
XS GIS Cut Line= 4
      3566364.51     10526483.17      3564619.73     10527649.83
      3564400.98     10528113.37      3563572.85     10529233.17
#Sta/Elev= 30
  2729.2  443.49  3025.1  443.64  3068.9  441.52  3097.1  435.79  3213.3  436.95
  3249.4  429.35  3298.3  424.39  3393.7  421.35  3601.6  408.07  3781.8  403.04
    3998  398.95  4352.3  399.73  4682.7  394.46  4962.8  395.13  4993.1  387.29
    5004  385.88  5006.8  385.38    5010  385.88  5051.2  394.33  5188.1  394.29
  5205.2   394.2  5294.6  394.89  5452.7  394.66  5763.7  395.55  5773.5  395.16
  6119.4  397.28  6127.1  397.16  6360.4     397  6700.9  402.03  6733.4  402.54
#Mann= 13 ,-1 , 0
  2729.2     .05       0  4993.1     .16       0    5004     .07       0
    5010     .16       0  5188.1     .05       0  5205.2     .16       0
  5294.6     .05       0  5452.7     .16       0  5763.7     .05       0
  5773.5     .16       0  6119.4      .1       0  6127.1     .05       0
  6700.9     .08       0
Bank Sta=4962.8,5051.2
XS Rating Curve= 0 ,0
Exp/Cntr=0.3,0.1

Type RM Length L Ch R = 1 ,49722   ,1419,1419,1419
BEGIN DESCRIPTION:
SANDERS CREEK 57.0
END DESCRIPTION:
XS GIS Cut Line= 4
      3564114.53     10525868.55      3563685.26      10527529.8
      3563642.11     10528030.04      3563447.85     10529264.43
#Sta/Elev= 30
  3100.1  442.87    3810  417.87  3850.7  413.64  3972.6  413.73  4001.9  418.21
  4068.6  414.13  4127.7  414.02  4280.7  410.79  4531.3  393.01  4932.4  394.04
  4958.3  395.25  4968.3  393.86  4988.4  384.86  4995.4  384.82  4998.2  384.32
  5001.4  384.82  5018.5  394.14  5025.3   394.7  5039.3  394.38  5300.2   392.6
  5673.9   394.1  5795.4  395.25  5868.1  400.02  6018.1  397.61  6248.3  398.41
  6301.6  399.47  6321.8  401.98  6352.2  400.03  6560.9  403.64  6567.6  403.66
#Mann= 10 ,-1 , 0
  3100.1     .05       0  4068.6      .1       0  4127.7     .05       0
  4932.4     .16       0  4995.4     .07       0  5001.4     .16       0
  5039.3     .05       0  5300.2      .1       0  5673.9     .05       0
  6560.9     .08       0
#XS Ineff= 3 ,-1
    3825 3993.18  417.06 5937.64 6309.66  400.26 6321.16 6440.48  401.98
Permanent Ineff=
       F       F       F
Bank Sta=4958.3,5025.3
XS Rating Curve= 0 ,0
Exp/Cntr=0.3,0.1

Type RM Length L Ch R = 1 ,48303   ,1706,1706,1706
BEGIN DESCRIPTION:
SANDERS CREEK 55.0
END DESCRIPTION:
XS GIS Cut Line= 4
      3563598.92     10525540.41      3562937.44     10527285.25
      3563004.11      10527871.6      3562749.94     10529451.94
#Sta/Elev= 30
  2918.6  444.27  3251.4     435  3587.6  419.79  3700.6  418.41  3800.2  413.75
  4072.2   412.8  4481.3  412.42    4546  409.59  4585.5  406.64  4791.1  408.27
  4861.5  403.62  4873.4  399.42    4942   392.4  4962.9  392.45  4989.3  383.65
  4992.1  383.15  4995.3  383.65  5022.5  393.45    5254  391.78  5274.1  389.29
  5304.3  391.98  5421.3   391.1  5567.2  392.03    5628  397.77  5660.8   397.8
  5697.8  397.77  5871.1     394  6234.1  401.99  6397.8  401.07  6975.4  419.88
#Mann= 9 ,-1 , 0
  2918.6     .05       0  3587.6      .1       0  4072.2     .05       0
    4546     .16       0  4989.3     .07       0  4995.3     .16       0
  5421.3     .05       0  5660.8      .1       0  5697.8     .05       0
Bank Sta=4962.9,5022.5
XS Rating Curve= 0 ,0
Exp/Cntr=0.3,0.1

Type RM Length L Ch R = 1 ,46597   ,1292,1292,1292
BEGIN DESCRIPTION:
SANDERS CREEK 53.0
END DESCRIPTION:
XS GIS Cut Line= 4
       3563489.5     10525488.39      3562010.36     10527170.66
      3561557.23     10527373.79      3560864.54      10528139.4
#Sta/Elev= 30
  2633.9  442.96  2778.8  438.37  3045.4  430.25  3264.6   421.4  3281.5  419.21
  3410.3  414.31  3471.9  412.63  3571.4  408.87  3654.5  405.63  3697.2   409.3
  3754.2  410.37  4001.8  408.09  4200.1   410.5  4299.7  404.87  4426.9  388.84
  4745.7  391.83  4970.7  390.22  4989.6  382.52  4992.3  382.02  4995.6  382.52
  5003.6  383.36  5015.4     389  5025.5  390.96  5624.4  389.64  5719.3   389.2
  5755.1  391.04  5794.9  388.84  5995.7   397.5  6264.7  418.34    6403   422.4
#Mann= 10 ,-1 , 0
  2633.9      .1       0  2778.8     .05       0  3281.5      .1       0
  3410.3     .05       0  3471.9      .1       0  3571.4     .05       0
  4989.6     .03       0  4995.6     .05       0  5624.4      .1       0
  5794.9     .05       0
Bank Sta=4970.7,5025.5
XS Rating Curve= 0 ,0
Exp/Cntr=0.3,0.1

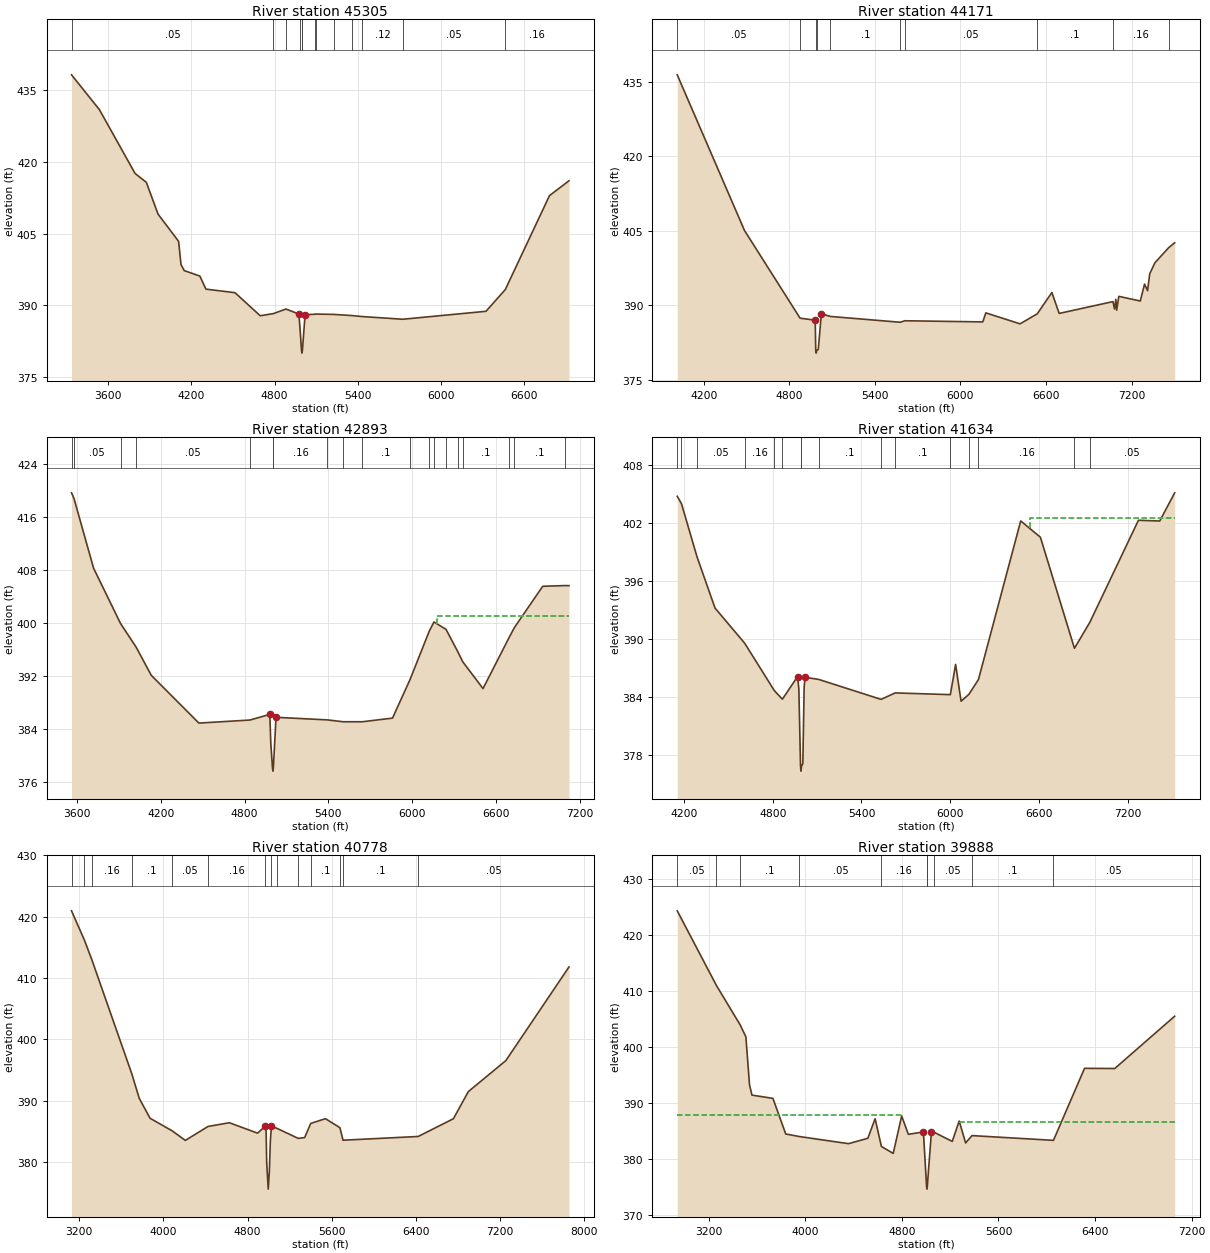
Type RM Length L Ch R = 1 ,45305   ,1134,1134,1134
BEGIN DESCRIPTION:
SANDERS CREEK 51.0
END DESCRIPTION:
XS GIS Cut Line= 4
      3563161.37     10525352.97      3561760.36       10526004.
      3561515.57     10526123.79      3560692.09     10527691.67
#Sta/Elev= 30
  3335.5  438.16  3536.4  430.89  3793.7  417.56    3875   415.7  3959.5  409.06
  4107.8  403.37  4125.2  398.53  4148.1  397.26    4261  396.11  4305.1  393.38
  4514.6  392.64  4696.7  387.82  4792.1  388.27  4882.2  389.22  4975.2  388.19
  4983.4  385.29  4994.7  380.51  4997.5  380.01  5000.7  380.51  5020.3  388.04
  5088.8  388.13  5095.7  388.17  5227.8   388.1  5361.1  387.85  5433.5  387.65
  5725.4  387.09  6325.2  388.75  6464.6  393.29  6783.4  412.92  6923.9  416.02
#Mann= 13 ,-1 , 0
  3335.5     .05       0  4792.1      .1       0  4882.2     .16       0
  4983.4      .1       0  4994.7     .07       0  5000.7      .1       0
  5088.8     .12       0  5095.7      .1       0  5227.8     .12       0
  5361.1      .1       0  5433.5     .12       0  5725.4     .05       0
  6464.6     .16       0
Bank Sta=4975.2,5020.3
XS Rating Curve= 0 ,0
Exp/Cntr=0.3,0.1

Type RM Length L Ch R = 1 ,44171   ,1278,1278,1278
BEGIN DESCRIPTION:
SANDERS CREEK 48.1
END DESCRIPTION:
XS GIS Cut Line= 3
      3562729.61     10524763.41      3561604.59     10525214.81
      3559708.73     10526471.77
#Sta/Elev= 30
    4015  436.45  4486.4  405.09  4876.1  387.42  4982.1  387.02  4985.9  380.88
  4988.7  380.38  4991.9  380.88  5003.6  381.12  5025.2  388.32    5088  387.77
  5578.3   386.6  5610.6   386.9  6156.8  386.67    6178  388.49    6418  386.28
  6538.3  388.29    6641  392.59  6692.2  388.38  7069.1  390.76  7080.2  389.27
  7089.2  391.22  7095.2  389.02  7110.2  391.82  7260.6  390.88  7290.7  394.29
  7311.8  392.96  7326.8  396.35  7362.9  398.57  7460.9  401.66  7501.9  402.61
#Mann= 10 ,-1 , 0
    4015     .05       0  4876.1     .16       0  4985.9     .07       0
  4991.9     .16       0    5088      .1       0  5578.3     .16       0
  5610.6     .05       0  6538.3      .1       0  7069.1     .16       0
  7460.9      .1       0
Bank Sta=4982.1,5025.2
XS Rating Curve= 0 ,0
Exp/Cntr=0.3,0.1

Type RM Length L Ch R = 1 ,42893   ,1259,1259,1259
BEGIN DESCRIPTION:
SANDERS CREEK 50.0
END DESCRIPTION:
XS GIS Cut Line= 3
       3562243.5     10524180.08      3560792.09     10524902.31
      3559611.55     10526443.95
#Sta/Elev= 30
  3560.8  419.61  3578.7  418.74  3718.7  408.25  3911.7  399.92  4024.5  396.32
  4131.6  392.12    4473  384.91  4838.9  385.37  4980.9  386.22  4988.1  381.82
  5000.2  378.17    5003  377.67  5006.2  378.17  5025.6  385.78    5394  385.39
  5506.5  385.11  5643.7  385.11  5859.8  385.66  5985.5  391.48  6123.5  398.79
    6157  400.15  6243.5  399.02  6328.5  395.62  6363.4  394.14    6508  390.11
    6693  397.72  6731.8  399.27  6935.9  405.53  7093.1  405.63  7123.7  405.62
#Mann= 19 ,-1 , 0
  3560.8      .1       0  3578.7     .05       0  3911.7     .08       0
  4024.5     .05       0  4838.9     .16       0  5000.2     .07       0
  5006.2     .16       0    5394      .1       0  5506.5     .16       0
  5643.7      .1       0  5985.5     .16       0  6123.5      .1       0
    6157     .16       0  6243.5      .1       0  6328.5     .16       0
  6363.4      .1       0    6693     .05       0  6731.8      .1       0
  7093.1     .05       0
#XS Ineff= 2 , 0
                         6179.72          401.09
Permanent Ineff=
       F       F
Bank Sta=4980.9,5025.6
XS Rating Curve= 0 ,0
Exp/Cntr=0.3,0.1

Type RM Length L Ch R = 1 ,41634   ,856,856,856
BEGIN DESCRIPTION:
SANDERS CREEK 48.0
END DESCRIPTION:
XS GIS Cut Line= 3
      3561174.05     10523707.85      3560285.14     10524339.81
      3559458.98     10526457.29
#Sta/Elev= 30
  4154.4  404.81  4182.9  404.05  4288.4  398.53  4409.8  393.24  4610.7  389.59
  4810.8  384.69  4865.3   383.8  4968.1  386.14  4976.7  384.86  4988.1  376.85
  4990.9  376.35  4994.1  376.85  5003.7  377.13  5012.4  385.01  5018.5  386.07
  5112.5  385.84  5532.7  383.78  5628.1  384.45  6001.1  384.27  6036.7   387.4
  6073.6  383.59  6126.5   384.3  6191.2  385.84  6476.9  402.26  6610.1  400.57
  6840.2  389.07  6943.9  391.75    7273  402.33  7416.9  402.25    7518  405.17
#Mann= 16 ,-1 , 0
  4154.4     .05       0  4182.9     .08       0  4288.4     .05       0
  4610.7     .16       0  4810.8     .05       0  4865.3     .16       0
  4988.1     .07       0  4994.1     .16       0  5112.5      .1       0
  5532.7     .16       0  5628.1      .1       0  6001.1     .16       0
  6126.5      .1       0  6191.2     .16       0  6840.2      .1       0
  6943.9     .05       0
#XS Ineff= 2 , 0
                         6536.36           402.6
Permanent Ineff=
       F       F
Bank Sta=4968.1,5018.5
XS Rating Curve= 0 ,0
Exp/Cntr=0.3,0.1

Type RM Length L Ch R = 1 ,40778   ,890,890,890
BEGIN DESCRIPTION:
SANDERS CREEK 47.0
END DESCRIPTION:
XS GIS Cut Line= 4
      3559482.58     10522097.75       3559764.6     10523666.17
      3559878.41     10523750.52       3559342.1     10526691.69
#Sta/Elev= 30
  3128.5  420.93  3249.8   416.2  3320.2  413.02  3700.4   394.4  3771.6  390.38
  3874.2  387.13  4084.3  385.08  4209.5  383.52  4424.6  385.79  4627.2   386.4
  4895.4   384.7  4966.5   385.8  4976.7  385.06  4982.1  379.91  4996.8  375.58
  5007.2  378.38  5017.3  383.56  5027.5  385.87  5083.8  385.45  5281.8  383.85
  5342.6  383.98  5400.6  386.29  5540.4  387.06  5677.9  385.59  5707.3  383.55
  6421.1  384.16  6755.5  387.05  6897.9  391.48  7253.6  396.52  7853.4  411.78
#Mann= 14 ,-1 , 0
  3128.5     .16       0  3249.8     .05       0  3320.2     .16       0
  3700.4      .1       0  4084.3     .05       0  4424.6     .16       0
  4966.5     .05       0  5027.5      .1       0  5083.8      .1       0
  5281.8     .05       0  5400.6      .1       0  5677.9     .05       0
  5707.3      .1       0  6421.1     .05       0
Bank Sta=4966.5,5027.5
XS Rating Curve= 0 ,0
Exp/Cntr=0.3,0.1

Type RM Length L Ch R = 1 ,39888   ,659,659,659
BEGIN DESCRIPTION:
SANDERS CREEK 45.1
END DESCRIPTION:
XS GIS Cut Line= 4
      3559378.41     10522153.33      3559399.25     10524049.14
      3559572.86      10524340.8      3559281.19     10526201.94
#Sta/Elev= 30
  2939.9  424.24    3264  410.92  3460.3   403.9  3508.2  401.74  3538.3   393.2
  3558.3  391.33  3732.1  390.75  3838.3  384.39  3951.1  383.93  4358.3  382.66
  4518.3  383.62  4578.3  387.11  4630.6  382.16  4728.3  380.92  4798.3   387.6
  4853.7  384.33  4978.4  384.75  5004.5  375.04  5007.3  374.54  5010.5  375.04
  5044.5  384.72  5068.1  384.68    5217  383.06  5274.6   386.7  5327.9  382.79
  5380.9   384.1  6055.2  383.25  6312.6  396.11  6562.8  396.08  7059.1  405.42
#Mann= 10 ,-1 , 0
  2939.9     .05       0    3264     .16       0  3460.3      .1       0
  3951.1     .05       0  4630.6     .16       0  5004.5     .07       0
  5010.5     .16       0  5068.1     .05       0  5380.9      .1       0
  6055.2     .05       0
#XS Ineff= 2 , 0
         4798.86  387.72 5279.55           386.6
Permanent Ineff=
       F       F
Bank Sta=4978.4,5044.5
XS Rating Curve= 0 ,0
Exp/Cntr=0.3,0.1