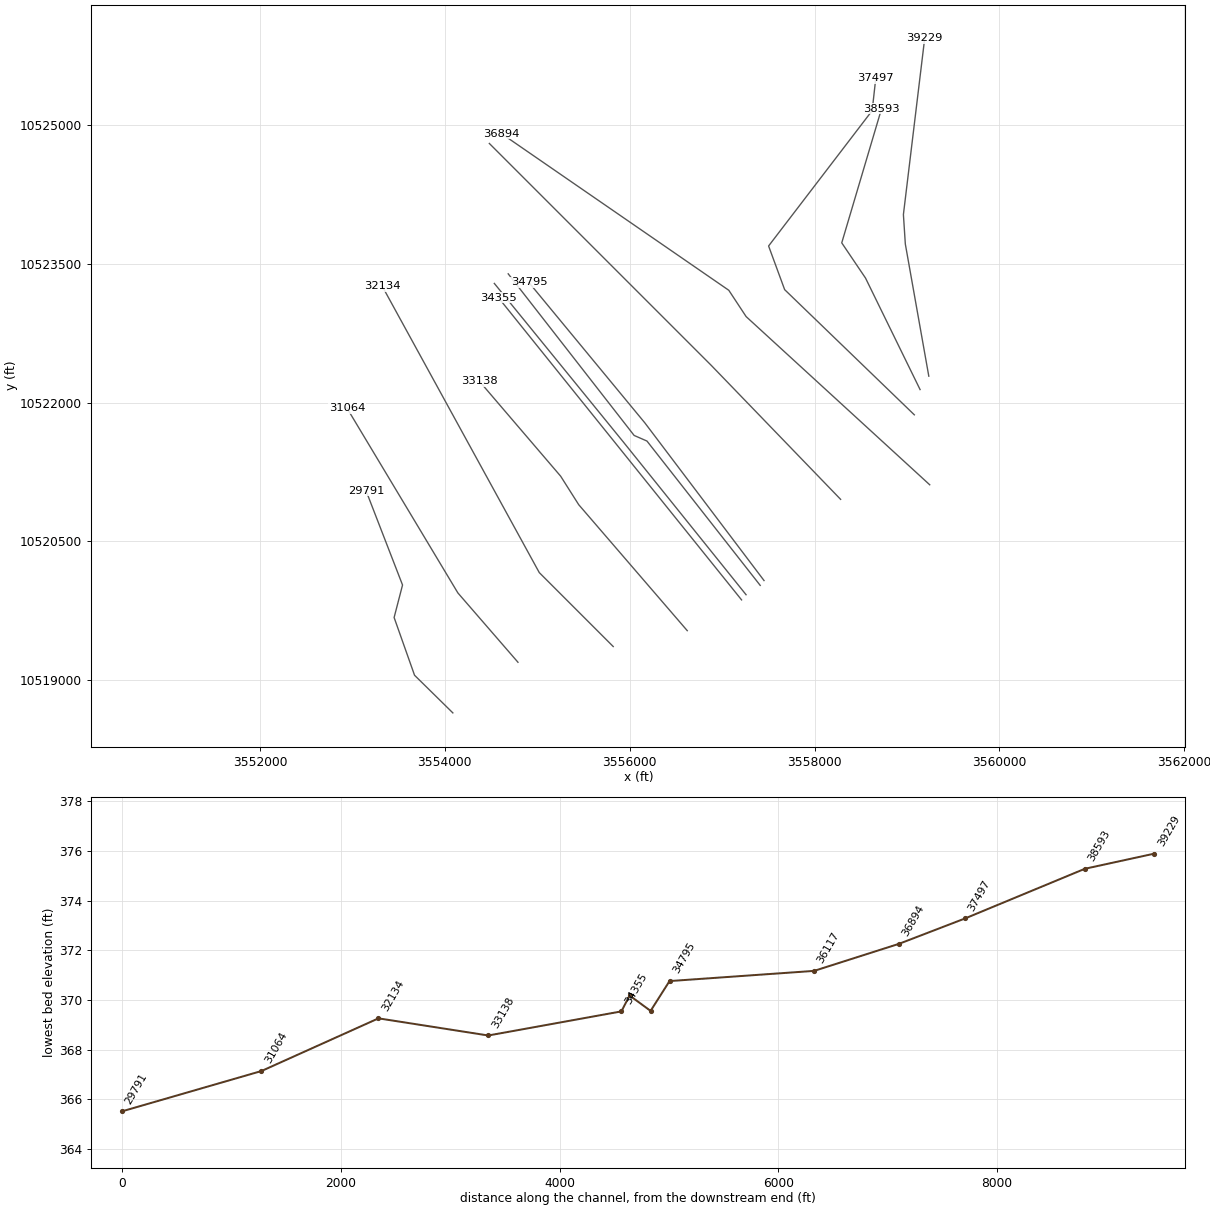
HEC-RAS study SANDERS CREEK.prj: SANDERS CREEK Base Level Engineering

--- SANDERS CREEK.g01 (geometry) --- (continued)

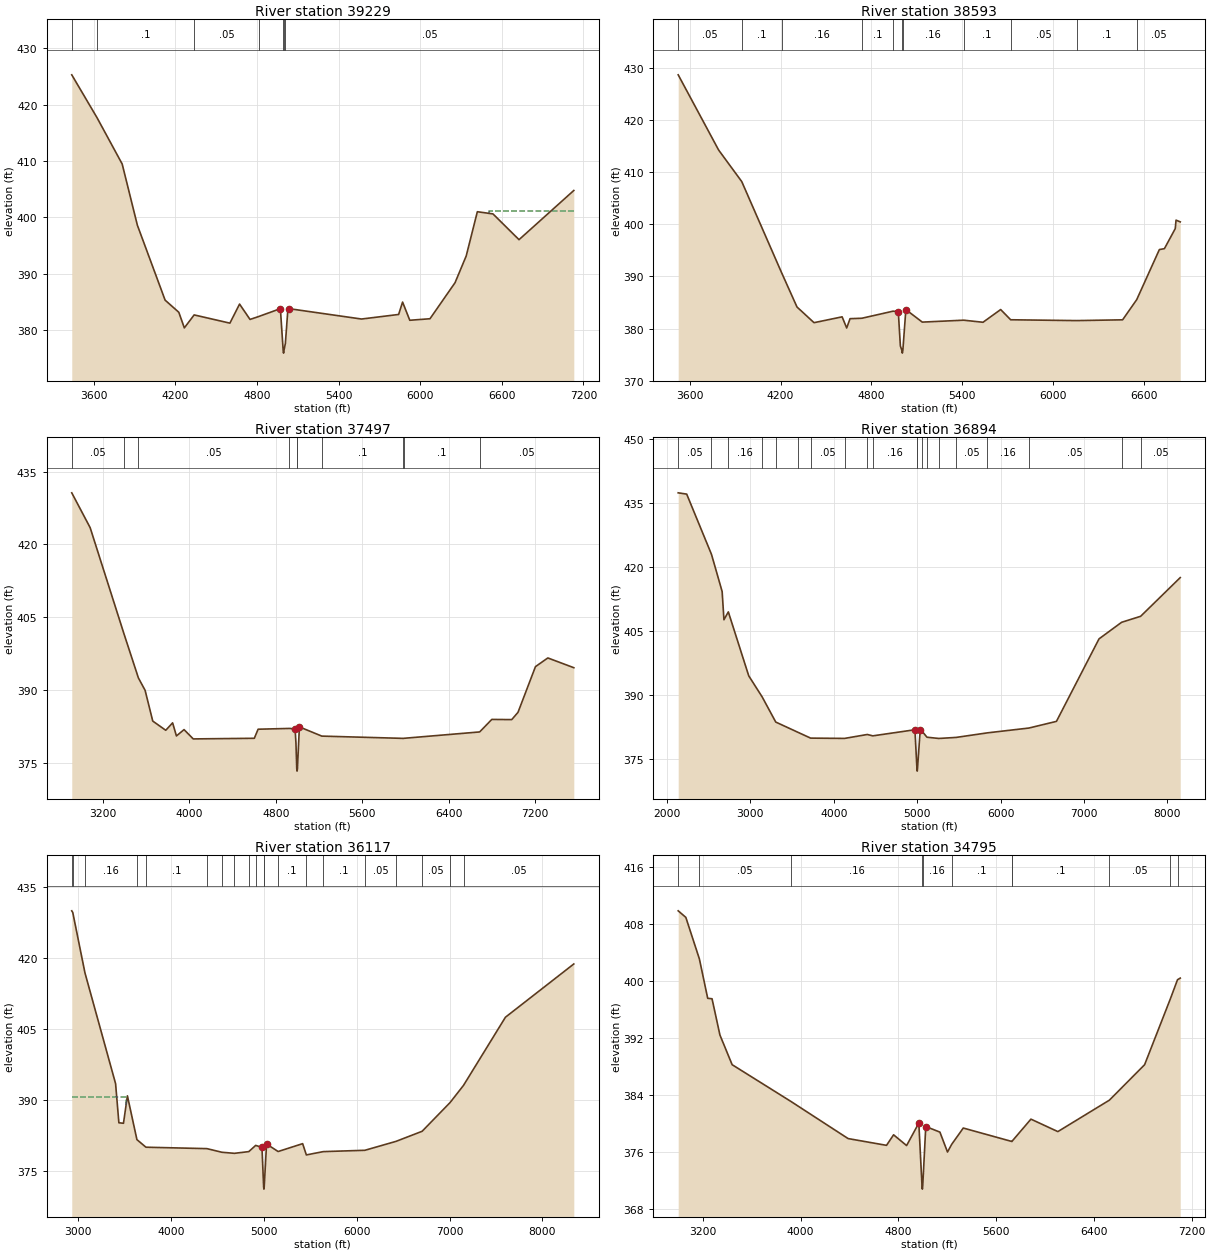
Type RM Length L Ch R = 1 ,39229   ,636,636,636
BEGIN DESCRIPTION:
SANDERS CREEK 45.0
END DESCRIPTION:
XS GIS Cut Line= 4
      3559236.48     10522286.65      3558982.58      10523715.8
      3558961.75     10524035.25       3559192.1     10525941.62
#Sta/Elev= 30
  3437.6  425.27  3624.2  417.63  3808.3  409.45    3920  398.59  4124.1  385.29
  4224.7  383.14  4265.4  380.37  4337.6  382.67  4600.5  381.21  4671.6  384.59
  4748.4  381.87  4811.6  382.38  4971.7  383.78  4992.2  376.39    4995  375.89
  4998.2  376.39  5008.5  377.63  5025.3  383.14  5035.3  383.78  5568.2  381.94
  5841.3  382.75  5870.4  384.95  5923.3  381.72  6071.9  381.99  6256.2  388.39
  6338.2  393.13  6420.2  400.98  6535.2  400.59  6726.6  396.02  7129.5  404.75
#Mann= 7 ,-1 , 0
  3437.6     .05       0  3624.2      .1       0  4337.6     .05       0
  4811.6     .16       0  4992.2     .07       0  4998.2     .16       0
  5008.5     .05       0
#XS Ineff= 2 , 0
                         6502.84          401.09
Permanent Ineff=
       F       F
Bank Sta=4971.7,5035.3
XS Rating Curve= 0 ,0
Exp/Cntr=0.3,0.1

Type RM Length L Ch R = 1 ,38593   ,1096,1096,1096
BEGIN DESCRIPTION:
SANDERS CREEK 43.0
END DESCRIPTION:
XS GIS Cut Line= 4
      3559142.11     10522141.63      3558552.02     10523347.75
      3558294.68     10523728.84      3558725.63     10525181.07
#Sta/Elev= 30
  3523.7  428.67  3790.9  414.24  3943.7  408.19  4207.9  390.65  4308.7  384.13
  4421.2  381.12  4606.9  382.24    4637   380.1  4659.2  381.89  4737.4  381.97
  4943.7  383.33  4978.1  383.24  4991.8  376.65  5002.1  375.78  5004.8  375.28
  5008.1  375.78    5028  383.63  5136.6  381.23  5409.9   381.6  5537.8   381.2
  5654.5  383.64  5720.6  381.68  6155.9  381.52  6460.3  381.67  6553.7  385.55
  6703.3  395.15  6736.5  395.32  6808.2  399.17  6813.4  400.79  6841.1  400.46
#Mann= 11 ,-1 , 0
  3523.7     .05       0  3943.7      .1       0  4207.9     .16       0
  4737.4      .1       0  4943.7     .16       0  5002.1     .07       0
  5008.1     .16       0  5409.9      .1       0  5720.6     .05       0
  6155.9      .1       0  6553.7     .05       0
Bank Sta=4978.1,5028
XS Rating Curve= 0 ,0
Exp/Cntr=0.3,0.1

Type RM Length L Ch R = 1 ,37497   ,603,603,603
BEGIN DESCRIPTION:
SANDERS CREEK 42.0
END DESCRIPTION:
XS GIS Cut Line= 5
      3559079.81     10521868.57      3557677.02     10523222.75
      3557503.41     10523694.97      3558623.87     10525159.44
      3558663.04     10525510.73
#Sta/Elev= 30
  2909.8  430.65  3080.1  423.47  3394.8  401.49  3527.1  392.49  3589.2  389.93
  3659.9   383.6  3780.3   381.7  3843.9  383.23  3879.4  380.53  3949.9  381.84
  4034.7  379.92  4600.7  380.05  4635.9  381.92  4925.9  382.08  4978.1  381.99
  4986.2  379.15  4993.9  373.78  4996.7  373.28  4999.9  373.78  5018.2   382.4
  5225.5   380.5  5981.6  380.03  5988.1  380.05  6688.1  381.36  6800.4  383.94
  6985.3   383.9  7043.4  385.41  7204.9  394.82  7319.5  396.61  7560.1   394.6
#Mann= 10 ,-1 , 0
  2909.8     .05       0  3394.8      .1       0  3527.1     .05       0
  4925.9     .16       0  4993.9     .07       0  4999.9     .16       0
  5225.5      .1       0  5981.6     .16       0  5988.1      .1       0
  6688.1     .05       0
Bank Sta=4978.1,5018.2
XS Rating Curve= 0 ,0
Exp/Cntr=0.3,0.1

Type RM Length L Ch R = 1 ,36894   ,777,777,777
BEGIN DESCRIPTION:
SANDERS CREEK 41.0
END DESCRIPTION:
XS GIS Cut Line= 4
      3559246.46     10521111.65      3557260.36     10522931.08
      3557072.86      10523215.8      3554615.79     10524909.37
#Sta/Elev= 30
    2135  437.43  2236.9  437.13  2534.1  423.02  2661.8  414.32  2683.4  407.71
    2736  409.55  2980.6  394.58  3142.3  389.62  3304.5  383.75  3576.4   381.3
  3722.6  379.99  4129.3  379.92  4401.9  380.84  4467.9  380.52  4972.9  381.95
  4997.4  372.76  5000.2  372.26  5003.4  372.76  5036.6  381.97  5054.6   381.7
  5117.5   380.2  5258.8  379.91  5465.7  380.15  5841.3  381.22  6339.5  382.35
  6669.5  383.91    7180  403.23  7450.5  407.11    7679  408.52  8153.6  417.58
#Mann= 20 ,-1 , 0
    2135     .05       0  2534.1     .05       0    2736     .16       0
  3142.3      .1       0  3304.5     .05       0  3576.4      .1       0
  3722.6     .05       0  4129.3     .16       0  4401.9     .05       0
  4467.9     .16       0  4997.4     .07       0  5003.4     .16       0
  5054.6      .1       0  5117.5     .16       0  5258.8     .16       0
  5465.7     .05       0  5841.3     .16       0  6339.5     .05       0
  7450.5      .1       0    7679     .05       0
Bank Sta=4972.9,5036.6
XS Rating Curve= 0 ,0
Exp/Cntr=0.3,0.1

Type RM Length L Ch R = 1 ,36117   ,1322,1322,1322
BEGIN DESCRIPTION:
SANDERS CREEK 40.0
END DESCRIPTION:
XS GIS Cut Line= 3
      3558282.41     10520954.11      3556882.38     10522404.14
       3554482.4     10524804.13
#Sta/Elev= 30
  2929.4  429.93  2940.5  429.56  3071.9   416.8  3401.6  393.44  3437.1  385.18
  3486.5  385.07    3529  390.87  3631.5  381.62  3728.8  380.02  4385.7  379.72
  4548.1  378.95    4682  378.73  4836.9  379.09  4911.2   380.4  4978.8  379.99
    4997  371.67  4999.8  371.17    5003  371.67  5028.3  380.69    5153  379.11
  5417.2  380.77  5457.3  378.39  5639.9  379.09    6088  379.37  6422.6  381.25
  6704.4  383.38  7004.9  389.43  7150.5  393.07  7602.2  407.46  8339.1  418.71
#Mann= 20 ,-1 , 0
  2929.4      .1       0  2940.5     .05       0  3071.9     .16       0
  3631.5     .05       0  3728.8      .1       0  4385.7     .16       0
  4548.1      .1       0    4682     .16       0  4836.9      .1       0
  4911.2     .16       0    4997     .07       0    5003     .16       0
    5153      .1       0  5457.3     .05       0  5639.9      .1       0
    6088     .05       0  6422.6      .1       0  6704.4     .05       0
  7004.9     .08       0  7150.5     .05       0
#XS Ineff= 2 , 0
         3511.36  390.65
Permanent Ineff=
       F       F
Bank Sta=4978.8,5028.3
XS Rating Curve= 0 ,0
Exp/Cntr=0.3,0.1

Type RM Length L Ch R = 1 ,34795   ,173,173,173
BEGIN DESCRIPTION:
SANDERS CREEK 37.3
END DESCRIPTION:
XS GIS Cut Line= 3
      3557453.99     10520075.66      3556164.95     10521781.06
       3554910.6     10523300.17
#Sta/Elev= 30
  2998.7  409.85  3061.2  408.93    3172   403.1  3240.2  397.56  3275.6   397.5
  3340.1  392.41    3440  388.24  3921.5  383.07    4389  377.86  4703.2  376.91
  4761.1  378.39  4867.6  376.88  4967.5  380.04  4993.6  371.26  4996.4  370.76
  4999.6  371.26  5024.4  379.55  5140.1  378.77  5202.2  375.97  5235.7  377.03
  5331.2  379.34  5729.2  377.45    5731   377.5  5884.9  380.59  6105.1  378.84
  6527.1  383.26  6815.1  388.24    7026   397.5  7084.1  400.17  7106.5   400.4
#Mann= 11 ,-1 , 0
  2998.7     .16       0    3172     .05       0  3921.5     .16       0
  4993.6     .07       0  4999.6     .16       0  5235.7      .1       0
  5729.2     .08       0    5731      .1       0  6527.1     .05       0
    7026     .08       0  7084.1     .05       0
Bank Sta=4967.5,5024.4
XS Rating Curve= 0 ,0
Exp/Cntr=0.3,0.1

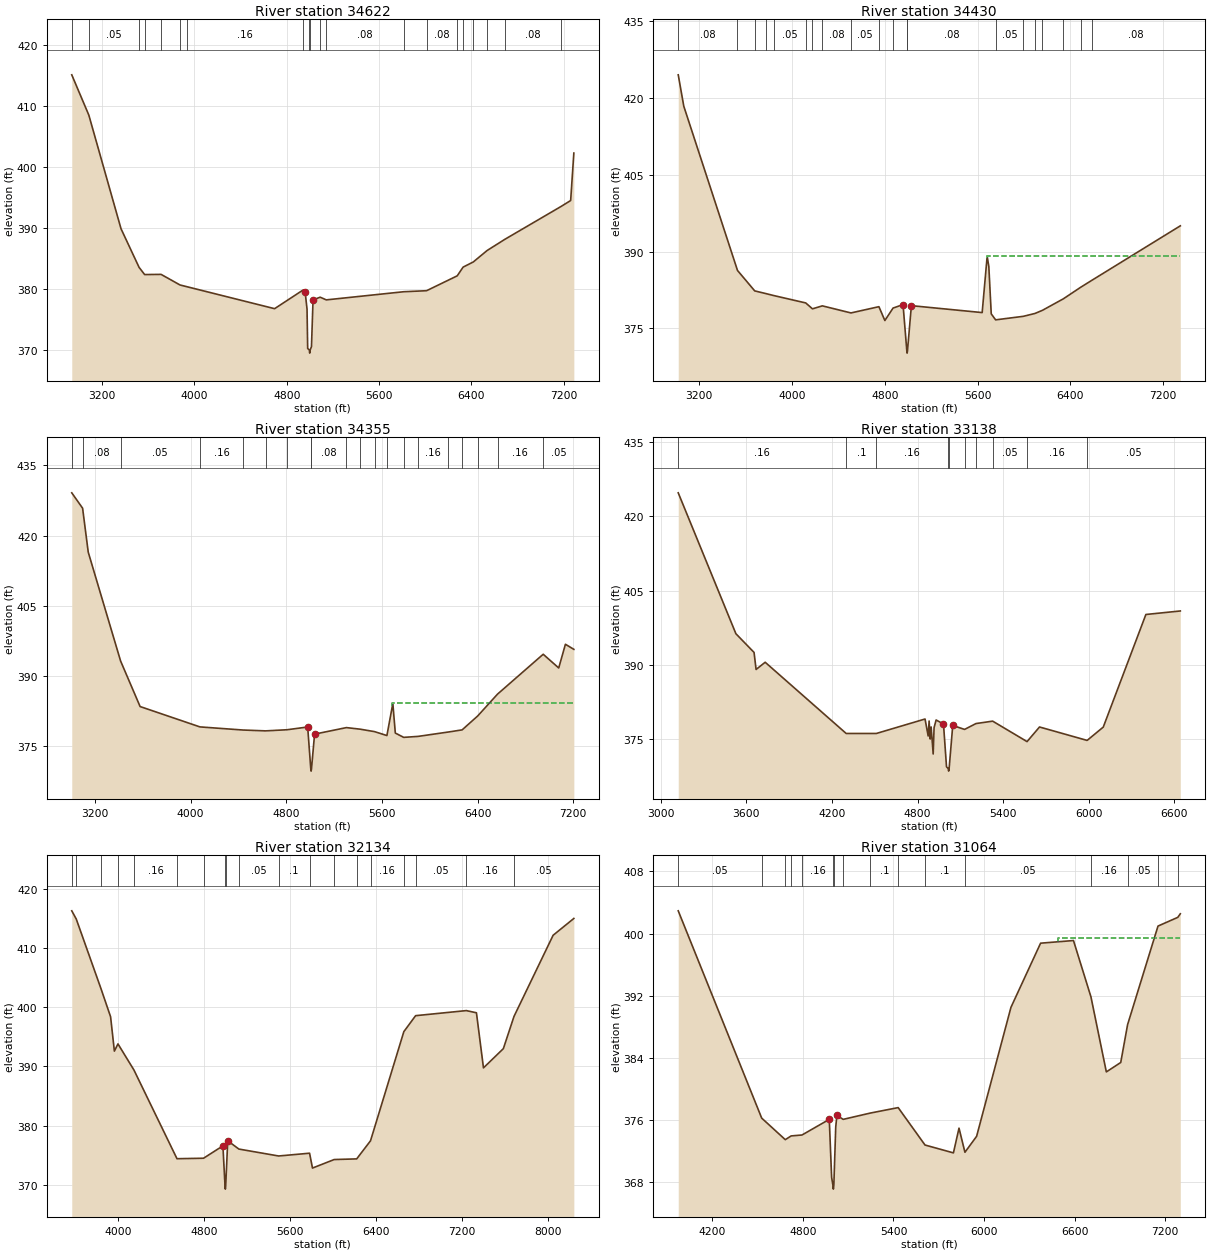
Type RM Length L Ch R = 1 ,34622   ,192,192,192
BEGIN DESCRIPTION:
SANDERS CREEK 37.2
END DESCRIPTION:
XS GIS Cut Line= 4
      3557412.56     10520023.33      3556187.52     10521584.74
      3556048.63      10521645.5      3554686.47     10523393.76
#Sta/Elev= 30
  2936.8  415.08  3084.7  408.49  3363.7  389.91  3520.3  383.59  3568.5  382.41
  3711.2  382.44  3874.9  380.71  3931.4  380.44  4695.2  376.83  4939.2  379.85
  4960.1  379.53  4976.3  376.77  4981.9  370.33  4996.7  370.06  4999.4  369.56
  5002.7  370.06  5014.7   370.6  5028.5  378.26    5090  378.71  5143.3  378.27
    5814   379.6  6012.7  379.77  6278.2   382.2  6329.5  383.63  6417.4  384.47
    6538  386.35  6690.9  388.17  7176.8  393.53  7261.7  394.52  7289.3  402.28
#Mann= 20 ,-1 , 0
  2936.8     .16       0  3084.7     .05       0  3520.3     .08       0
  3568.5     .16       0  3711.2     .16       0  3874.9     .05       0
  3931.4     .16       0  4939.2     .08       0  4996.7     .07       0
  5002.7     .08       0    5090     .16       0  5143.3     .08       0
    5814      .1       0  6012.7     .08       0  6278.2      .1       0
  6329.5     .05       0  6417.4      .1       0    6538      .1       0
  6690.9     .08       0  7176.8     .08       0
Bank Sta=4960.1,5028.5
XS Rating Curve= 0 ,0
Exp/Cntr=0.3,0.1

Type RM Length L Ch R = 1 ,34430   ,75,75,75
BEGIN DESCRIPTION:
SANDERS CREEK 37.0
END DESCRIPTION:
XS GIS Cut Line= 3
      3557259.59     10519922.38      3555934.05     10521572.15
      3554536.38     10523289.96
#Sta/Elev= 30
  3018.4  424.47  3066.3  418.35  3529.6  386.31  3678.2  382.32  3773.5   381.8
  3844.3   381.4  4118.2  379.97  4176.3  378.82  4261.5   379.4  4508.3  378.02
  4749.5  379.24  4800.8  376.54  4871.5  378.97  4957.6  379.65    4990  370.68
  4992.7  370.18    4996  370.68  5029.5  379.44  5640.1  378.09  5683.2  389.07
  5697.6  387.07  5718.4  377.84  5756.2  376.67  5995.3  377.36  6095.8  377.92
    6160  378.53  6340.9  380.78  6489.3  383.02    6586  384.38  7349.3  395.01
#Mann= 20 ,-1 , 0
  3018.4     .08       0  3529.6     .08       0  3678.2     .05       0
  3773.5     .08       0  3844.3     .05       0  4118.2     .08       0
  4176.3     .05       0  4261.5     .08       0  4508.3     .05       0
  4749.5     .08       0  4871.5     .08       0    4990     .07       0
    4996     .08       0  5756.2     .05       0  5995.3     .05       0
  6095.8     .08       0    6160     .05       0  6340.9     .05       0
  6489.3     .05       0    6586     .08       0
#XS Ineff= 2 , 0
                         5681.82          389.07
Permanent Ineff=
       F       F
Bank Sta=4957.6,5029.5
XS Rating Curve= 0 ,0
Exp/Cntr=0.3,0.1

Type RM Length L Ch R = 1 ,34355   ,1217,1217,1217
BEGIN DESCRIPTION:
SANDERS CREEK 37.1
END DESCRIPTION:
XS GIS Cut Line= 2
      3557210.98     10519866.39      3554579.63     10523137.36
#Sta/Elev= 30
  3007.1  429.14  3097.6  425.85  3144.8  416.44  3415.3  393.13  3578.5  383.37
  4078.8  379.01  4440.1  378.34    4628  378.16  4806.2   378.4  4979.7  378.99
  5005.5  370.04  5008.3  369.54  5011.5  370.04  5037.3  377.46  5303.2  378.86
  5416.5  378.53  5538.5     378  5642.1  377.16  5691.6  384.03  5712.4  377.69
  5782.6  376.77  5903.5  376.98  6148.8  377.89  6270.8  378.37  6401.1  381.35
    6567  386.03  6948.9  394.57  7078.7  391.63  7134.7  396.71  7205.1  395.62
#Mann= 20 ,-1 , 0
  3007.1      .1       0  3097.6     .08       0  3415.3     .05       0
  4078.8     .16       0  4440.1     .05       0    4628     .16       0
  4806.2     .05       0  5005.5     .07       0  5011.5     .08       0
  5303.2     .05       0  5416.5     .16       0  5538.5     .08       0
  5642.1     .16       0  5782.6     .05       0  5903.5     .16       0
  6148.8     .05       0  6270.8     .16       0  6401.1     .16       0
    6567     .16       0  6948.9     .05       0
#XS Ineff= 2 , 0
                          5687.5          384.18
Permanent Ineff=
       F       F
Bank Sta=4979.7,5037.3
XS Rating Curve= 0 ,0
Exp/Cntr=0.3,0.1

Type RM Length L Ch R = 1 ,33138   ,1004,1004,1004
BEGIN DESCRIPTION:
SANDERS CREEK 35.0
END DESCRIPTION:
XS GIS Cut Line= 4
      3556623.38     10519533.57       3555449.3     10520896.24
      3555253.99      10521204.4      3554373.41     10522233.54
#Sta/Elev= 30
  3123.1  424.75  3527.1  396.31  3654.4  392.53  3668.6  389.09  3732.3  390.55
  4299.9  376.17  4511.1  376.17  4852.5  379.09  4874.4  375.66    4881  378.69
  4888.6  375.05  4895.2  377.49  4909.5  372.03  4915.8  377.35    4930  378.89
  4981.7  378.09  5002.9  369.44  5015.1  369.07  5017.9  368.57  5021.1  369.07
  5046.6  377.79  5129.5  376.99  5209.3  378.17  5326.3  378.66  5567.3  374.53
  5654.6  377.48  5988.3  374.77  6101.3  377.46  6399.9  400.19  6641.1   400.9
#Mann= 10 ,-1 , 0
  3123.1     .16       0  4299.9      .1       0  4511.1     .16       0
  5015.1     .07       0  5021.1     .16       0  5129.5     .05       0
  5209.3      .1       0  5326.3     .05       0  5567.3     .16       0
  5988.3     .05       0
Bank Sta=4981.7,5046.6
XS Rating Curve= 0 ,0
Exp/Cntr=0.3,0.1

Type RM Length L Ch R = 1 ,32134   ,1070,1070,1070
BEGIN DESCRIPTION:
SANDERS CREEK 34.0
END DESCRIPTION:
XS GIS Cut Line= 3
      3555822.47      10519361.8      3555022.49     10520161.78
      3553322.48      10523261.8
#Sta/Elev= 30
  3570.6  416.29  3612.2  414.91  3842.1  403.14  3931.4  398.39  3966.7  392.58
    4000   393.8  4148.2   389.4  4548.6   374.4  4795.2  374.48  4975.5  376.57
  4995.3  369.76  4998.1  369.26  5001.3  369.76  5020.3  377.43  5123.8  376.03
  5493.8  374.86    5781  375.33  5808.1  372.82  6009.9  374.26  6219.1  374.37
  6347.5  377.43  6657.2  395.87  6766.7  398.57  7237.9  399.43  7332.1  399.06
  7397.5  389.75  7582.3     393  7681.1  398.44  8044.9  412.16  8237.5     415
#Mann= 19 ,-1 , 0
  3570.6     .05       0  3612.2     .16       0  3842.1      .1       0
    4000     .05       0  4148.2     .16       0  4548.6      .1       0
  4795.2     .16       0  4995.3     .07       0  5001.3     .16       0
  5123.8     .05       0  5493.8      .1       0    5781     .16       0
  6009.9      .1       0  6219.1     .05       0  6347.5     .16       0
  6657.2      .1       0  6766.7     .05       0  7237.9     .16       0
  7681.1     .05       0
Bank Sta=4975.5,5020.3
XS Rating Curve= 0 ,0
Exp/Cntr=0.3,0.1

Type RM Length L Ch R = 1 ,31064   ,1273,1273,1273
BEGIN DESCRIPTION:
SANDERS CREEK 32.0
END DESCRIPTION:
XS GIS Cut Line= 3
      3554792.09     10519191.66      3554142.11     10519941.64
      3552942.12     10521941.62
#Sta/Elev= 30
  3974.9  402.92  4527.6  376.27  4683.8   373.5  4722.7  373.98  4794.7   374.1
  4975.1  376.11  4990.7  368.65  4999.3  367.64  5002.1  367.14  5005.3  367.64
  5017.9  375.14  5025.7  376.61  5067.3  376.11  5247.3  376.92  5431.4  377.62
  5609.1  372.81  5797.3   371.8  5834.2  374.98  5873.5  371.88  5950.8  373.93
  6178.2  390.51  6374.5  398.76  6592.2   399.1  6708.1  391.85  6809.9  382.21
  6905.2  383.42  6950.6  388.29    7152  400.96  7282.9  402.08  7299.7  402.54
#Mann= 16 ,-1 , 0
  3974.9     .05       0  4527.6      .1       0  4683.8     .16       0
  4722.7     .05       0  4794.7     .16       0  4999.3     .07       0
  5005.3     .16       0  5067.3     .05       0  5247.3      .1       0
  5431.4     .05       0  5609.1      .1       0  5873.5     .05       0
  6708.1     .16       0  6950.6     .05       0    7152     .16       0
  7282.9     .05       0
#XS Ineff= 2 , 0
                         6491.74          399.47
Permanent Ineff=
       F       F
Bank Sta=4975.1,5025.7
XS Rating Curve= 0 ,0
Exp/Cntr=0.3,0.1

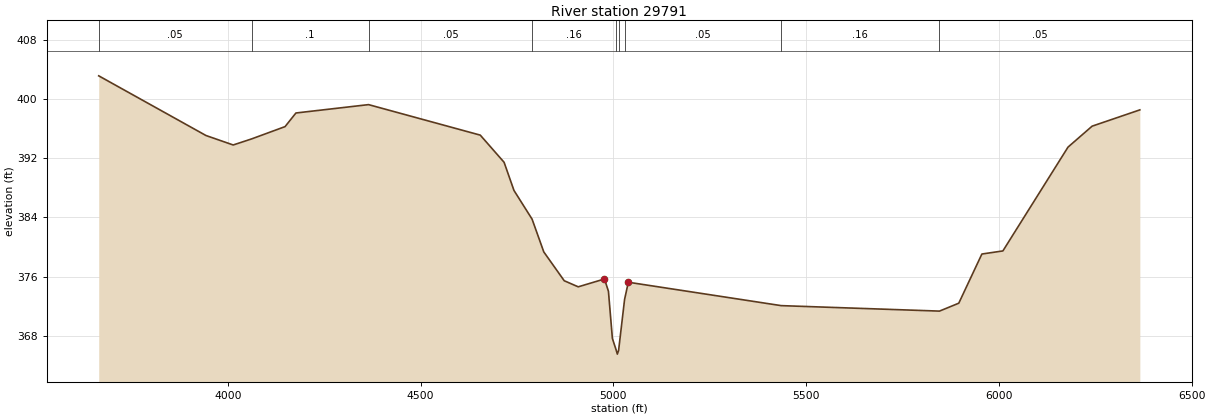
Type RM Length L Ch R = 1 ,29791   ,523,523,523
BEGIN DESCRIPTION:
SANDERS CREEK 31.1
END DESCRIPTION:
XS GIS Cut Line= 5
      3554087.67     10518643.88      3553673.25     10519051.15
       3553452.2     10519675.87      3553543.34     10520027.43
      3553148.51     10521047.05
#Sta/Elev= 30
  3665.3  403.11  3943.4  395.05  4014.1  393.77  4061.9  394.59  4148.6  396.25
  4176.8  398.09  4365.1  399.22  4654.9   395.1  4716.7  391.43  4742.3  387.63
  4789.3  383.75  4819.7  379.32  4872.7  375.43    4909  374.61    4977  375.67
  4987.3  374.02  4997.6  367.63  5007.7  366.02  5010.4  365.52  5013.7  366.02
  5029.2  372.91  5038.9  375.23  5435.4  372.07  5845.9  371.33    5896   372.4
  5955.9  379.04  6010.4  379.46  6179.3  393.48  6241.8  396.31  6365.6  398.51
#Mann= 9 ,-1 , 0
  3665.3     .05       0  4061.9      .1       0  4365.1     .05       0
  4789.3     .16       0  5007.7     .07       0  5013.7     .16       0
  5029.2     .05       0  5435.4     .16       0  5845.9     .05       0
Bank Sta=4977,5038.9
XS Rating Curve= 0 ,0
Exp/Cntr=0.3,0.1