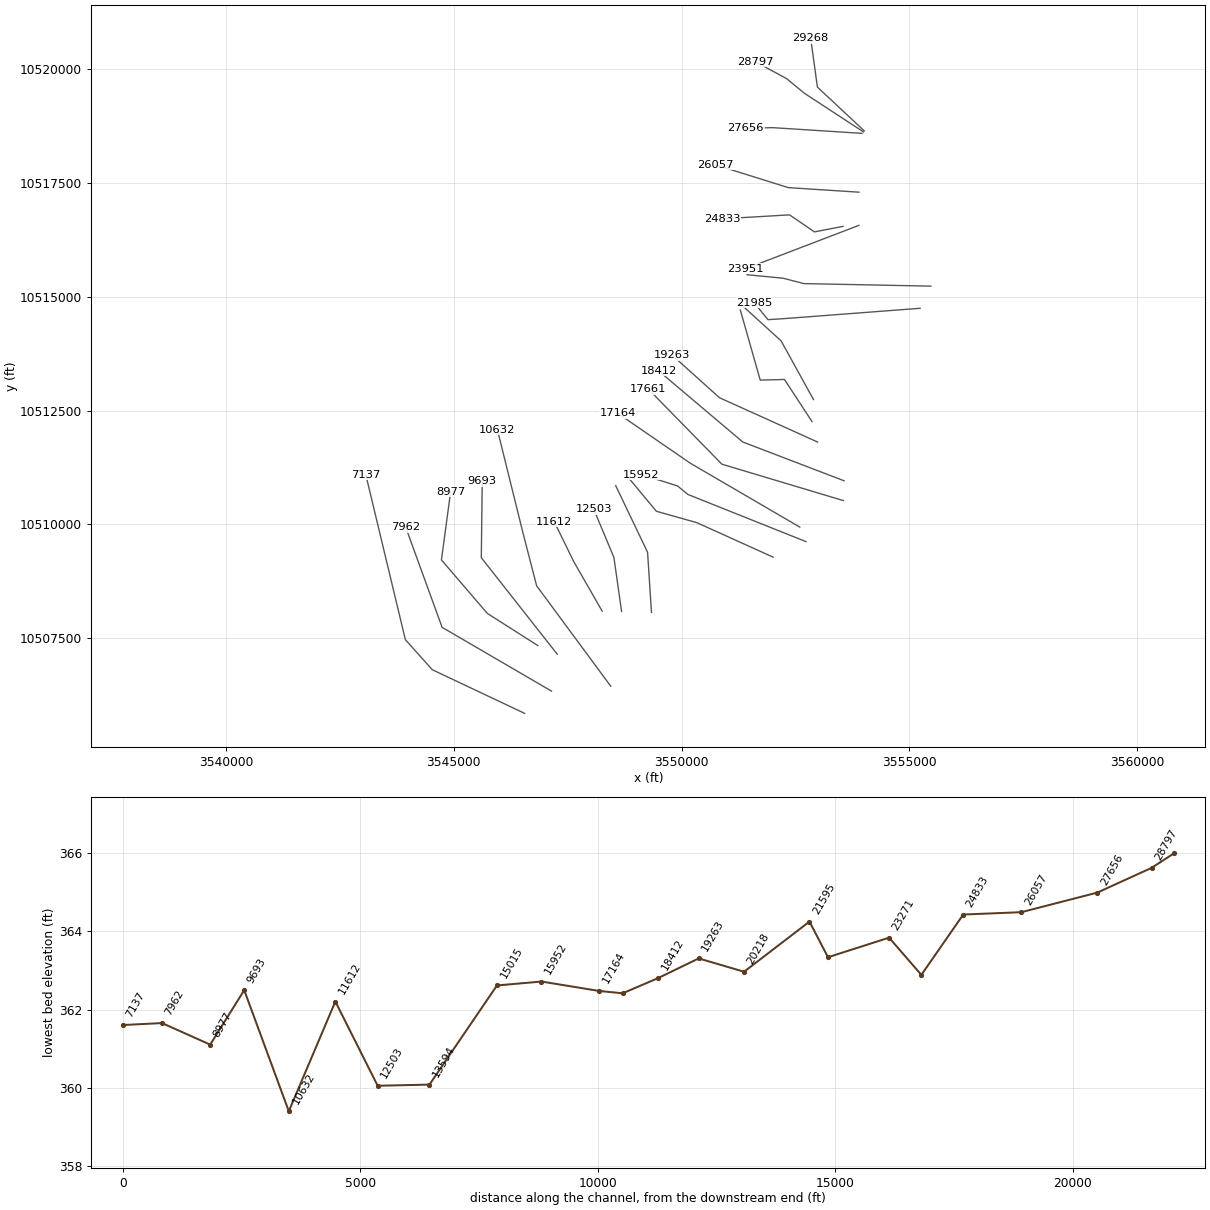
HEC-RAS study SANDERS CREEK.prj: SANDERS CREEK Base Level Engineering

--- SANDERS CREEK.g01 (geometry) --- (continued)

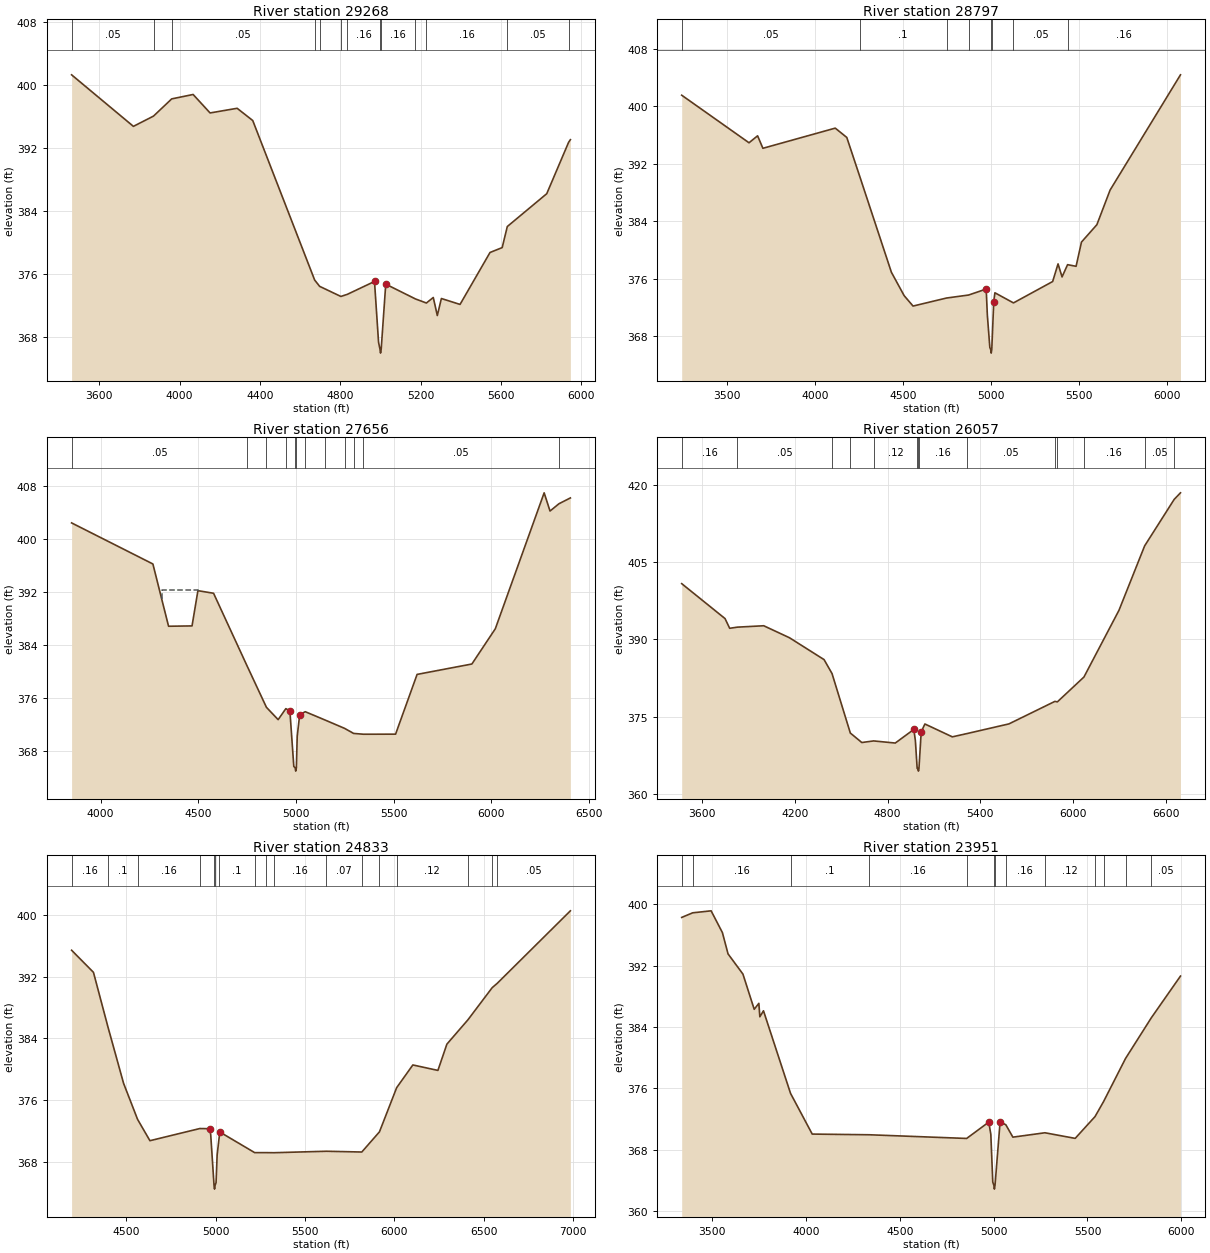
Type RM Length L Ch R = 1 ,29268   ,471,471,471
BEGIN DESCRIPTION:
SANDERS CREEK 31.0
END DESCRIPTION:
XS GIS Cut Line= 3
      3554005.21     10518639.54      3552979.11     10519597.75
      3552831.76     10520668.21
#Sta/Elev= 30
  3461.7  401.25  3769.5  394.72  3869.7  396.02  3960.2   398.2    4067  398.76
  4151.5  396.42  4286.3  397.01    4364  395.46  4672.4  375.25  4697.3  374.45
    4803  373.17  4835.3  373.44  4970.5  375.07  4990.7  367.36  4997.8  366.49
  5000.6  365.99  5003.8  366.49  5026.5  374.73  5174.2  372.86  5228.9  372.34
  5263.3  373.04  5283.4  370.75  5303.6  372.91  5396.6  372.16  5545.9  378.74
  5606.5  379.36    5632  382.03  5828.5  386.19  5937.4   392.7  5946.2  393.03
#Mann= 13 ,-1 , 0
  3461.7     .05       0  3869.7      .1       0  3960.2     .05       0
  4672.4      .1       0  4697.3     .05       0    4803      .1       0
  4835.3     .16       0  4997.8     .07       0  5003.8     .16       0
  5174.2     .05       0  5228.9     .16       0    5632     .05       0
  5937.4      .1       0
Bank Sta=4970.5,5026.5
XS Rating Curve= 0 ,0
Exp/Cntr=0.3,0.1

Type RM Length L Ch R = 1 ,28797   ,1141,1141,1141
BEGIN DESCRIPTION:
SANDERS CREEK 30.0
END DESCRIPTION:
XS GIS Cut Line= 4
      3553992.15     10518613.53      3552697.34     10519459.97
      3552302.02     10519784.38       3551620.6      10520153.3
#Sta/Elev= 30
  3242.3  401.57  3624.7  394.94  3673.4  395.91  3703.6  394.17  4114.5  396.98
  4180.1  395.68  4253.8  390.24  4433.5  376.89  4505.9  373.63  4556.5  372.18
  4746.7   373.3  4872.3  373.72  4971.9  374.55  4978.4  370.96  4992.7   366.4
  4997.6  366.12  5000.3  365.62  5003.6  366.12  5014.9  372.81  5021.4  374.03
  5126.9  372.62  5349.5   375.6  5380.1  378.06  5402.9  376.24  5434.2  377.95
  5482.5  377.72  5513.2   381.1  5600.6  383.52  5675.8  388.35  6075.5  404.41
#Mann= 8 ,-1 , 0
  3242.3     .05       0  4253.8      .1       0  4746.7     .05       0
  4872.3     .16       0  4997.6     .07       0  5003.6     .16       0
  5126.9     .05       0  5434.2     .16       0
Bank Sta=4971.9,5014.9
XS Rating Curve= 0 ,0
Exp/Cntr=0.3,0.1

Type RM Length L Ch R = 1 ,27656   ,1599,1599,1599
BEGIN DESCRIPTION:
SANDERS CREEK 28.0
END DESCRIPTION:
XS GIS Cut Line= 3
      3553957.45     10518582.85       3551998.2     10518707.99
      3551407.89     10518694.97
#Sta/Elev= 30
  3851.9  402.46  4268.1  396.26  4348.3  386.86  4468.5  386.91  4498.6  392.23
  4578.7  391.84  4750.2  380.88  4849.5  374.62  4909.4  372.76  4948.8  374.42
  4969.5  374.09  4989.6  365.69  4996.6  365.49  4999.3  364.99  5002.6  365.49
  5007.1  370.26  5019.6   373.5  5048.1  373.96  5147.5  372.73  5249.2  371.45
  5295.9  370.68  5346.1  370.56  5510.6  370.57  5620.8  379.59  5901.3  381.16
  6021.3  386.48  6271.3     407  6301.4  404.25  6347.1  405.35  6405.6  406.23
#Mann= 12 ,-1 , 0
  3851.9     .05       0  4750.2      .1       0  4849.5     .05       0
  4948.8     .16       0  4996.6     .07       0  5002.6     .16       0
  5048.1     .05       0  5147.5      .1       0  5249.2     .12       0
  5295.9      .1       0  5346.1     .05       0  6347.1     .15       0
#XS Ineff= 1 ,-1
 4313.07 4497.16  392.29
Permanent Ineff=
       F
Bank Sta=4969.5,5019.6
XS Rating Curve= 0 ,0
Exp/Cntr=0.3,0.1

Type RM Length L Ch R = 1 ,26057   ,1224,1224,1224
BEGIN DESCRIPTION:
SANDERS CREEK 26.0
END DESCRIPTION:
XS GIS Cut Line= 3
       3553892.1     10517291.64      3552342.11     10517391.64
      3550742.13     10517891.64
#Sta/Elev= 30
  3467.2  400.81  3747.8  394.04  3777.8  392.16  3827.7  392.38  3998.3  392.65
  4164.9  390.33  4389.1  386.09  4440.6  383.39    4559  371.87  4633.4  370.03
  4709.8  370.34  4850.1  369.93  4970.3  372.57  4980.3  370.37  4991.8  365.01
  4997.4  364.99  5000.1  364.49  5003.4  364.99  5017.9  372.09  5041.9  373.62
  5219.5  371.13  5315.3  371.77  5586.2  373.64  5883.7     378  5899.4   377.9
  6071.7  382.72  6298.6  395.65  6464.6  408.12    6656  417.13  6696.7   418.4
#Mann= 14 ,-1 , 0
  3467.2     .16       0  3827.7     .05       0  4440.6     .12       0
    4559     .16       0  4709.8     .12       0  4991.8     .16       0
  4997.4     .07       0  5003.4     .16       0  5315.3     .05       0
  5883.7      .1       0  5899.4     .05       0  6071.7     .16       0
  6464.6     .05       0    6656     .08       0
Bank Sta=4970.3,5017.9
XS Rating Curve= 0 ,0
Exp/Cntr=0.3,0.1

Type RM Length L Ch R = 1 ,24833   ,882,882,882
BEGIN DESCRIPTION:
SANDERS CREEK 25.0
END DESCRIPTION:
XS GIS Cut Line= 4
      3553542.07     10516541.64        3552914.     10516420.66
      3552367.13     10516793.93       3550882.8     10516707.12
#Sta/Elev= 30
  4195.5  395.46  4317.7  392.59  4398.1  385.55    4486  378.18  4564.4  373.49
  4633.4  370.72  4912.3   372.3  4967.2  372.28  4973.3   371.5  4991.8  364.93
  4994.6  364.43  4997.8  364.93  5003.1  365.26  5009.2  368.87    5022  371.45
  5024.1  371.85  5219.1  369.17  5281.4  369.17  5327.2  369.16  5620.3  369.35
  5817.9  369.25  5916.7  371.87  6012.9  377.61  6103.3  380.56  6243.5  379.85
  6293.6  383.26  6410.8  386.41    6547   390.6  6575.1  391.16  6984.1  400.58
#Mann= 17 ,-1 , 0
  4195.5     .16       0  4398.1      .1       0  4564.4     .16       0
  4912.3     .12       0  4991.8     .07       0  4997.8     .12       0
    5022      .1       0  5219.1     .16       0  5281.4      .1       0
  5327.2     .16       0  5620.3     .07       0  5817.9     .05       0
  5916.7     .16       0  6012.9     .12       0  6410.8     .05       0
    6547     .16       0  6575.1     .05       0
Bank Sta=4967.2,5024.1
XS Rating Curve= 0 ,0
Exp/Cntr=0.3,0.1

Type RM Length L Ch R = 1 ,23951   ,680,680,680
BEGIN DESCRIPTION:
SANDERS CREEK 24.0
END DESCRIPTION:
XS GIS Cut Line= 2
      3553890.53     10516563.88      3551407.97     10515613.39
#Sta/Elev= 30
  3337.5  398.28    3396  398.88  3494.3  399.14  3554.4  396.31  3584.5  393.53
  3663.9   390.9    3724  386.31  3748.7  387.09    3754  385.34  3773.4  386.12
  3917.5  375.37  4033.1  370.06  4337.6  369.97  4856.2  369.49  4974.1  371.62
    4985  370.04  4995.5   363.8  5001.4  363.39  5004.1  362.89  5007.4  363.39
  5034.4  371.64  5064.8  371.28  5102.6  369.66  5273.4  370.23  5434.6   369.5
  5540.5  372.34  5586.3  374.31  5702.8   379.9  5840.5  385.21  5995.8  390.64
#Mann= 13 ,-1 , 0
  3337.5     .05       0    3396     .16       0  3917.5      .1       0
  4337.6     .16       0  4856.2     .12       0  5001.4     .07       0
  5007.4     .12       0  5064.8     .16       0  5273.4     .12       0
  5540.5     .16       0  5586.3     .12       0  5702.8     .16       0
  5840.5     .05       0
Bank Sta=4974.1,5034.4
XS Rating Curve= 0 ,0
Exp/Cntr=0.3,0.1

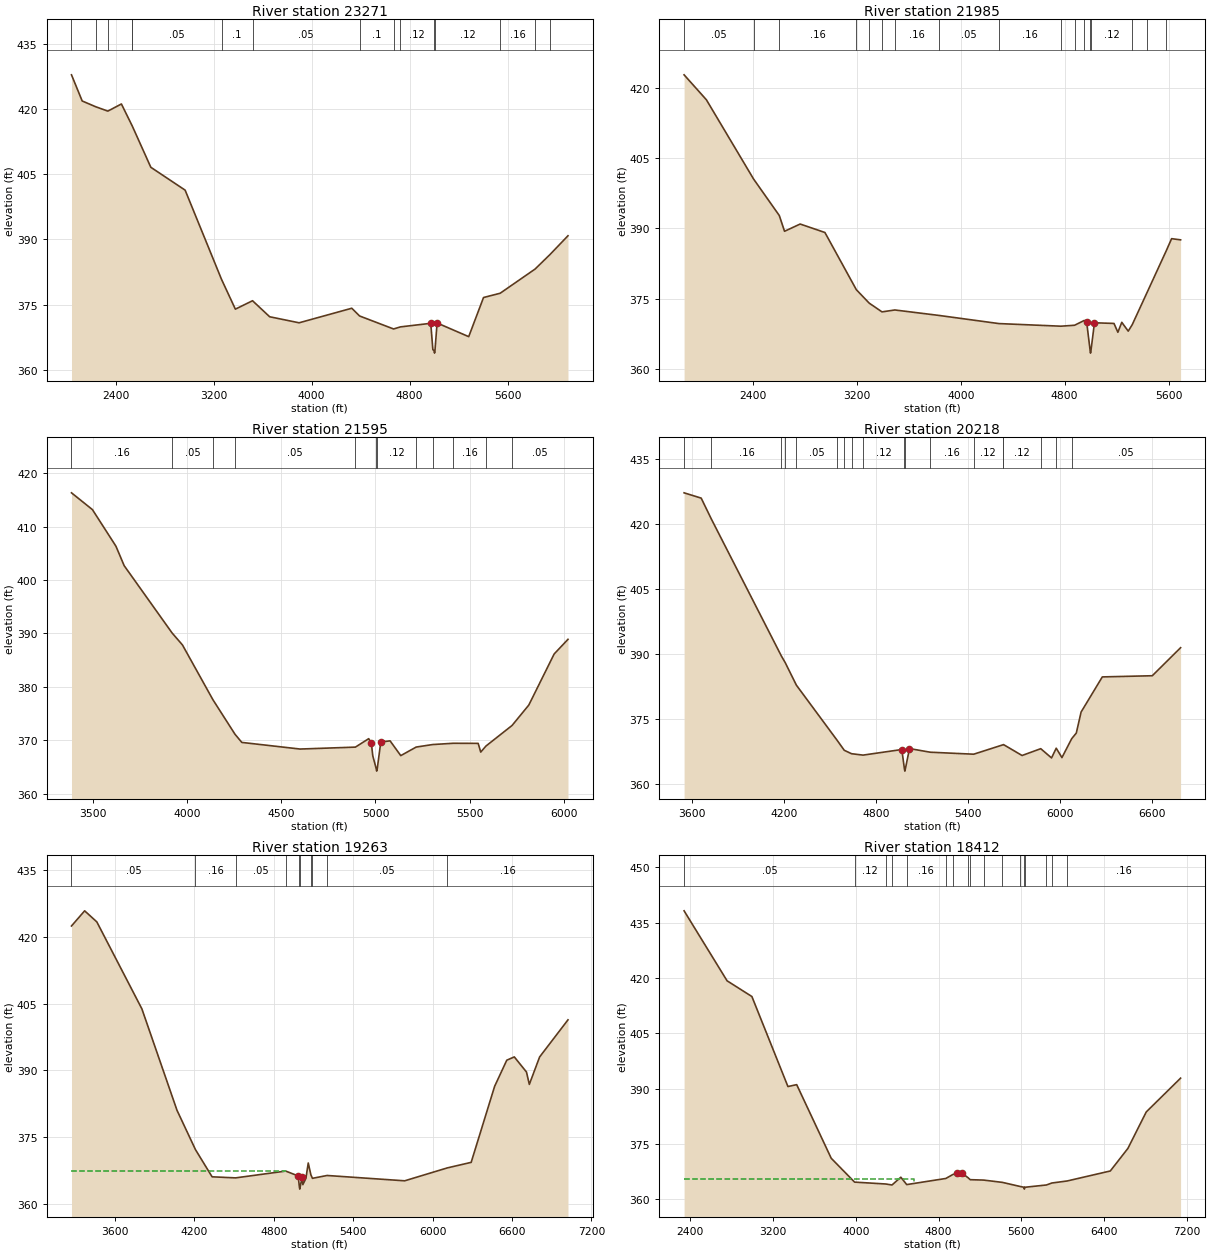
Type RM Length L Ch R = 1 ,23271   ,1286,1286,1286
BEGIN DESCRIPTION:
SANDERS CREEK 23.1
END DESCRIPTION:
XS GIS Cut Line= 4
      3555469.53     10515229.69      3552684.84     10515285.25
       3552226.5      10515403.3      3551436.02     10515479.58
#Sta/Elev= 30
  2040.6  427.89    2128  421.87  2238.4  420.54  2337.3  419.54  2448.1  421.18
  2535.3  416.19  2535.9  416.16  2688.2  406.61  2968.2  401.35  3265.1  380.83
  3378.3  373.96  3518.3   375.9  3658.3  372.21  3898.4  370.82  4328.5  374.17
  4392.3  372.39  4669.7   369.4  4726.1  369.88  4973.2   370.7  4990.3  364.66
  5001.2  364.34    5004  363.84  5007.2  364.34  5024.9  370.78    5283  367.63
    5404  376.64  5539.6  377.62  5824.8  383.19  5946.3  386.53  6093.3  390.85
#Mann= 15 ,-1 , 0
  2040.6     .16       0  2238.4     .05       0  2337.3      .1       0
  2535.3     .08       0  2535.9     .05       0  3265.1      .1       0
  3518.3     .05       0  4392.3      .1       0  4669.7     .16       0
  4726.1     .12       0  5001.2     .07       0  5007.2     .12       0
  5539.6     .16       0  5824.8      .1       0  5946.3     .05       0
Bank Sta=4973.2,5024.9
XS Rating Curve= 0 ,0
Exp/Cntr=0.3,0.1

Type RM Length L Ch R = 1 ,21985   ,390,390,390
BEGIN DESCRIPTION:
SANDERS CREEK 23.0
END DESCRIPTION:
XS GIS Cut Line= 4
      3555233.44     10514743.58      3552316.78     10514521.36
      3551893.17     10514493.58      3551594.55     10514861.65
#Sta/Elev= 30
  1869.4  422.86  2041.2  417.52  2404.9  400.56  2602.6  392.77    2643   389.4
  2763.3  390.95  2953.9  389.14  3195.8  376.91  3294.7  374.04  3393.5  372.16
  3492.4  372.57  3832.6   371.4  4293.4  369.66  4771.5   369.1  4876.4   369.3
  4951.4  370.33  4969.6  370.01  4996.6  363.84  4999.4  363.34  5002.6  363.84
  5029.7  369.83    5180  369.69  5210.1   367.8  5240.2  369.93  5289.8  368.04
  5320.3  369.41  5437.7  376.48  5583.4  385.28  5623.8  387.82    5693  387.57
#Mann= 17 ,-1 , 0
  1869.4     .05       0  2404.9      .1       0  2602.6     .16       0
  3195.8     .05       0  3294.7      .1       0  3393.5     .05       0
  3492.4     .16       0  3832.6     .05       0  4293.4     .16       0
  4771.5     .05       0  4876.4     .16       0  4951.4     .12       0
  4996.6     .07       0  5002.6     .12       0  5320.3     .16       0
  5437.7     .12       0  5583.4     .16       0
Bank Sta=4969.6,5029.7
XS Rating Curve= 0 ,0
Exp/Cntr=0.3,0.1

Type RM Length L Ch R = 1 ,21595   ,1377,1377,1377
BEGIN DESCRIPTION:
SANDERS CREEK 22.0
END DESCRIPTION:
XS GIS Cut Line= 3
      3552892.11     10512741.63      3552182.04     10514028.64
      3551319.41       10514813.
#Sta/Elev= 30
  3386.4   416.3  3497.6  413.16  3622.5  406.31    3666  402.68  3920.7  390.08
  3975.5  387.85    4137  377.62  4254.4  371.15  4290.6  369.62  4600.1  368.38
  4893.7  368.74  4964.3  370.32  4978.4  369.47  4985.9  367.12  5003.8  364.75
  5006.6  364.25  5009.8  364.75  5028.4   369.7  5077.8  369.91  5134.5  367.15
  5216.3  368.75  5303.7  369.22  5413.5  369.46  5545.4  369.44    5559  367.81
  5586.7  368.94  5725.3  372.79  5814.3  376.61  5948.8  386.16  6022.2   388.9
#Mann= 12 ,-1 , 0
  3386.4     .16       0  3920.7     .05       0    4137     .16       0
  4254.4     .05       0  4893.7     .12       0  5003.8     .07       0
  5009.8     .12       0  5216.3     .16       0  5303.7     .12       0
  5413.5     .16       0  5586.7     .12       0  5725.3     .05       0
Bank Sta=4978.4,5028.4
XS Rating Curve= 0 ,0
Exp/Cntr=0.3,0.1

Type RM Length L Ch R = 1 ,20218   ,955,955,955
BEGIN DESCRIPTION:
SANDERS CREEK 21.1
END DESCRIPTION:
XS GIS Cut Line= 4
      3552860.16     10512256.63      3552256.89     10513181.08
      3551724.37     10513167.43      3551286.96     10514705.26
#Sta/Elev= 30
  3548.8   427.1  3660.2  425.88  3726.3  421.07  4183.3  389.46  4207.5  387.99
  4280.6  382.78  4545.3  370.11  4592.6  367.77  4640.2  366.98  4714.9  366.66
  4967.6  367.95  4984.6  363.47  4987.3  362.97  4990.6  363.47  5017.6  368.17
  5152.5  367.33  5435.9  366.87  5626.4  369.03    5630  369.09  5751.2  366.57
  5872.9  368.14  5943.2  366.01  5973.8  368.25    6011  366.09  6074.7  370.45
  6104.7  371.75  6135.8  376.58  6274.1  384.68  6599.7  384.95  6784.2  391.41
#Mann= 18 ,-1 , 0
  3548.8     .05       0  3726.3     .16       0  4183.3     .05       0
  4207.5     .16       0  4280.6     .05       0  4545.3     .16       0
  4592.6     .05       0  4640.2     .16       0  4714.9     .12       0
  4984.6     .07       0  4990.6     .12       0  5152.5     .16       0
  5435.9     .12       0  5626.4     .16       0    5630     .12       0
  5872.9     .16       0  5973.8     .12       0  6074.7     .05       0
Bank Sta=4967.6,5017.6
XS Rating Curve= 0 ,0
Exp/Cntr=0.3,0.1

Type RM Length L Ch R = 1 ,19263   ,851,851,851
BEGIN DESCRIPTION:
SANDERS CREEK 20.1
END DESCRIPTION:
XS GIS Cut Line= 3
      3552982.72     10511808.29      3550829.93     10512780.51
      3549797.02     10513709.26
#Sta/Elev= 30
  3271.9   422.5  3371.3  425.91  3463.4  423.42  3803.6  403.87  4068.9  381.06
  4208.7  372.19  4334.2  366.08  4511.6  365.84  4890.4  367.37  4984.3  366.28
  4993.8  363.81  4996.6  363.31  4999.8  363.81  5014.5  366.06    5020  364.32
  5043.1  365.73  5060.7  369.19  5080.2  366.57  5092.4  365.74  5202.8  366.38
  5789.3  365.18    6112  368.09  6291.6  369.33  6468.7  386.42  6560.6  392.31
  6617.5  393.05  6709.4  389.66  6731.1  386.87  6808.8  393.04  7023.1  401.39
#Mann= 10 ,-1 , 0
  3271.9     .05       0  4208.7     .16       0  4511.6     .05       0
  4890.4     .12       0  4993.8     .07       0  4999.8     .12       0
  5080.2     .16       0  5092.4     .12       0  5202.8     .05       0
    6112     .16       0
#XS Ineff= 2 , 0
         4894.29   367.5
Permanent Ineff=
       F       F
Bank Sta=4984.3,5014.5
XS Rating Curve= 0 ,0
Exp/Cntr=0.3,0.1

Type RM Length L Ch R = 1 ,18412   ,751,751,751
BEGIN DESCRIPTION:
SANDERS CREEK 21.0
END DESCRIPTION:
XS GIS Cut Line= 3
      3553564.28     10510957.61      3551342.08     10511808.29
      3549493.14     10513370.78
#Sta/Elev= 30
  2339.8  438.25  2755.5  419.28  2995.3  415.02  3343.7  390.62  3428.5  391.13
  3762.3  371.17  3988.3  364.71  4290.1   364.2  4349.7  363.93  4435.2  366.04
  4492.2  364.04  4870.3   365.7  4939.3  366.79  4977.3  367.07  5026.7  367.17
  5084.5  365.91    5106  365.37  5236.6  365.26  5417.2  364.64  5588.6  363.53
    5627  363.31  5629.7  362.81    5633  363.31    5842  363.93  5895.7  364.47
  6043.4  365.02  6460.5  367.73  6630.7  373.85  6807.9  383.73    7140  392.89
#Mann= 17 ,-1 , 0
  2339.8     .05       0  3988.3     .12       0  4290.1     .16       0
  4349.7     .12       0  4492.2     .16       0  4870.3     .12       0
  4939.3     .16       0  5084.5     .12       0    5106     .16       0
  5236.6     .05       0  5417.2     .16       0  5588.6     .05       0
    5627     .07       0    5633     .05       0    5842     .16       0
  5895.7     .05       0  6043.4     .16       0
#XS Ineff= 2 , 0
         4558.24  365.66
Permanent Ineff=
       F       F
Bank Sta=4977.3,5026.7
XS Rating Curve= 0 ,0
Exp/Cntr=0.3,0.1

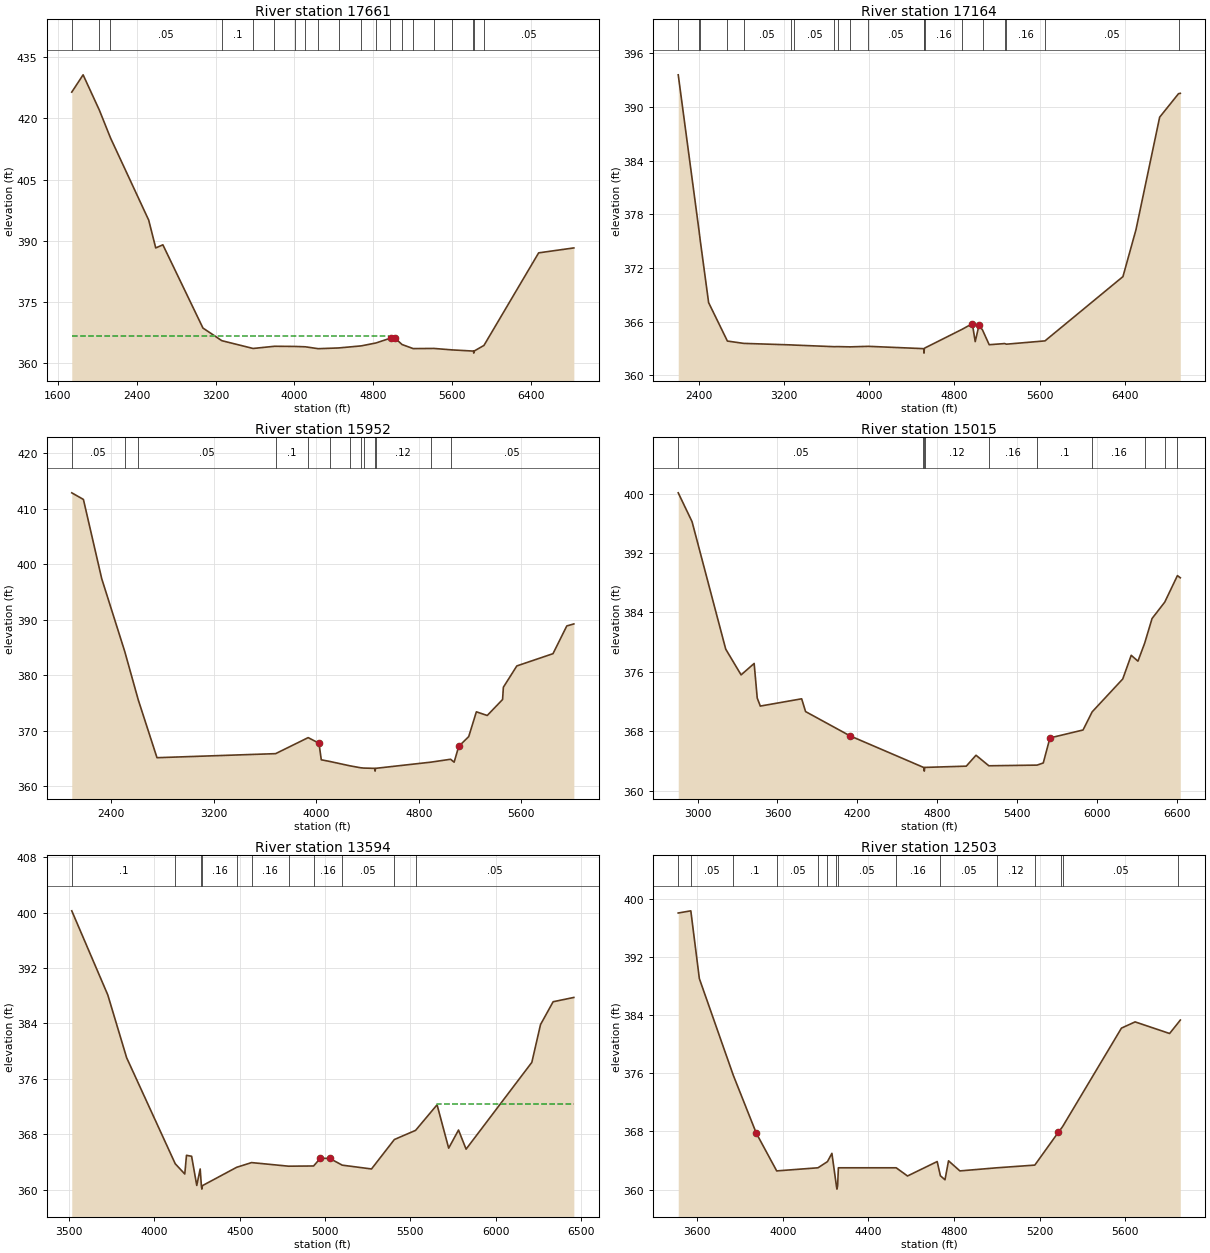
Type RM Length L Ch R = 1 ,17661   ,497,497,497
BEGIN DESCRIPTION:
SANDERS CREEK 20.0
END DESCRIPTION:
XS GIS Cut Line= 3
      3553546.94     10510523.57      3550882.01     10511322.18
       3549267.4     10512971.51
#Sta/Elev= 30
  1742.8  426.43  1857.7  430.67  2022.2  422.03  2134.7  415.24  2522.7  395.04
  2594.1  388.22  2666.5  388.98  3072.8  368.57  3264.4  365.47  3581.4  363.56
  3797.9   364.1  4006.8  364.06  4111.3  363.97  4241.5  363.51  4448.7  363.69
  4678.1   364.2  4826.8  364.91  4972.6  366.08  4976.9  366.03  5019.4   366.1
  5091.2  364.53  5204.5  363.53  5414.5  363.57  5600.3  363.21  5815.4  362.92
  5818.2  362.42  5821.4  362.92  5921.6  364.31  6476.1  387.01  6832.9  388.22
#Mann= 20 ,-1 , 0
  1742.8     .05       0  2022.2      .1       0  2134.7     .05       0
  3264.4      .1       0  3581.4     .05       0  3797.9     .05       0
  4006.8     .05       0  4111.3     .16       0  4241.5     .12       0
  4448.7     .16       0  4678.1     .05       0  4826.8     .12       0
  4972.6     .12       0  5091.2     .05       0  5204.5     .07       0
  5414.5     .12       0  5600.3     .16       0  5815.4     .07       0
  5821.4     .16       0  5921.6     .05       0
#XS Ineff= 2 , 0
         4954.93  366.55
Permanent Ineff=
       F       F
Bank Sta=4976.9,5019.4
XS Rating Curve= 0 ,0
Exp/Cntr=0.3,0.1

Type RM Length L Ch R = 1 ,17164   ,1212,1212,1212
BEGIN DESCRIPTION:
SANDERS CREEK 19.0
END DESCRIPTION:
XS GIS Cut Line= 3
      3552592.08     10509941.66      3550192.11     10511341.64
      3548592.11     10512441.64
#Sta/Elev= 30
  2202.9  393.61  2398.8  376.14  2409.1  375.15  2488.6  368.13    2665  363.83
  2818.2  363.57  3262.4   363.4  3295.2  363.38  3669.7   363.2  3700.9  363.21
    3818  363.18  3990.8  363.24  4510.7  362.98  4513.5  362.48  4516.7  362.98
    4521  363.05  4872.5  365.15  4967.7  365.77  4994.9  363.77  5030.7  365.62
  5064.3  365.05  5126.2  363.42  5272.1  363.55  5288.1  363.48  5650.9  363.85
  6383.8  371.04  6506.3  376.29  6728.8  388.87  6906.1   391.5    6923  391.54
#Mann= 20 ,-1 , 0
  2202.9     .05       0  2398.8      .1       0  2409.1     .05       0
    2665      .1       0  2818.2     .05       0  3262.4      .1       0
  3295.2     .05       0  3669.7     .12       0  3700.9     .16       0
    3818     .12       0  3990.8     .05       0  4510.7     .07       0
  4516.7     .05       0    4521     .16       0  4872.5     .12       0
  5064.3     .16       0  5272.1     .12       0  5288.1     .16       0
  5650.9     .05       0  6906.1     .08       0
Bank Sta=4967.7,5030.7
XS Rating Curve= 0 ,0
Exp/Cntr=0.3,0.1

Type RM Length L Ch R = 1 ,15952   ,937,937,937
BEGIN DESCRIPTION:
SANDERS CREEK 18.0
END DESCRIPTION:
XS GIS Cut Line= 4
      3552729.13     10509622.04      3550138.83     10510656.77
      3549909.66     10510844.27      3549118.02     10511094.27
#Sta/Elev= 30
  2093.3  412.88  2184.1  411.69    2327   397.4  2506.3   384.3  2611.8  375.57
  2757.9  365.14  3683.1  365.87    3937  368.76  4021.3  367.75  4039.2  364.76
  4104.5  364.47  4261.5  363.68  4345.2  363.33  4369.7  363.27  4456.1  363.22
  4458.9  362.72  4462.1  363.22  4895.4  364.34  5047.9  364.86  5075.3  364.33
    5111  367.17  5189.2  368.95  5248.7  373.41  5333.5  372.75  5453.2  375.63
  5459.3  377.84  5564.2  381.68  5846.4  383.89  5953.9  388.89  6008.9  389.25
#Mann= 13 ,-1 , 0
  2093.3     .05       0  2506.3      .1       0  2611.8     .05       0
  3683.1      .1       0    3937     .16       0  4104.5     .05       0
  4261.5     .16       0  4345.2     .05       0  4369.7     .12       0
  4456.1     .07       0  4462.1     .12       0  4895.4     .16       0
  5047.9     .05       0
Bank Sta=4021.3,5111
XS Rating Curve= 0 ,0
Exp/Cntr=0.3,0.1

Type RM Length L Ch R = 1 ,15015   ,1421,1421,1421
BEGIN DESCRIPTION:
SANDERS CREEK 17.0
END DESCRIPTION:
XS GIS Cut Line= 4
      3552006.84     10509281.79      3550333.27     10510038.72
      3549444.39     10510288.72      3548798.56     10511066.48
#Sta/Elev= 30
  2854.5   400.1  2958.2  396.22  3211.2  379.05  3326.7  375.58  3424.7  377.12
  3447.8  372.47  3470.9  371.38  3781.6  372.36  3810.9  370.64  4143.8  367.38
  4695.9  363.13  4699.9  363.12  4702.6  362.62  4705.9  363.12  5017.9  363.29
  5091.2  364.76  5187.5  363.34  5550.2  363.43  5596.3  363.72  5646.3  367.09
    5895  368.16  5963.4   370.6  6193.2  375.03    6257  378.22  6307.4  377.43
  6357.5  379.83  6413.3  383.17  6508.7  385.38  6603.9  388.95  6625.6  388.66
#Mann= 10 ,-1 , 0
  2854.5     .05       0  4695.9     .12       0  4699.9     .07       0
  4705.9     .12       0  5187.5     .16       0  5550.2      .1       0
  5963.4     .16       0  6357.5     .05       0  6508.7     .16       0
  6603.9     .05       0
Bank Sta=4143.8,5646.3
XS Rating Curve= 0 ,0
Exp/Cntr=0.3,0.1

Type RM Length L Ch R = 1 ,13594   ,1091,1091,1091
BEGIN DESCRIPTION:
SANDERS CREEK 19.1
END DESCRIPTION:
XS GIS Cut Line= 3
      3549337.19     10508070.87      3549251.58     10509388.85
      3548552.04     10510851.19
#Sta/Elev= 30
  3515.9  400.25  3727.1  388.11  3837.3  379.06  4122.2  363.75  4178.1  362.27
  4188.1  364.97  4218.1  364.83  4248.2  360.62  4268.3     363  4275.3  360.59
    4278  360.09  4281.3  360.59  4482.1  363.24  4569.3  363.92    4786   363.4
  4932.7  363.43  4972.8  364.55  5027.5  364.52  5100.5  363.55  5272.1     363
  5406.1  367.25  5530.5  368.57  5656.3  372.26  5724.3     366    5782  368.62
  5826.3  365.86  6211.5  378.38  6262.4  383.83  6336.3  387.13  6457.7  387.75
#Mann= 11 ,-1 , 0
  3515.9      .1       0  4122.2     .16       0  4275.3     .07       0
  4281.3     .16       0  4482.1     .12       0  4569.3     .16       0
    4786     .12       0  4932.7     .16       0  5100.5     .05       0
  5406.1      .1       0  5530.5     .05       0
#XS Ineff= 2 , 0
                         5656.25          372.39
Permanent Ineff=
       F       F
Bank Sta=4972.8,5027.5
XS Rating Curve= 0 ,0
Exp/Cntr=0.3,0.1

Type RM Length L Ch R = 1 ,12503   ,891,891,891
BEGIN DESCRIPTION:
SANDERS CREEK 18.1
END DESCRIPTION:
XS GIS Cut Line= 3
      3548681.17     10508090.33      3548513.01     10509275.21
      3548069.37     10510336.67
#Sta/Elev= 30
    3511   398.1  3569.8   398.4  3609.7  389.07  3768.3  375.75  3875.9  367.77
  3971.3  362.57  4164.3     363  4208.7  363.85  4229.4  364.99  4250.2  360.56
  4252.9  360.06  4256.2  360.56  4259.7     363  4529.9     363  4582.9  361.87
  4721.6  363.86  4736.6   361.9  4758.1  361.35  4774.6  363.96  4827.7  362.57
  5001.7     363    5178  363.37  5288.7  367.92  5300.1  368.36  5307.6  368.66
    5583  382.24  5646.8   383.1  5808.1   381.5  5849.2  383.01  5858.2  383.35
#Mann= 15 ,-1 , 0
    3511      .1       0  3569.8     .05       0  3768.3      .1       0
  3971.3     .05       0  4164.3     .16       0  4208.7     .05       0
  4250.2    .033       0  4256.2     .05       0  4529.9     .16       0
  4736.6     .05       0  5001.7     .12       0    5178     .05       0
  5300.1      .1       0  5307.6     .05       0  5849.2      .1       0
Bank Sta=3875.9,5288.7
XS Rating Curve= 0 ,0
Exp/Cntr=0.3,0.1

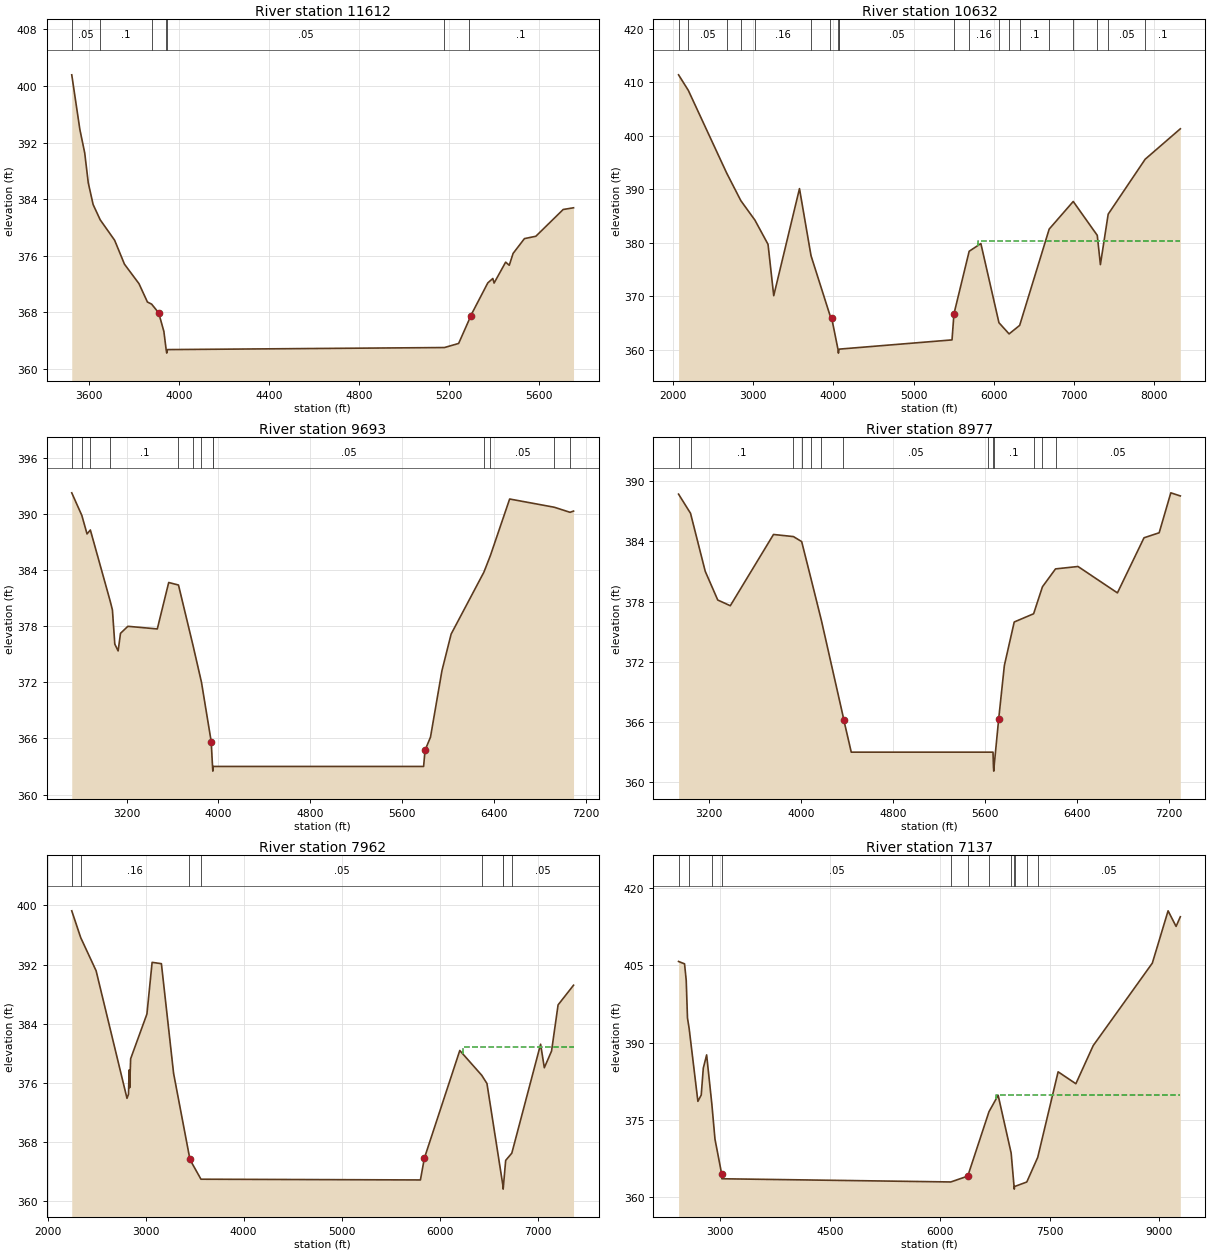
Type RM Length L Ch R = 1 ,11612   ,980,980,980
BEGIN DESCRIPTION:
SANDERS CREEK 17.1
END DESCRIPTION:
XS GIS Cut Line= 3
       3548255.6     10508096.17      3547627.88     10509189.77
      3547201.34     10510063.01
#Sta/Elev= 30
  3522.1  401.58  3558.2  393.85  3579.8  390.53  3595.6   386.3  3617.2  383.23
  3648.7  381.07  3712.9  378.18  3756.7  374.79  3821.4  372.03  3858.8  369.44
  3877.6  369.14  3908.9  367.91    3932  365.28  3942.1  362.71  3944.8  362.21
  3948.1  362.71  5180.5     363  5243.7  363.58  5287.7  366.74  5297.1  367.48
  5373.3  372.14  5395.8  372.77  5401.4  372.12  5452.9  375.08    5469  374.64
  5485.9  376.31  5536.5  378.41  5587.1  378.74  5708.9  382.53  5754.9  382.77
#Mann= 7 ,-1 , 0
  3522.1     .05       0  3648.7      .1       0  3877.6     .05       0
  3942.1    .033       0  3948.1     .05       0  5180.5     .16       0
  5287.7      .1       0
Bank Sta=3908.9,5297.1
XS Rating Curve= 0 ,0
Exp/Cntr=0.3,0.1

Type RM Length L Ch R = 1 ,10632   ,939,939,939
BEGIN DESCRIPTION:
SANDERS CREEK 16.0
END DESCRIPTION:
XS GIS Cut Line= 4
      3548442.63      10506450.2      3546817.65     10508651.57
      3546519.04     10509804.34      3545956.81     10512074.06
#Sta/Elev= 30
  2066.4  411.38  2188.3  408.48  2668.4     393  2844.3  387.88  3020.2  384.24
  3183.8  379.72  3254.8  370.13  3576.3  390.13  3720.6   377.6  3957.6  366.45
  3977.3  366.05  4059.9  359.91  4062.6  359.41  4065.9  359.91  4075.5  360.16
    5481  361.88  5505.1  366.74  5505.8  366.78  5695.1  378.43  5841.2  379.87
    6067  365.09  6193.7     363  6325.6  364.59  6694.2  382.57  6994.5  387.73
  7294.8   381.4  7333.7  375.94  7430.9  385.36  7892.8  395.62  8331.7   401.3
#Mann= 20 ,-1 , 0
  2066.4      .1       0  2188.3     .05       0  2668.4      .1       0
  2844.3     .16       0  3020.2     .16       0  3720.6     .16       0
  3957.6     .16       0  4059.9    .033       0  4065.9     .16       0
  4075.5     .05       0  5505.8     .16       0  5695.1     .16       0
    6067     .05       0  6193.7     .16       0  6325.6      .1       0
  6694.2     .05       0  6994.5     .05       0  7294.8     .16       0
  7430.9     .05       0  7892.8      .1       0
#XS Ineff= 2 , 0
                         5801.04          380.37
Permanent Ineff=
       F       F
Bank Sta=3977.3,5505.1
XS Rating Curve= 0 ,0
Exp/Cntr=0.3,0.1

Type RM Length L Ch R = 1 ,9693    ,716,716,716
BEGIN DESCRIPTION:
SANDERS CREEK 14.0
END DESCRIPTION:
XS GIS Cut Line= 3
      3547269.04     10507151.57      3545602.37     10509269.62
      3545623.18     10510948.42
#Sta/Elev= 30
    2721  392.23  2809.1  389.81  2854.1  387.84  2883.2  388.26  3056.8  380.63
  3075.5  379.72  3096.3  376.07  3125.2  375.34    3146  377.22  3210.1  377.97
  3466.7  377.69  3566.2  382.65  3651.4  382.38  3777.3  375.97  3851.9  371.99
  3936.6  365.66  3948.1     363  3950.8   362.5  3954.1     363  5788.2     363
  5800.7  364.73  5848.2  366.13  5948.2  373.24  6028.2  377.14  6313.6  383.75
  6370.4  385.53  6538.3  391.57  6927.4  390.69  7064.5  390.15  7095.1  390.28
#Mann= 13 ,-1 , 0
    2721     .16       0  2809.1      .1       0  2883.2     .16       0
  3056.8      .1       0  3651.4     .08       0  3777.3      .1       0
  3851.9     .05       0  3948.1    .033       0  3954.1     .05       0
  6313.6     .08       0  6370.4     .05       0  6927.4      .1       0
  7064.5     .05       0
Bank Sta=3936.6,5800.7
XS Rating Curve= 0 ,0
Exp/Cntr=0.3,0.1

Type RM Length L Ch R = 1 ,8977    ,1015,1015,1015
BEGIN DESCRIPTION:
SANDERS CREEK 13.0
END DESCRIPTION:
XS GIS Cut Line= 4
      3546842.12     10507341.63      3545734.32      10508047.4
      3544727.37     10509221.01      3544928.76     10510714.08
#Sta/Elev= 30
  2935.3  388.71  3039.5   386.8  3167.2  381.03  3276.4  378.16  3385.6  377.59
  3761.5  384.69    3935  384.48  4006.7  383.98  4088.7  380.25  4178.7  376.11
    4365  366.68  4373.5   366.2  4438.2     363  5628.5     363  5671.8     363
  5675.4  361.61  5678.2  361.11  5681.4  361.61  5721.2  366.31  5770.6  371.64
  5856.4  375.97  6025.1  376.79    6102  379.48  6215.8  381.26  6411.4   381.5
  6754.4  378.87  6985.8  384.36  7117.7  384.86  7219.1  388.84  7301.8  388.53
#Mann= 13 ,-1 , 0
  2935.3     .16       0  3039.5      .1       0    3935     .08       0
  4006.7     .05       0  4088.7      .1       0  4178.7     .16       0
    4365     .05       0  5628.5      .1       0  5675.4    .033       0
  5681.4      .1       0  6025.1     .08       0    6102      .1       0
  6215.8     .05       0
Bank Sta=4373.5,5721.2
XS Rating Curve= 0 ,0
Exp/Cntr=0.3,0.1

Type RM Length L Ch R = 1 ,7962    ,825,825,825
BEGIN DESCRIPTION:
SANDERS CREEK 11.0
END DESCRIPTION:
XS GIS Cut Line= 3
      3547142.14     10506341.62      3544742.11     10507741.64
       3543942.1     10509941.67
#Sta/Elev= 30
  2247.4  399.26  2338.5  395.65  2495.9  391.16    2811  373.93  2826.3  374.48
  2832.5  377.76  2838.3  375.36  2848.2  379.27  3014.4  385.32  3067.3   392.3
    3162  392.12  3286.5   377.3  3445.5  366.22  3452.7  365.67  3565.7     363
  5804.7   362.9  5845.3  365.85  6206.4  380.39  6429.8  377.05  6483.7  375.93
  6646.3  362.16    6649  361.66  6652.3  362.16  6674.6  365.54  6737.3  366.52
    7031  381.24  7068.9  378.06  7142.8  380.32  7209.3  386.55  7366.9  389.21
#Mann= 8 ,-1 , 0
  2247.4      .1       0  2338.5     .16       0  3445.5     .07       0
  3565.7     .05       0  6429.8      .1       0  6646.3    .033       0
  6652.3      .1       0  6737.3     .05       0
#XS Ineff= 2 , 0
                         6238.07          380.89
Permanent Ineff=
       F       F
Bank Sta=3452.7,5845.3
XS Rating Curve= 0 ,0
Exp/Cntr=0.3,0.1

Type RM Length L Ch R = 1 ,7137    ,0,0,0
BEGIN DESCRIPTION:
SANDERS CREEK 1.0
END DESCRIPTION:
XS GIS Cut Line= 4
      3546553.75     10505852.96      3544525.98     10506811.29
       3543935.7     10507471.01      3543067.93      10511087.9
#Sta/Elev= 30
  2437.5  405.76  2519.3   405.3  2542.1   402.1  2559.3   394.8  2581.4  392.84
  2701.4  378.63  2746.9  379.86  2775.2  385.08  2820.7  387.64  2892.1  378.07
  2934.6   371.3  3025.5  364.58  3028.9  363.62  6152.6     363  6384.1  364.13
  6673.7  376.62  6798.9  379.81  6976.4   368.6  7016.1  362.11  7018.9  361.61
  7022.1  362.11  7189.7  362.99  7339.1  367.77  7617.4  384.36  7859.5  382.05
    8096  389.44  8903.1  405.44  9118.2  415.58  9227.2  412.56  9285.1  414.43
#Mann= 12 ,-1 , 0
  2437.5      .1       0  2581.4     .16       0  2892.1     .07       0
  3028.9     .05       0  6152.6     .07       0  6384.1     .05       0
  6673.7      .1       0  6976.4     .05       0  7016.1    .033       0
  7022.1     .05       0  7189.7      .1       0  7339.1     .05       0
#XS Ineff= 2 , 0
                          6772.1          379.95
Permanent Ineff=
       F       F
Bank Sta=3025.5,6384.1
XS Rating Curve= 0 ,0
Exp/Cntr=0.3,0.1

Chan Stop Cuts=-1
Use User Specified Reach Order=0
Composite Channel Slope=5