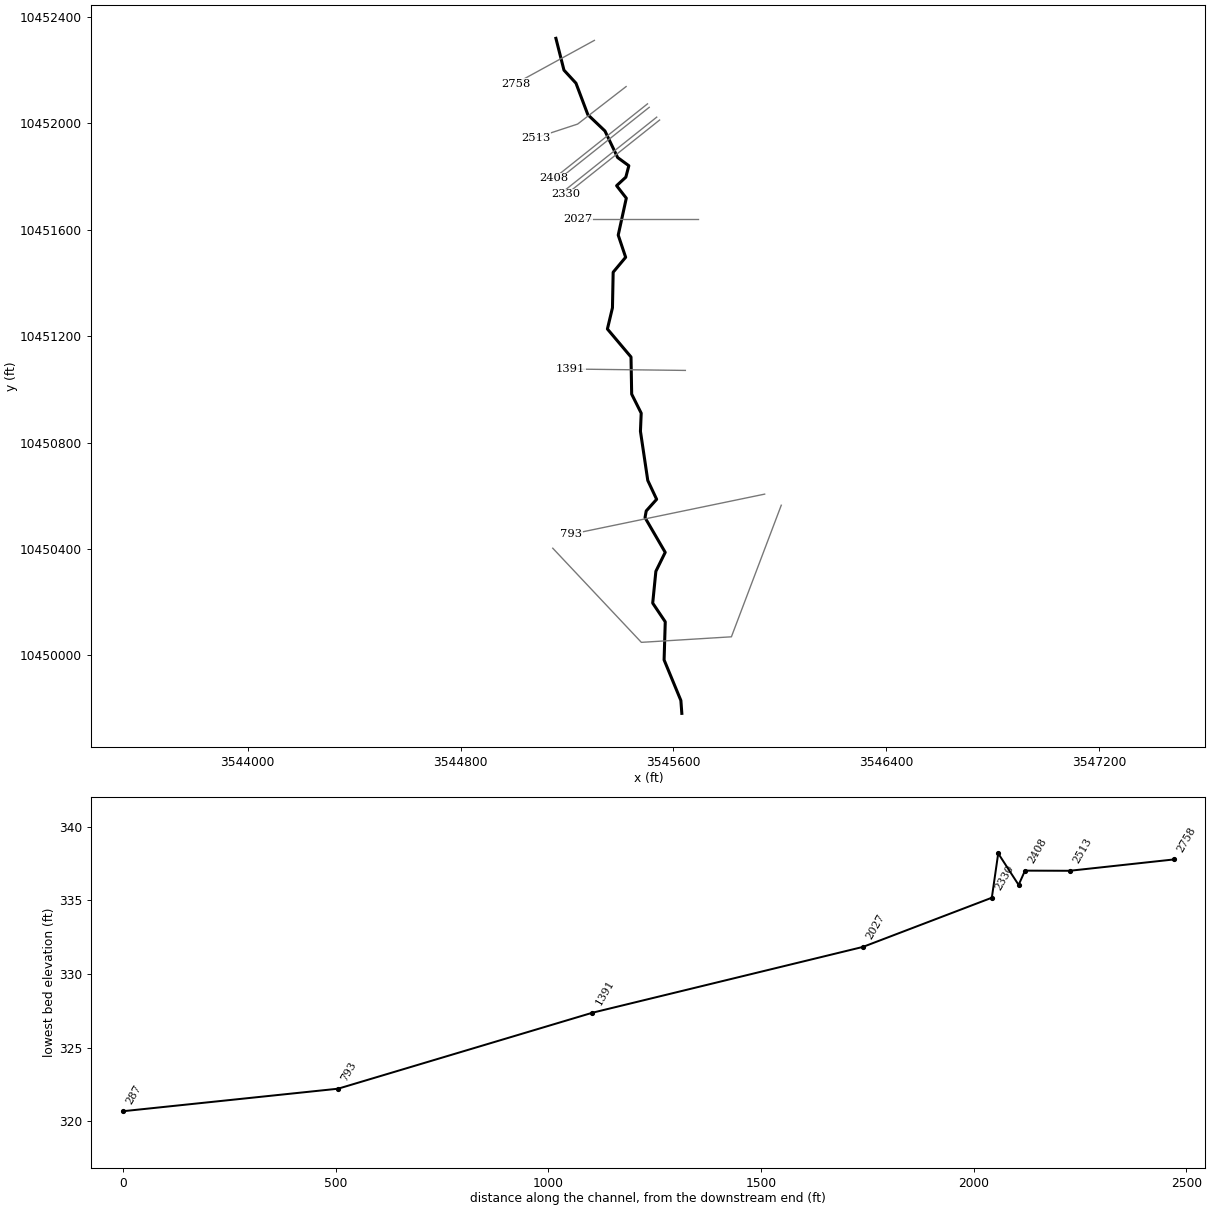
--- SANDYBRTRIB2.prj (project) ---

Proj Title=SANDY BRANCH TRIBUTARY 2
Current Plan=p01
Default Exp/Contr=0.3,0.1
English Units
Geom File=g01
Flow File=f01
Plan File=p01
Y Axis Title=Elevation
X Axis Title(PF)=Main Channel Distance
X Axis Title(XS)=Station
BEGIN DESCRIPTION:
UNT02313 IN SAND CR
END DESCRIPTION:
DSS Export Rating Curves= 0
DSS Export Rating Curve Sorted= 0
DSS Export Volume Flow Curves= 0
DXF OffsetX= 0
DXF OffsetY= 0
DXF ScaleX= 1
DXF ScaleY= 10

--- SANDYBRTRIB2.p01 (plan) ---

Plan Title=Multiple Run
Short Identifier=Multiple
Geom File=g01
Flow File=f01
Subcritical Flow
K Sum by GR= 0
Std Step Tol= 0.01
Critical Tol= 0.01
Num of Std Step Trials= 20
Max Error Tol= 0.3
Flow Tol Ratio= 0.001
Split Flow NTrial= 30
Split Flow Tol= 0.02
Split Flow Ratio= 0.02
Log Output Level= 0
Friction Slope Method= 1
Unsteady Friction Slope Method= 2
Unsteady Bridges Friction Slope Method= 1
Parabolic Critical Depth
Global Vel Dist=  1 , 1 , 1
Global Log Level= 0
CheckData=True
Encroach Param= -1, 0, 0, 0
BEGIN DESCRIPTION:
Multiple Run
END DESCRIPTION:

--- SANDYBRTRIB2.f01 (steady flow) ---

Flow Title=Multiple
Program Version=4.10
Number of Profiles= 7
Profile Names=10-year,25-year,50-year,1pct_min,100-year,1pct_plu,500-year
River Rch & RM=UNT02313 IN SAND,Reach-1         ,2758
     395     511     601     517     699     946     943
River Rch & RM=SANDYBRTRIB2,Reach-1         ,2758
     395     511     601     517     699     946     943
Boundary for River Rch & Prof#=SANDYBRTRIB2,Reach-1         , 1
Up Type= 0
Dn Type= 3
Dn Slope=0.005
Boundary for River Rch & Prof#=SANDYBRTRIB2,Reach-1         , 2
Up Type= 0
Dn Type= 3
Dn Slope=0.005
Boundary for River Rch & Prof#=SANDYBRTRIB2,Reach-1         , 3
Up Type= 0
Dn Type= 3
Dn Slope=0.005
Boundary for River Rch & Prof#=SANDYBRTRIB2,Reach-1         , 4
Up Type= 0
Dn Type= 3
Dn Slope=0.005
Boundary for River Rch & Prof#=SANDYBRTRIB2,Reach-1         , 5
Up Type= 0
Dn Type= 3
Dn Slope=0.005
Boundary for River Rch & Prof#=SANDYBRTRIB2,Reach-1         , 6
Up Type= 0
Dn Type= 3
Dn Slope=0.005
Boundary for River Rch & Prof#=SANDYBRTRIB2,Reach-1         , 7
Up Type= 0
Dn Type= 3
Dn Slope=0.005
DSS Import GetInterval= 0
DSS Import GetPeak= 0
DSS Import FillOption= 0

--- SANDYBRTRIB2.g01 (geometry) ---

Geom Title=Existing Conditions
Program Version=4.10

River Reach=SANDYBRTRIB2    ,Reach-1
Reach XY= 30
      3545158.67     10452319.63      3545188.97     10452200.04
      3545234.11     10452150.99      3545278.81      10452032.5
      3545343.05      10451971.3      3545390.79     10451871.48
      3545432.89     10451840.66      3545421.61     10451797.69
      3545386.89     10451765.57      3545423.35      10451718.7
      3545392.96     10451579.81      3545420.89     10451496.47
      3545373.95     10451440.29      3545371.28     10451306.48
      3545352.31     10451226.83      3545441.02     10451121.58
      3545443.54     10450981.93      3545479.37      10450910.4
      3545476.51     10450842.38      3545504.08     10450657.36
      3545537.39     10450586.48      3545498.24     10450542.76
      3545493.75     10450517.54      3545569.65     10450387.05
      3545534.51     10450315.71      3545522.62     10450196.15
      3545569.81     10450125.88      3545565.45     10449982.66
      3545628.51     10449830.15      3545632.11     10449781.64

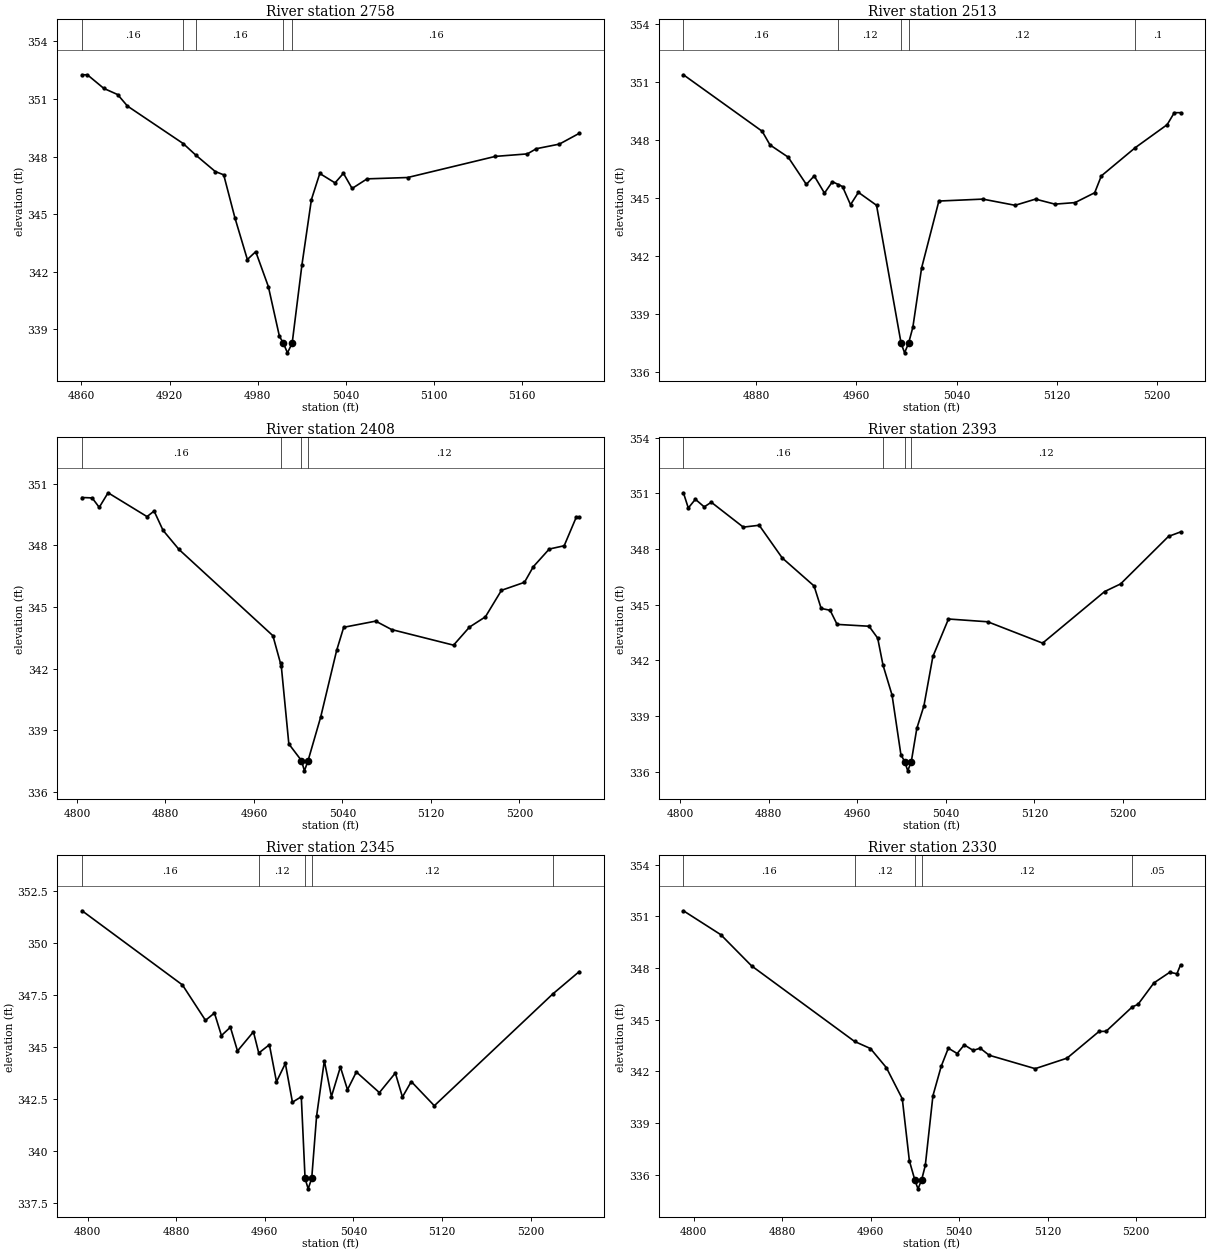
Type RM Length L Ch R = 1 ,2758    ,245,245,245
BEGIN DESCRIPTION:
UNT02313 IN SAND CR 5.1
END DESCRIPTION:
XS GIS Cut Line= 2
      3545303.36     10452311.99      3545006.52     10452149.49
#Sta/Elev= 30
  4860.4  352.26    4864  352.26  4875.2  351.55  4884.6  351.23  4891.3  350.63
  4929.2  348.68  4937.9  348.07  4951.1  347.22  4956.8  347.05  4964.4  344.82
  4972.9  342.64  4978.6  343.05  4987.2  341.23  4994.7  338.65  4997.4  338.28
  5000.2  337.78  5003.4  338.28    5010  342.33  5016.5  345.76  5022.2  347.12
  5032.6  346.63  5038.3  347.13  5044.2  346.34  5054.4  346.84    5082  346.91
  5141.7  348.01  5163.5  348.14  5169.6  348.41  5185.3  348.65  5198.8  349.21
#Mann= 5 ,-1 , 0
  4860.4     .16       0  4929.2     .12       0  4937.9     .16       0
  4997.4     .07       0  5003.4     .16       0
Bank Sta=4997.4,5003.4
XS Rating Curve= 0 ,0
Exp/Cntr=0.3,0.1

Type RM Length L Ch R = 1 ,2513    ,105,105,105
BEGIN DESCRIPTION:
UNT02313 IN SAND CR 5.0
END DESCRIPTION:
XS GIS Cut Line= 3
      3545422.65     10452138.33      3545240.39      10451997.3
      3545081.98     10451945.22
#Sta/Elev= 30
  4821.8  351.39  4884.7  348.47    4891  347.76  4905.5  347.13    4920  345.72
  4926.3  346.16  4934.5  345.27  4940.8  345.86  4945.7  345.71  4948.9  345.61
  4955.3  344.67  4961.6  345.31  4976.1  344.64  4995.7  337.51  4998.5  337.01
  5001.7  337.51  5005.1  338.33  5012.1   341.4  5025.9  344.86    5061  344.96
  5086.8  344.64  5103.1  344.96  5118.6   344.7  5134.7  344.78  5150.4  345.29
  5155.7  346.16  5182.8  347.62  5208.3  348.81    5214  349.43    5219  349.43
#Mann= 5 ,-1 , 0
  4821.8     .16       0  4945.7     .12       0  4995.7     .07       0
  5001.7     .12       0  5182.8      .1       0
Bank Sta=4995.7,5001.7
XS Rating Curve= 0 ,0
Exp/Cntr=0.3,0.1

Type RM Length L Ch R = 1 ,2408    ,15,15,15
BEGIN DESCRIPTION:
UNT02313 IN SAND CR 5.2
END DESCRIPTION:
XS GIS Cut Line= 2
      3545503.01     10452073.28      3545151.45     10451793.33
#Sta/Elev= 30
  4804.6  350.33  4813.7  350.31  4820.1  349.85  4828.1  350.56  4863.3   349.4
  4869.7  349.67  4877.8  348.73  4892.2   347.8  4977.1   343.6    4984  342.25
  4984.7  342.11  4991.5  338.33  5002.9  337.52  5005.6  337.02  5008.9  337.52
  5020.3  339.64  5034.7  342.88  5041.1  344.01    5070  344.31  5084.4   343.9
  5140.4  343.14  5154.8  344.02  5169.2  344.52  5183.7  345.81  5204.5   346.2
  5212.5  346.96  5226.9  347.82  5240.4  347.98  5251.4  349.38    5254  349.38
#Mann= 4 ,-1 , 0
  4804.6     .16       0    4984     .12       0  5002.9     .07       0
  5008.9     .12       0
Bank Sta=5002.9,5008.9
XS Rating Curve= 0 ,0
Exp/Cntr=0.3,0.1

Type RM Length L Ch R = 1 ,2393    ,48,48,48
BEGIN DESCRIPTION:
UNT02313 IN SAND CR 5.4
END DESCRIPTION:
XS GIS Cut Line= 2
       3545509.5     10452060.25      3545157.95      10451780.3
#Sta/Elev= 30
  4802.8  351.03  4807.2  350.21  4813.6  350.68  4821.6  350.27    4828  350.52
  4856.9  349.18  4871.3  349.28  4892.1  347.52  4920.9  346.01  4927.3   344.8
  4935.4   344.7  4941.7  343.94  4970.6  343.84  4978.4   343.2  4983.2  341.75
  4991.4  340.13  4999.4  336.92  5002.8  336.55  5005.6  336.05  5008.8  336.55
  5013.8  338.34  5020.2  339.55  5028.3  342.21  5042.4  344.23  5077.9  344.08
  5127.5  342.93  5183.6  345.71    5198  346.12  5241.3  348.68  5252.2  348.92
#Mann= 4 ,-1 , 0
  4802.8     .16       0  4983.2     .12       0  5002.8     .07       0
  5008.8     .12       0
Bank Sta=5002.8,5008.8
XS Rating Curve= 0 ,0
Exp/Cntr=0.3,0.1

Type RM Length L Ch R = 1 ,2345    ,15,15,15
BEGIN DESCRIPTION:
UNT02313 IN SAND CR 5.3
END DESCRIPTION:
XS GIS Cut Line= 2
      3545537.69     10452023.33       3545186.6     10451743.76
#Sta/Elev= 30
  4795.1  351.54  4885.7  347.98  4906.5  346.28  4914.6  346.63  4920.9  345.55
    4929  345.95  4935.4  344.81  4949.8  345.73  4954.6  344.71  4964.2  345.11
  4970.6  343.33  4978.6  344.21    4985  342.35    4993  342.61  4996.4  338.69
  4999.2  338.19  5002.4  338.69  5006.8  341.68  5013.8  344.34  5020.2  342.62
  5028.3  344.04  5034.7  342.95  5042.7   343.8  5063.5  342.81  5077.9  343.75
  5084.3   342.6  5092.3  343.34  5113.1  342.18  5219.9  347.54  5243.9  348.62
#Mann= 5 ,-1 , 0
  4795.1     .16       0  4954.6     .12       0  4996.4     .07       0
  5002.4     .12       0  5219.9     .05       0
Bank Sta=4996.4,5002.4
XS Rating Curve= 0 ,0
Exp/Cntr=0.3,0.1

Type RM Length L Ch R = 1 ,2330    ,303,303,303
BEGIN DESCRIPTION:
UNT02313 IN SAND CR 5.5
END DESCRIPTION:
XS GIS Cut Line= 2
      3545548.54     10452012.48      3545197.06      10451732.6
#Sta/Elev= 30
  4790.8  351.33  4824.6  349.94  4852.4  348.13  4945.5  343.74  4959.8  343.33
  4974.2  342.22  4988.6  340.41    4995  336.81    5000  335.68  5002.8  335.18
    5006  335.68  5009.4  336.54  5016.3  340.59  5023.8   342.3  5030.2  343.35
  5038.2  343.04  5044.6  343.54  5052.7  343.22    5059  343.35  5067.1  342.94
  5108.7  342.16  5137.5  342.77  5166.4  344.32  5172.8  344.33  5196.5  345.75
  5201.6  345.89    5216  347.14  5230.4  347.76  5236.8  347.67  5240.1  348.19
#Mann= 5 ,-1 , 0
  4790.8     .16       0  4945.5     .12       0    5000     .07       0
    5006     .12       0  5196.5     .05       0
Bank Sta=5000,5006
XS Rating Curve= 0 ,0
Exp/Cntr=0.3,0.1

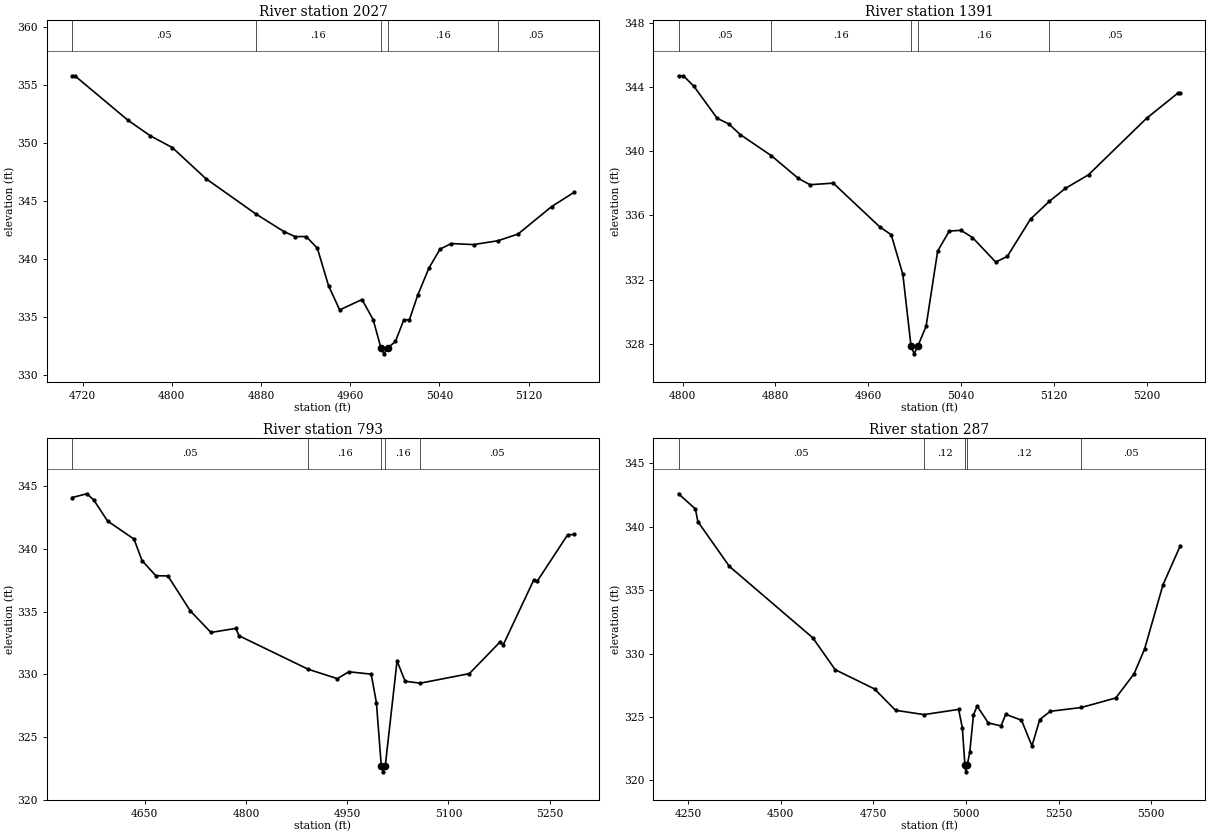
Type RM Length L Ch R = 1 ,2027    ,636,636,636
BEGIN DESCRIPTION:
UNT02313 IN SAND CR 4.0
END DESCRIPTION:
XS GIS Cut Line= 3
      3545692.09     10451641.64      3545392.11     10451641.64
      3545242.09     10451641.64
#Sta/Elev= 30
  4710.6  355.79  4713.1  355.79  4760.6  351.97  4780.6  350.63  4800.6   349.6
  4830.6  346.93  4875.1  343.91  4900.6  342.37  4910.6  341.94  4920.6  341.94
  4930.6  340.93  4940.6  337.71  4950.6  335.62  4970.6  336.52  4980.6  334.79
  4987.6  332.34  4990.3  331.84  4993.6  332.34  5000.6  332.91  5008.1  334.77
  5013.1  334.77  5020.6   336.9  5030.6  339.22  5040.6  340.86  5050.6  341.34
  5070.6  341.25  5092.5  341.58  5110.6  342.16  5140.6  344.52  5160.6  345.74
#Mann= 5 ,-1 , 0
  4710.6     .05       0  4875.1     .16       0  4987.6     .07       0
  4993.6     .16       0  5092.5     .05       0
Bank Sta=4987.6,4993.6
XS Rating Curve= 0 ,0
Exp/Cntr=0.3,0.1

Type RM Length L Ch R = 1 ,1391    ,598,598,598
BEGIN DESCRIPTION:
UNT02313 IN SAND CR 3.0
END DESCRIPTION:
XS GIS Cut Line= 2
      3545645.37     10451071.08      3545213.01     10451076.29
#Sta/Elev= 30
  4796.5   344.7  4800.7   344.7  4809.8  344.04  4829.8  342.05  4839.8   341.7
  4849.8  341.03  4876.5  339.72  4899.8   338.3  4909.8  337.91  4929.8  338.01
  4969.8  335.29  4979.8  334.79  4989.8  332.32  4996.8  327.87  4999.5  327.37
  5002.8  327.87  5009.8  329.08  5019.8  333.78  5029.8  335.02  5039.8  335.07
  5049.8  334.62  5069.8  333.09  5079.8  333.44  5099.8  335.77  5116.1  336.88
  5129.8  337.68  5149.8  338.53  5199.8  342.05  5226.8  343.62  5228.9  343.62
#Mann= 5 ,-1 , 0
  4796.5     .05       0  4876.5     .16       0  4996.8     .07       0
  5002.8     .16       0  5116.1     .05       0
Bank Sta=4996.8,5002.8
XS Rating Curve= 0 ,0
Exp/Cntr=0.3,0.1

Type RM Length L Ch R = 1 ,793     ,506,506,506
BEGIN DESCRIPTION:
UNT02313 IN SAND CR 1.0
END DESCRIPTION:
XS GIS Cut Line= 2
      3545943.54     10450605.98       3545215.7     10450455.22
#Sta/Elev= 30
  4542.5  344.11  4564.4  344.41  4574.6  343.92    4595  342.24  4634.3  340.79
  4646.1  339.08  4666.5  337.87  4684.5  337.85  4717.6  335.06  4748.2  333.34
  4784.9  333.66    4790  333.07  4892.3   330.4  4935.4  329.65  4952.5   330.2
  4985.6  330.01  4993.3  327.74  5000.5  322.71  5003.3  322.21  5006.5  322.71
  5023.9  331.07  5035.8  329.44  5058.4  329.29    5131  330.05  5176.1  332.56
  5181.2  332.35  5226.3  337.52  5231.4  337.42  5276.5  341.13  5285.8  341.16
#Mann= 5 ,-1 , 0
  4542.5     .05       0  4892.3     .16       0  5000.5     .07       0
  5006.5     .16       0  5058.4     .05       0
Bank Sta=5000.5,5006.5
XS Rating Curve= 0 ,0
Exp/Cntr=0.3,0.1

Type RM Length L Ch R = 1 ,287     ,0,0,0
BEGIN DESCRIPTION:
UNT02313 IN SAND CR 1.1
END DESCRIPTION:
XS GIS Cut Line= 4
        3546006.     10450564.28      3545818.51     10450069.52
      3545479.97     10450048.69      3545146.86     10450402.61
#Sta/Elev= 30
  4224.1  342.59  4269.7  341.39  4276.2   340.4  4361.3  336.87  4586.5  331.24
  4646.8  328.73  4753.2  327.21  4809.7  325.53  4886.5  325.19    4980   325.6
    4990  324.17  4997.1  321.18  4999.8  320.68  5003.1  321.18  5010.1  322.23
  5020.1  325.17  5030.1  325.86  5060.2  324.53  5094.5   324.3  5107.2  325.21
  5149.7  324.75    5178  322.72  5199.1   324.8  5227.4  325.45  5311.2  325.75
  5404.2   326.5  5453.5   328.4  5481.9  330.35  5531.6  335.42  5578.4   338.5
#Mann= 5 ,-1 , 0
  4224.1     .05       0  4886.5     .12       0  4997.1     .07       0
  5003.1     .12       0  5311.2     .05       0
Bank Sta=4997.1,5003.1
XS Rating Curve= 0 ,0
Exp/Cntr=0.3,0.1

Chan Stop Cuts=-1
Use User Specified Reach Order=0
Composite Channel Slope=5