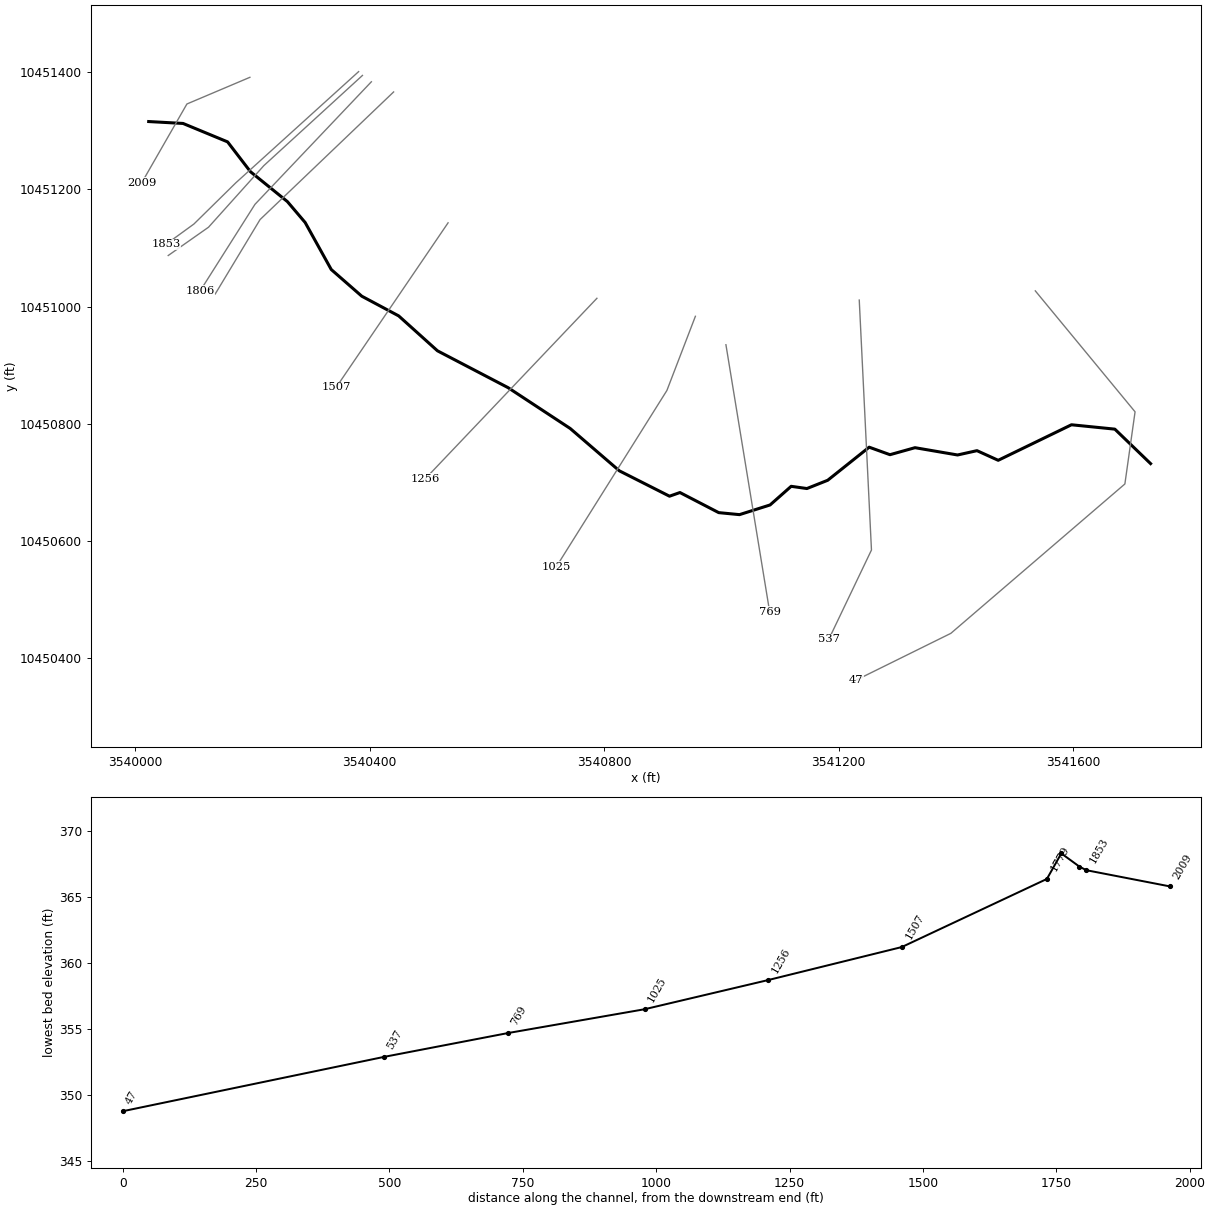
--- SANDYBRTRB41.prj (project) ---

Proj Title=SANDY BRANCH TRIBUTARY 4 1
Current Plan=p01
Default Exp/Contr=0.3,0.1
English Units
Geom File=g01
Flow File=f01
Plan File=p01
Y Axis Title=Elevation
X Axis Title(PF)=Main Channel Distance
X Axis Title(XS)=Station
BEGIN DESCRIPTION:
UNT02312 IN SAND CR
END DESCRIPTION:
DSS Export Rating Curves= 0
DSS Export Rating Curve Sorted= 0
DSS Export Volume Flow Curves= 0
DXF Filename=UNT02312 IN SAND CR.
DXF OffsetX= 0
DXF OffsetY= 0
DXF ScaleX= 1
DXF ScaleY= 10

--- SANDYBRTRB41.p01 (plan) ---

Plan Title=Multiple Run
Short Identifier=Multiple
Geom File=g01
Flow File=f01
Subcritical Flow
K Sum by GR= 0
Std Step Tol= 0.01
Critical Tol= 0.01
Num of Std Step Trials= 20
Max Error Tol= 0.3
Flow Tol Ratio= 0.001
Split Flow NTrial= 30
Split Flow Tol= 0.02
Split Flow Ratio= 0.02
Log Output Level= 0
Friction Slope Method= 1
Unsteady Friction Slope Method= 2
Unsteady Bridges Friction Slope Method= 1
Parabolic Critical Depth
Global Vel Dist=  1 , 1 , 1
Global Log Level= 0
CheckData=True
Encroach Param= -1, 0, 0, 0
BEGIN DESCRIPTION:
Multiple Run
END DESCRIPTION:

--- SANDYBRTRB41.f01 (steady flow) ---

Flow Title=Multiple
Program Version=4.10
Number of Profiles= 7
Profile Names=10-year,25-year,50-year,1pct_min,100-year,1pct_plu,500-year
River Rch & RM=UNT02312 IN SAND,Reach-1         ,2009
     265     336     391     334     451     610     598
River Rch & RM=UNT02312 IN SAND,Reach-1         ,47
     597     798     960     844    1142    1544    1610
River Rch & RM=SANDYBRTRIB41,Reach-1         ,2009
     265     336     391     334     451     610     598
River Rch & RM=SANDYBRTRIB41,Reach-1         ,47
     597     798     960     844    1142    1544    1610
Boundary for River Rch & Prof#=SANDYBRTRIB41,Reach-1         , 1
Up Type= 0
Dn Type= 3
Dn Slope=0.005
Boundary for River Rch & Prof#=SANDYBRTRIB41,Reach-1         , 2
Up Type= 0
Dn Type= 3
Dn Slope=0.005
Boundary for River Rch & Prof#=SANDYBRTRIB41,Reach-1         , 3
Up Type= 0
Dn Type= 3
Dn Slope=0.005
Boundary for River Rch & Prof#=SANDYBRTRIB41,Reach-1         , 4
Up Type= 0
Dn Type= 3
Dn Slope=0.005
Boundary for River Rch & Prof#=SANDYBRTRIB41,Reach-1         , 5
Up Type= 0
Dn Type= 3
Dn Slope=0.005
Boundary for River Rch & Prof#=SANDYBRTRIB41,Reach-1         , 6
Up Type= 0
Dn Type= 3
Dn Slope=0.005
Boundary for River Rch & Prof#=SANDYBRTRIB41,Reach-1         , 7
Up Type= 0
Dn Type= 3
Dn Slope=0.005
DSS Import GetInterval= 0
DSS Import GetPeak= 0
DSS Import FillOption= 0

--- SANDYBRTRB41.g01 (geometry) ---

Geom Title=Existing Conditions
Program Version=4.10

River Reach=SANDYBRTRIB41   ,Reach-1
Reach XY= 30
      3540023.05     10451316.06      3540081.64     10451312.81
       3540157.6     10451281.34      3540196.66     10451230.34
      3540259.59     10451179.34      3540289.97     10451143.54
      3540334.46     10451063.24      3540386.54     10451017.67
      3540449.48     10450984.03      3540515.67     10450924.35
      3540636.11     10450861.42      3540742.11     10450791.64
        3540826.     10450719.27      3540911.46     10450675.98
      3540929.26     10450682.23      3540995.42      10450647.9
      3541030.84     10450644.48      3541083.02     10450661.01
        3541119.     10450692.86      3541145.84     10450689.06
      3541181.34      10450703.2      3541252.06     10450759.71
      3541287.56     10450746.89      3541330.22     10450758.85
      3541402.84      10450746.4      3541435.96     10450753.77
      3541472.17     10450737.31      3541597.14     10450798.01
      3541671.13     10450790.55      3541732.11     10450731.64

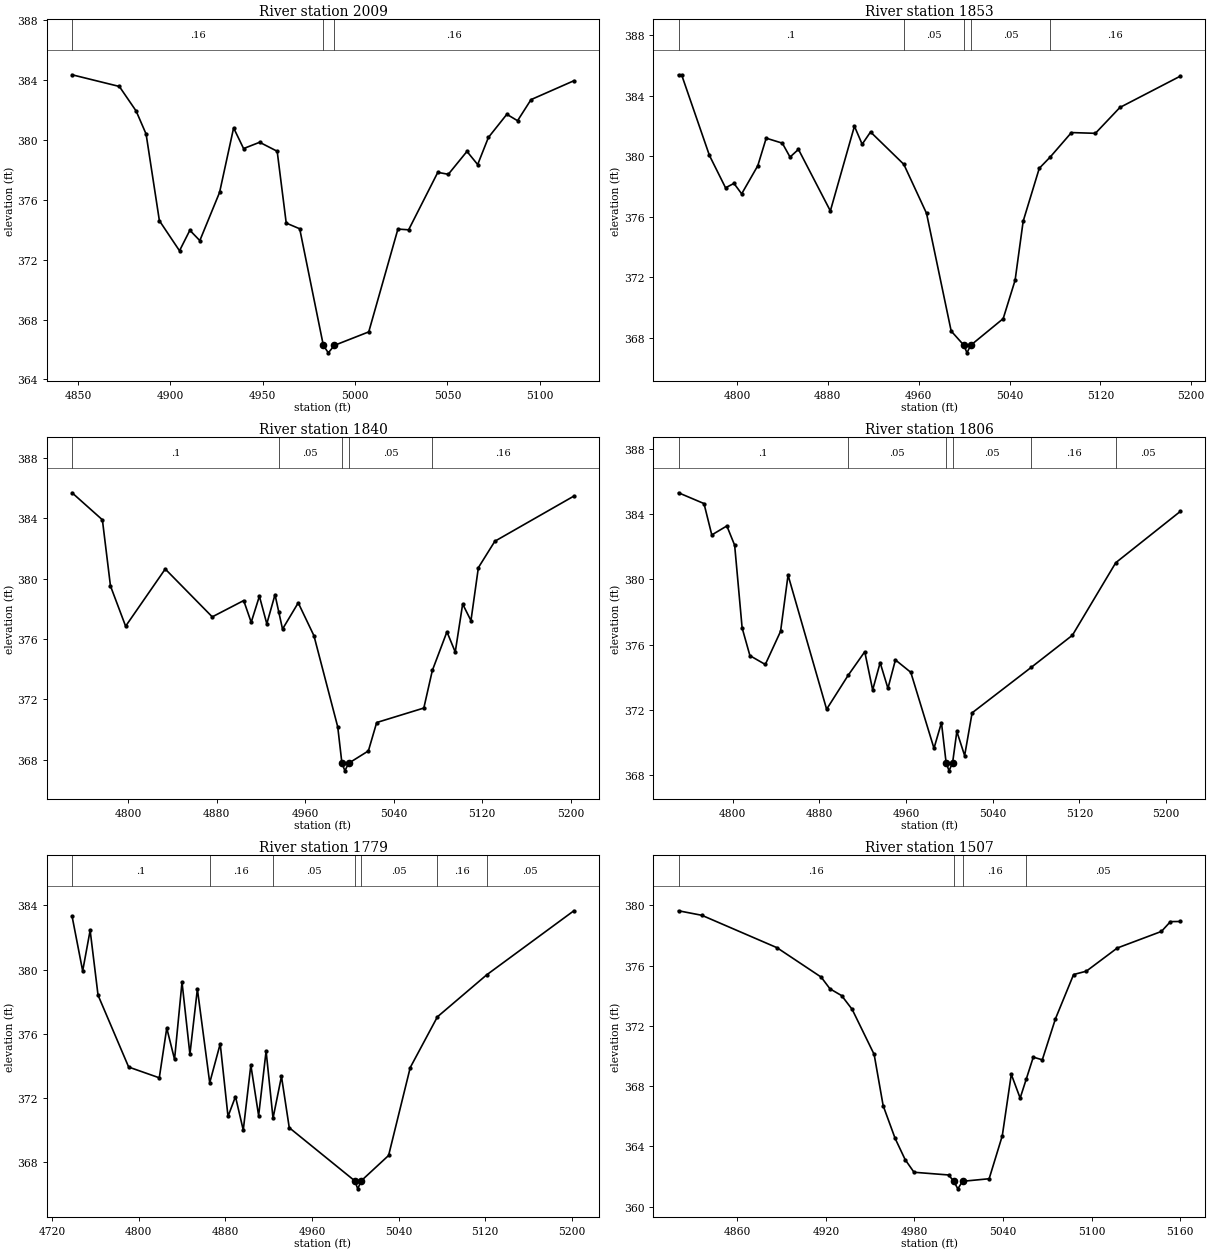
Type RM Length L Ch R = 1 ,2009    ,156,156,156
BEGIN DESCRIPTION:
UNT02312 IN SAND CR 4.0
END DESCRIPTION:
XS GIS Cut Line= 3
      3540195.68     10451391.63      3540088.22     10451346.04
      3540011.17     10451211.47
#Sta/Elev= 30
  4846.7  384.36  4872.3  383.58  4881.4  381.94  4886.8   380.4    4894  374.61
  4904.9   372.6  4910.5  373.97  4915.9  373.28  4926.6   376.5  4934.2  380.81
  4939.6  379.43  4948.3  379.85  4957.8  379.25  4962.7  374.45    4970  374.07
  4982.8  366.28  4985.5  365.78  4988.8  366.28  5007.4  367.18  5023.2  374.05
    5029     374  5044.8  377.84  5050.5  377.71  5060.6  379.24  5066.4  378.36
  5072.2  380.17  5082.2  381.72    5088  381.29  5095.3   382.7  5118.5  383.96
#Mann= 3 ,-1 , 0
  4846.7     .16       0  4982.8     .07       0  4988.8     .16       0
Bank Sta=4982.8,4988.8
XS Rating Curve= 0 ,0
Exp/Cntr=0.3,0.1

Type RM Length L Ch R = 1 ,1853    ,13,13,13
BEGIN DESCRIPTION:
UNT02312 IN SAND CR 1.5
END DESCRIPTION:
XS GIS Cut Line= 4
      3540381.16     10451401.36      3540171.77     10451211.49
      3540100.16     10451140.96      3540052.66     10451106.42
#Sta/Elev= 30
  4748.5  385.38  4751.2  385.38  4775.7  380.05  4789.9  377.91  4797.3   378.2
  4804.1  377.51  4818.3  379.37  4825.7  381.19  4839.9  380.86  4846.7  379.94
  4854.1  380.45  4882.2  376.38  4903.4  381.98  4910.2  380.79  4917.6   381.6
  4946.9  379.46  4966.9  376.22  4988.6  368.44  4999.8   367.5  5002.5     367
  5005.8   367.5  5034.4  369.26  5044.9   371.8    5052   375.7  5066.2   379.2
  5075.9  379.95  5094.5  381.56  5115.6  381.51  5137.2  383.22  5190.4  385.29
#Mann= 5 ,-1 , 0
  4748.5      .1       0  4946.9     .05       0  4999.8     .03       0
  5005.8     .05       0  5075.9     .16       0
Bank Sta=4999.8,5005.8
XS Rating Curve= 0 ,0
Exp/Cntr=0.3,0.1

Type RM Length L Ch R = 1 ,1840    ,34,34,34
BEGIN DESCRIPTION:
UNT02312 IN SAND CR 1.4
END DESCRIPTION:
XS GIS Cut Line= 4
      3540387.68     10451394.85      3540219.51     10451240.79
      3540125.11     10451135.54      3540056.36     10451087.19
#Sta/Elev= 30
  4749.4  385.69  4776.8   383.9  4784.1  379.52  4797.8  376.85  4833.6  380.64
  4876.1  377.47  4904.5  378.55  4911.3  377.11  4918.7  378.84  4925.4  377.01
  4932.8  378.94  4936.2   377.8  4939.6  376.66  4953.8   378.4    4968  376.22
  4989.5  370.18  4993.3  367.77    4996  367.27  4999.3  367.77  5017.2  368.59
  5024.7  370.47  5067.3  371.43    5075  373.92  5088.2  376.48  5095.7  375.14
  5102.4  378.32  5109.9  377.22  5116.6  380.73  5131.5  382.48  5202.9  385.47
#Mann= 5 ,-1 , 0
  4749.4      .1       0  4936.2     .05       0  4993.3     .03       0
  4999.3     .05       0    5075     .16       0
Bank Sta=4993.3,4999.3
XS Rating Curve= 0 ,0
Exp/Cntr=0.3,0.1

Type RM Length L Ch R = 1 ,1806    ,27,27,27
BEGIN DESCRIPTION:
UNT02312 IN SAND CR 1.3
END DESCRIPTION:
XS GIS Cut Line= 3
      3540402.89     10451384.02      3540204.32      10451174.6
      3540111.01     10451027.03
#Sta/Elev= 30
    4750  385.29  4773.5  384.63  4780.7  382.71  4794.6  383.26  4801.8  382.08
  4808.7  377.02  4815.9  375.32  4830.1  374.78  4844.2  376.81  4851.1  380.25
  4886.7  372.04  4906.5  374.11  4921.9  375.56  4929.2  373.22  4936.1  374.89
  4943.3  373.32  4950.2  375.06  4964.4   374.3  4985.8  369.65  4992.7  371.22
    4997  368.77  4999.7  368.27    5003  368.77  5006.9  370.68  5014.1   369.2
    5021  371.82  5075.5   374.6  5113.6  376.57  5153.6  381.01  5213.2  384.15
#Mann= 6 ,-1 , 0
    4750      .1       0  4906.5     .05       0    4997     .03       0
    5003     .05       0  5075.5     .16       0  5153.6     .05       0
Bank Sta=4997,5003
XS Rating Curve= 0 ,0
Exp/Cntr=0.3,0.1

Type RM Length L Ch R = 1 ,1779    ,272,272,272
BEGIN DESCRIPTION:
UNT02312 IN SAND CR 1.6
END DESCRIPTION:
XS GIS Cut Line= 3
      3540440.84     10451366.63        3540213.     10451148.56
      3540136.53     10451021.47
#Sta/Elev= 30
  4738.3  383.33  4748.1  379.92    4755  382.45  4762.3  378.41  4790.6  373.93
  4818.9  373.26  4825.8  376.36    4833  374.41  4839.9  379.22  4847.2  374.73
  4854.1  378.79  4865.5  372.95  4875.2  375.38  4882.4  370.85  4889.3  372.09
  4896.5     370  4903.5  374.05  4910.7   370.9  4917.6  374.93    4924  370.74
  4931.8  373.35    4939  370.15  4999.5  366.84  5002.3  366.34  5005.5  366.84
  5030.8  368.42  5050.8   373.9  5075.9  377.06  5121.5  379.68    5202  383.67
#Mann= 7 ,-1 , 0
  4738.3      .1       0  4865.5     .16       0    4924     .05       0
  4999.5     .03       0  5005.5     .05       0  5075.9     .16       0
  5121.5     .05       0
Bank Sta=4999.5,5005.5
XS Rating Curve= 0 ,0
Exp/Cntr=0.3,0.1

Type RM Length L Ch R = 1 ,1507    ,251,251,251
BEGIN DESCRIPTION:
UNT02312 IN SAND CR 3.0
END DESCRIPTION:
XS GIS Cut Line= 2
      3540533.74     10451143.04       3540342.8     10450861.84
#Sta/Elev= 30
  4820.2  379.64    4836  379.34  4886.9  377.19  4916.8  375.24  4922.8  374.46
  4930.7  374.01  4937.8   373.1  4952.7  370.11  4958.8  366.71  4966.9  364.54
  4973.7  363.13  4979.7  362.29  5003.2  362.11  5006.6  361.69  5009.4  361.19
  5012.6  361.69  5030.6  361.86  5039.5  364.71  5045.6  368.79  5051.6  367.21
  5055.8  368.49  5060.5  369.93  5066.6  369.75  5075.5  372.47  5087.8  375.41
  5096.4  375.63  5117.4  377.17  5147.3  378.27  5153.4  378.92  5160.1  378.93
#Mann= 4 ,-1 , 0
  4820.2     .16       0  5006.6     .07       0  5012.6     .16       0
  5055.8     .05       0
Bank Sta=5006.6,5012.6
XS Rating Curve= 0 ,0
Exp/Cntr=0.3,0.1

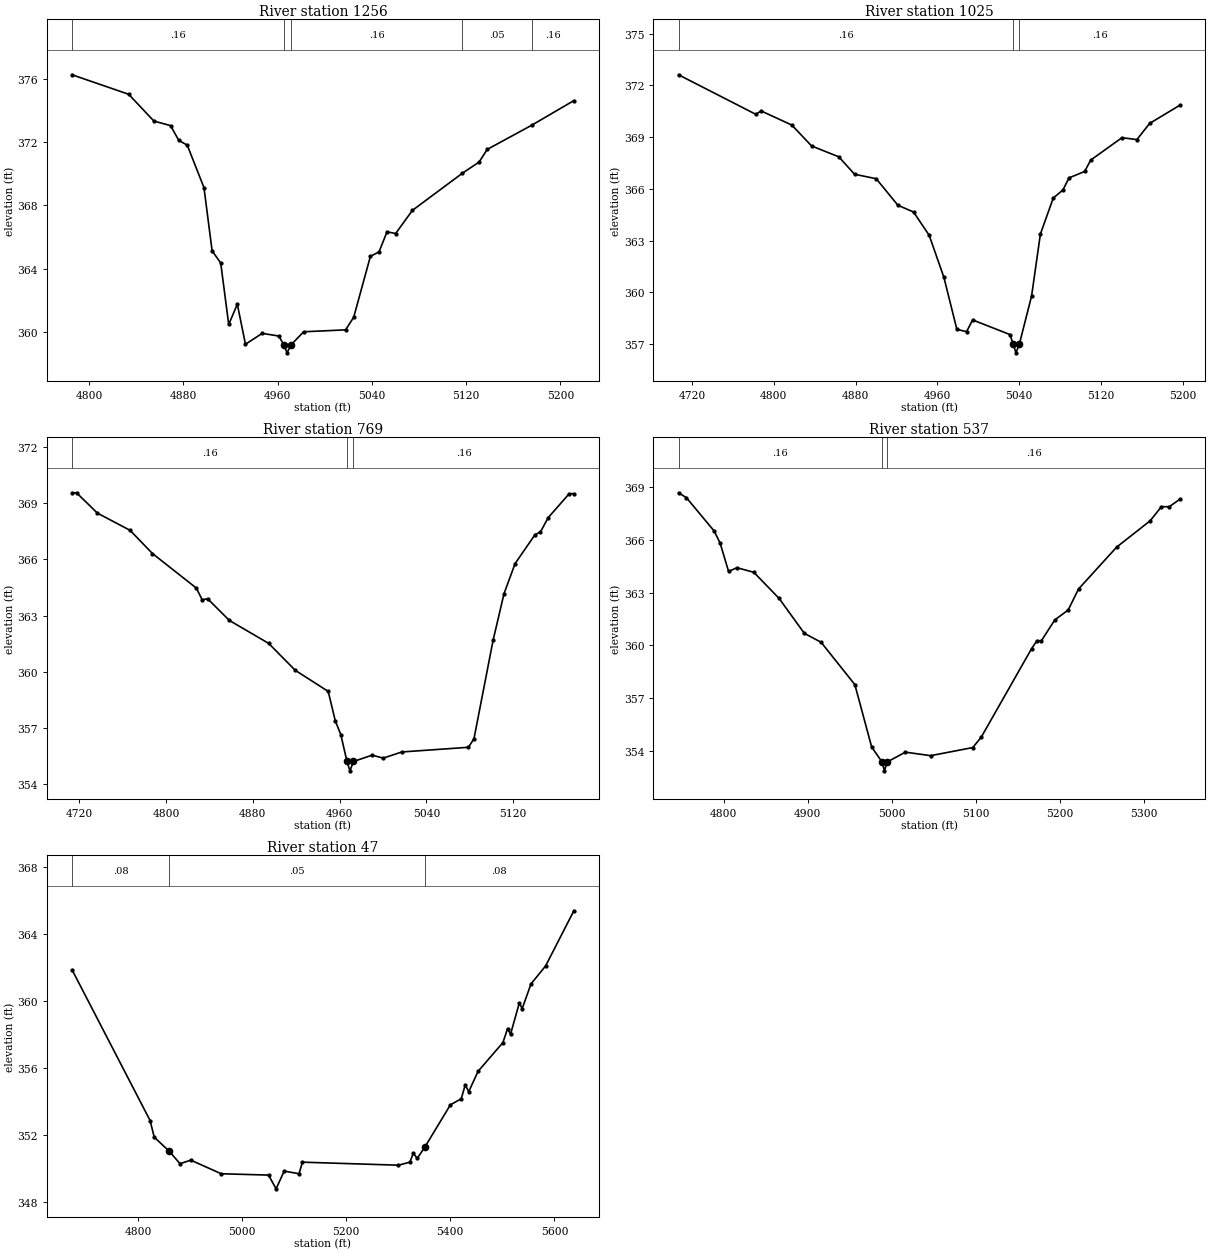
Type RM Length L Ch R = 1 ,1256    ,231,231,231
BEGIN DESCRIPTION:
UNT02312 IN SAND CR 3.1
END DESCRIPTION:
XS GIS Cut Line= 2
      3540787.64     10451014.11      3540494.51     10450705.41
#Sta/Elev= 30
  4785.7  376.24  4833.7  375.01  4855.1  373.32  4869.3  373.03  4876.2   372.1
  4883.4   371.8  4897.6  369.12  4904.5  365.13  4911.8  364.36  4918.6  360.48
  4925.9  361.76  4932.8  359.23    4947  359.92  4961.1  359.75  4965.4  359.19
  4968.1  358.69  4971.4  359.19  4982.2  360.02  5017.7  360.14  5024.6  360.93
  5038.8  364.78  5046.1  365.06  5052.9  366.33  5060.2  366.22  5074.4  367.68
  5116.9  370.03    5131  370.73  5137.9  371.53  5175.5  373.05  5211.4  374.61
#Mann= 5 ,-1 , 0
  4785.7     .16       0  4965.4     .07       0  4971.4     .16       0
  5116.9     .05       0  5175.5     .16       0
Bank Sta=4965.4,4971.4
XS Rating Curve= 0 ,0
Exp/Cntr=0.3,0.1

Type RM Length L Ch R = 1 ,1025    ,256,256,256
BEGIN DESCRIPTION:
UNT02312 IN SAND CR 2.0
END DESCRIPTION:
XS GIS Cut Line= 3
      3540955.62     10450983.33      3540907.01      10450856.6
      3540718.46     10450555.61
#Sta/Elev= 30
  4706.8  372.62  4782.3  370.33  4787.7  370.52  4817.7   369.7    4837  368.49
  4863.6  367.86    4879  366.85  4900.2  366.59  4921.4  365.05  4936.7  364.66
    4952  363.31  4966.4  360.87  4979.1  357.85  4988.6  357.72  4994.5   358.4
    5031  357.55  5034.2  356.99  5036.9  356.49  5040.2  356.99  5052.2  359.79
  5060.8  363.38  5073.4  365.47  5082.9  365.94  5088.8  366.64  5104.1  367.01
    5110  367.67  5140.6  368.97  5155.2  368.86  5167.7   369.8  5197.7  370.87
#Mann= 3 ,-1 , 0
  4706.8     .16       0  5034.2     .07       0  5040.2     .16       0
Bank Sta=5034.2,5040.2
XS Rating Curve= 0 ,0
Exp/Cntr=0.3,0.1

Type RM Length L Ch R = 1 ,769     ,232,232,232
BEGIN DESCRIPTION:
UNT02312 IN SAND CR 1.1
END DESCRIPTION:
XS GIS Cut Line= 2
      3541007.71     10450934.75      3541082.37     10450478.11
#Sta/Elev= 30
  4713.3  369.57  4717.4  369.57  4736.7  368.48  4766.8  367.56  4787.4  366.32
  4827.9  364.47  4833.3  363.84  4838.3   363.9  4858.3  362.74  4894.6  361.51
  4919.1  360.07  4949.5  358.94    4956  357.37  4961.1  356.63  4966.8  355.19
  4969.5  354.69  4972.8  355.19    4990  355.53  5000.2  355.37  5017.4   355.7
  5078.8  355.95  5083.9  356.41  5101.5  361.67  5111.6  364.17  5121.8  365.78
  5140.2  367.33  5145.2  367.47  5152.2  368.23  5171.7  369.52    5176  369.52
#Mann= 3 ,-1 , 0
  4713.3     .16       0  4966.8     .07       0  4972.8     .16       0
Bank Sta=4966.8,4972.8
XS Rating Curve= 0 ,0
Exp/Cntr=0.3,0.1

Type RM Length L Ch R = 1 ,537     ,490,490,490
BEGIN DESCRIPTION:
UNT02312 IN SAND CR 1.2
END DESCRIPTION:
XS GIS Cut Line= 3
      3541235.14     10451011.08      3541255.97     10450584.03
      3541183.07     10450431.29
#Sta/Elev= 30
  4746.5  368.66  4755.9  368.38  4788.9  366.49    4796   365.8    4806   364.2
    4816  364.41    4836  364.15  4866.1  362.67  4896.1  360.69  4916.1  360.18
  4956.2  357.78  4976.2  354.24  4988.6  353.39  4991.4  352.89  4994.6  353.39
  5016.3  353.95  5046.3  353.75  5096.4  354.21  5106.4  354.79  5166.4  359.82
  5172.7  360.27  5178.1  360.27    5194  361.45  5209.9  362.01  5222.2   363.2
  5267.6  365.58  5307.4  367.07  5320.8  367.87  5330.1  367.87  5343.3  368.31
#Mann= 3 ,-1 , 0
  4746.5     .16       0  4988.6     .07       0  4994.6     .16       0
Bank Sta=4988.6,4994.6
XS Rating Curve= 0 ,0
Exp/Cntr=0.3,0.1

Type RM Length L Ch R = 1 ,47      ,0,0,0
BEGIN DESCRIPTION:
UNT02312 IN SAND CR 1.0
END DESCRIPTION:
XS GIS Cut Line= 5
      3541535.46     10451026.78      3541705.63     10450820.15
      3541688.26     10450696.88      3541391.39     10450441.67
      3541229.91      10450361.8
#Sta/Elev= 30
  4673.6  361.84  4823.5  352.85  4831.4  351.86    4860  351.03  4880.9  350.28
  4901.7  350.49    4960  349.68  5050.9   349.6  5065.5  348.78    5081  349.84
  5109.5  349.68  5116.1  350.37  5300.4  350.19  5322.4  350.37    5329   350.9
  5336.6   350.6  5350.8  351.25  5400.3  353.79  5421.1  354.15  5428.8  354.98
  5435.4  354.57  5453.5  355.79  5501.1   357.5  5510.2  358.34  5515.8     358
  5532.6  359.86  5538.2  359.53  5555.1     361  5583.1  362.07  5637.4  365.36
#Mann= 3 , 0 , 0
  4673.6     .08       0    4860     .05       0  5350.8     .08       0
Bank Sta=4860,5350.8
XS Rating Curve= 0 ,0
Exp/Cntr=0.3,0.1

Chan Stop Cuts=-1
Use User Specified Reach Order=0
Composite Channel Slope=5