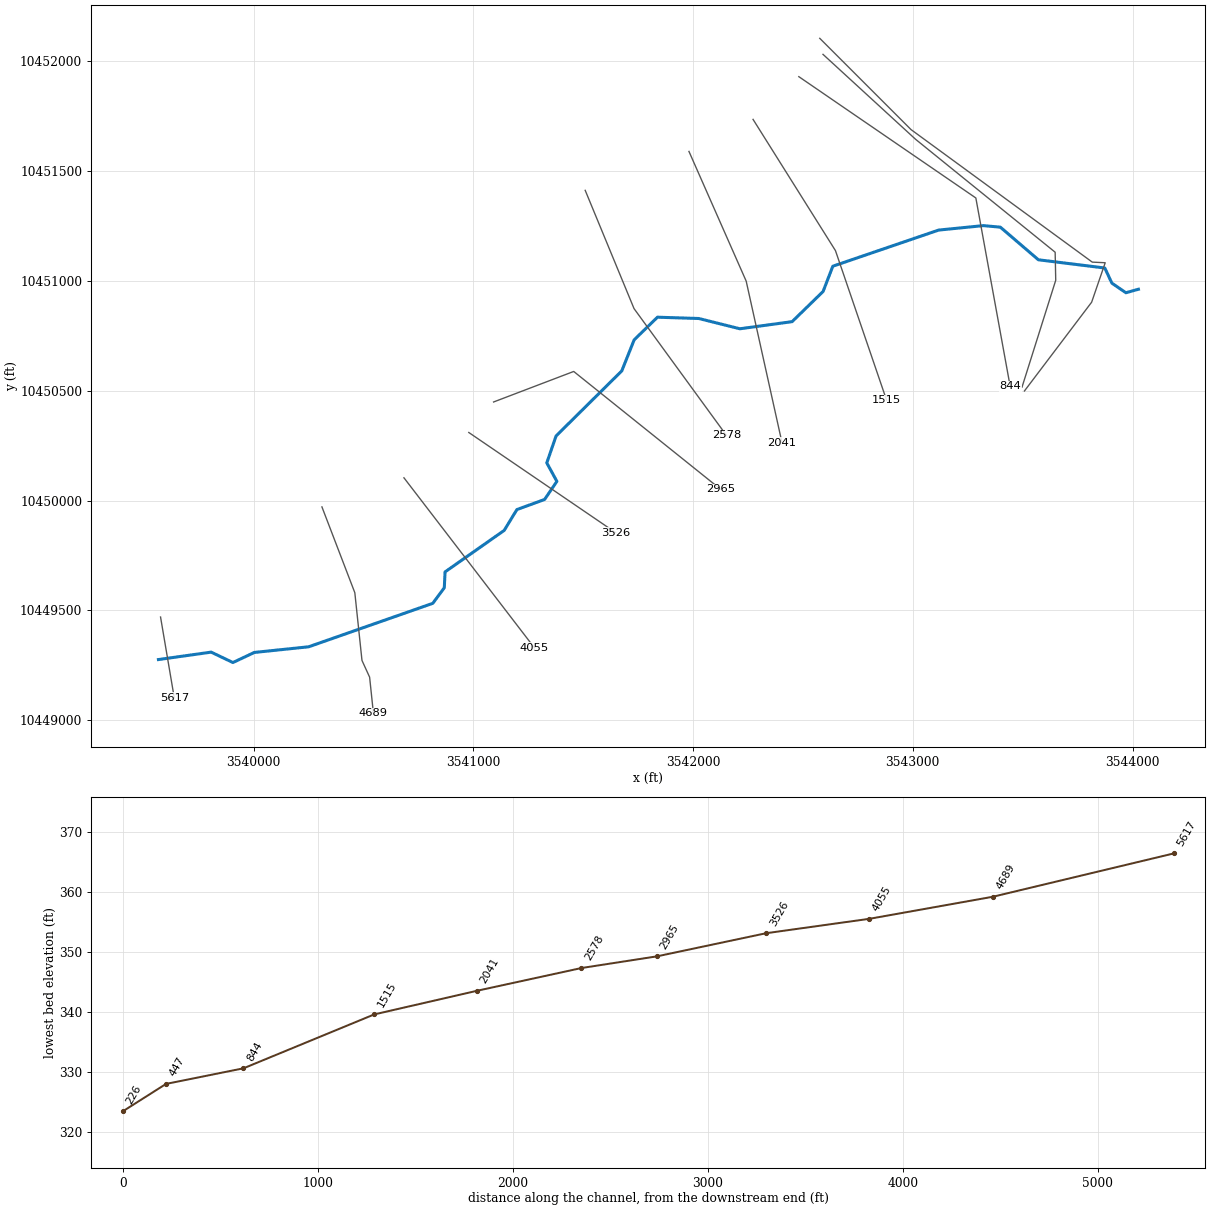
--- SANDYBRTRIB4.prj (project) ---

Proj Title=SANDY BRANCH TRIBUTARY 4
Current Plan=p01
Default Exp/Contr=0.3,0.1
English Units
Geom File=g01
Flow File=f01
Plan File=p01
Y Axis Title=Elevation
X Axis Title(PF)=Main Channel Distance
X Axis Title(XS)=Station
BEGIN DESCRIPTION:
UNT0785 IN SAND CR
END DESCRIPTION:
DSS Export Rating Curves= 0
DSS Export Rating Curve Sorted= 0
DSS Export Volume Flow Curves= 0
DXF OffsetX= 0
DXF OffsetY= 0
DXF ScaleX= 1
DXF ScaleY= 10

--- SANDYBRTRIB4.p01 (plan) ---

Plan Title=Multiple Run
Short Identifier=Multiple
Geom File=g01
Flow File=f01
Subcritical Flow
K Sum by GR= 0
Std Step Tol= 0.01
Critical Tol= 0.01
Num of Std Step Trials= 20
Max Error Tol= 0.3
Flow Tol Ratio= 0.001
Split Flow NTrial= 30
Split Flow Tol= 0.02
Split Flow Ratio= 0.02
Log Output Level= 0
Friction Slope Method= 1
Unsteady Friction Slope Method= 2
Unsteady Bridges Friction Slope Method= 1
Parabolic Critical Depth
Global Vel Dist=  1 , 1 , 1
Global Log Level= 0
CheckData=True
Encroach Param= -1, 0, 0, 0
BEGIN DESCRIPTION:
Multiple Run
END DESCRIPTION:

--- SANDYBRTRIB4.f01 (steady flow) ---

Flow Title=Multiple
Program Version=4.10
Number of Profiles= 7
Profile Names=10-year,25-year,50-year,1pct_min,100-year,1pct_plu,500-year
River Rch & RM=UNT0785 IN SAND,Reach-1         ,5617
     306     390     455     390     527     713     701
River Rch & RM=UNT0785 IN SAND,Reach-1         ,2578
     597     798     960     844    1142    1544    1610
River Rch & RM=UNT0785 IN SAND,Reach-1         ,226
    1793    2532    3157    2865    3875    5240    5825
River Rch & RM=SANDYBRTRIB4,Reach-1         ,5617
     306     390     455     390     527     713     701
River Rch & RM=SANDYBRTRIB4,Reach-1         ,2578
     597     798     960     844    1142    1544    1610
River Rch & RM=SANDYBRTRIB4,Reach-1         ,226
    1793    2532    3157    2865    3875    5240    5825
Boundary for River Rch & Prof#=SANDYBRTRIB4,Reach-1         , 1
Up Type= 0
Dn Type= 3
Dn Slope=0.005
Boundary for River Rch & Prof#=SANDYBRTRIB4,Reach-1         , 2
Up Type= 0
Dn Type= 3
Dn Slope=0.005
Boundary for River Rch & Prof#=SANDYBRTRIB4,Reach-1         , 3
Up Type= 0
Dn Type= 3
Dn Slope=0.005
Boundary for River Rch & Prof#=SANDYBRTRIB4,Reach-1         , 4
Up Type= 0
Dn Type= 3
Dn Slope=0.005
Boundary for River Rch & Prof#=SANDYBRTRIB4,Reach-1         , 5
Up Type= 0
Dn Type= 3
Dn Slope=0.005
Boundary for River Rch & Prof#=SANDYBRTRIB4,Reach-1         , 6
Up Type= 0
Dn Type= 3
Dn Slope=0.005
Boundary for River Rch & Prof#=SANDYBRTRIB4,Reach-1         , 7
Up Type= 0
Dn Type= 3
Dn Slope=0.005
DSS Import GetInterval= 0
DSS Import GetPeak= 0
DSS Import FillOption= 0

--- SANDYBRTRIB4.g01 (geometry) ---

Geom Title=Existing Conditions
Program Version=4.10

River Reach=SANDYBRTRIB4    ,Reach-1
Reach XY= 30
      3539567.11     10449276.64      3539807.17     10449310.43
      3539906.16     10449263.06      3540003.31     10449308.97
      3540250.83     10449334.73      3540815.65      10449532.5
      3540868.12     10449603.41      3540871.53     10449675.55
       3541140.6      10449864.3      3541198.53     10449959.24
      3541324.52     10450005.15      3541380.46     10450087.56
      3541334.47     10450171.62      3541376.75     10450294.15
      3541675.87     10450590.39      3541732.11     10450731.64
      3541838.21     10450834.66      3542026.49     10450828.71
      3542213.26     10450781.98      3542451.01     10450814.45
        3542592.     10450951.81      3542636.21     10451066.67
      3543117.79     10451231.13      3543321.29     10451251.41
       3543398.5      10451244.4      3543571.59     10451096.01
      3543874.02     10451058.51      3543906.07      10450989.7
      3543969.96     10450945.95       3544026.9     10450961.93

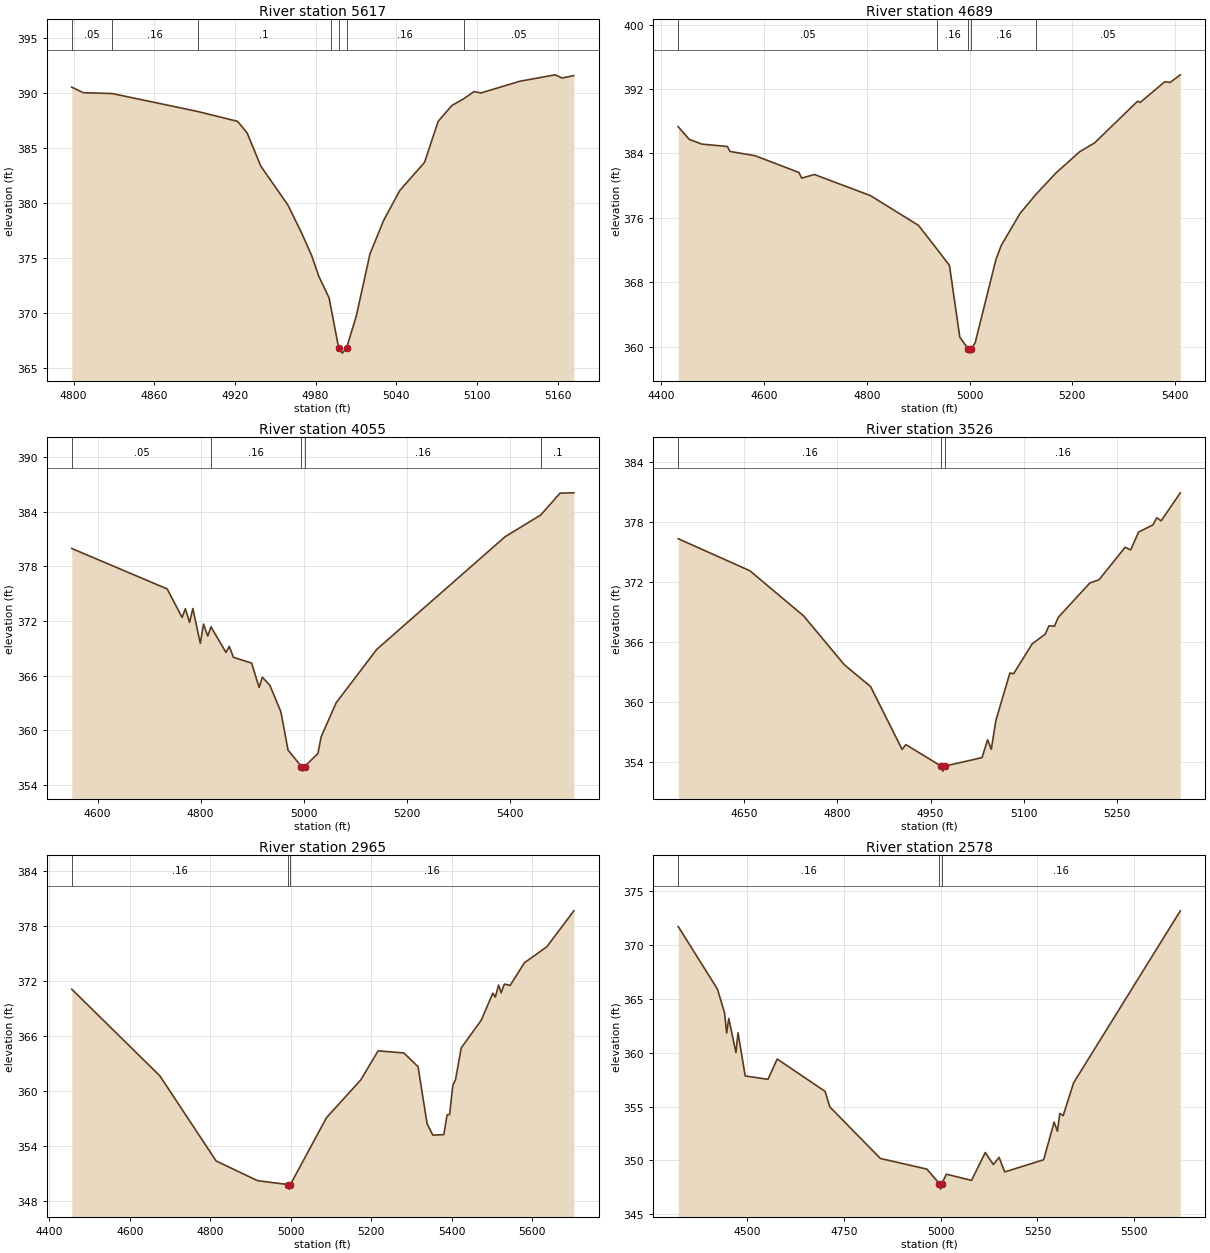
Type RM Length L Ch R = 1 ,5617    ,928,928,928
BEGIN DESCRIPTION:
UNT02311 IN SAND CR 6.0
END DESCRIPTION:
XS GIS Cut Line= 2
       3539576.8     10449470.22       3539639.3     10449102.19
#Sta/Elev= 30
  4798.7  390.57  4807.4  390.06  4828.7  389.99  4892.2  388.36    4922  387.46
  4929.1   386.4  4939.3  383.38  4959.5  379.83  4969.7  377.28  4977.2  375.21
  4982.3  373.39    4990  371.41  4991.1  370.71  4997.1  366.88  4999.9  366.38
  5003.1  366.88  5010.3  369.78  5020.4   375.4  5030.5  378.43  5042.6  381.17
    5061  383.73  5071.1  387.45  5081.3   388.9    5090   389.5  5097.8  390.17
  5102.9  390.04    5132  391.11  5158.1  391.69  5163.2   391.4    5172  391.62
#Mann= 7 ,-1 , 0
  4798.7     .05       0  4828.7     .16       0  4892.2      .1       0
  4991.1     .16       0  4997.1     .07       0  5003.1     .16       0
    5090     .05       0
Bank Sta=4997.1,5003.1
XS Rating Curve= 0 ,0
Exp/Cntr=0.3,0.1

Type RM Length L Ch R = 1 ,4689    ,634,634,634
BEGIN DESCRIPTION:
UNT02311 IN SAND CR 4.0
END DESCRIPTION:
XS GIS Cut Line= 5
      3540311.19     10449971.43      3540460.94      10449580.8
      3540493.49     10449272.64      3540528.21     10449196.68
      3540545.57     10449031.74
#Sta/Elev= 30
  4432.7   387.3  4454.2  385.73  4478.9  385.14  4528.3  384.85  4533.6  384.23
  4582.4   383.7  4667.7  381.62  4673.1  380.92  4697.8  381.37  4807.2  378.74
  4900.5  375.05  4937.5  372.02  4960.8  370.08  4980.9  361.17  4997.5  359.68
  5000.2  359.18  5003.5  359.68  5011.1  360.52  5051.3  370.81  5061.4  372.53
  5098.4  376.55  5129.8  378.94  5168.6  381.59  5214.6  384.21  5243.1  385.28
  5327.2  390.48  5332.2  390.32  5380.2   392.9  5390.3   392.8  5410.3  393.75
#Mann= 5 ,-1 , 0
  4432.7     .05       0  4937.5     .16       0  4997.5     .07       0
  5003.5     .16       0  5129.8     .05       0
Bank Sta=4997.5,5003.5
XS Rating Curve= 0 ,0
Exp/Cntr=0.3,0.1

Type RM Length L Ch R = 1 ,4055    ,529,529,529
BEGIN DESCRIPTION:
UNT02311 IN SAND CR 3.0
END DESCRIPTION:
XS GIS Cut Line= 2
      3540684.46      10450103.8      3541278.09     10449330.35
#Sta/Elev= 30
  4549.7  379.95    4735  375.51    4764  372.38  4770.3  373.34  4778.5  371.83
  4784.8  373.36  4799.3  369.54  4805.6  371.65  4813.8  370.34    4820  371.35
  4849.2  368.54  4855.5  369.21  4863.7     368    4899  367.37  4913.5   364.7
  4919.8  365.82  4934.4  364.93  4955.8  362.02  4969.7  357.82  4995.7  356.01
  4998.5  355.51  5001.7  356.01  5027.7  357.44    5034  359.28  5063.1  363.01
    5142  368.88  5391.2  381.24  5460.7  383.64  5497.9  386.03  5524.7  386.06
#Mann= 5 ,-1 , 0
  4549.7     .05       0    4820     .16       0  4995.7     .07       0
  5001.7     .16       0  5460.7      .1       0
Bank Sta=4995.7,5001.7
XS Rating Curve= 0 ,0
Exp/Cntr=0.3,0.1

Type RM Length L Ch R = 1 ,3526    ,561,561,561
BEGIN DESCRIPTION:
UNT02311 IN SAND CR 2.0
END DESCRIPTION:
XS GIS Cut Line= 2
      3540979.61     10450309.96      3541647.53     10449854.56
#Sta/Elev= 30
  4543.8  376.31    4659  373.12  4745.7  368.61  4811.5  363.72  4853.5  361.56
  4904.3  355.28  4910.3  355.77  4967.1  353.62  4969.8  353.12  4973.1  353.62
    5033  354.47  5041.9  356.25  5047.9   355.3  5055.2  358.17  5077.8  362.91
  5083.8  362.84  5113.7  365.82  5134.7  366.79  5140.7  367.62  5149.6  367.58
  5155.6  368.46  5206.5  371.89  5221.4  372.22  5263.4  375.46  5272.2  375.19
  5285.1  376.98  5308.1  377.69  5314.2   378.4  5321.4   378.1  5352.2  380.89
#Mann= 3 ,-1 , 0
  4543.8     .16       0  4967.1     .07       0  4973.1     .16       0
Bank Sta=4967.1,4973.1
XS Rating Curve= 0 ,0
Exp/Cntr=0.3,0.1

Type RM Length L Ch R = 1 ,2965    ,387,387,387
BEGIN DESCRIPTION:
UNT02311 IN SAND CR 1.0
END DESCRIPTION:
XS GIS Cut Line= 3
      3541092.44     10450448.85      3541457.03     10450587.74
      3542125.41     10450051.74
#Sta/Elev= 30
    4456   371.1  4674.8  361.64  4814.5  352.35  4917.5  350.19  4992.9  349.77
  4995.7  349.27  4998.9  349.77  5088.7  357.08  5173.6  361.19  5216.8  364.37
  5280.8  364.14    5316  362.64  5338.4  356.42  5352.6  355.17    5380  355.22
    5388  357.37  5394.4  357.42  5402.4  360.63  5408.8  361.17  5423.2  364.69
  5472.8  367.71  5501.6  370.66    5508  370.25    5516  371.56  5522.4   370.7
  5530.4  371.66  5544.8  371.52    5580  373.98  5636.1  375.75  5702.9  379.66
#Mann= 3 ,-1 , 0
    4456     .16       0  4992.9     .07       0  4998.9     .16       0
Bank Sta=4992.9,4998.9
XS Rating Curve= 0 ,0
Exp/Cntr=0.3,0.1

Type RM Length L Ch R = 1 ,2578    ,537,537,537
BEGIN DESCRIPTION:
UNT0785 IN SAND CR 4.0
END DESCRIPTION:
XS GIS Cut Line= 3
      3541509.32     10451411.95      3541731.54     10450873.77
      3542151.67     10450297.39
#Sta/Elev= 30
    4323  371.73  4424.1  365.92  4442.3  363.75    4448  361.83  4453.4  363.19
  4471.9  360.02  4477.3  361.86  4495.8  357.85  4554.5  357.53  4578.4  359.42
    4702  356.41  4714.2  354.97  4844.6  350.18  4964.6  349.19  4997.1  347.83
  4999.9  347.33  5003.1  347.83  5014.8  348.72  5079.7  348.14  5115.2  350.73
  5136.1  349.61  5150.8  350.28  5165.5  348.93  5265.9  350.06  5292.9  353.56
  5301.4  352.71  5307.6  354.37  5316.1  354.15  5343.2  357.21  5618.5  373.19
#Mann= 3 ,-1 , 0
    4323     .16       0  4997.1     .07       0  5003.1     .16       0
Bank Sta=4997.1,5003.1
XS Rating Curve= 0 ,0
Exp/Cntr=0.3,0.1

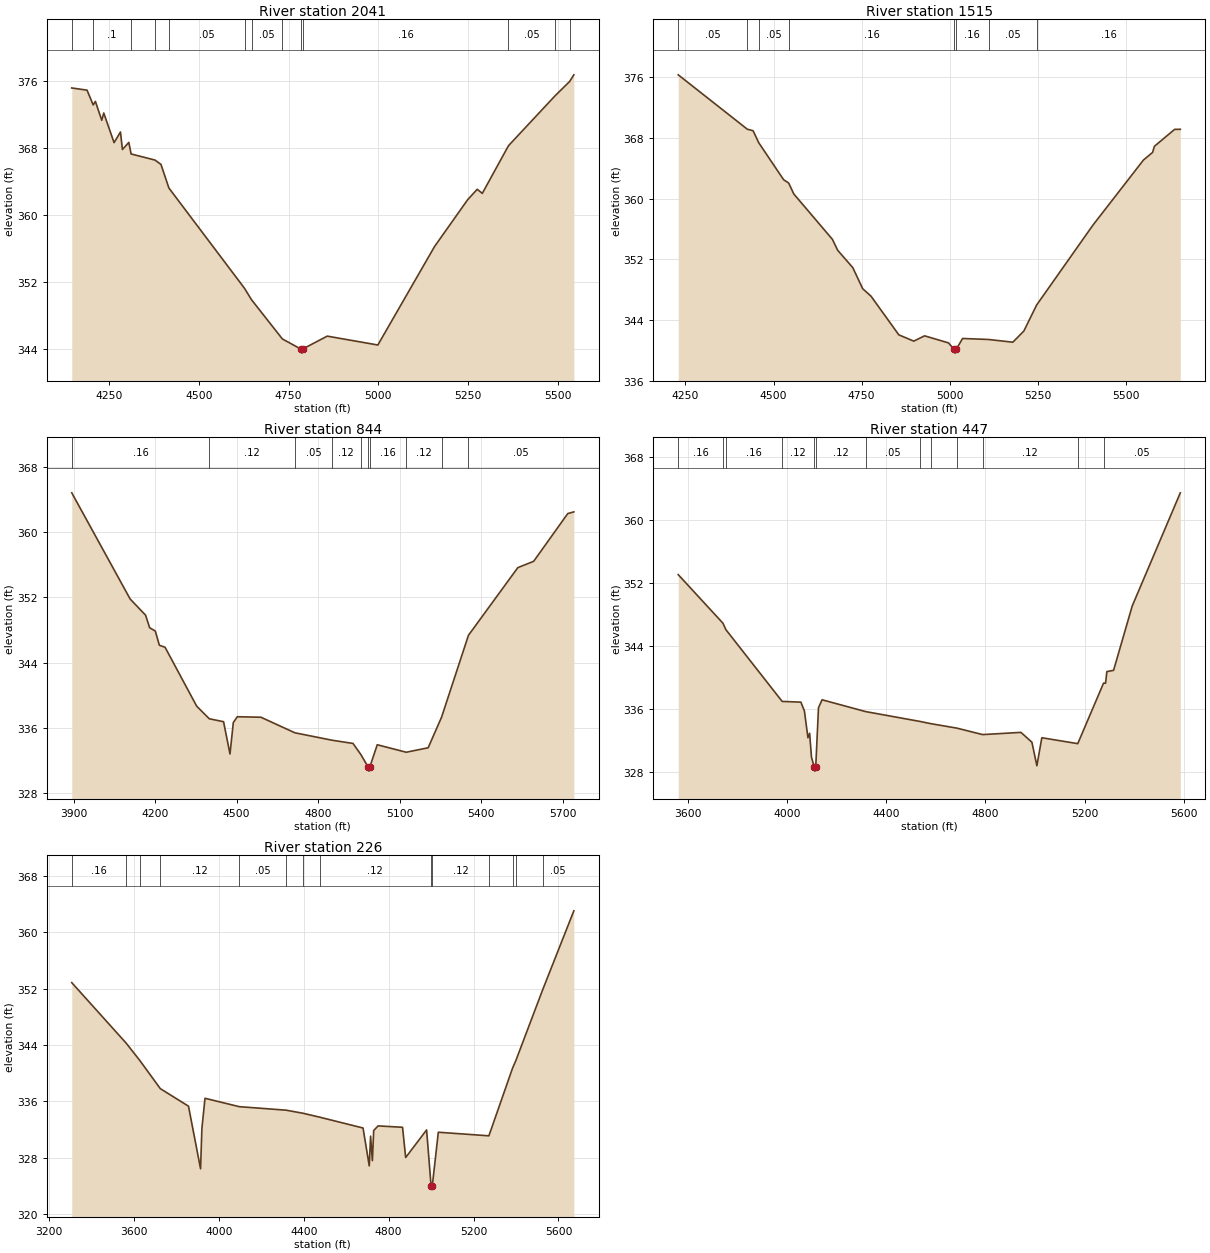
Type RM Length L Ch R = 1 ,2041    ,526,526,526
BEGIN DESCRIPTION:
UNT0785 IN SAND CR 3.0
END DESCRIPTION:
XS GIS Cut Line= 3
      3541981.54     10451589.05      3542241.96     10450998.77
      3542405.16     10450262.61
#Sta/Elev= 30
  4145.8  375.21  4188.3  374.95  4205.6  373.18  4211.6  373.61  4229.4  371.35
  4234.9  372.22  4263.7  368.68  4281.5  369.95    4287  367.86  4304.8  368.71
  4311.1  367.33  4377.7   366.6  4394.4  366.08  4416.5  363.26  4627.4  351.27
  4646.7  349.92  4732.8  345.23  4783.7  344.04  4786.4  343.54  4789.7  344.04
  4857.8  345.57  4998.8  344.51  5156.8  356.27    5249  361.86  5275.7  363.11
  5289.9  362.62  5362.8  368.31    5493  374.29  5533.2  375.98    5545  376.78
#Mann= 13 ,-1 , 0
  4145.8     .05       0  4205.6      .1       0  4311.1     .05       0
  4377.7      .1       0  4416.5     .05       0  4627.4     .16       0
  4646.7     .05       0  4732.8     .16       0  4783.7     .07       0
  4789.7     .16       0  5362.8     .05       0    5493     .16       0
  5533.2     .05       0
Bank Sta=4783.7,4789.7
XS Rating Curve= 0 ,0
Exp/Cntr=0.3,0.1

Type RM Length L Ch R = 1 ,1515    ,671,671,671
BEGIN DESCRIPTION:
UNT0785 IN SAND CR 2.0
END DESCRIPTION:
XS GIS Cut Line= 3
      3542273.19      10451734.9      3542648.21     10451137.65
      3542880.83     10450457.14
#Sta/Elev= 30
  4229.6  376.31  4425.6  369.14    4442  368.94  4458.1  367.35  4528.6  362.48
    4543  362.04  4557.4  360.61    4667  354.62  4682.1  353.17  4724.7   350.9
    4753  348.11  4776.5  347.13  4855.4  342.03  4897.9   341.2  4928.5   341.9
  4996.3  340.97  5012.2  340.12  5014.9  339.62  5018.2  340.12  5036.3  341.55
  5109.9  341.42  5178.9  341.06  5210.2  342.54  5246.2  345.95  5406.2   356.5
  5549.3  365.07  5575.3  366.08  5580.6  366.89  5637.9  369.12    5654  369.13
#Mann= 8 ,-1 , 0
  4229.6     .05       0  4425.6     .16       0  4458.1     .05       0
    4543     .16       0  5012.2     .07       0  5018.2     .16       0
  5109.9     .05       0  5246.2     .16       0
Bank Sta=5012.2,5018.2
XS Rating Curve= 0 ,0
Exp/Cntr=0.3,0.1

Type RM Length L Ch R = 1 ,844     ,397,397,397
BEGIN DESCRIPTION:
UNT0785 IN SAND CR 1.0
END DESCRIPTION:
XS GIS Cut Line= 3
      3542481.54     10451929.32      3543287.09     10451377.24
      3543443.34     10450519.64
#Sta/Elev= 30
  3893.3  364.84  4108.2   351.8  4165.1  349.81    4180  348.27  4200.9  347.86
  4215.8  346.12  4236.8  345.87  4353.3  338.63  4399.7  337.09  4452.1  336.73
  4475.8  332.77    4488  336.63  4502.8  337.34  4589.5  337.28  4714.5  335.37
  4850.9  334.46  4928.6  334.06  4957.5   332.7  4984.4  331.16  4987.1  330.66
  4990.4  331.16  5017.9   333.9  5124.6  332.98  5205.3  333.53  5254.6  337.28
  5353.6  347.34  5535.3  355.65  5593.7  356.43  5719.2  362.29  5741.6   362.5
#Mann= 10 ,-1 , 0
  3893.3     .16       0  4399.7     .12       0  4714.5     .05       0
  4850.9     .12       0  4957.5     .16       0  4984.4     .07       0
  4990.4     .16       0  5124.6     .12       0  5254.6     .16       0
  5353.6     .05       0
Bank Sta=4984.4,4990.4
XS Rating Curve= 0 ,0
Exp/Cntr=0.3,0.1

Type RM Length L Ch R = 1 ,447     ,221,221,221
BEGIN DESCRIPTION:
UNT0785 IN SAND CR 1.01
END DESCRIPTION:
XS GIS Cut Line= 5
      3542591.59     10452030.77      3543012.61     10451644.48
      3543648.02     10451130.37      3543650.63     10451002.77
      3543497.16     10450516.37
#Sta/Elev= 30
  3560.3  353.02  3740.9  346.85  3752.5  346.04  3979.8  336.92  4055.4  336.83
  4069.6   335.7  4083.8  332.31  4090.6  332.88    4098  329.86  4109.2  328.57
  4111.9  328.07  4115.2  328.57  4126.4  336.12  4140.8  337.13  4316.7  335.63
    4536  334.38  4579.4   334.1  4684.8  333.53  4788.8  332.71  4943.5  332.99
  4987.8  331.74  5007.8  328.75  5027.8  332.31  5172.8  331.56    5277  339.25
    5285  339.23  5290.3  340.71  5317.4  340.87  5392.6  349.04  5586.7  363.41
#Mann= 13 ,-1 , 0
  3560.3     .16       0  3740.9     .12       0  3752.5     .16       0
  3979.8     .12       0  4109.2     .07       0  4115.2     .12       0
  4316.7     .05       0    4536     .12       0  4579.4     .05       0
  4684.8     .16       0  4788.8     .12       0  5172.8      .1       0
    5277     .05       0
Bank Sta=4109.2,4115.2
XS Rating Curve= 0 ,0
Exp/Cntr=0.3,0.1

Type RM Length L Ch R = 1 ,226     ,0,0,0
BEGIN DESCRIPTION:
UNT0785 IN SAND CR 1.011
END DESCRIPTION:
XS GIS Cut Line= 6
      3542576.82     10452103.73      3542992.06     10451688.49
      3543816.88     10451085.31      3543875.79      10451082.5
      3543814.07     10450902.95      3543508.27     10450498.96
#Sta/Elev= 30
  3307.7  352.85  3563.4  344.28  3628.9  341.77  3724.7   337.8  3857.4  335.31
  3914.3  326.42  3920.5  332.14  3935.2  336.43  4096.6  335.24  4317.5  334.74
  4395.7  334.31  4474.9  333.75  4679.5  332.21  4708.8  326.83    4715  331.05
  4723.5  327.58  4729.7  331.86  4750.6  332.51  4865.6  332.31  4880.3  328.02
  4978.9  331.94  4999.8  324.03  5002.5  323.53  5005.8  324.03    5034  331.61
  5272.2   331.1    5384  340.74    5399  341.77  5525.9  351.87  5672.3  363.05
#Mann= 14 ,-1 , 0
  3307.7     .16       0  3563.4     .12       0  3628.9     .16       0
  3724.7     .12       0  4096.6     .05       0  4317.5     .12       0
  4395.7     .05       0  4474.9     .12       0  4999.8     .07       0
  5005.8     .12       0  5272.2      .1       0    5384     .05       0
    5399      .1       0  5525.9     .05       0
Bank Sta=4999.8,5005.8
XS Rating Curve= 0 ,0
Exp/Cntr=0.3,0.1

Chan Stop Cuts=-1
Use User Specified Reach Order=0
Composite Channel Slope=5