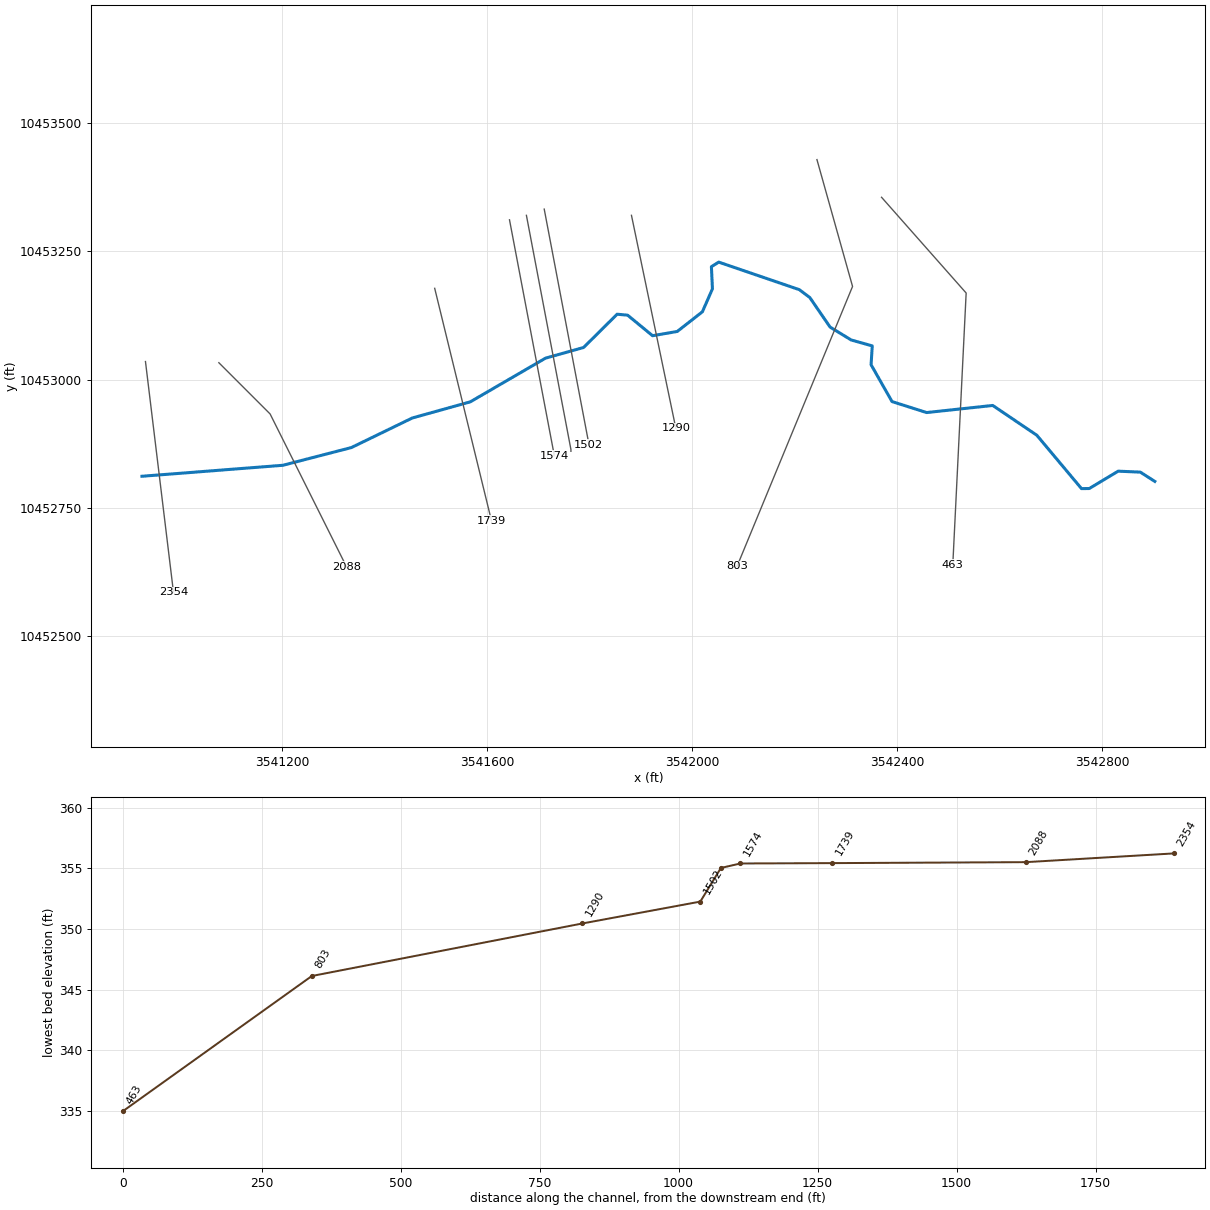
--- SANDYBRTRIB51.prj (project) ---

Proj Title=SANDY BRANCH TRIBUTARY 5 1
Current Plan=p01
Default Exp/Contr=0.3,0.1
English Units
Geom File=g01
Flow File=f01
Plan File=p01
Y Axis Title=Elevation
X Axis Title(PF)=Main Channel Distance
X Axis Title(XS)=Station
BEGIN DESCRIPTION:
UNT02310 IN SAND CR
END DESCRIPTION:
DSS Export Rating Curves= 0
DSS Export Rating Curve Sorted= 0
DSS Export Volume Flow Curves= 0
DXF OffsetX= 0
DXF OffsetY= 0
DXF ScaleX= 1
DXF ScaleY= 10

--- SANDYBRTRIB51.p01 (plan) ---

Plan Title=Multiple Run
Short Identifier=Multiple
Geom File=g01
Flow File=f01
Subcritical Flow
K Sum by GR= 0
Std Step Tol= 0.01
Critical Tol= 0.01
Num of Std Step Trials= 20
Max Error Tol= 0.3
Flow Tol Ratio= 0.001
Split Flow NTrial= 30
Split Flow Tol= 0.02
Split Flow Ratio= 0.02
Log Output Level= 0
Friction Slope Method= 1
Unsteady Friction Slope Method= 2
Unsteady Bridges Friction Slope Method= 1
Parabolic Critical Depth
Global Vel Dist=  1 , 1 , 1
Global Log Level= 0
CheckData=True
Encroach Param= -1, 0, 0, 0
BEGIN DESCRIPTION:
Multiple Run
END DESCRIPTION:

--- SANDYBRTRIB51.f01 (steady flow) ---

Flow Title=Multiple
Program Version=4.10
Number of Profiles= 7
Profile Names=10-year,25-year,50-year,1pct_min,100-year,1pct_plu,500-year
River Rch & RM=UNT02310 IN SAND,Reach-1         ,2354
     293     374     436     374     506     684     675
River Rch & RM=SANDYBRTRIB51,Reach-1         ,2354
     293     374     436     374     506     684     675
Boundary for River Rch & Prof#=SANDYBRTRIB51,Reach-1         , 1
Up Type= 0
Dn Type= 3
Dn Slope=0.005
Boundary for River Rch & Prof#=SANDYBRTRIB51,Reach-1         , 2
Up Type= 0
Dn Type= 3
Dn Slope=0.005
Boundary for River Rch & Prof#=SANDYBRTRIB51,Reach-1         , 3
Up Type= 0
Dn Type= 3
Dn Slope=0.005
Boundary for River Rch & Prof#=SANDYBRTRIB51,Reach-1         , 4
Up Type= 0
Dn Type= 3
Dn Slope=0.005
Boundary for River Rch & Prof#=SANDYBRTRIB51,Reach-1         , 5
Up Type= 0
Dn Type= 3
Dn Slope=0.005
Boundary for River Rch & Prof#=SANDYBRTRIB51,Reach-1         , 6
Up Type= 0
Dn Type= 3
Dn Slope=0.005
Boundary for River Rch & Prof#=SANDYBRTRIB51,Reach-1         , 7
Up Type= 0
Dn Type= 3
Dn Slope=0.005
DSS Import GetInterval= 0
DSS Import GetPeak= 0
DSS Import FillOption= 0

--- SANDYBRTRIB51.g01 (geometry) ---

Geom Title=Existing Conditions
Program Version=4.10

River Reach=SANDYBRTRIB51   ,Reach-1
Reach XY= 30
      3540927.11     10452811.64       3541202.1     10452833.07
      3541335.59     10452867.63      3541454.34     10452925.27
      3541567.33     10452956.72      3541714.06     10453041.94
      3541788.37     10453062.77       3541853.7     10453127.63
      3541874.13      10453125.8      3541922.87     10453085.68
      3541970.97     10453094.02      3542019.96     10453132.35
      3542039.59     10453177.15      3542037.53     10453220.35
      3542051.81     10453229.23      3542209.07     10453175.49
      3542229.46     10453160.13      3542268.95     10453102.56
      3542310.14      10453077.4      3542351.25     10453065.85
      3542348.89     10453029.17      3542389.73      10452957.3
      3542457.22     10452935.88      3542586.16     10452949.72
      3542672.11     10452891.64      3542759.23     10452787.56
      3542774.41     10452787.75      3542830.75     10452821.57
      3542873.92     10452819.73      3542902.11     10452801.64

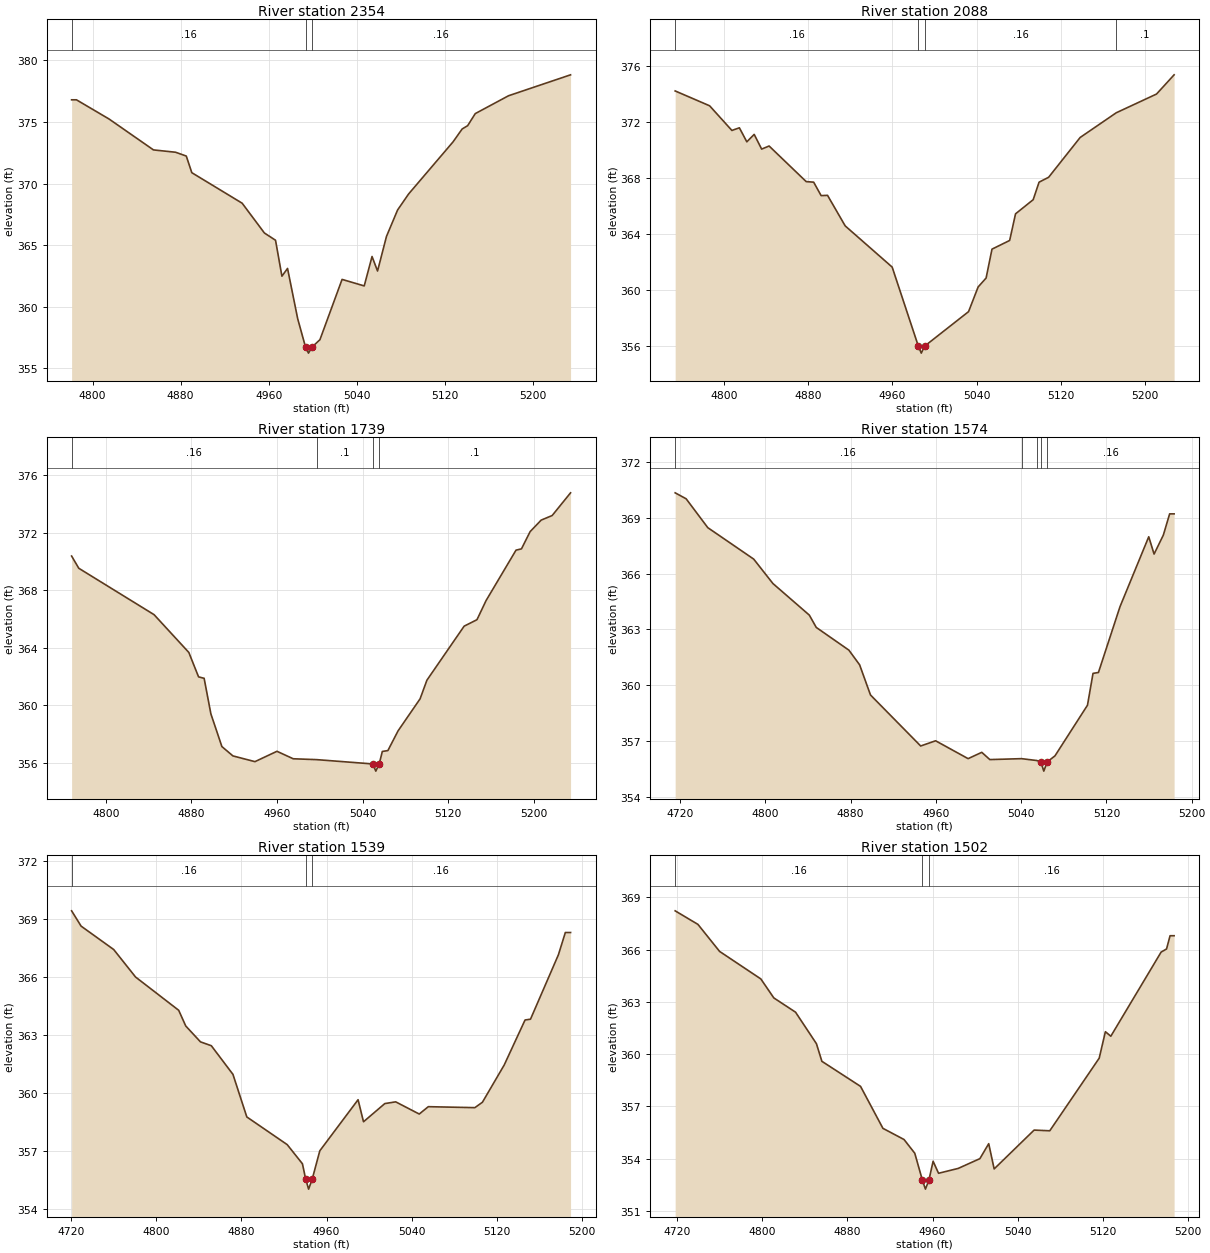
Type RM Length L Ch R = 1 ,2354    ,266,266,266
BEGIN DESCRIPTION:
UNT02310 IN SAND CR 3.1
END DESCRIPTION:
XS GIS Cut Line= 2
        3540934.     10453035.35      3540988.58     10452585.75
#Sta/Elev= 30
    4781   376.8  4785.4   376.8    4815  375.24  4855.3  372.73  4875.4  372.54
  4885.1  372.23  4890.1  370.88  4935.8   368.4    4956  365.98  4966.1  365.39
  4971.9  362.47    4977   363.1  4986.2  359.02  4993.3  356.72    4996  356.22
  4999.3  356.72  5006.4  357.31  5026.5  362.21  5046.6  361.68  5053.7  364.07
  5058.7  362.89  5066.8   365.7  5076.9  367.85  5086.9  369.15  5127.2  373.38
  5135.5  374.43  5140.5   374.7  5147.4  375.68  5177.6  377.13  5233.9  378.83
#Mann= 3 ,-1 , 0
    4781     .16       0  4993.3     .07       0  4999.3     .16       0
Bank Sta=4993.3,4999.3
XS Rating Curve= 0 ,0
Exp/Cntr=0.3,0.1

Type RM Length L Ch R = 1 ,2088    ,349,349,349
BEGIN DESCRIPTION:
UNT02310 IN SAND CR 3.0
END DESCRIPTION:
XS GIS Cut Line= 3
      3541077.11     10453033.06       3541177.1     10452933.07
       3541326.2     10452634.87
#Sta/Elev= 30
  4753.2  374.21    4786  373.15  4807.2  371.39  4814.3  371.58  4821.4  370.58
  4828.4  371.11  4835.5  370.06  4842.6  370.28  4877.9  367.74    4885   367.7
  4892.1  366.74  4898.2  366.76    4915  364.58  4959.7  361.64  4984.6     356
  4987.4   355.5  4990.6     356  5032.4  358.46  5041.5  360.22  5049.1  360.86
  5054.7  362.92  5071.5  363.54  5077.1  365.44  5093.9  366.45  5099.5   367.7
  5108.6  368.05  5138.6  370.89  5172.9  372.65  5211.3  373.99    5228  375.36
#Mann= 4 ,-1 , 0
  4753.2     .16       0  4984.6     .07       0  4990.6     .16       0
  5172.9      .1       0
Bank Sta=4984.6,4990.6
XS Rating Curve= 0 ,0
Exp/Cntr=0.3,0.1

Type RM Length L Ch R = 1 ,1739    ,165,165,165
BEGIN DESCRIPTION:
UNT02310 IN SAND CR 2.1
END DESCRIPTION:
XS GIS Cut Line= 2
      3541497.99     10453178.12      3541608.69     10452724.94
#Sta/Elev= 30
    4768  370.39  4774.7  369.54  4845.1  366.31  4877.6  363.68  4886.7  361.98
  4891.9  361.88  4898.2  359.41  4908.5  357.13  4918.8  356.48  4939.4  356.08
    4960   356.8  4975.2  356.28    4997  356.22  5049.6  355.92  5052.4  355.42
  5055.6  355.92  5058.5  356.79  5063.7  356.85  5073.2  358.22  5093.8  360.45
  5100.2  361.75    5135  365.51    5147  365.96  5155.5  367.29  5183.5   370.8
  5188.6  370.89  5196.7  372.09    5207  372.89  5217.3  373.21  5234.5  374.79
#Mann= 4 ,-1 , 0
    4768     .16       0    4997      .1       0  5049.6     .07       0
  5055.6      .1       0
Bank Sta=5049.6,5055.6
XS Rating Curve= 0 ,0
Exp/Cntr=0.3,0.1

Type RM Length L Ch R = 1 ,1574    ,35,35,35
BEGIN DESCRIPTION:
UNT02310 IN SAND CR 2.4
END DESCRIPTION:
XS GIS Cut Line= 3
      3541643.84     10453311.73      3541730.64     10452855.17
      3541730.64     10452851.71
#Sta/Elev= 30
  4715.3  370.34  4725.6  370.02  4745.9  368.47    4789  366.78    4807  365.47
  4841.2  363.77  4847.7  363.11  4878.3  361.89  4888.4   361.1  4898.6  359.48
  4945.7  356.74  4959.7  357.02  4990.2  356.06    5003   356.4  5010.6  356.01
  5040.3  356.06  5054.6  355.96  5058.5  355.89  5061.2  355.39  5064.5  355.89
  5071.7  356.21  5102.2  358.93  5107.4  360.64  5112.5  360.69  5132.7  364.22
  5159.7  367.98  5164.7  367.05  5173.4  368.07  5179.3  369.21  5183.5  369.21
#Mann= 5 ,-1 , 0
  4715.3     .16       0  5040.3      .1       0  5054.6     .16       0
  5058.5     .07       0  5064.5     .16       0
Bank Sta=5058.5,5064.5
XS Rating Curve= 0 ,0
Exp/Cntr=0.3,0.1

Type RM Length L Ch R = 1 ,1539    ,37,37,37
BEGIN DESCRIPTION:
UNT02310 IN SAND CR 2.2
END DESCRIPTION:
XS GIS Cut Line= 3
      3541676.83     10453320.41      3541763.62     10452863.85
      3541763.62     10452860.38
#Sta/Elev= 30
  4720.8   369.4  4729.7  368.61  4760.3   367.4  4780.8  365.98  4821.3  364.26
  4827.9  363.45  4841.7  362.63  4851.9  362.43  4872.2  360.95  4885.2  358.75
  4923.1  357.32  4937.4  356.33  4940.5  355.52  4943.2  355.02  4946.5  355.52
  4953.7     357  4989.6  359.64  4994.7   358.5  5014.7  359.44  5024.9  359.53
    5047   358.9  5055.5  359.28  5099.2  359.23  5106.3  359.51  5126.7  361.43
  5146.3  363.76  5151.4   363.8  5177.6  367.13  5184.1  368.28    5189  368.28
#Mann= 3 ,-1 , 0
  4720.8     .16       0  4940.5     .07       0  4946.5     .16       0
Bank Sta=4940.5,4946.5
XS Rating Curve= 0 ,0
Exp/Cntr=0.3,0.1

Type RM Length L Ch R = 1 ,1502    ,212,212,212
BEGIN DESCRIPTION:
UNT02310 IN SAND CR 2.3
END DESCRIPTION:
XS GIS Cut Line= 3
      3541711.54     10453332.62      3541798.35       10452876.
      3541798.35      10452872.5
#Sta/Elev= 30
  4718.4  368.23  4739.8  367.45  4760.1   365.9  4798.8  364.32    4811  363.23
  4831.4  362.41    4851   360.6  4856.1  359.59  4892.4  358.15  4913.4  355.74
  4933.2   355.1  4943.3  354.31  4950.5  352.75  4953.3  352.25  4956.5  352.75
  4960.5  353.85  4965.6  353.16  4984.1  353.44  5004.4     354  5012.7  354.86
  5017.8  353.41  5055.3  355.64    5070   355.6  5116.4  359.77  5122.2  361.29
  5127.3  361.03  5174.5  365.86  5179.6  366.04  5182.9   366.8  5186.7   366.8
#Mann= 3 ,-1 , 0
  4718.4     .16       0  4950.5     .07       0  4956.5     .16       0
Bank Sta=4950.5,4956.5
XS Rating Curve= 0 ,0
Exp/Cntr=0.3,0.1

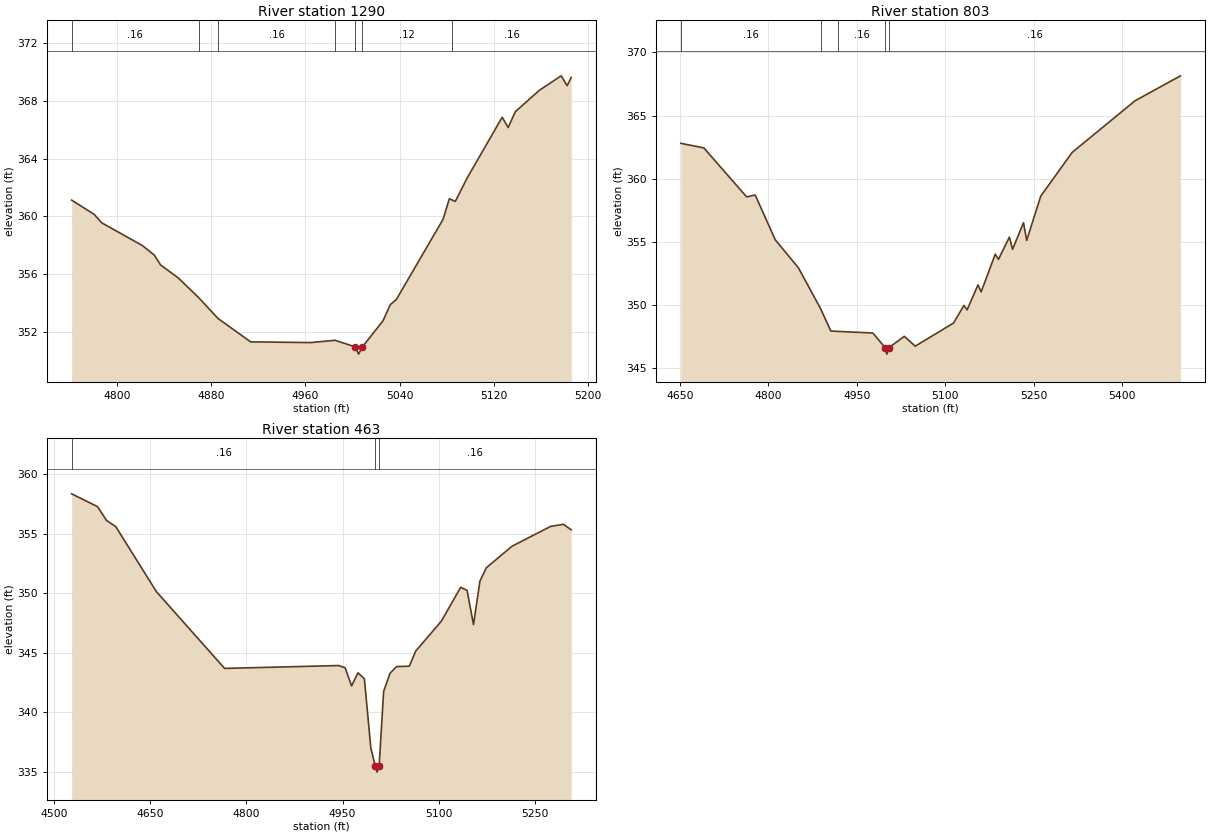
Type RM Length L Ch R = 1 ,1290    ,487,487,487
BEGIN DESCRIPTION:
UNT02310 IN SAND CR 2.0
END DESCRIPTION:
XS GIS Cut Line= 2
      3541881.68     10453320.46      3541968.19     10452905.18
#Sta/Elev= 30
  4761.5  361.12  4780.7  360.13    4787  359.55  4821.6  357.97  4831.8   357.3
    4837  356.63  4852.2  355.72  4869.3  354.37  4885.8  352.92  4913.5   351.3
  4964.6  351.25  4985.2  351.41  5002.4  350.95  5005.2  350.45  5008.4  350.95
  5025.9  352.76  5032.1  353.88  5037.2  354.23  5076.9  359.79  5082.2  361.21
  5084.6  361.13  5087.3  361.03  5097.4  362.66  5127.1  366.86  5132.2  366.15
  5138.2  367.24  5158.7  368.73  5177.2  369.73  5182.3  369.05  5185.7  369.61
#Mann= 7 ,-1 , 0
  4761.5     .16       0  4869.3     .12       0  4885.8     .16       0
  4985.2     .12       0  5002.4     .07       0  5008.4     .12       0
  5084.6     .16       0
Bank Sta=5002.4,5008.4
XS Rating Curve= 0 ,0
Exp/Cntr=0.3,0.1

Type RM Length L Ch R = 1 ,803     ,340,340,340
BEGIN DESCRIPTION:
UNT02310 IN SAND CR 1.0
END DESCRIPTION:
XS GIS Cut Line= 3
      3542243.36     10453429.13      3542312.79     10453181.78
      3542087.45     10452635.77
#Sta/Elev= 30
  4651.5   362.8  4690.4  362.44  4763.1  358.56  4777.6  358.71  4811.6  355.17
  4850.9  352.95  4888.6  349.71  4905.9  347.95  4917.4  347.92  4977.3  347.79
  4998.2  346.62    5001  346.12  5004.2  346.62  5030.6  347.53  5049.1  346.75
  5114.1  348.58  5131.7  349.97  5137.1  349.62  5155.6   351.6    5161  351.05
  5184.9  354.03  5190.3  353.62  5208.9  355.38  5214.3  354.41  5232.8  356.52
  5238.2  355.12  5262.1  358.62  5315.4  362.08  5421.9  366.16  5499.1  368.14
#Mann= 5 ,-1 , 0
  4651.5     .16       0  4888.6     .12       0  4917.4     .16       0
  4998.2     .07       0  5004.2     .16       0
Bank Sta=4998.2,5004.2
XS Rating Curve= 0 ,0
Exp/Cntr=0.3,0.1

Type RM Length L Ch R = 1 ,463     ,0,0,0
BEGIN DESCRIPTION:
UNT02310 IN SAND CR 1.1
END DESCRIPTION:
XS GIS Cut Line= 3
      3542369.35     10453355.64      3542534.31     10453168.97
      3542508.27     10452639.42
#Sta/Elev= 30
  4527.3  358.35  4567.6  357.28  4581.8  356.11  4596.1   355.6  4659.6  350.13
  4765.9  343.69  4943.9  343.93    4954  343.74    4964  342.22    4974  343.32
    4984  342.82    4994  337.02    5001  335.48  5003.8  334.98    5007  335.48
    5014  341.76    5024  343.28  5034.1  343.84  5054.1  343.88  5064.1  345.15
  5104.1  347.66  5134.2   350.5  5144.2  350.24  5154.2  347.37  5164.2  351.01
  5174.2  352.14  5214.3  353.95  5274.3  355.61  5294.4  355.79  5306.6  355.33
#Mann= 3 ,-1 , 0
  4527.3     .16       0    5001     .07       0    5007     .16       0
Bank Sta=5001,5007
XS Rating Curve= 0 ,0
Exp/Cntr=0.3,0.1

Chan Stop Cuts=-1
Use User Specified Reach Order=0
Composite Channel Slope=5