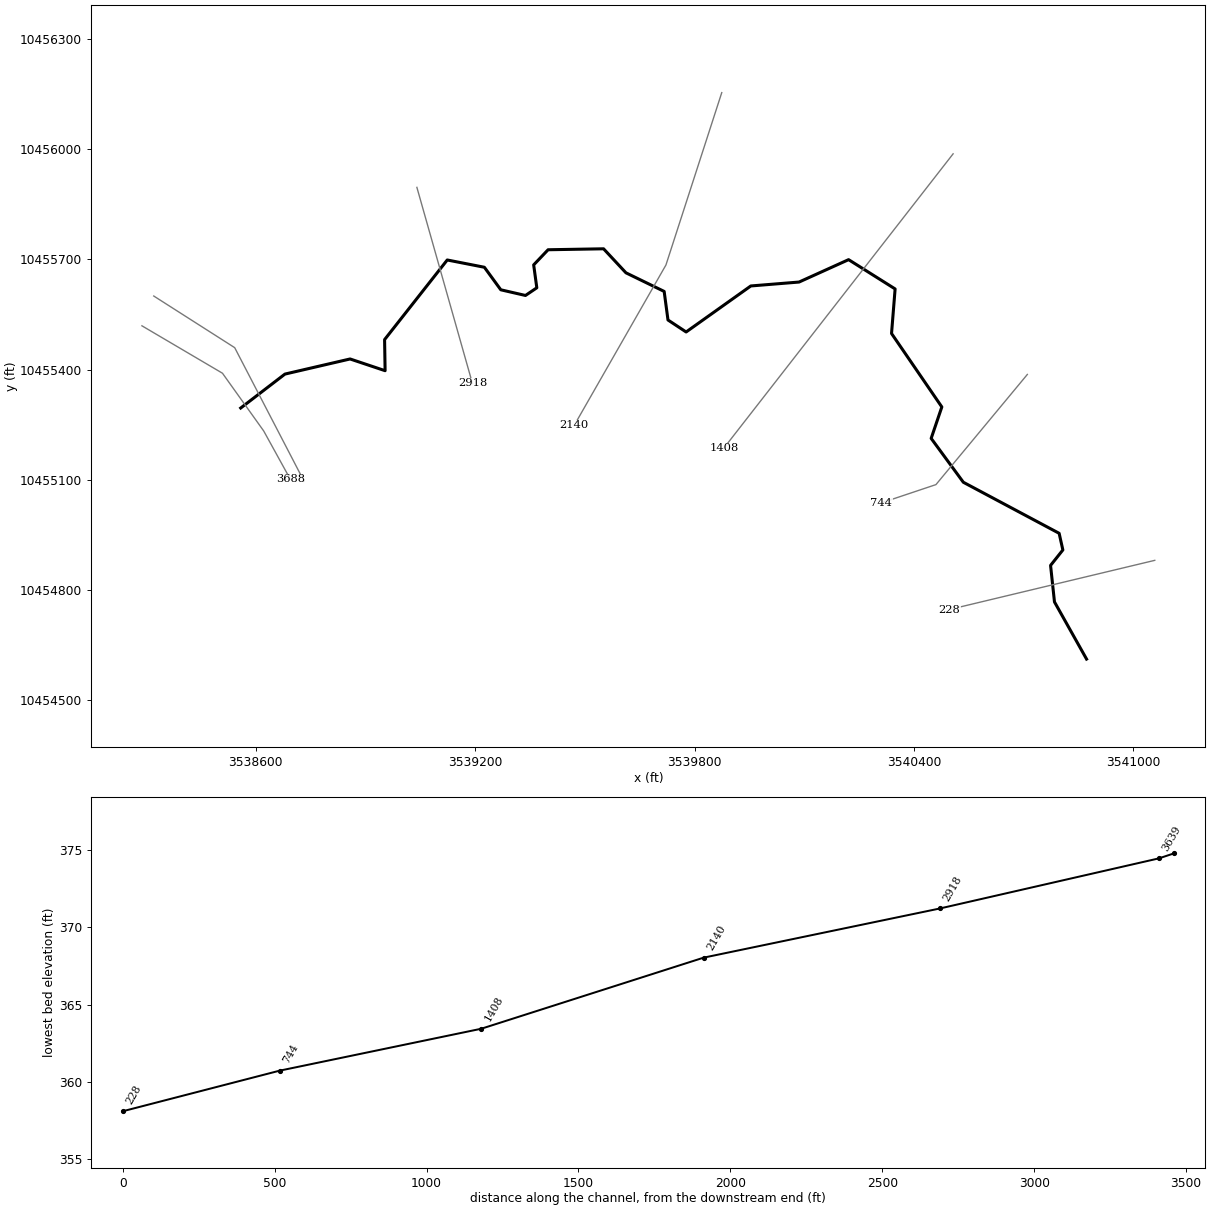
--- SANDY BRANCH TRIBUTARY 6 1.prj (project) ---

Proj Title=SANDY BRANCH TRIBUTARY 6 1 Base Level Engineering
Current Plan=p01
Default Exp/Contr=0.3,0.1
English Units
Geom File=g01
Flow File=f01
Plan File=p01
Y Axis Title=Elevation
X Axis Title(PF)=Main Channel Distance
X Axis Title(XS)=Station
BEGIN DESCRIPTION:
SANDY BRANCH TRIBUTARY 6 1
END DESCRIPTION:
DSS Export Rating Curves= 0
DSS Export Rating Curve Sorted= 0
DSS Export Volume Flow Curves= 0
DXF OffsetX= 0
DXF OffsetY= 0
DXF ScaleX= 1
DXF ScaleY= 10

--- SANDY BRANCH TRIBUTARY 6 1.p01 (plan) ---

Plan Title=Multiple Run
Short Identifier=Multiple
Geom File=g01
Flow File=f01
Subcritical Flow
K Sum by GR= 0
Std Step Tol= 0.01
Critical Tol= 0.01
Num of Std Step Trials= 20
Max Error Tol= 0.3
Flow Tol Ratio= 0.001
Split Flow NTrial= 30
Split Flow Tol= 0.02
Split Flow Ratio= 0.02
Log Output Level= 0
Friction Slope Method= 1
Unsteady Friction Slope Method= 2
Unsteady Bridges Friction Slope Method= 1
Parabolic Critical Depth
Global Vel Dist=  1 , 1 , 1
Global Log Level= 0
CheckData=True
Encroach Param= -1, 0, 0, 0
BEGIN DESCRIPTION:
Multiple Run
END DESCRIPTION:

--- SANDY BRANCH TRIBUTARY 6 1.f01 (steady flow) ---

Flow Title=Multiple
Number of Profiles=7
Profile Names=10-year,25-year,50-year,1pct_min,100-year,1pct_plu,500-year
River Rch & RM= SANDY BRANCH TRI,Reach-1,3688
     535     707     843     736     995    1345    1378
Boundary for River Rch & Prof#=SANDY BRANCH TRI,Reach-1,1
Up Type=0
Dn Type=3
Dn Slope=0.005
Boundary for River Rch & Prof#=SANDY BRANCH TRI,Reach-1,2
Up Type=0
Dn Type=3
Dn Slope=0.005
Boundary for River Rch & Prof#=SANDY BRANCH TRI,Reach-1,3
Up Type=0
Dn Type=3
Dn Slope=0.005
Boundary for River Rch & Prof#=SANDY BRANCH TRI,Reach-1,4
Up Type=0
Dn Type=3
Dn Slope=0.005
Boundary for River Rch & Prof#=SANDY BRANCH TRI,Reach-1,5
Up Type=0
Dn Type=3
Dn Slope=0.005
Boundary for River Rch & Prof#=SANDY BRANCH TRI,Reach-1,6
Up Type=0
Dn Type=3
Dn Slope=0.005
Boundary for River Rch & Prof#=SANDY BRANCH TRI,Reach-1,7
Up Type=0
Dn Type=3
Dn Slope=0.005

--- SANDY BRANCH TRIBUTARY 6 1.g01 (geometry) ---

Geom Title=Existing Conditions
Program Version=4.10

River Reach=SANDY BRANCH TRI,Reach-1
Reach XY= 30
      3538558.57     10455295.33      3538679.52     10455387.73
      3538857.74     10455428.91      3538953.52     10455396.96
      3538952.11     10455481.64      3539123.47     10455698.47
      3539225.04     10455678.66      3539269.96     10455617.27
      3539337.44     10455601.83      3539368.47     10455622.72
      3539359.88     10455685.12      3539399.29     10455726.33
      3539551.07     10455728.93      3539612.27     10455663.52
      3539716.77     10455612.85      3539727.25     10455535.03
      3539776.84      10455502.4      3539953.78     10455627.72
      3540085.74     10455638.38      3540221.21     10455699.37
      3540348.47     10455619.62      3540338.68     10455498.28
      3540476.25     10455298.23      3540447.09     10455212.63
      3540535.06     10455093.18       3540797.1     10454954.15
      3540807.29     10454908.83      3540773.67     10454866.74
      3540784.35     10454767.31      3540872.11     10454611.64

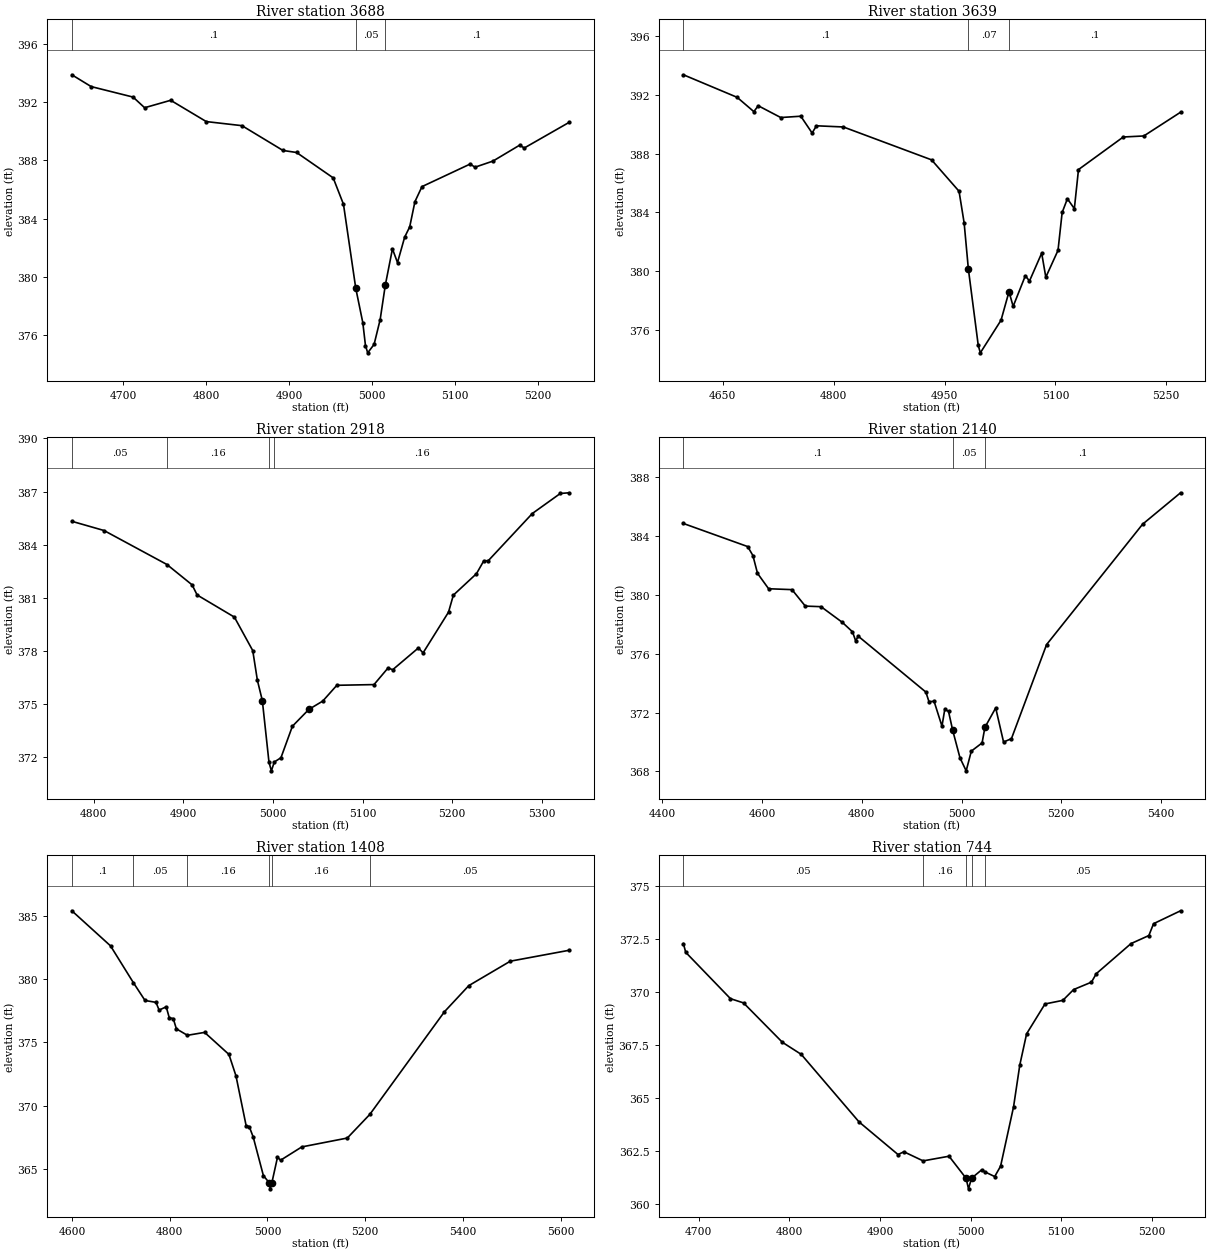
Type RM Length L Ch R = 1 ,3688    ,49,49,49
BEGIN DESCRIPTION:
UNT0784 IN SAND CR 12.2
END DESCRIPTION:
XS GIS Cut Line= 4
      3538288.41     10455519.21      3538508.67     10455390.09
      3538621.52     10455232.75      3538694.21     10455101.47
#Sta/Elev= 30
  4638.1  393.87  4661.4  393.06  4711.9  392.34  4725.8  391.61  4757.2  392.12
  4800.1  390.66  4843.1  390.38  4892.5  388.68  4908.9  388.54    4953   386.8
  4965.4  384.99  4980.2  379.23  4988.7  376.87  4991.9   375.3  4994.6   374.8
  5002.3  375.38  5009.6  377.08  5015.8  379.44  5024.4  381.93  5030.5  380.99
  5039.1  382.73  5045.2  383.44  5051.5  385.17    5060   386.2  5118.1  387.75
  5123.8  387.53  5145.5  387.95  5177.6  389.04  5183.3  388.85  5237.1   390.6
#Mann= 3 , 0 , 0
  4638.1      .1       0  4980.2     .05       0  5015.8      .1       0
Bank Sta=4980.2,5015.8
XS Rating Curve= 0 ,0
Exp/Cntr=0.3,0.1

Type RM Length L Ch R = 1 ,3639    ,721,721,721
BEGIN DESCRIPTION:
UNT0784 IN SAND CR 12.1
END DESCRIPTION:
XS GIS Cut Line= 3
      3538320.74     10455600.34      3538542.13      10455459.7
      3538731.84     10455095.87
#Sta/Elev= 30
  4596.7  393.34  4669.4  391.81    4692  390.84  4697.9  391.24  4728.4  390.44
  4755.5  390.53  4770.8  389.39  4776.7  389.88  4813.1   389.8  4932.4  387.57
  4969.6  385.44  4976.5  383.29  4982.2  380.17  4995.6  374.98  4998.4  374.48
  5026.4  376.69  5037.2  378.63  5042.8  377.63  5059.3  379.71  5064.9  379.35
  5081.4  381.24    5087  379.61  5103.5  381.43  5109.1     384  5116.2  384.93
  5125.6  384.26  5131.2  386.91  5191.8  389.12  5219.6  389.19  5269.3   390.8
#Mann= 3 , 0 , 0
  4596.7      .1       0  4982.2     .07       0  5037.2      .1       0
Bank Sta=4982.2,5037.2
XS Rating Curve= 0 ,0
Exp/Cntr=0.3,0.1

Type RM Length L Ch R = 1 ,2918    ,778,778,778
BEGIN DESCRIPTION:
UNT0784 IN SAND CR 11.0
END DESCRIPTION:
XS GIS Cut Line= 2
      3539040.45      10455896.2      3539192.38     10455362.29
#Sta/Elev= 30
  4775.4  385.32  4811.3   384.8  4881.6  382.88  4909.7  381.73  4915.3  381.16
  4956.9  379.91  4977.4  378.02  4982.6  376.34  4988.1   375.2  4995.5  371.73
  4998.2  371.23  5001.5  371.73  5008.9  371.97  5021.7  373.75  5040.1   374.7
  5055.6  375.17  5071.3  376.06  5112.8   376.1  5128.5  377.04  5133.7  376.94
  5162.4  378.17  5167.6  377.89    5196  380.19  5201.4  381.15  5227.2  382.36
  5235.3  383.08  5240.5   383.1  5289.6  385.76  5320.8  386.89  5330.5  386.93
#Mann= 4 ,-1 , 0
  4775.4     .05       0  4881.6     .16       0  4995.5     .07       0
  5001.5     .16       0
Bank Sta=4988.1,5040.1
XS Rating Curve= 0 ,0
Exp/Cntr=0.3,0.1

Type RM Length L Ch R = 1 ,2140    ,732,732,732
BEGIN DESCRIPTION:
UNT0784 IN SAND CR 9.0
END DESCRIPTION:
XS GIS Cut Line= 3
      3539874.31     10456154.21      3539721.65     10455684.84
      3539470.68     10455247.97
#Sta/Elev= 30
  4442.1  384.87    4571   383.3  4581.5  382.69  4590.7  381.48    4613  380.43
  4659.9  380.37  4686.6  379.25  4718.2  379.21    4761  378.14  4781.3   377.5
  4787.6  376.89  4792.9   377.2  4928.5   373.4  4934.7  372.75    4945  372.77
  4960.8  371.08  4966.5  372.23    4974  372.08  4982.3   370.8    4997  368.92
  5009.4  368.04  5019.7  369.38  5041.3  369.94    5047     371  5068.6  372.32
  5084.4     370  5100.2  370.23  5170.7  376.63  5363.3  384.82  5439.5  386.96
#Mann= 3 , 0 , 0
  4442.1      .1       0  4982.3     .05       0    5047      .1       0
Bank Sta=4982.3,5047
XS Rating Curve= 0 ,0
Exp/Cntr=0.3,0.1

Type RM Length L Ch R = 1 ,1408    ,664,664,664
BEGIN DESCRIPTION:
UNT0784 IN SAND CR 8.0
END DESCRIPTION:
XS GIS Cut Line= 2
      3540507.11     10455987.52      3539879.97     10455186.02
#Sta/Elev= 30
  4599.6  385.38  4678.8  382.61  4725.5  379.71  4749.4   378.3  4771.9  378.15
  4778.3  377.54  4792.8   377.8  4799.1  376.93  4807.2  376.87  4813.6  376.06
  4836.2  375.55  4871.4  375.78  4921.2  374.04  4935.6  372.35  4956.4  368.42
  4962.8  368.34  4970.9  367.52  4991.7  364.48  5003.2  363.93  5005.9  363.43
  5009.2  363.93  5020.6  365.92    5027  365.69  5070.4  366.74  5163.5  367.44
  5209.7  369.31  5362.4  377.41  5412.2  379.47  5497.2   381.4  5617.3  382.26
#Mann= 6 ,-1 , 0
  4599.6      .1       0  4725.5     .05       0  4836.2     .16       0
  5003.2     .07       0  5009.2     .16       0  5209.7     .05       0
Bank Sta=5003.2,5009.2
XS Rating Curve= 0 ,0
Exp/Cntr=0.3,0.1

Type RM Length L Ch R = 1 ,744     ,516,516,516
BEGIN DESCRIPTION:
UNT0784 IN SAND CR 6.0
END DESCRIPTION:
XS GIS Cut Line= 3
      3540710.16     10455386.78      3540460.16     10455086.78
      3540310.18     10455036.79
#Sta/Elev= 30
  4683.1  372.29  4685.6  371.88    4735  369.69  4749.4  369.49  4792.3  367.63
  4813.1  367.06  4876.9  363.87  4919.9  362.33  4926.4  362.46  4947.6  362.03
  4976.2  362.25    4995  361.21  4997.7  360.71    5001  361.21  5012.3  361.61
  5016.3   361.5  5026.6  361.29  5033.1  361.78  5047.4  364.58  5054.3  366.56
  5061.8  368.03  5082.1  369.44  5101.8  369.61  5113.7  370.12  5133.4  370.47
  5138.7  370.87    5177  372.29  5196.7  372.67  5201.9  373.23  5231.7  373.84
#Mann= 5 ,-1 , 0
  4683.1     .05       0  4947.6     .16       0    4995     .07       0
    5001     .16       0  5016.3     .05       0
Bank Sta=4995,5001
XS Rating Curve= 0 ,0
Exp/Cntr=0.3,0.1

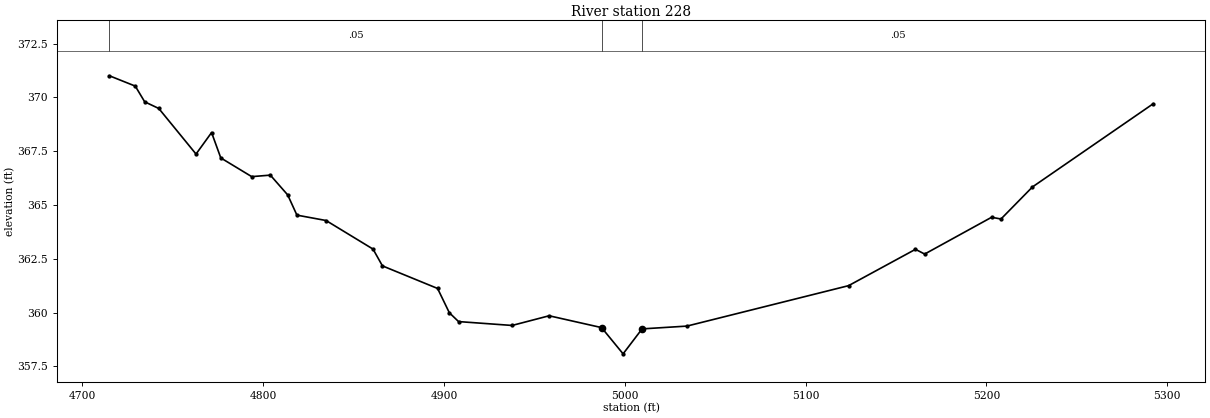
Type RM Length L Ch R = 1 ,228     ,0,0,0
BEGIN DESCRIPTION:
UNT0784 IN SAND CR 5.0
END DESCRIPTION:
XS GIS Cut Line= 2
      3541058.68     10454880.54      3540497.13     10454746.63
#Sta/Elev= 30
    4715  371.01  4729.3  370.53  4734.5   369.8  4742.3  369.49  4762.9  367.37
  4771.5  368.37  4776.6  367.19  4793.7  366.32    4804  366.39  4813.6  365.47
  4818.7  364.53  4834.8  364.28  4860.8  362.95    4866  362.17  4896.5  361.12
    4903  359.99  4908.1  359.58  4937.7   359.4  4958.2  359.85  4987.2   359.3
  4999.1  358.08  5009.6  359.24  5034.4  359.37  5123.8  361.25  5160.8  362.94
  5165.9  362.72  5202.9  364.43  5208.1  364.35  5225.5  365.84  5292.3  369.71
#Mann= 3 , 0 , 0
    4715     .05       0  4987.2     .03       0  5009.6     .05       0
Bank Sta=4987.2,5009.6
XS Rating Curve= 0 ,0
Exp/Cntr=0.3,0.1

Chan Stop Cuts=-1
Use User Specified Reach Order=0
Composite Channel Slope=5