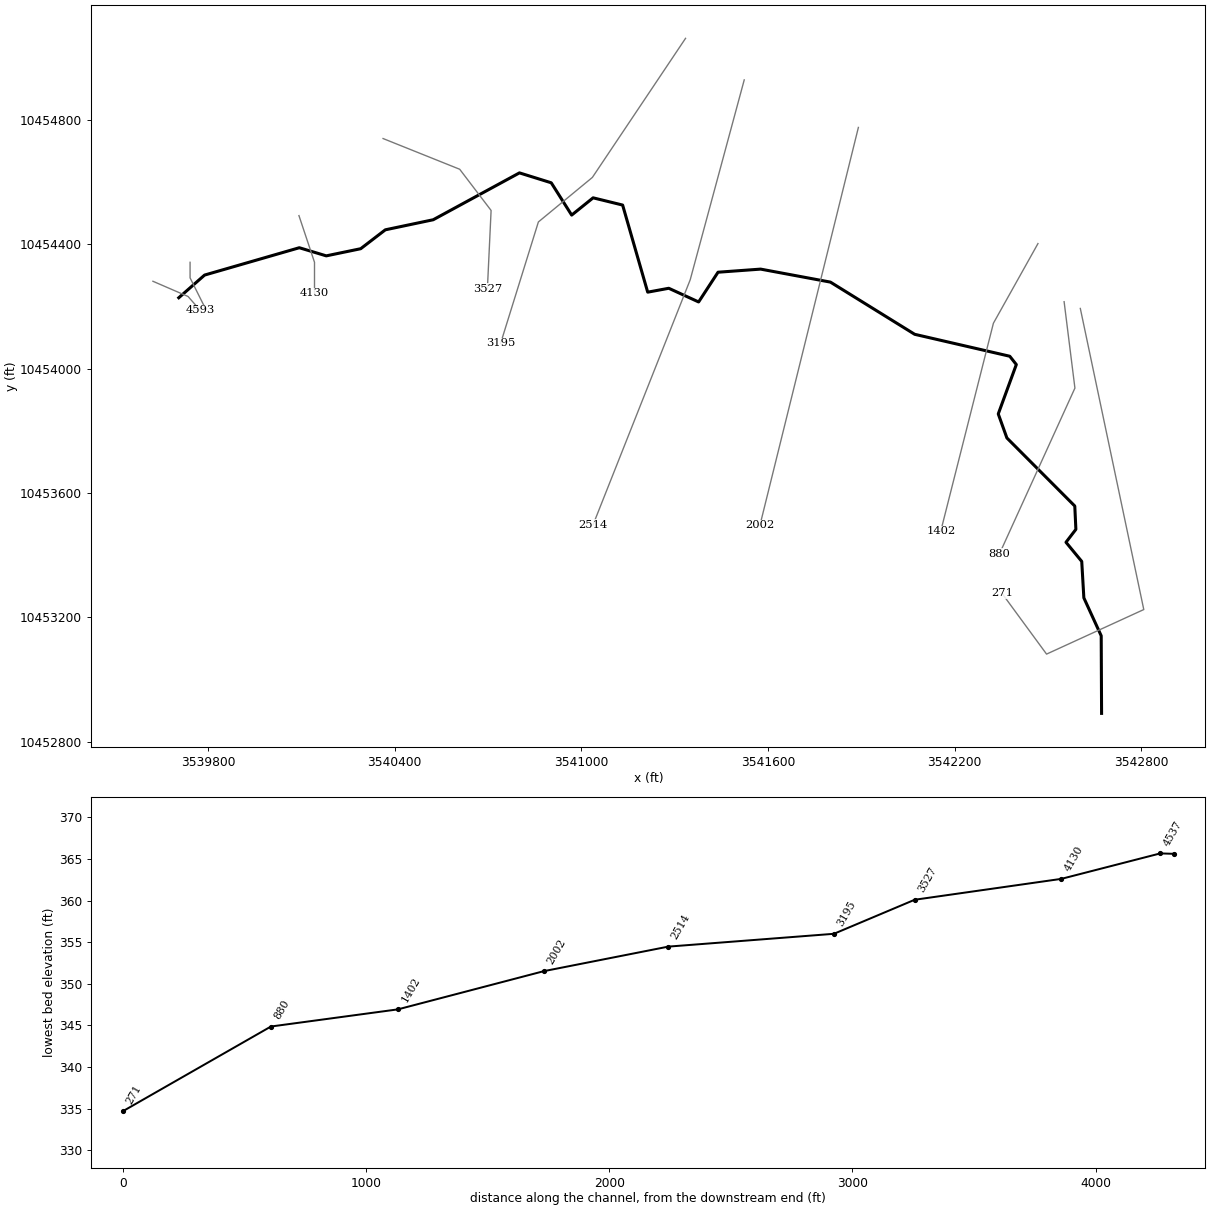
--- SANDY BRANCH TRIBUTARY 6.prj (project) ---

Proj Title=SANDY BRANCH TRIBUTARY 6 Base Level Engineering
Current Plan=p01
Default Exp/Contr=0.3,0.1
English Units
Geom File=g01
Flow File=f01
Plan File=p01
Y Axis Title=Elevation
X Axis Title(PF)=Main Channel Distance
X Axis Title(XS)=Station
BEGIN DESCRIPTION:
SANDY BRANCH TRIBUTARY 6
END DESCRIPTION:
DSS Export Rating Curves= 0
DSS Export Rating Curve Sorted= 0
DSS Export Volume Flow Curves= 0
DXF OffsetX= 0
DXF OffsetY= 0
DXF ScaleX= 1
DXF ScaleY= 10

--- SANDY BRANCH TRIBUTARY 6.p01 (plan) ---

Plan Title=Multiple Run
Short Identifier=Multiple
Geom File=g01
Flow File=f01
Subcritical Flow
K Sum by GR= 0
Std Step Tol= 0.01
Critical Tol= 0.01
Num of Std Step Trials= 20
Max Error Tol= 0.3
Flow Tol Ratio= 0.001
Split Flow NTrial= 30
Split Flow Tol= 0.02
Split Flow Ratio= 0.02
Log Output Level= 0
Friction Slope Method= 1
Unsteady Friction Slope Method= 2
Unsteady Bridges Friction Slope Method= 1
Parabolic Critical Depth
Global Vel Dist=  1 , 1 , 1
Global Log Level= 0
CheckData=True
Encroach Param= -1, 0, 0, 0
BEGIN DESCRIPTION:
Multiple Run
END DESCRIPTION:

--- SANDY BRANCH TRIBUTARY 6.f01 (steady flow) ---

Flow Title=Multiple
Program Version=4.10
Number of Profiles= 7
Profile Names=10-year,25-year,50-year,1pct_min,100-year,1pct_plu,500-year
River Rch & RM=SANDY BRANCH TRI,Reach-1         ,4593
     246     310     358     304     411     556     537
River Rch & RM=SANDY BRANCH TRI,Reach-1         ,3195
     722     972    1174    1035    1400    1893    1985
Boundary for River Rch & Prof#=SANDY BRANCH TRI,Reach-1         , 1
Up Type= 0
Dn Type= 3
Dn Slope=0.012
Boundary for River Rch & Prof#=SANDY BRANCH TRI,Reach-1         , 2
Up Type= 0
Dn Type= 3
Dn Slope=0.012
Boundary for River Rch & Prof#=SANDY BRANCH TRI,Reach-1         , 3
Up Type= 0
Dn Type= 3
Dn Slope=0.012
Boundary for River Rch & Prof#=SANDY BRANCH TRI,Reach-1         , 4
Up Type= 0
Dn Type= 3
Dn Slope=0.012
Boundary for River Rch & Prof#=SANDY BRANCH TRI,Reach-1         , 5
Up Type= 0
Dn Type= 3
Dn Slope=0.012
Boundary for River Rch & Prof#=SANDY BRANCH TRI,Reach-1         , 6
Up Type= 0
Dn Type= 3
Dn Slope=0.012
Boundary for River Rch & Prof#=SANDY BRANCH TRI,Reach-1         , 7
Up Type= 0
Dn Type= 3
Dn Slope=0.012
DSS Import GetInterval= 0
DSS Import GetPeak= 0
DSS Import FillOption= 0

--- SANDY BRANCH TRIBUTARY 6.g01 (geometry) ---

Geom Title=Existing Conditions
Program Version=4.10

River Reach=SANDY BRANCH TRI,Reach-1
Reach XY= 30
      3539705.79     10454227.62      3539788.78     10454300.54
      3540093.26     10454388.42      3540179.91     10454362.29
       3540290.6     10454385.27      3540369.75       10454446.
      3540523.73     10454478.39       3540800.9     10454629.03
      3540903.11     10454597.17      3540968.77     10454493.34
      3541037.66     10454548.83      3541132.52      10454525.6
      3541213.14     10454245.59      3541280.88      10454258.1
      3541376.83     10454214.12      3541439.21     10454309.72
      3541576.18     10454319.69      3541800.47     10454277.92
      3542071.35     10454110.15      3542376.98      10454039.6
      3542398.04     10454012.89      3542339.98     10453854.22
      3542367.75     10453776.94      3542585.98     10453558.12
      3542589.49     10453483.11      3542557.67     10453441.63
      3542608.32      10453380.1      3542615.14     10453262.93
      3542670.89     10453141.07      3542672.11     10452891.64

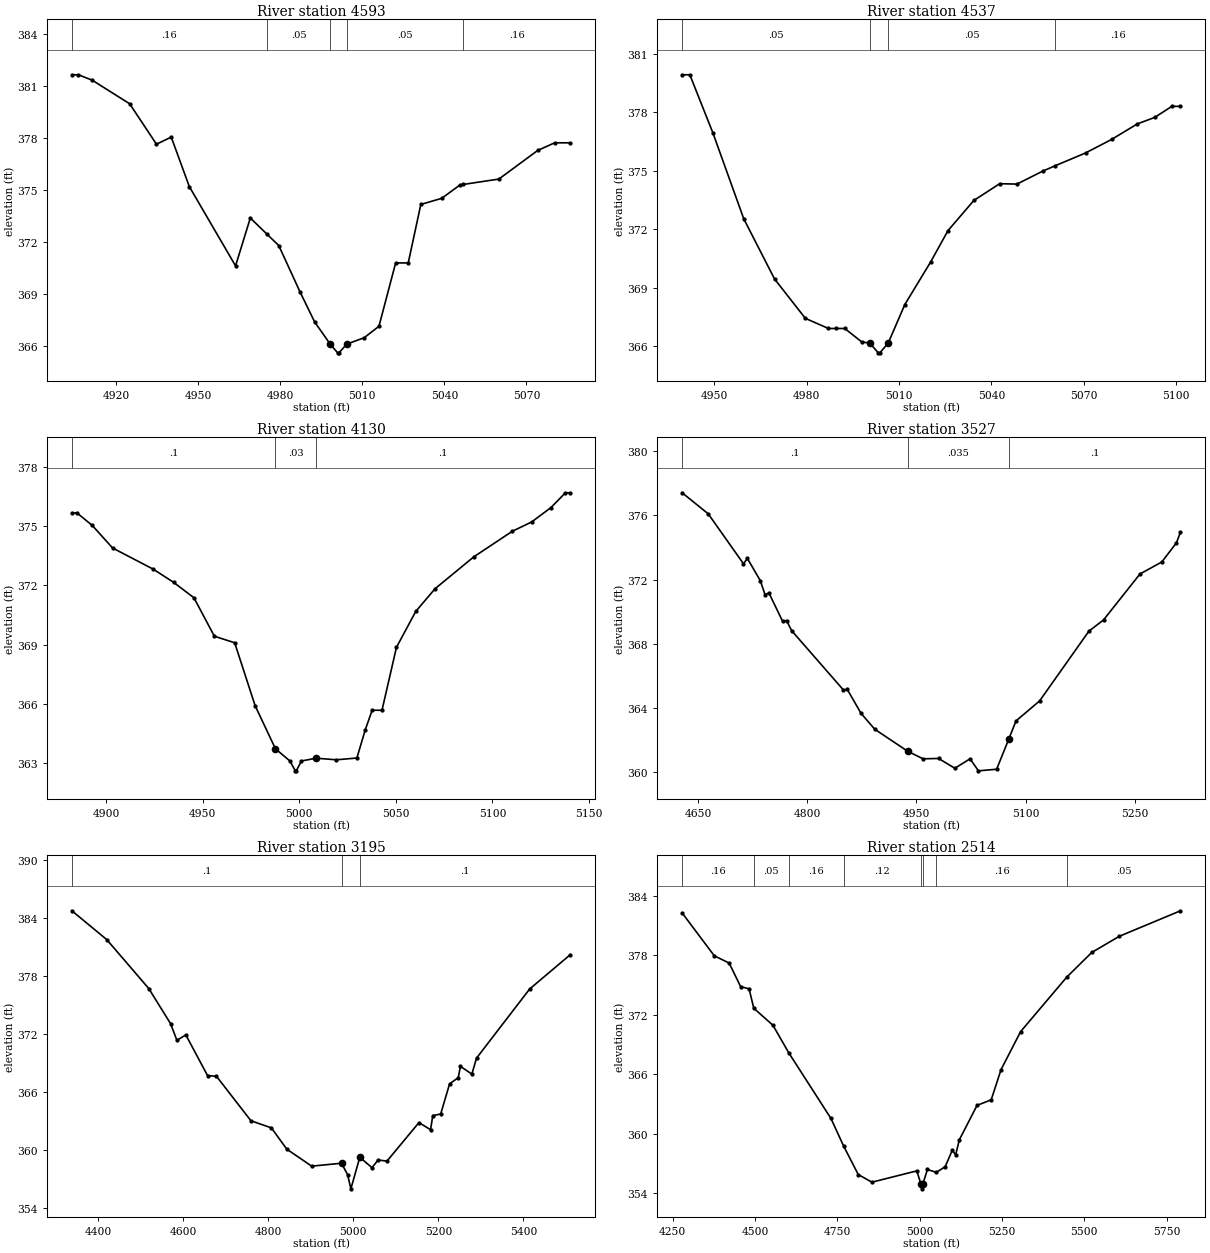
Type RM Length L Ch R = 1 ,4593    ,56,56,56
BEGIN DESCRIPTION:
UNT02309 IN SAND CR 3.1
END DESCRIPTION:
XS GIS Cut Line= 3
      3539622.73     10454280.61      3539735.56     10454231.79
      3539774.59     10454187.33
#Sta/Elev= 29
  4903.9  381.63  4906.3  381.63  4911.3  381.32    4925  379.96  4934.8  377.63
  4940.2  378.04  4946.8  375.19  4963.7  370.62  4969.1  373.38  4975.1  372.46
  4979.5  371.79  4987.2  369.14  4992.6  367.39  4998.3  366.11    5001  365.61
  5001.5  365.61  5004.3  366.11  5010.7  366.48  5016.1  367.14  5022.2  370.79
  5026.8  370.79  5031.4  374.16    5039  374.51  5045.7  375.28  5046.8  375.31
  5059.9  375.62  5074.1  377.27  5080.3  377.71    5086  377.71
#Mann= 5 ,-1 , 0
  4903.9     .16       0  4975.1     .05       0  4998.3    .035       0
  5004.3     .05       0  5046.8     .16       0
Bank Sta=4998.3,5004.3
XS Rating Curve= 0 ,0
Exp/Cntr=0.3,0.1

Type RM Length L Ch R = 1 ,4537    ,407,407,407
BEGIN DESCRIPTION:
UNT02309 IN SAND CR 3.0
END DESCRIPTION:
XS GIS Cut Line= 3
      3539742.11      10454341.6      3539742.11     10454291.64
      3539792.12     10454191.61
#Sta/Elev= 28
  4939.6  379.93  4942.1  379.93  4949.6  376.94  4959.6  372.54  4969.6  369.45
  4979.6  367.43  4987.1  366.91  4989.6  366.91  4992.4  366.91  4997.9  366.22
  5000.5  366.16  5003.3  365.66  5003.8  365.66  5006.5  366.16  5011.9  368.14
  5020.3  370.33  5025.9  371.93  5034.3  373.48  5042.7  374.34  5048.3  374.32
  5056.6  374.98  5060.7  375.26  5070.6  375.92    5079  376.61  5087.4  377.41
    5093  377.74  5098.6  378.31  5101.4  378.31
#Mann= 4 ,-1 , 0
  4939.6     .05       0  5000.5    .035       0  5006.5     .05       0
  5060.7     .16       0
Bank Sta=5000.5,5006.5
XS Rating Curve= 0 ,0
Exp/Cntr=0.3,0.1

Type RM Length L Ch R = 1 ,4130    ,603,603,603
BEGIN DESCRIPTION:
UNT02309 IN SAND CR 2.0
END DESCRIPTION:
XS GIS Cut Line= 3
      3540092.11     10454491.63      3540142.11     10454341.64
      3540142.11     10454241.64
#Sta/Elev= 30
  4882.2  375.67  4884.8  375.67  4892.7  375.04  4903.3  373.89  4924.3  372.82
  4934.9  372.15  4945.4  371.37    4956  369.42  4966.5  369.09  4977.1   365.9
  4987.6  363.72  4995.1   363.1  4997.9   362.6  4998.4   362.6  5001.1   363.1
  5008.7  363.24  5019.2  363.16  5029.8  363.25 5034.11  364.67  5037.7  365.67
  5042.8  365.67  5050.3  368.86  5060.3  370.68  5070.3  371.83  5090.3  373.44
  5110.3  374.74  5120.3  375.21  5130.3  375.94  5137.8  376.69  5140.3  376.69
#Mann= 3 , 0 , 0
  4882.2      .1       0  4987.6     .03       0  5008.7      .1       0
Bank Sta=4987.6,5008.7
XS Rating Curve= 0 ,0
Exp/Cntr=0.3,0.1

Type RM Length L Ch R = 1 ,3527    ,332,332,332
BEGIN DESCRIPTION:
UNT02309 IN SAND CR 1.0
END DESCRIPTION:
XS GIS Cut Line= 4
      3540362.49     10454739.41      3540608.84     10454640.65
      3540709.75     10454508.27      3540697.84     10454256.02
#Sta/Elev= 30
  4628.2  377.41    4664   376.1  4712.4  372.99  4717.8  373.32  4735.5  371.94
    4742  371.07  4747.4  371.17  4766.2   369.4  4771.6  369.45  4778.6  368.82
  4849.6  365.13    4855  365.16  4873.9  363.67  4892.7  362.68  4938.3   361.3
  4959.1  360.84  4980.4  360.86  5002.7  360.25  5023.6  360.84  5035.1  360.09
  5060.1  360.19  5076.7  362.06  5086.7   363.2    5119  364.44  5186.8  368.79
  5206.9  369.49  5256.9  372.35  5286.9   373.1    5307  374.29  5312.6  374.96
#Mann= 3 , 0 , 0
  4628.2      .1       0  4938.3    .035       0  5076.7      .1       0
Bank Sta=4938.3,5076.7
XS Rating Curve= 0 ,0
Exp/Cntr=0.3,0.1

Type RM Length L Ch R = 1 ,3195    ,681,681,681
BEGIN DESCRIPTION:
UNT0784 IN SAND CR 4.0
END DESCRIPTION:
XS GIS Cut Line= 4
       3541334.8     10455061.51      3541035.33     10454614.48
      3540861.72     10454471.25       3540740.2     10454080.65
#Sta/Elev= 30
  4338.1  384.79    4420  381.81  4519.1  376.73  4570.1  373.11  4585.1  371.38
  4606.1  371.94  4657.1  367.73  4678.2  367.65  4759.2  363.05  4807.4  362.31
  4843.5  360.11    4902  358.35  4972.3  358.65  4986.7  357.46  4994.3     356
  5015.3  359.27    5044  358.19  5058.3  358.99  5079.2  358.87  5154.4  362.86
  5181.7  362.12    5187  363.58  5205.6  363.75  5226.5  366.87  5246.8  367.51
    5252  368.68  5278.9  367.88  5289.8  369.53  5414.8  376.69  5510.3  380.24
#Mann= 3 , 0 , 0
  4338.1      .1       0  4972.3     .05       0  5015.3      .1       0
Bank Sta=4972.3,5015.3
XS Rating Curve= 0 ,0
Exp/Cntr=0.3,0.1

Type RM Length L Ch R = 1 ,2514    ,512,512,512
BEGIN DESCRIPTION:
UNT0784 IN SAND CR 3.0
END DESCRIPTION:
XS GIS Cut Line= 3
      3541523.43      10454927.9      3541349.83     10454285.57
      3541037.31     10453497.34
#Sta/Elev= 30
  4278.6  382.26  4376.3  377.94  4421.4  377.21  4456.1  374.84  4481.9  374.61
  4496.1  372.66  4554.4  370.94  4602.1  368.18  4730.5  361.55  4769.1  358.76
  4813.4   355.9  4854.8  355.13  4991.2  356.27  5003.5  354.96  5006.2  354.46
  5009.5  354.96  5023.5  356.41  5050.5  356.12  5077.3  356.69  5098.8  358.34
  5109.2  357.89  5120.3   359.4  5174.1  362.87  5217.1  363.43  5246.9  366.47
  5306.3   370.3  5446.4  375.79  5522.4  378.28  5606.2  379.91  5791.9  382.48
#Mann= 8 ,-1 , 0
  4278.6     .16       0  4496.1     .05       0  4602.1     .16       0
  4769.1     .12       0  5003.5     .07       0  5009.5     .12       0
  5050.5     .16       0  5446.4     .05       0
Bank Sta=5003.5,5009.5
XS Rating Curve= 0 ,0
Exp/Cntr=0.3,0.1

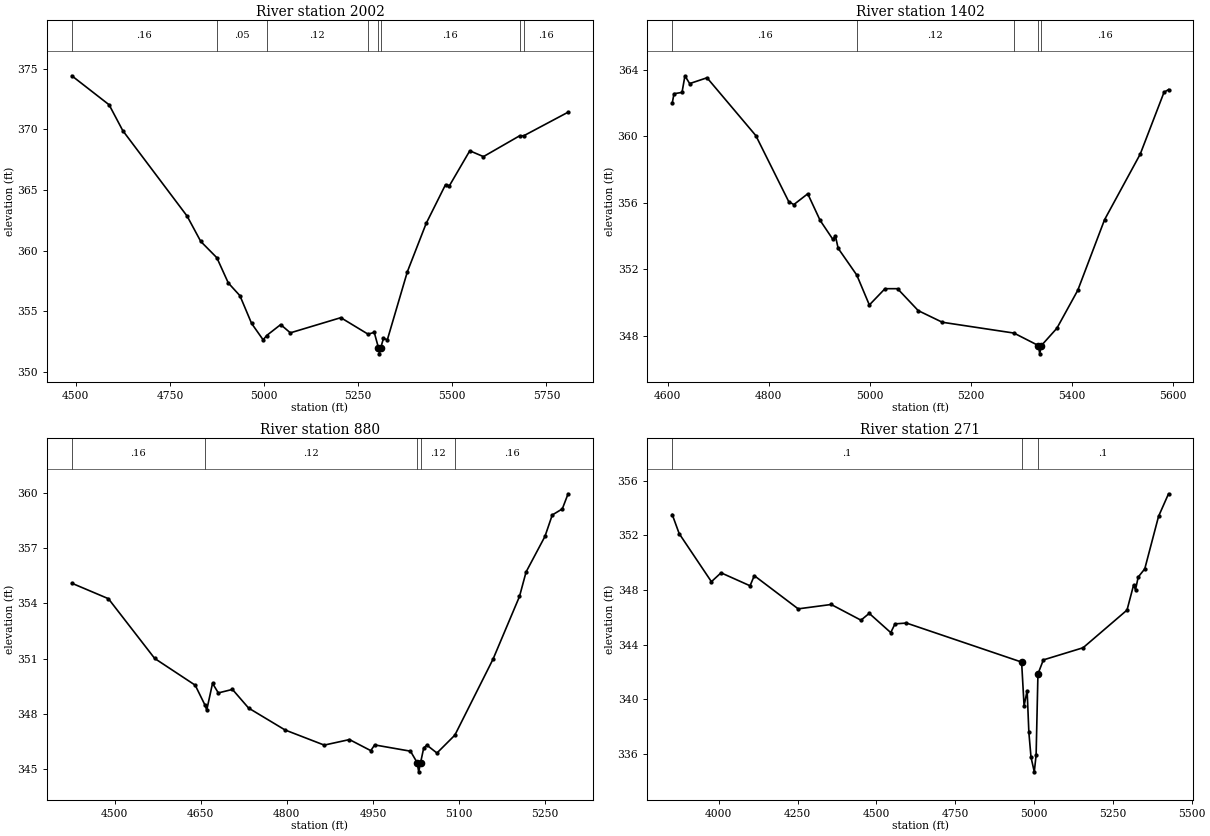
Type RM Length L Ch R = 1 ,2002    ,600,600,600
BEGIN DESCRIPTION:
UNT0784 IN SAND CR 2.0
END DESCRIPTION:
XS GIS Cut Line= 2
      3541890.37     10454775.09      3541573.77     10453495.69
#Sta/Elev= 30
  4489.4  374.42  4588.5  372.03  4624.8   369.9  4795.6  362.86  4831.9  360.77
  4874.6  359.43    4905  357.35  4935.9   356.3  4966.8  354.02  4997.6  352.66
  5006.9  353.02  5044.1  353.92  5069.8  353.24  5203.8  354.49  5276.2  353.13
  5292.6  353.28  5303.8  352.01  5306.5  351.51  5309.8  352.01  5317.1  352.78
  5327.4  352.67  5380.6  358.28  5430.4  362.25  5481.9  365.45  5492.2  365.36
  5546.3  368.24  5582.6  367.76  5678.4  369.47  5689.8  369.48  5807.4  371.42
#Mann= 8 ,-1 , 0
  4489.4     .16       0  4874.6     .05       0  5006.9     .12       0
  5276.2     .16       0  5303.8     .04       0  5309.8     .16       0
  5678.4     .05       0  5689.8     .16       0
Bank Sta=5303.8,5309.8
XS Rating Curve= 0 ,0
Exp/Cntr=0.3,0.1

Type RM Length L Ch R = 1 ,1402    ,522,522,522
BEGIN DESCRIPTION:
UNT0784 IN SAND CR 1.2
END DESCRIPTION:
XS GIS Cut Line= 3
      3542467.61     10454401.79      3542324.39     10454145.73
      3542155.12     10453477.32
#Sta/Elev= 30
  4609.2     362  4612.7  362.57  4628.6  362.65  4634.4  363.65  4643.7  363.18
  4678.1  363.53  4774.8  360.05  4839.9  356.08    4850   355.9  4877.6  356.55
  4902.1  354.95  4927.3  353.81  4932.4  354.01  4937.8  353.27  4974.7  351.66
  4999.6  349.86  5030.6  350.84  5055.4  350.84  5096.4  349.52  5144.1  348.82
  5285.9  348.17  5334.3  347.42    5337  346.92  5340.3  347.42    5371  348.46
  5412.3  350.74  5465.4  354.99  5536.1  358.94  5583.2  362.66  5592.1  362.82
#Mann= 5 ,-1 , 0
  4609.2     .16       0  4974.7     .12       0  5285.9     .16       0
  5334.3     .07       0  5340.3     .16       0
Bank Sta=5334.3,5340.3
XS Rating Curve= 0 ,0
Exp/Cntr=0.3,0.1

Type RM Length L Ch R = 1 ,880     ,609,609,609
BEGIN DESCRIPTION:
UNT0784 IN SAND CR 1.0
END DESCRIPTION:
XS GIS Cut Line= 3
      3542551.68     10454214.95       3542586.4      10453937.2
      3542344.08     10453404.98
#Sta/Elev= 30
  4425.3  355.09  4489.1  354.25  4569.7  351.01  4640.3  349.56  4657.5  348.47
  4660.4  348.21  4670.5  349.66  4680.6  349.14  4705.2  349.33  4733.3  348.32
  4796.9  347.13  4865.1  346.31  4909.1  346.61  4946.2  346.01    4953  346.32
  5015.4  345.98    5027  345.36  5029.7  344.86    5033  345.36  5038.4  346.15
  5043.9  346.31  5061.5  345.88  5092.7  346.85  5159.2  350.97  5205.3  354.37
  5216.8   355.7  5249.7  357.63  5262.4  358.79  5279.9  359.12    5290  359.94
#Mann= 5 ,-1 , 0
  4425.3     .16       0  4657.5     .12       0    5027     .07       0
    5033     .12       0  5092.7     .16       0
Bank Sta=5027,5033
XS Rating Curve= 0 ,0
Exp/Cntr=0.3,0.1

Type RM Length L Ch R = 1 ,271     ,0,0,0
BEGIN DESCRIPTION:
UNT0784 IN SAND CR 1.1
END DESCRIPTION:
XS GIS Cut Line= 4
      3542603.76     10454193.24      3542807.75     10453225.39
      3542495.25     10453082.16       3542352.3     10453277.09
#Sta/Elev= 30
    3852  353.53  3874.1  352.13  3976.3  348.61  4006.9  349.26  4098.9  348.31
  4112.4  349.05  4251.6  346.62  4356.3  346.94  4450.8  345.79    4477  346.29
  4545.3  344.88  4558.8  345.52  4595.1  345.58  4960.5  342.72  4968.3  339.51
    4978  340.63  4983.5  337.57  4990.3  335.75  5000.7  334.68  5006.5  335.91
  5012.3  341.85  5029.5  342.88  5155.5  343.77  5294.9  346.53  5315.7  348.36
  5321.9  348.02  5330.4  348.95  5351.2  349.55    5395   353.4  5426.6  355.05
#Mann= 3 , 0 , 0
    3852      .1       0  4960.5     .05       0  5012.3      .1       0
Bank Sta=4960.5,5012.3
XS Rating Curve= 0 ,0
Exp/Cntr=0.3,0.1

Chan Stop Cuts=-1
Use User Specified Reach Order=0
Composite Channel Slope=5