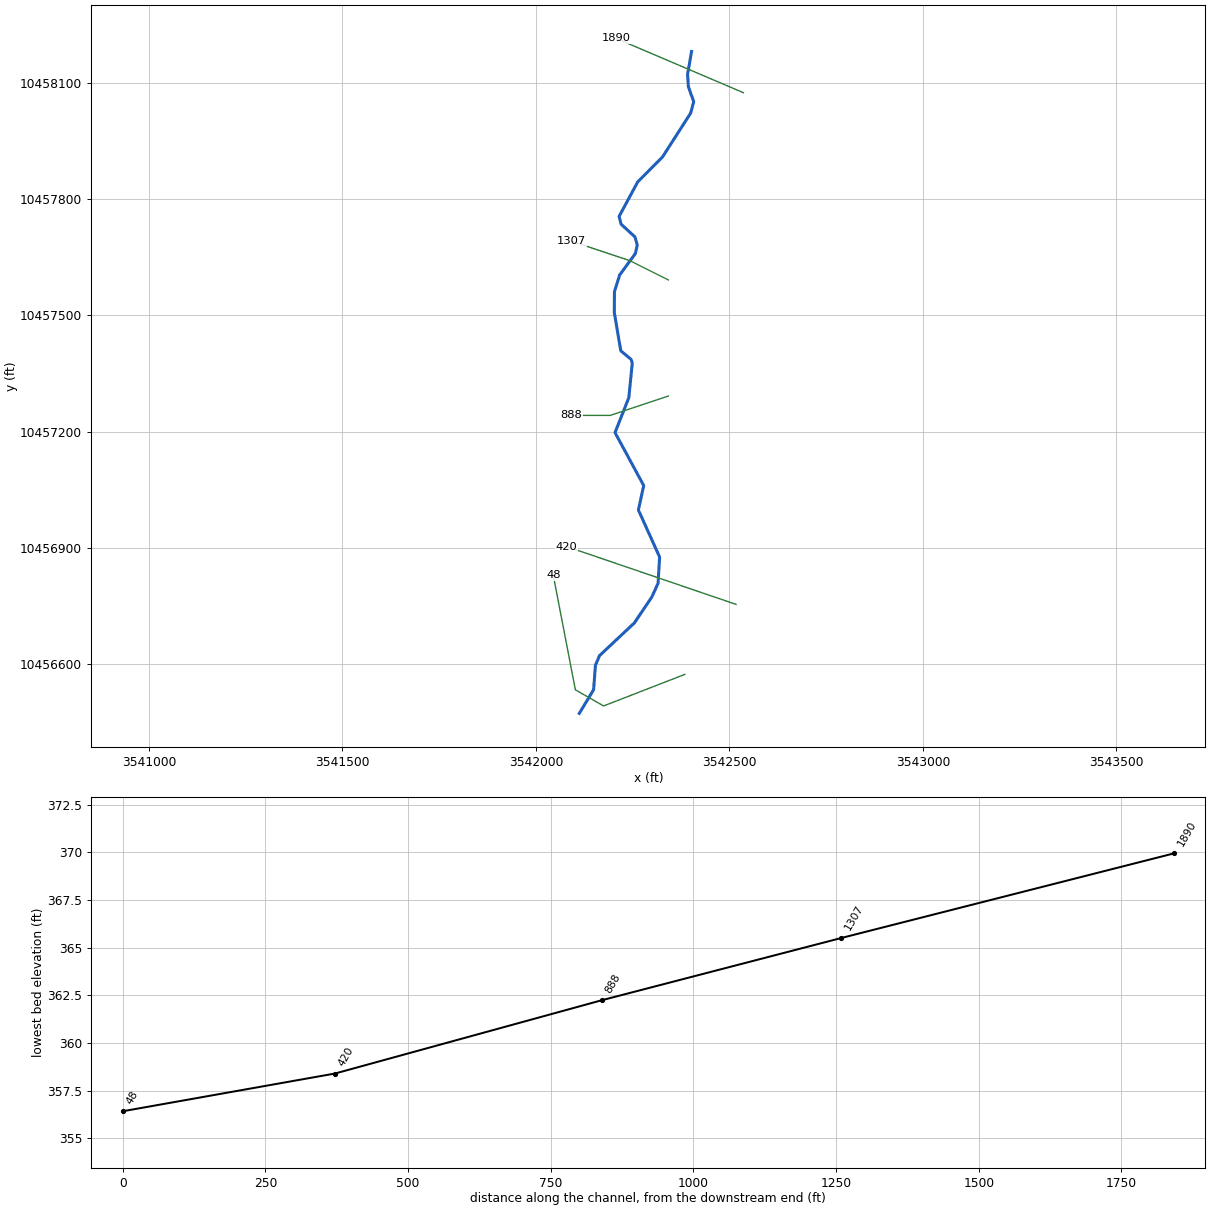
--- SANDYBRTRIB7.prj (project) ---

Proj Title=SANDY BRANCH TRIBUTARY 7
Current Plan=p01
Default Exp/Contr=0.3,0.1
English Units
Geom File=g01
Flow File=f01
Plan File=p01
Y Axis Title=Elevation
X Axis Title(PF)=Main Channel Distance
X Axis Title(XS)=Station
BEGIN DESCRIPTION:
UNT02306 IN SAND CR
END DESCRIPTION:
DSS Export Rating Curves= 0
DSS Export Rating Curve Sorted= 0
DSS Export Volume Flow Curves= 0
DXF Filename=UNT02306 IN SAND CR.
DXF OffsetX= 0
DXF OffsetY= 0
DXF ScaleX= 1
DXF ScaleY= 10

--- SANDYBRTRIB7.p01 (plan) ---

Plan Title=Multiple Run
Short Identifier=Multiple
Geom File=g01
Flow File=f01
Subcritical Flow
K Sum by GR= 0
Std Step Tol= 0.01
Critical Tol= 0.01
Num of Std Step Trials= 20
Max Error Tol= 0.3
Flow Tol Ratio= 0.001
Split Flow NTrial= 30
Split Flow Tol= 0.02
Split Flow Ratio= 0.02
Log Output Level= 0
Friction Slope Method= 1
Unsteady Friction Slope Method= 2
Unsteady Bridges Friction Slope Method= 1
Parabolic Critical Depth
Global Vel Dist=  1 , 1 , 1
Global Log Level= 0
CheckData=True
Encroach Param= -1, 0, 0, 0
BEGIN DESCRIPTION:
Multiple Run
END DESCRIPTION:

--- SANDYBRTRIB7.f01 (steady flow) ---

Flow Title=Multiple
Program Version=4.10
Number of Profiles= 7
Profile Names=10-year,25-year,50-year,1pct_min,100-year,1pct_plu,500-year
River Rch & RM=UNT02306 IN SAND,Reach-1         ,1890
     340     437     511     438     593     801     792
River Rch & RM=SANDYBRTRIB7,Reach-1         ,1890
     340     437     511     438     593     801     792
Boundary for River Rch & Prof#=SANDYBRTRIB7,Reach-1         , 1
Up Type= 0
Dn Type= 3
Dn Slope=0.005
Boundary for River Rch & Prof#=SANDYBRTRIB7,Reach-1         , 2
Up Type= 0
Dn Type= 3
Dn Slope=0.005
Boundary for River Rch & Prof#=SANDYBRTRIB7,Reach-1         , 3
Up Type= 0
Dn Type= 3
Dn Slope=0.005
Boundary for River Rch & Prof#=SANDYBRTRIB7,Reach-1         , 4
Up Type= 0
Dn Type= 3
Dn Slope=0.005
Boundary for River Rch & Prof#=SANDYBRTRIB7,Reach-1         , 5
Up Type= 0
Dn Type= 3
Dn Slope=0.005
Boundary for River Rch & Prof#=SANDYBRTRIB7,Reach-1         , 6
Up Type= 0
Dn Type= 3
Dn Slope=0.005
Boundary for River Rch & Prof#=SANDYBRTRIB7,Reach-1         , 7
Up Type= 0
Dn Type= 3
Dn Slope=0.005
DSS Import GetInterval= 0
DSS Import GetPeak= 0
DSS Import FillOption= 0

--- SANDYBRTRIB7.g01 (geometry) ---

Geom Title=Existing Conditions
Program Version=4.10

River Reach=SANDYBRTRIB7    ,Reach-1
Reach XY= 30
      3542402.24     10458181.85      3542392.01     10458123.49
      3542393.87     10458091.62      3542407.77     10458052.13
      3542399.86     10458022.71      3542327.03     10457909.25
      3542263.04     10457844.91      3542214.96     10457755.81
      3542220.11      10457735.7      3542256.13     10457702.69
      3542261.88     10457681.66      3542256.84     10457659.58
      3542216.43     10457604.59      3542202.94      10457561.2
       3542202.6     10457506.94       3542219.4      10457408.5
      3542246.11     10457386.33      3542248.97     10457376.36
      3542240.14     10457287.51      3542204.44     10457197.17
      3542278.59     10457060.27      3542264.83     10456997.21
      3542319.66     10456875.67      3542315.68     10456807.96
      3542299.78     10456772.73       3542254.4     10456705.34
      3542164.36     10456620.79      3542153.86     10456595.95
       3542149.1     10456532.89      3542112.11     10456471.64

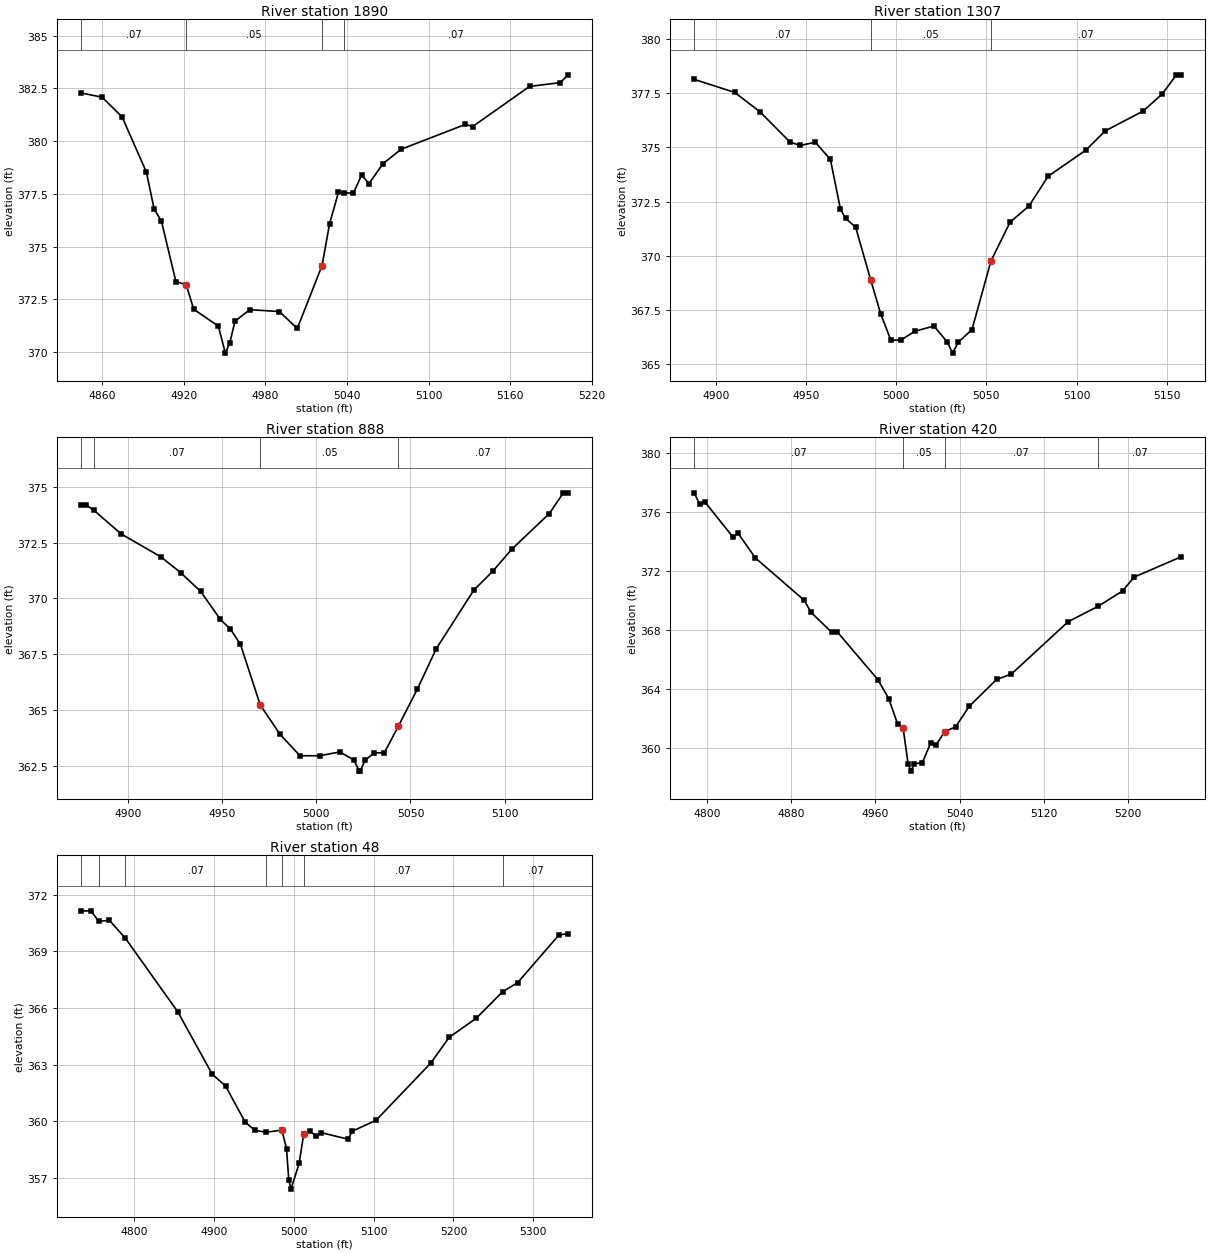
Type RM Length L Ch R = 1 ,1890    ,583,583,583
BEGIN DESCRIPTION:
UNT02306 IN SAND CR 4.0
END DESCRIPTION:
XS GIS Cut Line= 2
      3542536.17     10458075.52      3542206.76     10458215.96
#Sta/Elev= 30
  4844.5  382.28  4859.8  382.08  4874.5  381.15  4892.4  378.53  4898.1  376.78
  4903.5   376.2  4914.1  373.34  4921.7  373.19  4927.2  372.03  4945.3  371.23
  4950.5  369.95  4953.8  370.45  4957.6  371.47  4968.5  372.01  4990.2  371.92
  5003.4  371.12  5021.6   374.1  5027.1  376.07  5033.7  377.58  5037.7  377.56
  5044.6  377.52  5050.7  378.39  5056.1  377.98  5066.3  378.92  5079.7  379.61
    5127  380.79  5132.4  380.69  5174.2  382.59  5196.8  382.77  5202.6  383.14
#Mann= 4 ,-1 , 0
  4844.5     .07       0  4921.7     .05       0  5021.6     .07       0
  5037.7     .07       0
Bank Sta=4921.7,5021.6
XS Rating Curve= 0 ,0
Exp/Cntr=0.3,0.1

Type RM Length L Ch R = 1 ,1307    ,419,419,419
BEGIN DESCRIPTION:
UNT02306 IN SAND CR 3.0
END DESCRIPTION:
XS GIS Cut Line= 3
      3542342.12     10457591.63      3542242.11     10457641.64
      3542092.14     10457691.63
#Sta/Elev= 30
    4888  378.14  4910.4  377.54  4924.4  376.65  4941.1  375.25  4946.7  375.09
  4955.1  375.24  4963.5  374.45  4969.1  372.14  4971.9  371.73  4977.5  371.32
  4985.8   368.9  4991.4  367.32    4997  366.11  5002.5  366.11  5010.4  366.52
  5020.9  366.76  5028.4  366.01  5031.2  365.51  5034.4  366.01    5042   366.6
  5052.5  369.76  5063.1  371.55  5073.6   372.3  5084.2  373.67  5105.2  374.88
  5115.8  375.76  5136.9  376.68  5147.4  377.46  5155.3  378.35  5157.9  378.35
#Mann= 3 ,-1 , 0
    4888     .07       0  4985.8     .05       0  5052.5     .07       0
Bank Sta=4985.8,5052.5
XS Rating Curve= 0 ,0
Exp/Cntr=0.3,0.1

Type RM Length L Ch R = 1 ,888     ,468,468,468
BEGIN DESCRIPTION:
UNT02306 IN SAND CR 2.0
END DESCRIPTION:
XS GIS Cut Line= 3
      3542342.14     10457291.65      3542192.11     10457241.64
      3542092.06     10457241.64
#Sta/Elev= 30
  4875.4  374.18  4878.1  374.18  4882.2  373.94  4896.5  372.89  4917.6  371.86
  4928.1  371.15  4938.7  370.31  4949.2  369.05  4954.5  368.62  4959.8  367.94
  4970.3  365.22  4980.8   363.9  4991.4  362.94  5001.9  362.94  5012.5  363.11
    5020  362.75  5022.8  362.25  5023.3  362.25    5026  362.75  5030.9  363.07
  5036.1  363.07  5043.6  364.27  5053.6  365.92  5063.6  367.73  5083.6  370.37
  5093.6  371.21  5103.6  372.19  5123.6   373.8  5131.1  374.73  5133.6  374.73
#Mann= 4 ,-1 , 0
  4875.4     .07       0  4882.2     .07       0  4970.3     .05       0
  5043.6     .07       0
Bank Sta=4970.3,5043.6
XS Rating Curve= 0 ,0
Exp/Cntr=0.3,0.1

Type RM Length L Ch R = 1 ,420     ,372,372,372
BEGIN DESCRIPTION:
UNT02306 IN SAND CR 1.0
END DESCRIPTION:
XS GIS Cut Line= 2
      3542517.13     10456753.32      3542079.61     10456902.63
#Sta/Elev= 30
    4788  377.32  4793.2  376.55  4798.4  376.68  4824.5  374.34  4829.8  374.56
  4846.1  372.89  4892.4  370.02    4899  369.19  4918.5  367.84  4923.8  367.87
  4962.4  364.62  4972.9   363.3  4981.1  361.61  4986.4  361.32  4991.1   358.9
  4993.8   358.4  4997.1   358.9  5004.6  358.98  5012.5   360.3  5017.8  360.19
  5025.8  361.08  5036.3  361.42  5049.1   362.8  5075.1  364.63  5089.2     365
  5143.1  368.56  5171.4   369.6  5194.8  370.65  5205.7  371.59  5250.3  372.97
#Mann= 4 ,-1 , 0
    4788     .07       0  4986.4     .05       0  5025.8     .07       0
  5171.4     .07       0
Bank Sta=4986.4,5025.8
XS Rating Curve= 0 ,0
Exp/Cntr=0.3,0.1

Type RM Length L Ch R = 1 ,48      ,0,0,0
BEGIN DESCRIPTION:
UNT02306 IN SAND CR 1.11
END DESCRIPTION:
XS GIS Cut Line= 4
      3542384.96     10456572.42      3542174.93     10456490.84
      3542102.01      10456532.5      3542044.98     10456828.05
#Sta/Elev= 30
  4733.5  371.14  4745.7  371.13  4755.6  370.58  4768.7  370.64  4788.8  369.69
  4854.6  365.79  4897.5  362.51  4914.4  361.87  4938.9  359.97  4951.1  359.53
  4965.2  359.43    4985  359.54  4990.8  358.56  4993.6  356.92  4996.4  356.42
  5006.6  357.78  5012.4  359.35  5019.7  359.49  5028.2  359.23    5034  359.41
    5068  359.06  5073.1  359.48    5103  360.06  5171.7  363.09  5194.7  364.45
  5228.7  365.46  5261.6  366.86  5280.5  367.34  5332.4  369.87  5343.8  369.93
#Mann= 7 ,-1 , 0
  4733.5     .07       0  4755.6     .07       0  4788.8     .07       0
  4965.2     .07       0    4985     .05       0  5012.4     .07       0
  5261.6     .07       0
Bank Sta=4985,5012.4
XS Rating Curve= 0 ,0
Exp/Cntr=0.3,0.1

Chan Stop Cuts=-1
Use User Specified Reach Order=0
Composite Channel Slope=5