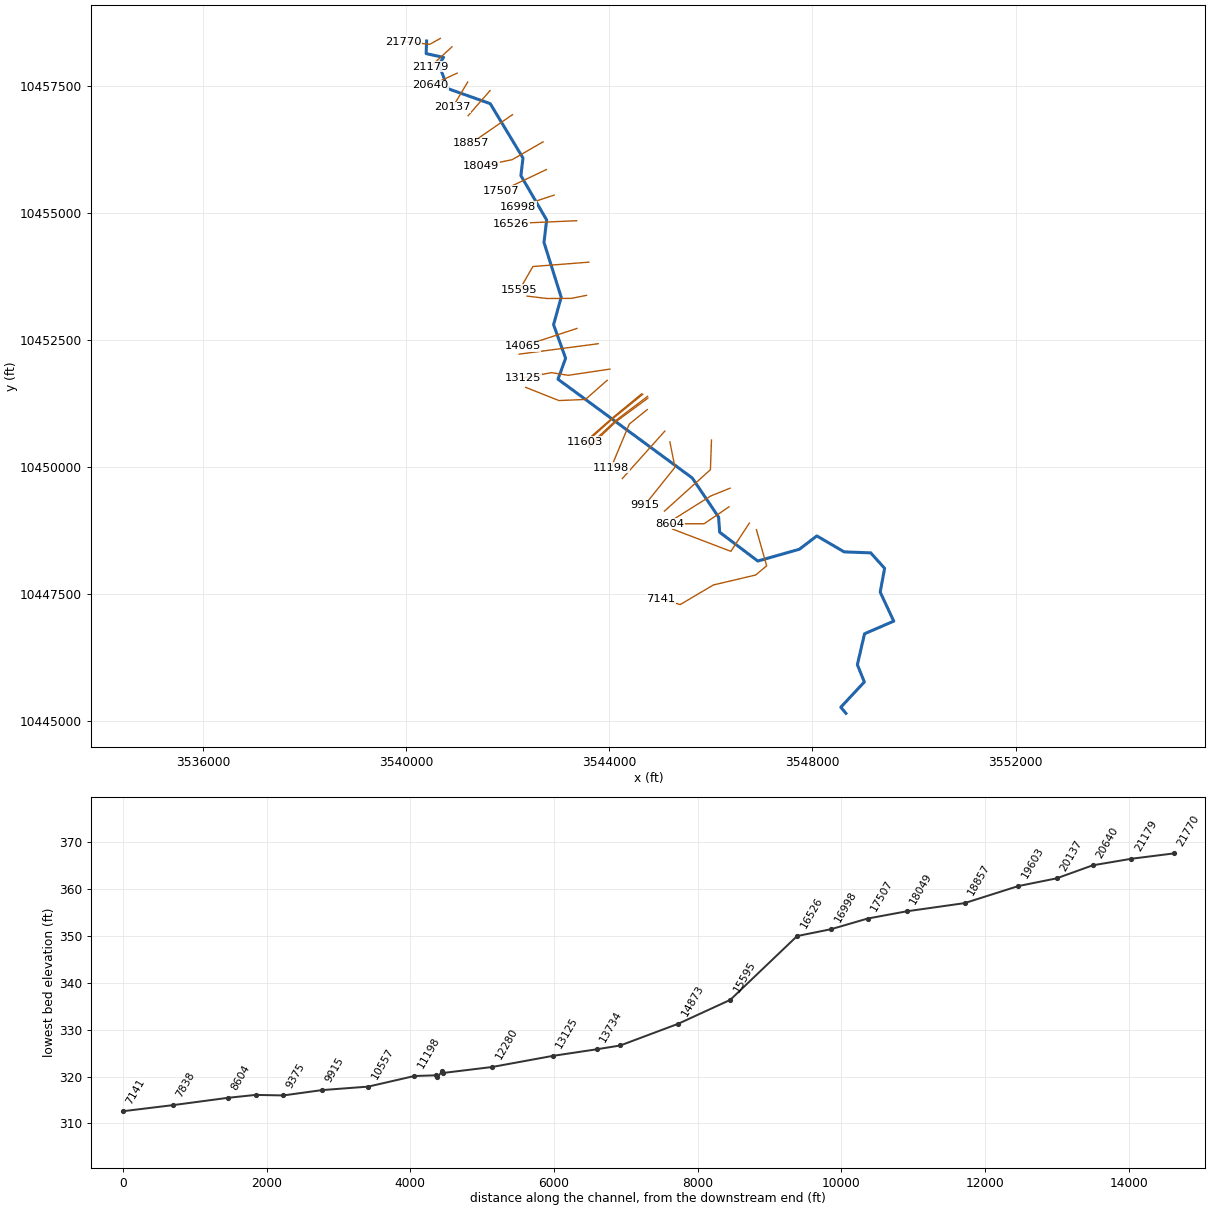
--- SANDY BRANCH.prj (project) ---

Proj Title=SANDY BRANCH Base Level Engineering
Current Plan=p01
Default Exp/Contr=0.3,0.1
English Units
Geom File=g01
Flow File=f01
Plan File=p01
BEGIN DESCRIPTION:
SANDY BRANCH
END DESCRIPTION:

--- SANDY BRANCH.p01 (plan) ---

Plan Title=Multiple Run
Short Identifier=Multiple
Geom File=g01
Flow File=f01
Subcritical Flow
K Sum by GR= 0
Std Step Tol= 0.01
Critical Tol= 0.01
Num of Std Step Trials= 20
Max Error Tol= 0.3
Flow Tol Ratio= 0.001
Split Flow NTrial= 30
Split Flow Tol= 0.02
Split Flow Ratio= 0.02
Log Output Level= 0
Friction Slope Method= 1
Unsteady Friction Slope Method= 2
Unsteady Bridges Friction Slope Method= 1
Parabolic Critical Depth
Global Vel Dist=  1 , 1 , 1
Global Log Level= 0
CheckData=True
Encroach Param= -1, 0, 0, 0
BEGIN DESCRIPTION:
Multiple Run
END DESCRIPTION:

--- SANDY BRANCH.f01 (steady flow) ---

Flow Title=Multiple
Number of Profiles=7
Profile Names=10-year,25-year,50-year,1pct_min,100-year,1pct_plu,500-year
River Rch & RM= SANDY BRANCH,Reach-1,21770
     573     759     907     792    1071    1448    1486
River Rch & RM= SANDY BRANCH,Reach-1,18049
     904    1232    1499    1332    1801    2436    2591
River Rch & RM= SANDY BRANCH,Reach-1,14065
    1483    2075    2570    2319    3136    4241    4660
River Rch & RM= SANDY BRANCH,Reach-1,11603
    1793    2532    3157    2865    3875    5240    5825
River Rch & RM= SANDY BRANCH,Reach-1,9375
    2240    3180    3977    3616    4890    6613    7380
Boundary for River Rch & Prof#=SANDY BRANCH,Reach-1,1
Up Type=0
Dn Type=3
Dn Slope=0.005
Boundary for River Rch & Prof#=SANDY BRANCH,Reach-1,2
Up Type=0
Dn Type=3
Dn Slope=0.005
Boundary for River Rch & Prof#=SANDY BRANCH,Reach-1,3
Up Type=0
Dn Type=3
Dn Slope=0.005
Boundary for River Rch & Prof#=SANDY BRANCH,Reach-1,4
Up Type=0
Dn Type=3
Dn Slope=0.005
Boundary for River Rch & Prof#=SANDY BRANCH,Reach-1,5
Up Type=0
Dn Type=3
Dn Slope=0.005
Boundary for River Rch & Prof#=SANDY BRANCH,Reach-1,6
Up Type=0
Dn Type=3
Dn Slope=0.005
Boundary for River Rch & Prof#=SANDY BRANCH,Reach-1,7
Up Type=0
Dn Type=3
Dn Slope=0.005

--- SANDY BRANCH.g01 (geometry) ---

Geom Title=Existing Conditions

River Reach=SANDY BRANCH,Reach-1
Reach XY= 30
      3540402.32     10458391.01      3540392.96     10458142.12
      3540736.29     10458068.41      3540644.28     10457926.52
      3540822.54     10457451.44      3541654.76     10457156.72
      3542299.93     10456085.84      3542258.50     10455737.93
      3542765.68     10454865.34      3542713.38     10454422.13
      3543052.10     10453342.51      3542902.11     10452801.64
      3543139.06     10452139.86      3542989.06     10451727.36
      3545632.11     10449781.64      3546150.78     10449010.91
      3546172.71     10448711.78      3546923.38     10448144.60
      3547741.12     10448376.39      3548085.71     10448639.43
      3548623.46     10448324.89      3549146.65     10448305.54
      3549420.11     10448001.02      3549333.19     10447532.00
      3549599.96     10446960.43      3549024.26     10446710.92
      3548883.92     10446102.07      3549020.89     10445761.70
      3548557.28     10445263.89      3548659.00     10445142.94

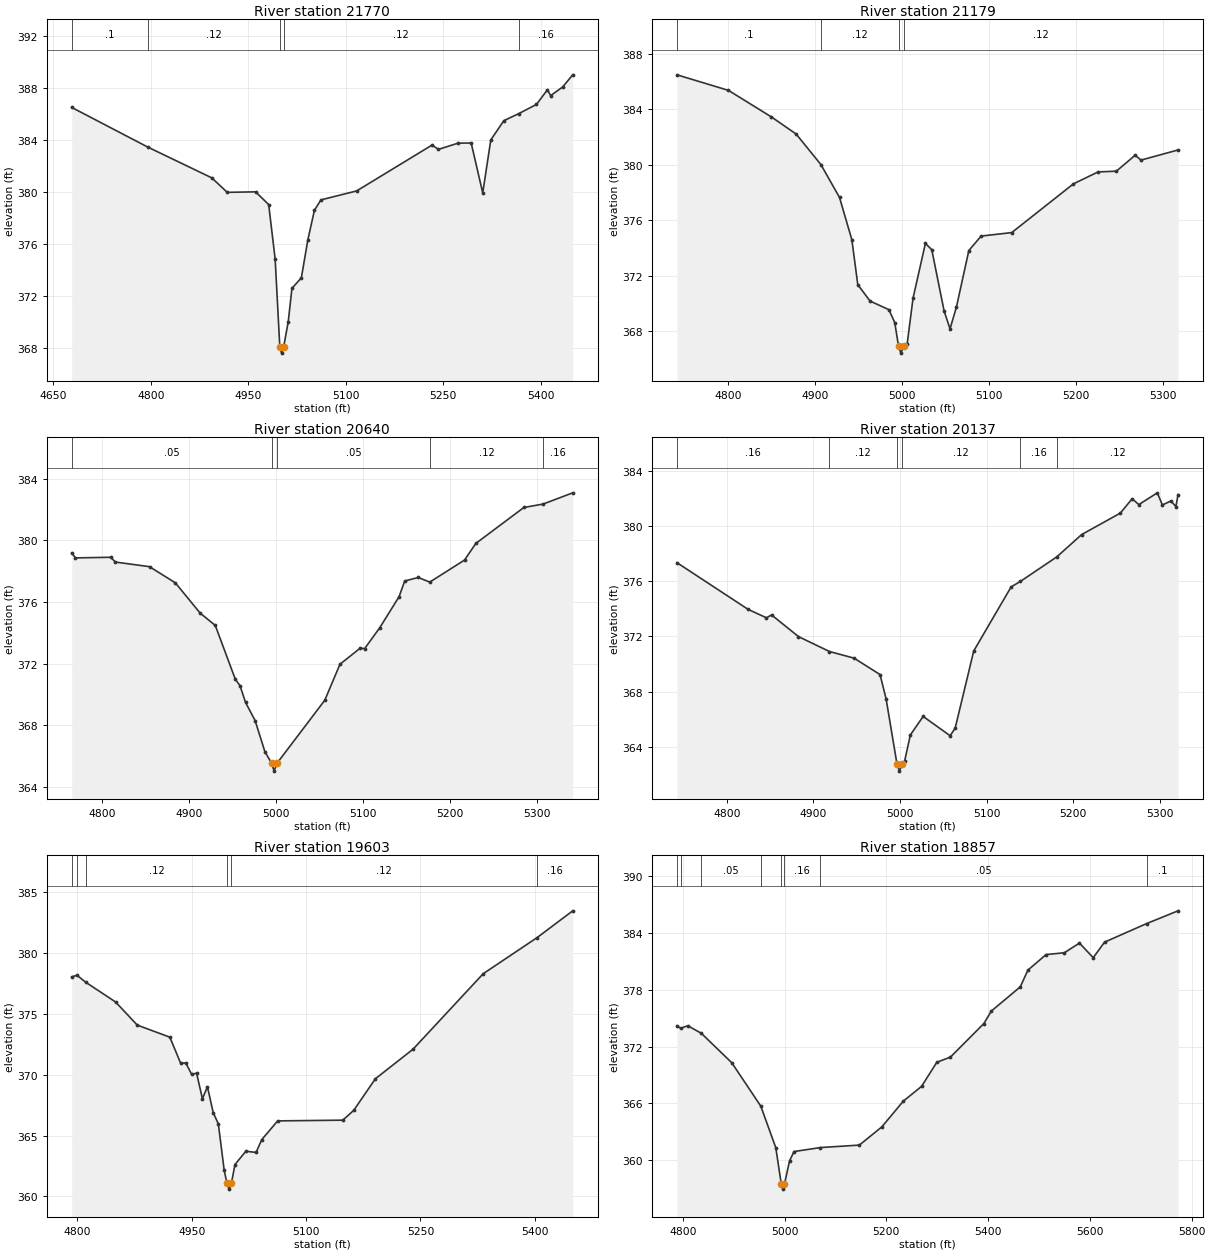
Type RM Length L Ch R = 1,21770,591,591,591
BEGIN DESCRIPTION:
SANDY BRANCH 34.0
END DESCRIPTION:
XS GIS Cut Line= 3
      3540673.88     10458443.40      3540467.76     10458326.24
      3539936.62     10458380.44
#Sta/Elev= 30
  4678.4  386.49  4795.7  383.43  4893.8  381.07  4917.8  379.95  4961.4  379.99
  4981.5  379.01  4991.5  374.79  4998.6  368.07  5001.3  367.57  5004.6  368.07
  5011.6  369.99  5017.3  372.56  5031.8  373.37  5041.8  376.30  5051.9  378.57
  5061.9  379.37  5116.9  380.06  5232.8  383.59  5242.8  383.26  5273.0  383.74
  5293.1  383.75  5310.9  379.91  5323.3  383.99  5343.4  385.47  5366.2  386.01
  5393.6  386.72  5410.4  387.85  5415.4  387.40  5433.8  388.06  5449.4  389.00
#Mann=5,-1,0
  4678.4     0.1       0  4795.7    0.12       0  4998.6    0.07       0
  5004.6    0.12       0  5366.2    0.16       0
Bank Sta=4998.6,5004.6
Exp/Cntr=0.3,0.1

Type RM Length L Ch R = 1,21179,539,539,539
BEGIN DESCRIPTION:
SANDY BRANCH 33.0
END DESCRIPTION:
XS GIS Cut Line= 2
      3540901.58     10458275.73      3540477.95     10457885.89
#Sta/Elev= 30
  4741.5  386.47  4800.6  385.35  4849.9  383.44  4878.3  382.21  4906.8  380.01
  4928.2  377.64  4942.4  374.59  4949.2  371.36  4963.3  370.18  4984.9  369.56
  4991.7  368.63  4996.0  366.93  4998.7  366.43  5002.0  366.93  5005.9  367.07
  5012.7  370.39  5026.9  374.33  5034.2  373.88  5048.4  369.46  5055.2  368.18
  5062.6  369.76  5076.8  373.82  5091.0  374.86  5126.1  375.11  5197.0  378.62
  5225.4  379.48  5246.3  379.53  5267.9  380.68  5274.7  380.33  5317.2  381.06
#Mann=4,-1,0
  4741.5     0.1       0  4906.8    0.12       0  4996.0    0.07       0
  5002.0    0.12       0
Bank Sta=4996,5002
Exp/Cntr=0.3,0.1

Type RM Length L Ch R = 1,20640,503,503,503
BEGIN DESCRIPTION:
SANDY BRANCH 32.0
END DESCRIPTION:
XS GIS Cut Line= 2
      3541003.13     10457757.49      3540481.19     10457516.00
#Sta/Elev= 30
  4765.5  379.18  4769.8  378.86  4810.2  378.90  4815.7  378.59  4854.8  378.29
  4884.5  377.24  4912.9  375.28  4930.3  374.48  4953.2  371.00  4958.7  370.57
  4965.0  369.49  4976.0  368.31  4987.2  366.30  4995.0  365.53  4997.8  365.03
  5001.0  365.53  5056.0  369.63  5073.4  371.96  5096.3  372.99  5101.8  372.98
  5119.2  374.34  5141.3  376.35  5147.7  377.36  5163.3  377.59  5176.5  377.29
  5216.4  378.72  5229.4  379.80  5284.5  382.13  5306.5  382.35  5340.6  383.08
#Mann=5,-1,0
  4765.5    0.05       0  4995.0    0.03       0  5001.0    0.05       0
  5176.5    0.12       0  5306.5    0.16       0
Bank Sta=4995,5001
Exp/Cntr=0.3,0.1

Type RM Length L Ch R = 1,20137,534,534,534
BEGIN DESCRIPTION:
SANDY BRANCH 30.0
END DESCRIPTION:
XS GIS Cut Line= 2
      3541211.48     10457583.03      3540914.89     10457086.11
#Sta/Elev= 30
  4742.4  377.34  4824.3  373.97  4845.7  373.35  4851.6  373.56  4882.7  371.99
  4918.5  370.91  4946.9  370.43  4976.9  369.24  4983.9  367.48  4996.5  362.75
  4999.2  362.25  5002.5  362.75  5005.3  362.98  5011.9  364.87  5026.7  366.21
  5057.9  364.81  5063.7  365.37  5085.1  370.95  5128.3  375.59  5139.1  375.99
  5181.0  377.76  5209.8  379.38  5254.4  380.93  5268.1  381.97  5275.8  381.55
  5297.2  382.40  5303.0  381.52  5312.8  381.81  5318.6  381.41  5321.1  382.27
#Mann=6,-1,0
  4742.4    0.16       0  4918.5    0.12       0  4996.5    0.07       0
  5002.5    0.12       0  5139.1    0.16       0  5181.0    0.12       0
Bank Sta=4996.5,5002.5
Exp/Cntr=0.3,0.1

Type RM Length L Ch R = 1,19603,746,746,746
BEGIN DESCRIPTION:
SANDY BRANCH 29.0
END DESCRIPTION:
XS GIS Cut Line= 2
      3541651.59     10457413.76      3541219.25     10456918.92
#Sta/Elev= 30
  4792.6  378.02  4799.5  378.15  4811.2  377.57  4850.1  375.96  4878.6  374.06
  4921.3  373.07  4935.5  370.93  4942.2  370.96  4949.8  370.03  4956.4  370.11
  4964.0  368.02  4970.6  369.00  4978.2  366.87  4984.9  365.96  4992.5  362.18
  4996.1  361.10  4998.9  360.60  5002.1  361.10  5006.7  362.62  5021.0  363.71
  5034.4  363.61  5041.8  364.66  5062.7  366.20  5148.1  366.26  5162.4  367.06
  5190.9  369.66  5240.2  372.08  5332.3  378.28  5402.9  381.24  5449.7  383.44
#Mann=6,-1,0
  4792.6    0.05       0  4799.5    0.16       0  4811.2    0.12       0
  4996.1    0.07       0  5002.1    0.12       0  5402.9    0.16       0
Bank Sta=4996.1,5002.1
Exp/Cntr=0.3,0.1

Type RM Length L Ch R = 1,18857,808,808,808
BEGIN DESCRIPTION:
SANDY BRANCH 28.0
END DESCRIPTION:
XS GIS Cut Line= 2
      3542093.21     10456939.44      3541283.31     10456379.53
#Sta/Elev= 30
  4788.7  374.18  4796.1  373.92  4809.7  374.19  4836.3  373.40  4896.3  370.29
  4953.3  365.72  4982.8  361.33  4993.7  357.47  4996.5  356.97  4999.7  357.47
  5009.8  359.94  5018.6  360.93  5070.3  361.35  5147.0  361.61  5191.2  363.53
  5233.5  366.25  5269.3  367.80  5299.1  370.33  5326.1  370.89  5391.7  374.42
  5406.5  375.74  5463.3  378.29  5478.2  380.05  5514.0  381.69  5549.8  381.88
  5579.6  382.90  5606.6  381.36  5628.9  383.00  5711.3  384.95  5773.3  386.30
#Mann=8,-1,0
  4788.7    0.05       0  4796.1    0.16       0  4836.3    0.05       0
  4953.3    0.16       0  4993.7    0.07       0  4999.7    0.16       0
  5070.3    0.05       0  5711.3     0.1       0
Bank Sta=4993.7,4999.7
Exp/Cntr=0.3,0.1

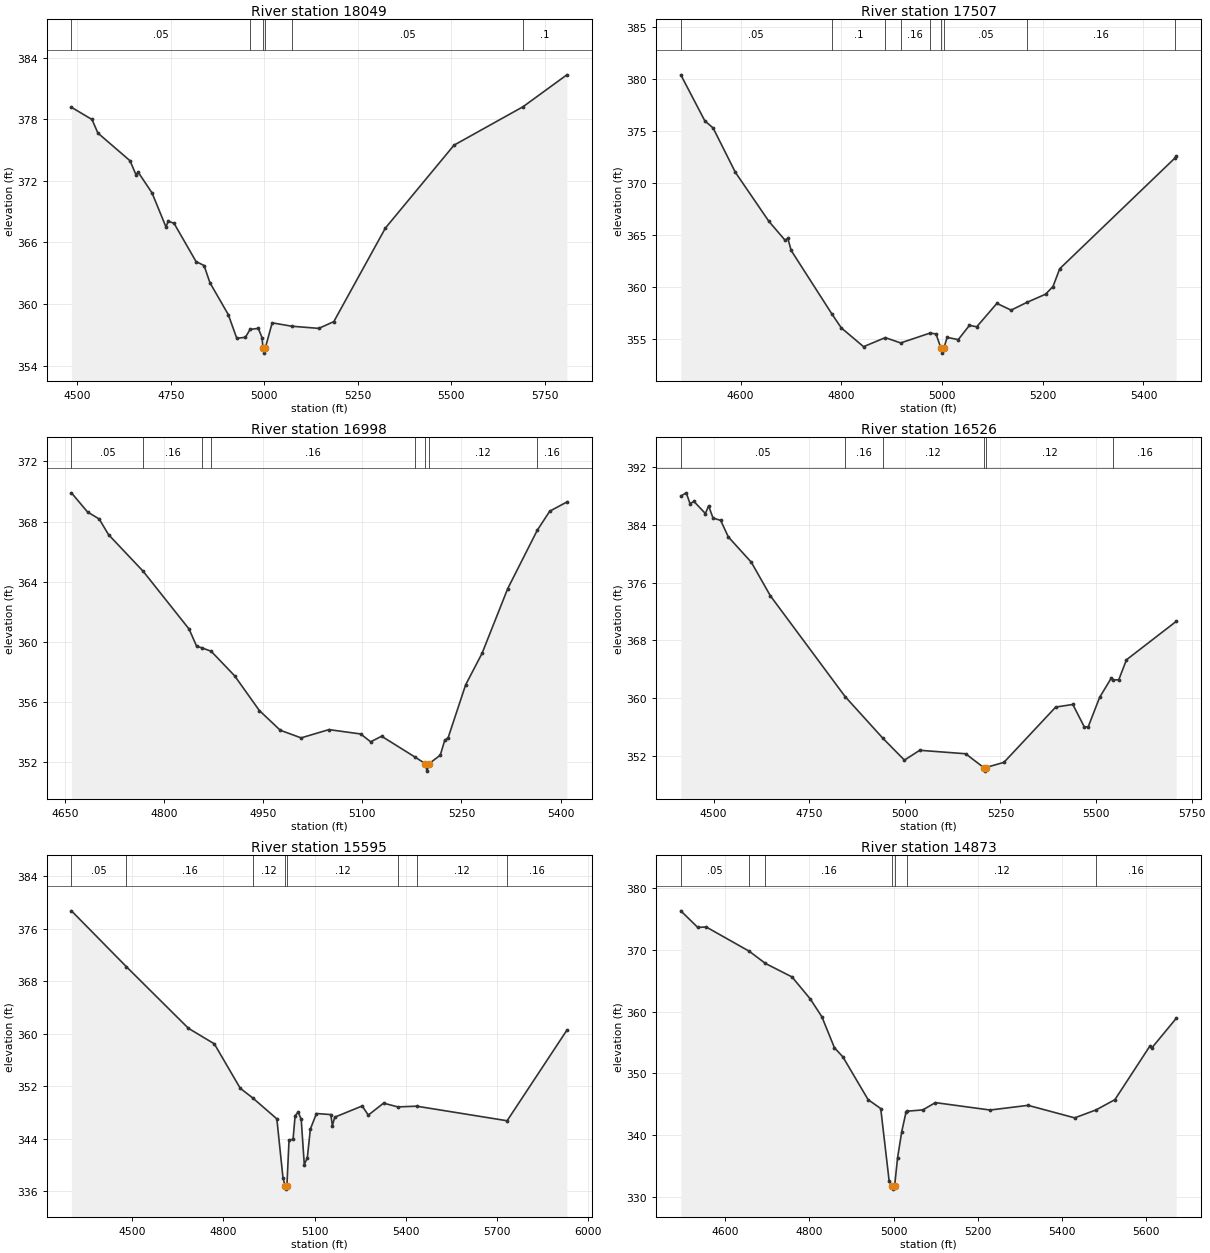
Type RM Length L Ch R = 1,18049,542,542,542
BEGIN DESCRIPTION:
SANDY BRANCH 27.0
END DESCRIPTION:
XS GIS Cut Line= 3
      3542695.02     10456404.00      3542087.34     10456052.42
      3541476.48     10455926.78
#Sta/Elev= 30
  4483.9  379.16  4538.9  377.97  4554.7  376.65  4640.8  373.95  4656.6  372.59
  4662.3  372.85  4699.6  370.82  4736.9  367.50  4742.7  368.07  4758.5  367.86
  4817.3  364.14  4838.8  363.75  4854.6  362.07  4903.5  358.98  4926.3  356.67
  4949.4  356.76  4961.9  357.53  4984.0  357.63  4993.8  356.74  4996.6  355.72
  4999.3  355.22  5002.6  355.72  5021.1  358.17  5073.5  357.84  5145.8  357.63
  5186.0  358.29  5324.0  367.40  5507.6  375.47  5692.6  379.22  5809.6  382.32
#Mann=6,-1,0
  4483.9    0.05       0  4961.9    0.12       0  4996.6    0.07       0
  5002.6    0.12       0  5073.5    0.05       0  5692.6     0.1       0
Bank Sta=4996.6,5002.6
Exp/Cntr=0.3,0.1

Type RM Length L Ch R = 1,17507,509,509,509
BEGIN DESCRIPTION:
SANDY BRANCH 26.0
END DESCRIPTION:
XS GIS Cut Line= 2
      3542760.11     10455857.12      3541870.93     10455436.38
#Sta/Elev= 30
  4481.4  380.42  4529.1  376.00  4545.6  375.31  4589.8  371.05  4656.2  366.35
  4688.4  364.53  4693.9  364.71  4700.5  363.55  4780.9  357.48  4800.0  356.11
  4844.3  354.30  4887.4  355.17  4917.9  354.66  4975.9  355.60  4988.1  355.53
  4997.8  354.18  5000.5  353.68  5003.8  354.18  5010.2  355.19  5032.3  354.98
  5054.5  356.35  5069.0  356.21  5109.0  358.46  5137.3  357.81  5168.3  358.55
  5205.6  359.34  5220.4  360.08  5233.8  361.79  5461.8  372.39  5465.1  372.60
#Mann=9,-1,0
  4481.4    0.05       0  4780.9     0.1       0  4887.4    0.12       0
  4917.9    0.16       0  4975.9    0.05       0  4997.8   0.035       0
  5003.8    0.05       0  5168.3    0.16       0  5461.8    0.05       0
Bank Sta=4997.8,5003.8
Exp/Cntr=0.3,0.1

Type RM Length L Ch R = 1,16998,472,472,472
BEGIN DESCRIPTION:
SANDY BRANCH 25.0
END DESCRIPTION:
XS GIS Cut Line= 2
      3542912.03     10455353.65      3542200.23     10455119.27
#Sta/Elev= 30
  4660.0  369.91  4684.3  368.64  4702.0  368.17  4716.1  367.13  4768.6  364.69
  4838.0  360.85  4849.4  359.71  4857.0  359.61  4871.3  359.38  4906.8  357.75
  4944.2  355.44  4975.8  354.13  5007.4  353.62  5049.5  354.17  5097.5  353.88
  5112.6  353.36  5129.2  353.73  5179.5  352.35  5195.1  351.91  5197.8  351.41
  5201.1  351.91  5217.9  352.47  5224.6  353.45  5229.8  353.63  5256.3  357.15
  5281.1  359.24  5319.9  363.54  5364.6  367.42  5383.5  368.69  5409.4  369.30
#Mann=8,-1,0
  4660.0    0.05       0  4768.6    0.16       0  4857.0    0.05       0
  4871.3    0.16       0  5179.5    0.12       0  5195.1    0.07       0
  5201.1    0.12       0  5364.6    0.16       0
Bank Sta=5195.1,5201.1
Exp/Cntr=0.3,0.1

Type RM Length L Ch R = 1,16526,931,931,931
BEGIN DESCRIPTION:
SANDY BRANCH 23.0
END DESCRIPTION:
XS GIS Cut Line= 2
      3543356.32     10454850.01      3542061.99     10454792.71
#Sta/Elev= 30
  4414.1  387.95  4428.3  388.40  4438.3  386.90  4448.3  387.22  4478.4  385.54
  4486.8  386.60  4498.4  384.92  4518.4  384.59  4538.4  382.31  4598.5  378.81
  4648.5  374.16  4843.8  360.25  4942.6  354.49  4998.9  351.47  5038.9  352.83
  5159.0  352.35  5206.1  350.45  5208.8  349.95  5212.1  350.45  5259.1  351.16
  5394.5  358.80  5439.3  359.16  5469.3  356.06  5479.4  356.06  5509.4  360.14
  5539.4  362.77  5545.6  362.55  5559.4  362.57  5579.5  365.33  5709.7  370.64
#Mann=6,-1,0
  4414.1    0.05       0  4843.8    0.16       0  4942.6    0.12       0
  5206.1    0.07       0  5212.1    0.12       0  5545.6    0.16       0
Bank Sta=5206.1,5212.1
Exp/Cntr=0.3,0.1

Type RM Length L Ch R = 1,15595,722,722,722
BEGIN DESCRIPTION:
SANDY BRANCH 22.0
END DESCRIPTION:
XS GIS Cut Line= 3
      3543595.86     10454033.20      3542494.27     10453947.26
      3542232.73     10453491.97
#Sta/Elev= 30
  4300.2  378.75  4480.9  370.24  4685.1  360.85  4770.3  358.48  4855.6  351.71
  4897.1  350.22  4976.0  347.05  4996.1  338.10  5003.1  336.84  5005.8  336.34
  5009.1  336.84  5016.1  343.83  5029.3  343.92  5036.2  347.54  5046.2  348.07
  5056.2  346.98  5066.3  340.07  5076.3  341.13  5086.3  345.50  5106.4  347.86
  5153.7  347.70  5158.7  346.01  5166.6  347.31  5256.8  349.01  5276.9  347.62
  5327.1  349.44  5374.2  348.87  5435.9  348.98  5733.6  346.76  5930.2  360.56
#Mann=8,-1,0
  4300.2    0.05       0  4480.9    0.16       0  4897.1    0.12       0
  5003.1    0.07       0  5009.1    0.12       0  5374.2    0.16       0
  5435.9    0.12       0  5733.6    0.16       0
Bank Sta=5003.1,5009.1
Exp/Cntr=0.3,0.1

Type RM Length L Ch R = 1,14873,808,808,808
BEGIN DESCRIPTION:
SANDY BRANCH 21.0
END DESCRIPTION:
XS GIS Cut Line= 4
      3543551.54     10453379.55      3543249.48     10453319.66
      3542775.52     10453317.05      3542382.41     10453363.90
#Sta/Elev= 30
  4494.1  376.33  4534.3  373.65  4554.7  373.71  4656.9  369.78  4695.3  367.81
  4758.6  365.62  4802.0  362.05  4829.4  359.18  4859.4  354.15  4879.4  352.68
  4939.4  345.75  4969.4  344.31  4989.4  332.59  4996.4  331.76  4999.2  331.26
  5002.4  331.76  5009.4  336.30  5019.4  340.59  5029.4  343.68  5032.4  343.88
  5069.4  344.09  5099.4  345.27  5229.4  344.07  5319.7  344.83  5430.5  342.80
  5481.3  344.09  5526.1  345.75  5608.7  354.37  5613.7  354.12  5671.9  358.92
#Mann=7,-1,0
  4494.1    0.05       0  4656.9     0.1       0  4695.3    0.16       0
  4996.4    0.07       0  5002.4    0.16       0  5032.4    0.12       0
  5481.3    0.16       0
Bank Sta=4996.4,5002.4
Exp/Cntr=0.3,0.1

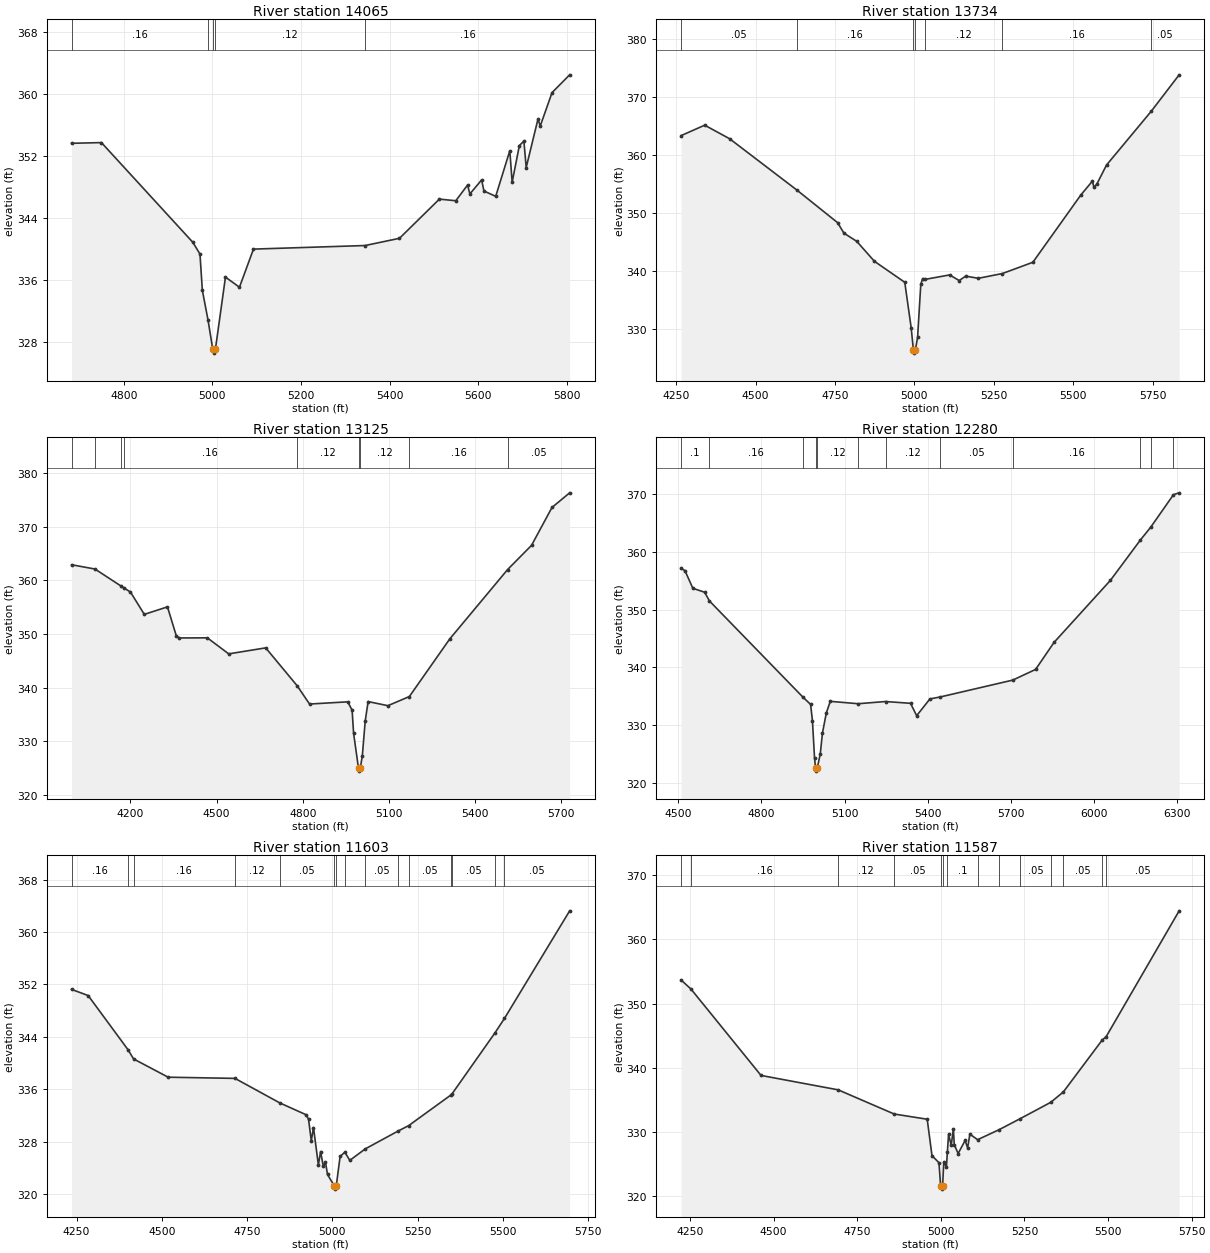
Type RM Length L Ch R = 1,14065,331,331,331
BEGIN DESCRIPTION:
SANDY BRANCH 20.0
END DESCRIPTION:
XS GIS Cut Line= 2
      3543362.01     10452727.42      3542294.30     10452375.86
#Sta/Elev= 30
  4682.1  353.65  4749.5  353.74  4955.7  340.90  4971.9  339.38  4977.2  334.72
  4990.1  330.87  5000.7  327.12  5003.5  326.62  5006.7  327.12  5029.4  336.41
  5061.0  335.11  5092.6  340.02  5344.5  340.48  5422.1  341.41  5512.2  346.46
  5549.2  346.25  5575.8  348.27  5581.0  347.13  5607.5  348.93  5612.8  347.50
  5639.3  346.82  5671.1  352.69  5676.4  348.64  5692.7  353.36  5702.9  353.93
  5708.1  350.53  5734.6  356.75  5739.9  355.89  5766.4  360.18  5806.2  362.47
#Mann=5,-1,0
  4682.1    0.16       0  4990.1    0.12       0  5000.7    0.07       0
  5006.7    0.12       0  5344.5    0.16       0
Bank Sta=5000.7,5006.7
Exp/Cntr=0.3,0.1

Type RM Length L Ch R = 1,13734,609,609,609
BEGIN DESCRIPTION:
SANDY BRANCH 19.0
END DESCRIPTION:
XS GIS Cut Line= 2
      3543780.77     10452426.43      3542225.29     10452220.94
#Sta/Elev= 30
  4264.9  363.29  4339.4  365.09  4418.0  362.75  4629.5  353.92  4757.8  348.30
  4778.0  346.48  4818.3  345.07  4874.0  341.63  4969.6  338.01  4989.8  330.18
  4996.9  326.30  4999.6  325.80  5002.9  326.30  5010.0  328.53  5020.1  337.66
  5026.0  338.65  5033.6  338.51  5110.9  339.28  5141.1  338.31  5161.3  339.07
  5201.6  338.70  5277.1  339.52  5373.1  341.46  5524.4  353.07  5560.5  355.44
  5565.6  354.37  5574.9  354.97  5605.1  358.22  5745.9  367.48  5833.9  373.77
#Mann=7,-1,0
  4264.9    0.05       0  4629.5    0.16       0  4996.9    0.07       0
  5002.9    0.16       0  5033.6    0.12       0  5277.1    0.16       0
  5745.9    0.05       0
Bank Sta=4996.9,5002.9
Exp/Cntr=0.3,0.1

Type RM Length L Ch R = 1,13125,845,845,845
BEGIN DESCRIPTION:
SANDY BRANCH 18.0
END DESCRIPTION:
XS GIS Cut Line= 4
      3544012.48     10451926.42      3543189.58     10451804.03
      3542861.46     10451856.11      3542301.58     10451754.56
#Sta/Elev= 30
  3995.5  362.91  4077.0  362.11  4166.6  358.97  4176.2  358.64  4200.5  357.81
  4248.6  353.65  4329.2  355.05  4359.8  349.67  4370.0  349.25  4467.9  349.27
  4542.3  346.28  4671.0  347.40  4780.3  340.34  4823.6  336.92  4956.5  337.33
  4971.7  335.77  4976.8  331.48  4994.0  324.90  4996.8  324.40  5000.0  324.90
  5007.2  327.25  5017.3  333.76  5027.4  337.38  5096.2  336.61  5170.9  338.32
  5311.5  349.07  5512.7  362.01  5596.0  366.53  5667.2  373.60  5728.7  376.33
#Mann=9,-1,0
  3995.5     0.1       0  4077.0    0.05       0  4166.6     0.1       0
  4176.2    0.16       0  4780.3    0.12       0  4994.0    0.07       0
  5000.0    0.12       0  5170.9    0.16       0  5512.7    0.05       0
Bank Sta=4994,5000
Exp/Cntr=0.3,0.1

Type RM Length L Ch R = 1,12280,677,677,677
BEGIN DESCRIPTION:
SANDY BRANCH 17.0
END DESCRIPTION:
XS GIS Cut Line= 4
      3543958.06     10451705.71      3543528.38     10451328.11
      3543007.55     10451306.41      3542352.38     10451566.74
#Sta/Elev= 30
  4509.6  357.15  4523.8  356.73  4552.2  353.68  4594.9  353.00  4611.9  351.50
  4949.0  334.87  4977.3  333.58  4984.0  330.74  4991.5  324.34  4995.2  322.53
  4998.0  322.03  5001.2  322.53  5012.4  325.06  5020.0  328.59  5034.2  332.13
  5048.5  334.11  5149.1  333.70  5247.8  334.08  5338.1  333.77  5360.2  331.63
  5408.2  334.53  5445.4  334.87  5707.3  337.79  5789.7  339.64  5856.3  344.32
  6059.6  355.05  6168.1  362.05  6205.4  364.27  6287.4  369.89  6307.9  370.21
#Mann=12,-1,0
  4509.6     0.1       0  4611.9    0.16       0  4949.0    0.12       0
  4995.2    0.07       0  5001.2    0.12       0  5149.1    0.05       0
  5247.8    0.12       0  5445.4    0.05       0  5707.3    0.16       0
  6168.1    0.05       0  6205.4    0.16       0  6287.4    0.05       0
Bank Sta=4995.2,5001.2
Exp/Cntr=0.3,0.1

Type RM Length L Ch R = 1,11603,16,16,16
BEGIN DESCRIPTION:
SANDY BRANCH 16.03
END DESCRIPTION:
XS GIS Cut Line= 3
      3544634.70     10451437.59      3544054.40     10450959.00
      3543521.62     10450492.41
#Sta/Elev= 30
  4235.3  351.25  4284.0  350.31  4401.0  342.03  4417.1  340.64  4518.5  337.85
  4714.4  337.67  4845.7  333.93  4923.8  332.10  4930.2  331.40  4938.1  328.15
  4944.6  330.16  4958.9  324.47  4965.4  326.50  4973.3  324.26  4979.7  324.90
  4985.7  323.01  5005.4  321.27  5008.1  320.77  5011.4  321.27  5022.6  325.75
  5036.5  326.41  5051.1  325.16  5096.4  326.91  5192.5  329.63  5223.3  330.45
  5348.5  335.17  5350.3  335.27  5477.3  344.66  5504.5  346.82  5695.7  363.24
#Mann=15,-1,0
  4235.3    0.16       0  4401.0    0.12       0  4417.1    0.16       0
  4714.4    0.12       0  4845.7    0.05       0  5005.4    0.04       0
  5011.4    0.05       0  5036.5     0.1       0  5096.4    0.05       0
  5192.5     0.1       0  5223.3    0.05       0  5348.5     0.1       0
  5350.3    0.05       0  5477.3     0.1       0  5504.5    0.05       0
Bank Sta=5005.4,5011.4
Exp/Cntr=0.3,0.1

Type RM Length L Ch R = 1,11587,68,68,68
BEGIN DESCRIPTION:
SANDY BRANCH 16.01
END DESCRIPTION:
XS GIS Cut Line= 3
      3544658.99     10451430.64      3544023.58     10450913.28
      3543524.31     10450466.02
#Sta/Elev= 30
  4223.0  353.67  4252.8  352.25  4462.2  338.82  4692.9  336.58  4860.5  332.82
  4959.2  332.01  4973.5  326.34  4994.4  325.25  4999.3  321.64  5002.0  321.14
  5005.3  321.64  5008.7  325.36  5016.6  324.57  5019.6  326.93  5023.1  329.68
  5031.0  327.97  5037.5  330.50  5040.1  328.07  5051.7  326.67  5072.6  328.72
  5080.1  327.55  5086.8  329.69  5110.0  328.83  5174.8  330.40  5238.1  332.12
  5328.7  334.64  5366.3  336.25  5482.5  344.32  5494.4  344.85  5712.7  364.42
#Mann=14,-1,0
  4223.0    0.05       0  4252.8    0.16       0  4692.9    0.12       0
  4860.5    0.05       0  4999.3    0.04       0  5005.3    0.05       0
  5019.6     0.1       0  5110.0    0.05       0  5174.8     0.1       0
  5238.1    0.05       0  5328.7     0.1       0  5366.3    0.05       0
  5482.5     0.1       0  5494.4    0.05       0
Bank Sta=4999.3,5005.3
Exp/Cntr=0.3,0.1

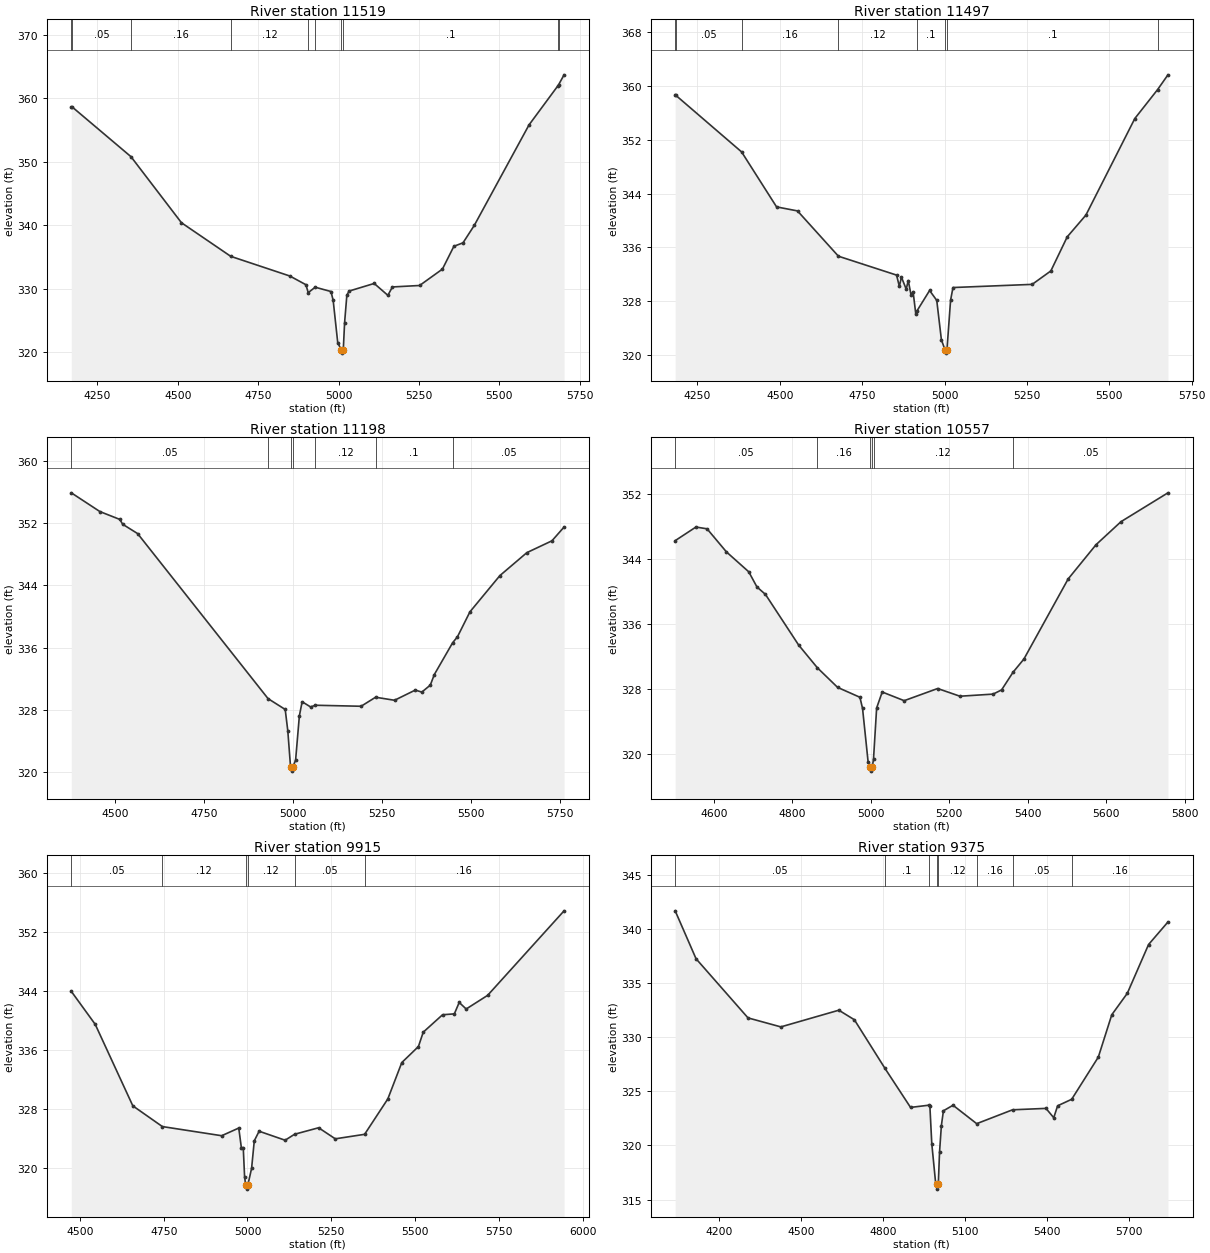
Type RM Length L Ch R = 1,11519,22,22,22
BEGIN DESCRIPTION:
SANDY BRANCH 16.0
END DESCRIPTION:
XS GIS Cut Line= 3
      3544754.70     10451389.98      3544129.69     10450916.01
      3543583.37     10450406.12
#Sta/Elev= 30
  4169.2  358.55  4172.6  358.57  4354.7  350.77  4511.6  340.37  4664.8  335.08
  4848.6  331.98  4898.5  330.61  4905.6  329.36  4927.2  330.22  4976.4  329.54
  4983.2  328.14  4997.4  321.48  5008.6  320.34  5011.3  319.84  5014.6  320.34
  5018.7  324.63  5025.7  328.96  5032.6  329.61  5110.7  330.81  5153.2  328.94
  5167.4  330.26  5251.9  330.49  5322.8  333.07  5358.4  336.66  5386.8  337.21
  5421.9  339.96  5591.9  355.77  5681.4  361.91  5684.0  362.11  5700.9  363.66
#Mann=10,-1,0
  4169.2     0.1       0  4172.6    0.05       0  4354.7    0.16       0
  4664.8    0.12       0  4905.6    0.05       0  4927.2     0.1       0
  5008.6    0.07       0  5014.6     0.1       0  5681.4    0.05       0
  5684.0     0.1       0
Bank Sta=5008.6,5014.6
Exp/Cntr=0.3,0.1

Type RM Length L Ch R = 1,11497,299,299,299
BEGIN DESCRIPTION:
SANDY BRANCH 16.02
END DESCRIPTION:
XS GIS Cut Line= 3
      3544759.70     10451354.26      3544136.43     10450894.18
      3543612.12     10450399.39
#Sta/Elev= 30
  4182.4  358.70  4183.9  358.64  4384.0  350.20  4490.1  342.02  4553.7  341.42
  4677.9  334.68  4854.4  331.87  4862.8  330.18  4869.0  331.58  4883.6  329.78
  4889.8  331.06  4898.3  328.92  4904.5  329.41  4912.7  326.08  4916.6  326.57
  4954.6  329.58  4976.3  328.11  4990.4  322.25  5001.3  320.76  5004.0  320.26
  5007.3  320.76  5018.3  328.15  5025.6  330.02  5265.9  330.49  5322.6  332.49
  5372.3  337.56  5429.0  340.80  5577.5  355.17  5646.7  359.48  5678.0  361.67
#Mann=8,-1,0
  4182.4     0.1       0  4183.9    0.05       0  4384.0    0.16       0
  4677.9    0.12       0  4916.6     0.1       0  5001.3    0.07       0
  5007.3     0.1       0  5646.7    0.05       0
Bank Sta=5001.3,5007.3
Exp/Cntr=0.3,0.1

Type RM Length L Ch R = 1,11198,641,641,641
BEGIN DESCRIPTION:
SANDY BRANCH 14.0
END DESCRIPTION:
XS GIS Cut Line= 3
      3544746.85     10451129.53      3544392.11     10450841.64
      3544033.94     10449985.17
#Sta/Elev= 30
  4377.0  355.89  4457.4  353.48  4513.4  352.47  4521.4  351.85  4563.4  350.65
  4930.1  329.43  4978.3  328.04  4985.6  325.29  4993.4  320.61  4996.2  320.11
  4999.4  320.61  5007.5  321.51  5018.1  327.21  5025.9  329.03  5049.7  328.36
  5063.0  328.58  5191.6  328.45  5232.4  329.61  5285.6  329.22  5344.0  330.53
  5362.4  330.27  5386.2  331.17  5397.5  332.53  5448.9  336.61  5462.5  337.38
  5497.6  340.59  5581.8  345.25  5657.6  348.20  5728.1  349.72  5762.2  351.49
#Mann=7,-1,0
  4377.0    0.05       0  4930.1    0.16       0  4993.4    0.07       0
  4999.4    0.16       0  5063.0    0.12       0  5232.4     0.1       0
  5448.9    0.05       0
Bank Sta=4993.4,4999.4
Exp/Cntr=0.3,0.1

Type RM Length L Ch R = 1,10557,642,642,642
BEGIN DESCRIPTION:
SANDY BRANCH 13.0
END DESCRIPTION:
XS GIS Cut Line= 2
      3545093.26     10450705.10      3544255.91     10449768.95
#Sta/Elev= 30
  4501.7  346.28  4554.6  347.96  4583.0  347.74  4632.4  344.89  4689.2  342.44
  4710.1  340.57  4731.8  339.65  4816.3  333.41  4864.1  330.60  4915.7  328.18
  4972.6  326.96  4979.3  325.58  4993.5  318.97  4998.0  318.35  5000.7  317.85
  5004.0  318.35  5007.2  319.32  5015.2  325.64  5029.4  327.61  5085.4  326.54
  5170.7  328.04  5227.5  327.09  5312.0  327.35  5333.7  327.87  5362.9  330.05
  5390.5  331.67  5503.4  341.56  5574.4  345.78  5638.0  348.62  5757.7  352.18
#Mann=6,-1,0
  4501.7    0.05       0  4864.1    0.16       0  4998.0    0.07       0
  5004.0    0.16       0  5007.2    0.12       0  5362.9    0.05       0
Bank Sta=4998,5004
Exp/Cntr=0.3,0.1

Type RM Length L Ch R = 1,9915,540,540,540
BEGIN DESCRIPTION:
SANDY BRANCH 12.0
END DESCRIPTION:
XS GIS Cut Line= 3
      3545192.10     10450491.68      3545292.11     10449991.64
      3544692.11     10449241.65
#Sta/Elev= 30
  4474.3  343.92  4545.7  339.45  4657.9  328.40  4746.1  325.59  4923.0  324.35
  4974.0  325.39  4981.7  322.74  4987.4  322.74  4991.4  318.78  4994.8  317.61
  4997.6  317.11  5000.8  317.61  5012.3  319.93  5020.3  323.66  5034.7  324.96
  5112.3  323.74  5140.6  324.55  5212.3  325.43  5262.0  323.93  5349.5  324.54
  5418.8  329.34  5460.5  334.27  5510.1  336.44  5524.5  338.39  5582.1  340.75
  5617.3  340.87  5631.8  342.42  5652.6  341.53  5716.6  343.38  5944.7  354.84
#Mann=6,-1,0
  4474.3    0.05       0  4746.1    0.12       0  4994.8    0.07       0
  5000.8    0.12       0  5140.6    0.05       0  5349.5    0.16       0
Bank Sta=4994.8,5000.8
Exp/Cntr=0.3,0.1

Type RM Length L Ch R = 1,9375,386,386,386
BEGIN DESCRIPTION:
SANDY BRANCH 11.0
END DESCRIPTION:
XS GIS Cut Line= 3
      3546011.22     10450527.89      3545990.39     10449944.52
      3545085.60     10449128.13
#Sta/Elev= 30
  4040.9  341.65  4117.2  337.23  4307.3  331.77  4427.4  330.94  4639.5  332.48
  4696.3  331.60  4808.3  327.11  4901.8  323.51  4970.5  323.72  4972.5  323.64
  4979.5  320.16  4993.7  316.50  4997.4  316.47  5000.2  315.97  5003.4  316.47
  5007.9  319.40  5014.6  321.84  5022.1  323.20  5057.2  323.71  5143.8  322.01
  5274.9  323.29  5397.2  323.42  5425.6  322.56  5439.8  323.66  5491.2  324.26
  5588.6  328.15  5637.9  332.06  5694.7  334.04  5772.4  338.54  5843.3  340.62
#Mann=8,-1,0
  4040.9    0.05       0  4808.3     0.1       0  4970.5    0.12       0
  4997.4    0.07       0  5003.4    0.12       0  5143.8    0.16       0
  5274.9    0.05       0  5491.2    0.16       0
Bank Sta=4997.4,5003.4
Exp/Cntr=0.3,0.1

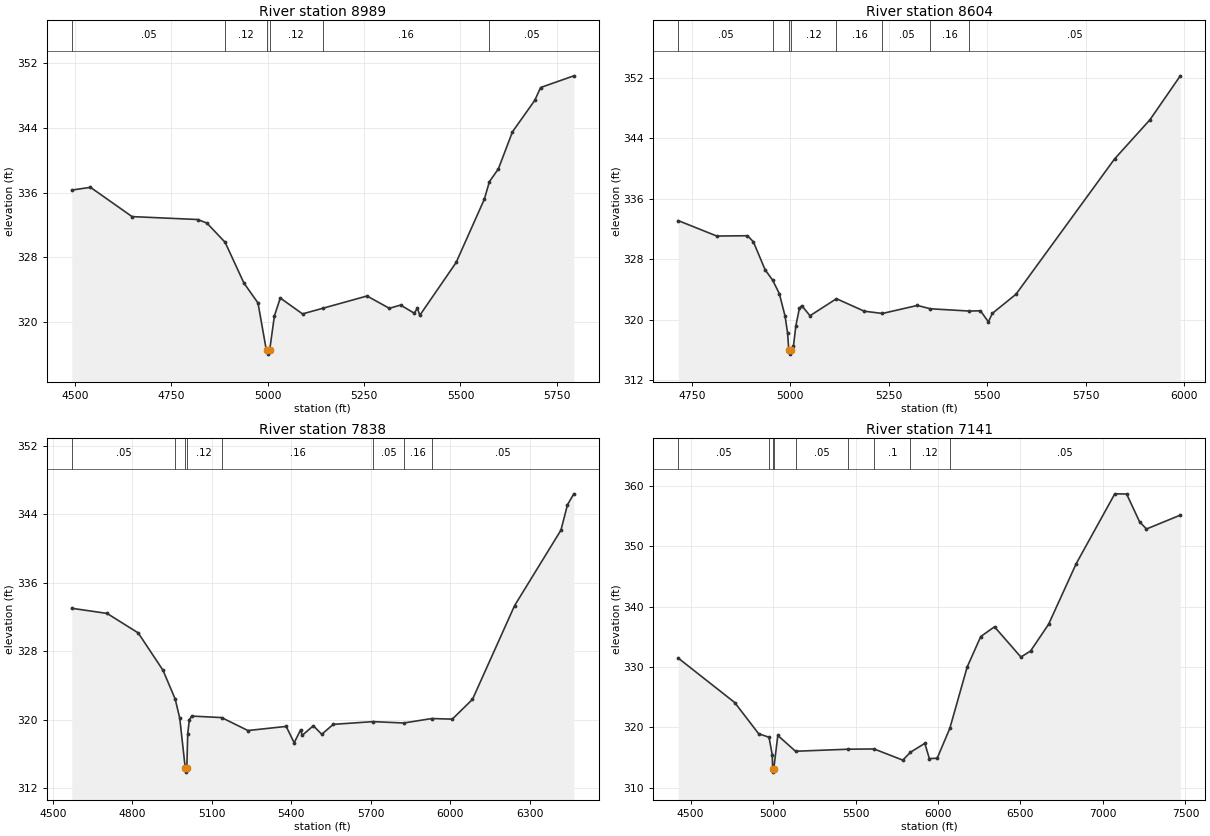
Type RM Length L Ch R = 1,8989,385,385,385
BEGIN DESCRIPTION:
SANDY BRANCH 10.0
END DESCRIPTION:
XS GIS Cut Line= 3
      3546377.05     10449580.06      3545996.83     10449426.55
      3545241.65     10448952.46
#Sta/Elev= 30
  4492.3  336.31  4540.8  336.65  4648.6  333.04  4818.9  332.68  4842.7  332.24
  4889.9  329.87  4938.6  324.85  4975.1  322.39  4996.3  316.69  4999.4  316.58
  5002.1  316.08  5005.4  316.58  5017.6  320.78  5032.9  323.00  5090.6  321.04
  5142.7  321.73  5257.9  323.25  5315.6  321.73  5344.8  322.13  5380.2  321.13
  5388.6  321.75  5394.5  320.86  5488.8  327.38  5561.8  335.17  5575.2  337.36
  5598.3  338.92  5634.9  343.50  5692.6  347.37  5707.9  348.96  5794.0  350.40
#Mann=6,-1,0
  4492.3    0.05       0  4889.9    0.12       0  4999.4    0.07       0
  5005.4    0.12       0  5142.7    0.16       0  5575.2    0.05       0
Bank Sta=4999.4,5005.4
Exp/Cntr=0.3,0.1

Type RM Length L Ch R = 1,8604,766,766,766
BEGIN DESCRIPTION:
SANDY BRANCH 8.0
END DESCRIPTION:
XS GIS Cut Line= 3
      3546356.24     10449212.88      3545866.67     10448879.55
      3545185.24     10448878.81
#Sta/Elev= 30
  4715.7  333.12  4813.5  331.08  4891.4  331.12  4906.3  330.32  4936.2  326.61
  4955.0  325.26  4972.1  323.47  4986.8  320.47  4993.1  318.27  4996.2  315.96
  4998.9  315.46  5002.2  315.96  5008.0  316.52  5014.1  319.21  5023.0  321.50
  5029.0  321.87  5050.0  320.54  5117.1  322.79  5187.6  321.14  5233.6  320.84
  5322.5  321.90  5355.2  321.46  5453.1  321.16  5482.5  321.19  5502.5  319.73
  5512.5  320.85  5572.5  323.38  5822.5  341.27  5912.5  346.47  5989.4  352.27
#Mann=8,-1,0
  4715.7    0.05       0  4955.0    0.12       0  4996.2    0.07       0
  5002.2    0.12       0  5117.1    0.16       0  5233.6    0.05       0
  5355.2    0.16       0  5453.1    0.05       0
Bank Sta=4996.2,5002.2
Exp/Cntr=0.3,0.1

Type RM Length L Ch R = 1,7838,697,697,697
BEGIN DESCRIPTION:
SANDY BRANCH 7.0
END DESCRIPTION:
XS GIS Cut Line= 3
      3546757.30     10448892.58      3546392.44     10448335.57
      3545243.23     10448774.65
#Sta/Elev= 30
  4571.0  333.04  4704.3  332.44  4822.0  330.16  4915.5  325.80  4961.5  322.44
  4978.7  320.22  4999.5  314.40  5002.2  313.90  5005.5  314.40  5008.9  318.37
  5014.9  320.00  5024.0  320.45  5137.0  320.27  5236.2  318.76  5380.8  319.24
  5410.9  317.33  5435.6  318.86  5441.0  318.19  5483.4  319.32  5515.1  318.32
  5558.4  319.48  5709.3  319.80  5824.3  319.64  5931.2  320.16  6008.0  320.09
  6084.3  322.40  6243.3  333.35  6418.4  342.17  6443.1  345.14  6467.1  346.41
#Mann=8,-1,0
  4571.0    0.05       0  4961.5    0.12       0  4999.5    0.07       0
  5005.5    0.12       0  5137.0    0.16       0  5709.3    0.05       0
  5824.3    0.16       0  5931.2    0.05       0
Bank Sta=4999.5,5005.5
Exp/Cntr=0.3,0.1

Type RM Length L Ch R = 1,7141,0,0,0
BEGIN DESCRIPTION:
SANDY BRANCH 1.0
END DESCRIPTION:
XS GIS Cut Line= 6
      3546896.21     10448761.75      3547097.59     10448049.99
      3546882.32     10447869.43      3546048.67     10447672.96
      3545395.46     10447286.68      3545015.32     10447398.99
#Sta/Elev= 30
  4424.6  331.50  4767.0  324.14  4912.1  318.97  4975.2  318.38  4994.4  315.49
  4997.6  313.10  5000.4  312.60  5003.6  313.10  5028.4  318.68  5135.8  316.06
  5455.3  316.40  5612.3  316.44  5786.3  314.59  5833.0  315.90  5919.9  317.37
  5947.3  314.85  5994.8  314.90  6071.6  319.87  6176.7  330.03  6259.1  335.08
  6342.4  336.69  6502.3  331.68  6560.8  332.67  6670.0  337.09  6837.7  347.15
  7071.8  358.73  7143.6  358.70  7222.2  354.09  7263.9  352.90  7469.1  355.20
#Mann=9,-1,0
  4424.6    0.05       0  4975.2    0.16       0  4997.6    0.07       0
  5003.6    0.16       0  5135.8    0.05       0  5455.3    0.16       0
  5612.3     0.1       0  5833.0    0.12       0  6071.6    0.05       0
Bank Sta=4997.6,5003.6
Exp/Cntr=0.3,0.1

Chan Stop Cuts=-1