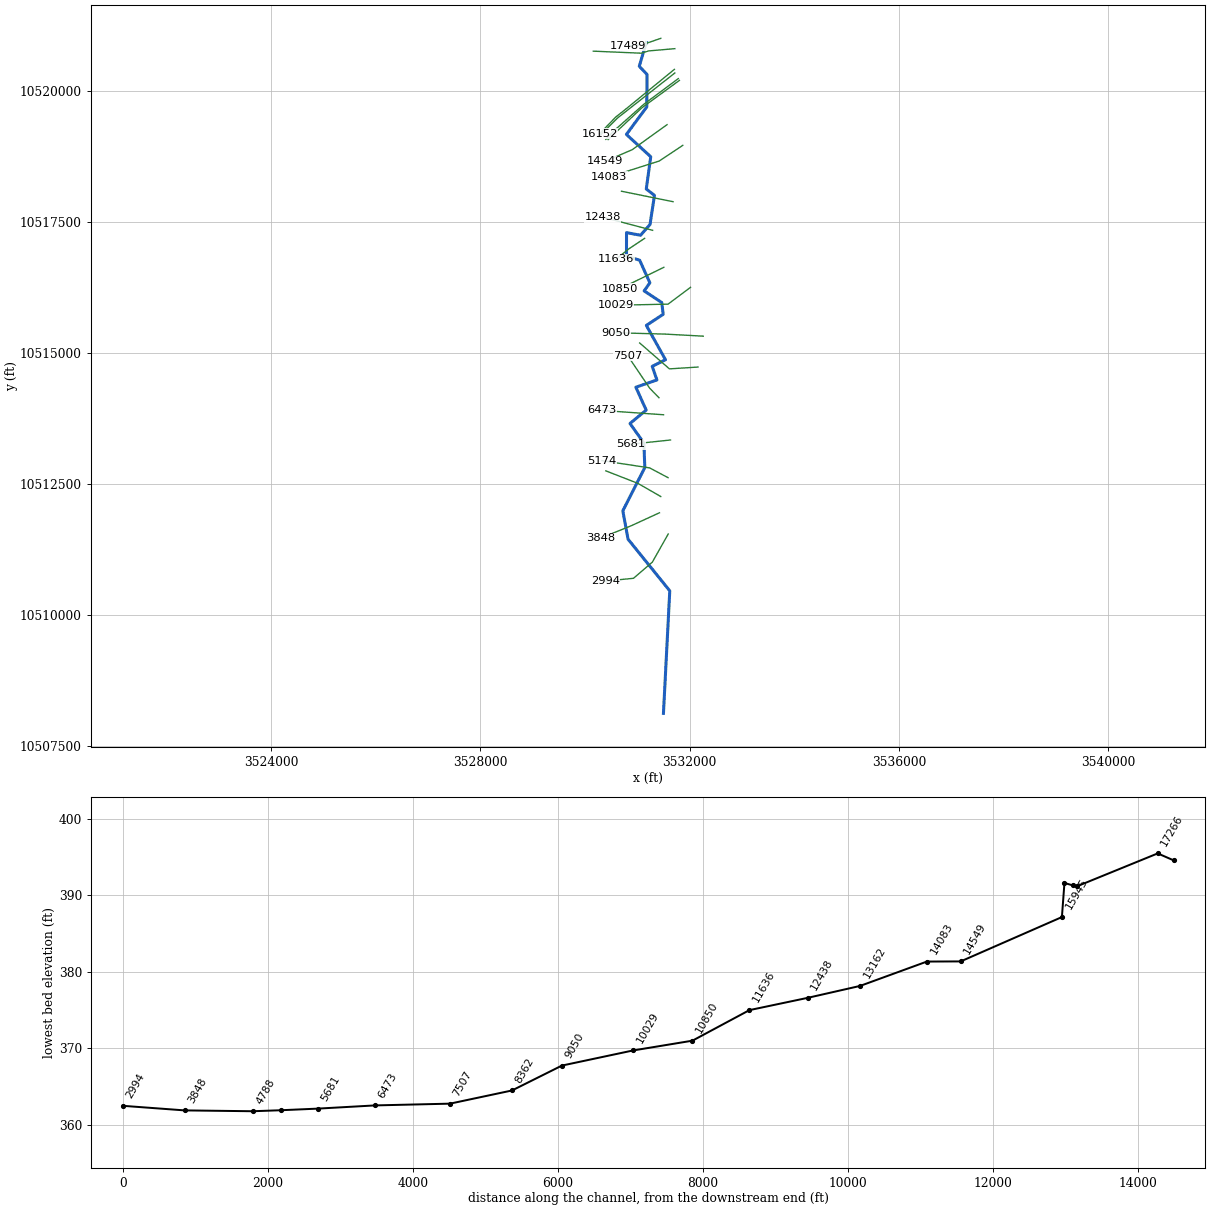
--- SASSAFRAS BRANCH.prj (project) ---

Proj Title=SASSAFRAS BRANCH Base Level Engineering
Current Plan=p01
Default Exp/Contr=0.3,0.1
English Units
Geom File=g01
Flow File=f01
Plan File=p01
BEGIN DESCRIPTION:
SASSAFRAS BRANCH
END DESCRIPTION:

--- SASSAFRAS BRANCH.p01 (plan) ---

Plan Title=Multiple Run
Short Identifier=Multiple
Geom File=g01
Flow File=f01
Subcritical Flow
K Sum by GR= 0
Std Step Tol= 0.01
Critical Tol= 0.01
Num of Std Step Trials= 20
Max Error Tol= 0.3
Flow Tol Ratio= 0.001
Split Flow NTrial= 30
Split Flow Tol= 0.02
Split Flow Ratio= 0.02
Log Output Level= 0
Friction Slope Method= 1
Unsteady Friction Slope Method= 2
Unsteady Bridges Friction Slope Method= 1
Parabolic Critical Depth
Global Vel Dist=  1 , 1 , 1
Global Log Level= 0
CheckData=True
Encroach Param= -1, 0, 0, 0
BEGIN DESCRIPTION:
Multiple Run
END DESCRIPTION:

--- SASSAFRAS BRANCH.f01 (steady flow) ---

Flow Title=Multiple
Number of Profiles=7
Profile Names=10-year,25-year,50-year,1pct_min,100-year,1pct_plu,500-year
River Rch & RM= SASSAFRAS BRANCH,Reach-1,17489
     852    1150    1390    1225    1657    2241    2349
River Rch & RM= SASSAFRAS BRANCH,Reach-1,17266
    1201    1648    2013    1791    2422    3275    3498
River Rch & RM= SASSAFRAS BRANCH,Reach-1,5174
    1386    1908    2335    2080    2813    3804    4073
Boundary for River Rch & Prof#=SASSAFRAS BRANCH,Reach-1,1
Up Type=0
Dn Type=3
Dn Slope=0.005
Boundary for River Rch & Prof#=SASSAFRAS BRANCH,Reach-1,2
Up Type=0
Dn Type=3
Dn Slope=0.005
Boundary for River Rch & Prof#=SASSAFRAS BRANCH,Reach-1,3
Up Type=0
Dn Type=3
Dn Slope=0.005
Boundary for River Rch & Prof#=SASSAFRAS BRANCH,Reach-1,4
Up Type=0
Dn Type=3
Dn Slope=0.005
Boundary for River Rch & Prof#=SASSAFRAS BRANCH,Reach-1,5
Up Type=0
Dn Type=3
Dn Slope=0.005
Boundary for River Rch & Prof#=SASSAFRAS BRANCH,Reach-1,6
Up Type=0
Dn Type=3
Dn Slope=0.005
Boundary for River Rch & Prof#=SASSAFRAS BRANCH,Reach-1,7
Up Type=0
Dn Type=3
Dn Slope=0.005

--- SASSAFRAS BRANCH.g01 (geometry) ---

Geom Title=Existing Conditions

River Reach=SASSAFRAS BRANCH,Reach-1
Reach XY= 30
      3531173.26     10520935.82      3531039.38     10520478.87
      3531188.04     10520321.97      3531182.68     10519702.83
      3530792.81     10519176.56      3531258.17     10518750.32
      3531172.82     10518134.24      3531329.78     10518011.78
      3531244.45     10517456.02      3531063.20     10517250.09
      3530795.44     10517300.46      3530794.92     10516850.34
      3531046.19     10516773.50      3531241.57     10516341.86
      3531131.63     10516186.76      3531467.86     10515964.86
      3531496.44     10515739.72      3531173.99     10515527.14
      3531540.12     10514871.56      3531286.27     10514745.40
      3531376.29     10514485.25      3530973.85     10514346.58
      3531171.32     10513909.41      3530861.95     10513653.16
      3531127.05     10513280.24      3531144.93     10512811.21
      3530724.79     10511984.67      3530824.62     10511442.14
      3531621.84     10510455.99      3531500.95     10508114.26

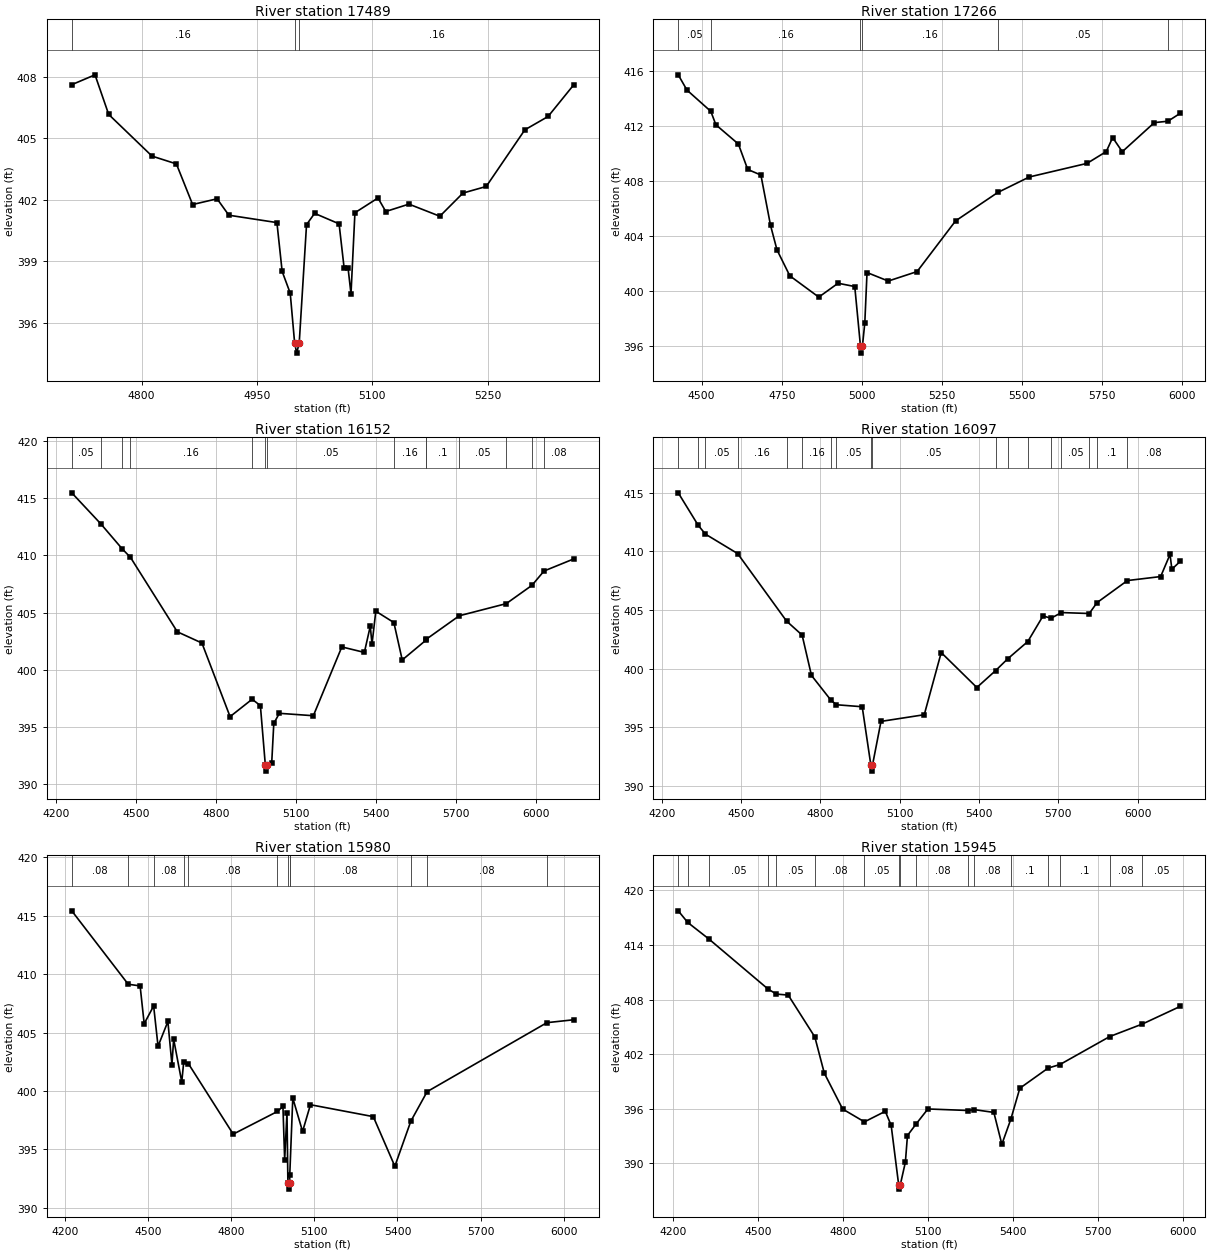
Type RM Length L Ch R = 1,17489,223,223,223
BEGIN DESCRIPTION:
SASSAFRAS BRANCH 27.1
END DESCRIPTION:
XS GIS Cut Line= 3
      3531450.71     10521012.87      3531114.81     10520897.43
      3530818.76     10520867.91
#Sta/Elev= 30
  4709.3  407.61  4739.5  408.09  4757.3  406.16  4813.6  404.13  4845.3  403.75
  4866.4  401.77  4898.2  402.05  4913.5  401.25  4976.0  400.89  4982.8  398.51
  4993.3  397.45  4999.0  395.03  5001.7  394.53  5005.0  395.03  5014.5  400.79
  5025.0  401.34  5056.8  400.83  5063.3  398.70  5068.4  398.70  5072.3  397.42
  5077.4  401.37  5107.4  402.09  5117.5  401.43  5147.6  401.79  5187.8  401.20
  5217.9  402.33  5248.1  402.65  5298.3  405.41  5328.5  406.06  5362.0  407.61
#Mann=3,-1,0
  4709.3    0.16       0  4999.0    0.07       0  5005.0    0.16       0
Bank Sta=4999,5005
Exp/Cntr=0.3,0.1

Type RM Length L Ch R = 1,17266,1114,1114,1114
BEGIN DESCRIPTION:
SASSAFRAS BRANCH 27.0
END DESCRIPTION:
XS GIS Cut Line= 4
      3531719.24     10520815.62      3531215.80     10520772.22
      3531076.91     10520728.82      3530161.07     10520767.88
#Sta/Elev= 30
  4426.8  415.72  4454.0  414.61  4528.5  413.06  4544.4  412.08  4614.6  410.68
  4643.7  408.83  4684.9  408.42  4715.0  404.75  4735.1  402.97  4775.2  401.08
  4865.6  399.53  4925.8  400.54  4977.9  400.30  4995.8  395.95  4998.6  395.45
  5001.8  395.95  5009.3  397.66  5016.2  401.32  5082.5  400.70  5172.5  401.39
  5292.6  405.08  5424.3  407.15  5522.8  408.28  5703.0  409.27  5763.1  410.13
  5783.1  411.15  5813.1  410.12  5913.2  412.24  5955.4  412.34  5994.3  412.92
#Mann=6,-1,0
  4426.8    0.05       0  4528.5    0.16       0  4995.8    0.07       0
  5001.8    0.16       0  5424.3    0.05       0  5955.4     0.1       0
Bank Sta=4995.8,5001.8
Exp/Cntr=0.3,0.1

Type RM Length L Ch R = 1,16152,55,55,55
BEGIN DESCRIPTION:
SASSAFRAS BRANCH 25.1
END DESCRIPTION:
XS GIS Cut Line= 4
      3531710.60     10520420.66      3530803.48     10519678.47
      3530587.33     10519506.60      3530282.66     10519191.51
#Sta/Elev= 30
  4257.4  415.46  4366.5  412.75  4446.7  410.57  4478.0  409.82  4654.0  403.32
  4746.4  402.34  4852.2  395.91  4935.1  397.43  4966.1  396.87  4984.8  391.65
  4987.6  391.15  4990.8  391.65  5008.6  391.84  5016.5  395.32  5037.4  396.20
  5165.1  395.99  5272.1  402.00  5356.8  401.52  5379.0  403.81  5385.5  402.25
  5399.8  405.12  5467.6  404.13  5499.1  400.86  5589.3  402.61  5590.0  402.68
  5713.3  404.72  5889.9  405.78  5986.6  407.38  6031.8  408.63  6143.9  409.69
#Mann=14,-1,0
  4257.4    0.05       0  4366.5    0.16       0  4446.7    0.05       0
  4478.0    0.16       0  4935.1    0.05       0  4984.8    0.03       0
  4990.8    0.05       0  5467.6    0.16       0  5589.3    0.08       0
  5590.0     0.1       0  5713.3    0.05       0  5889.9     0.1       0
  5986.6    0.05       0  6031.8    0.08       0
Bank Sta=4984.8,4990.8
Exp/Cntr=0.3,0.1

Type RM Length L Ch R = 1,16097,117,117,117
BEGIN DESCRIPTION:
SASSAFRAS BRANCH 25.0
END DESCRIPTION:
XS GIS Cut Line= 3
      3531719.30     10520351.23      3530625.52     10519491.84
      3530266.18     10519132.49
#Sta/Elev= 30
  4262.4  415.00  4337.9  412.23  4365.2  411.48  4487.1  409.82  4672.3  404.06
  4731.0  402.87  4766.4  399.43  4839.6  397.33  4860.7  396.93  4958.3  396.76
  4991.1  391.77  4993.9  391.27  4997.1  391.77  5029.4  395.51  5193.0  396.08
  5257.2  401.38  5391.9  398.40  5462.8  399.84  5508.4  400.84  5584.7  402.32
  5642.2  404.50  5672.6  404.31  5712.1  404.79  5817.1  404.71  5846.7  405.64
  5961.5  407.52  6087.3  407.86  6122.7  409.75  6129.7  408.49  6161.6  409.16
#Mann=18,-1,0
  4262.4    0.05       0  4337.9    0.08       0  4365.2    0.05       0
  4487.1    0.16       0  4672.3    0.05       0  4731.0    0.16       0
  4839.6    0.08       0  4860.7    0.05       0  4991.1    0.03       0
  4997.1    0.05       0  5462.8    0.16       0  5508.4    0.08       0
  5584.7     0.1       0  5672.6    0.08       0  5712.1    0.05       0
  5817.1    0.08       0  5846.7     0.1       0  5961.5    0.08       0
Bank Sta=4991.1,4997.1
Exp/Cntr=0.3,0.1

Type RM Length L Ch R = 1,15980,35,35,35
BEGIN DESCRIPTION:
SASSAFRAS BRANCH 25.2
END DESCRIPTION:
XS GIS Cut Line= 4
      3531785.24     10520243.57      3531123.79     10519751.39
      3530563.89     10519253.99      3530399.83     10519082.12
#Sta/Elev= 30
  4225.2  415.43  4428.8  409.14  4471.7  409.00  4486.4  405.76  4520.5  407.28
  4536.4  403.83  4571.9  405.95  4586.5  402.25  4592.7  404.43  4621.9  400.77
  4629.2  402.52  4646.1  402.33  4807.5  396.30  4966.8  398.24  4986.9  398.67
  4993.1  394.11  5001.5  398.15  5004.8  392.09  5007.5  391.59  5010.8  392.09
  5011.5  392.80  5022.4  399.39  5057.7  396.53  5086.1  398.82  5312.8  397.80
  5390.5  393.55  5448.2  397.41  5507.0  399.94  5939.1  405.85  6036.2  406.10
#Mann=12,-1,0
  4225.2    0.08       0  4428.8    0.05       0  4520.5    0.08       0
  4629.2    0.05       0  4646.1    0.08       0  4966.8    0.05       0
  5004.8    0.03       0  5010.8    0.05       0  5011.5    0.08       0
  5448.2     0.1       0  5507.0    0.08       0  5939.1    0.05       0
Bank Sta=5004.8,5010.8
Exp/Cntr=0.3,0.1

Type RM Length L Ch R = 1,15945,1396,1396,1396
BEGIN DESCRIPTION:
SASSAFRAS BRANCH 25.3
END DESCRIPTION:
XS GIS Cut Line= 3
      3531806.22     10520209.32      3531090.11     10519686.34
      3530443.43     10519078.72
#Sta/Elev= 30
  4218.1  417.76  4251.7  416.48  4326.4  414.66  4535.2  409.16  4564.6  408.60
  4606.7  408.49  4700.8  403.88  4734.2  399.90  4799.1  395.95  4876.0  394.54
  4949.7  395.70  4970.5  394.15  4996.9  387.64  4999.6  387.14  5002.9  387.64
  5020.7  390.10  5028.1  393.04  5059.7  394.35  5100.3  395.96  5243.7  395.79
  5263.5  395.89  5333.3  395.58  5361.6  392.07  5393.2  394.82  5425.1  398.24
  5525.2  400.46  5567.0  400.85  5743.0  403.93  5858.5  405.31  5992.2  407.25
#Mann=17,-1,0
  4218.1    0.05       0  4251.7    0.08       0  4326.4    0.05       0
  4535.2    0.08       0  4564.6    0.05       0  4700.8    0.08       0
  4876.0    0.05       0  4996.9    0.03       0  5002.9    0.05       0
  5059.7    0.08       0  5243.7     0.1       0  5263.5    0.08       0
  5393.2     0.1       0  5525.2    0.08       0  5567.0     0.1       0
  5743.0    0.08       0  5858.5    0.05       0
Bank Sta=4996.9,5002.9
Exp/Cntr=0.3,0.1

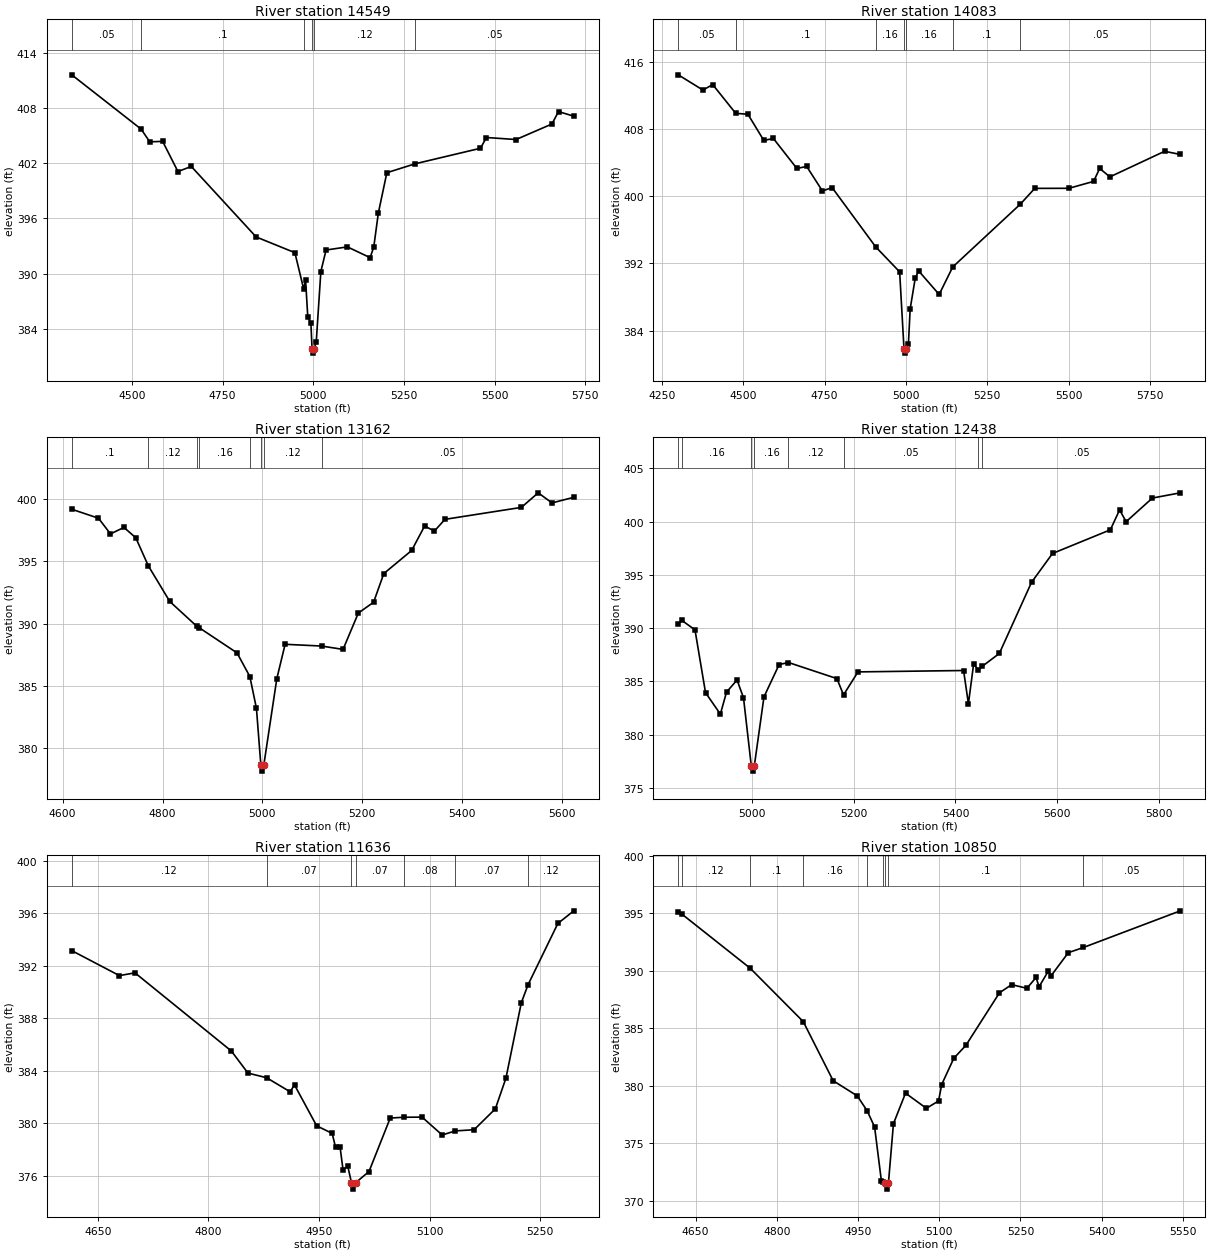
Type RM Length L Ch R = 1,14549,466,466,466
BEGIN DESCRIPTION:
SASSAFRAS BRANCH 24.0
END DESCRIPTION:
XS GIS Cut Line= 3
      3531569.73     10519363.54      3530905.64     10518886.10
      3530385.94     10518660.89
#Sta/Elev= 30
  4334.3  411.63  4525.6  405.72  4549.3  404.34  4584.9  404.39  4627.0  401.11
  4663.9  401.66  4842.7  393.99  4949.5  392.28  4973.8  388.32  4979.0  389.28
  4985.1  385.28  4993.7  384.58  4996.8  381.85  4999.6  381.35  5002.8  381.85
  5008.4  382.56  5021.1  390.22  5035.5  392.57  5094.3  392.91  5156.9  391.74
  5167.0  392.89  5179.6  396.59  5203.1  400.98  5281.0  401.95  5461.2  403.64
  5477.7  404.81  5559.3  404.59  5658.3  406.28  5676.4  407.63  5718.6  407.13
#Mann=6,-1,0
  4334.3    0.05       0  4525.6     0.1       0  4973.8    0.12       0
  4996.8    0.07       0  5002.8    0.12       0  5281.0    0.05       0
Bank Sta=4996.8,5002.8
Exp/Cntr=0.3,0.1

Type RM Length L Ch R = 1,14083,921,921,921
BEGIN DESCRIPTION:
SASSAFRAS BRANCH 22.0
END DESCRIPTION:
XS GIS Cut Line= 3
      3531871.11     10518967.91      3531420.50     10518668.68
      3530465.97     10518364.97
#Sta/Elev= 30
  4300.6  414.44  4376.3  412.63  4406.4  413.28  4477.1  409.86  4514.6  409.75
  4563.5  406.63  4592.8  406.87  4665.0  403.30  4695.1  403.54  4743.6  400.62
  4773.2  401.03  4907.2  393.97  4980.8  391.00  4994.2  381.83  4997.0  381.33
  5000.2  381.83  5007.7  382.37  5013.1  386.58  5028.7  390.25  5039.2  391.11
  5102.2  388.31  5143.9  391.58  5351.8  399.06  5396.0  400.93  5501.0  400.94
  5576.7  401.76  5595.4  403.30  5626.9  402.30  5794.8  405.34  5843.2  404.97
#Mann=7,-1,0
  4300.6    0.05       0  4477.1     0.1       0  4907.2    0.16       0
  4994.2    0.07       0  5000.2    0.16       0  5143.9     0.1       0
  5351.8    0.05       0
Bank Sta=4994.2,5000.2
Exp/Cntr=0.3,0.1

Type RM Length L Ch R = 1,13162,724,724,724
BEGIN DESCRIPTION:
SASSAFRAS BRANCH 20.0
END DESCRIPTION:
XS GIS Cut Line= 2
      3531684.51     10517891.55      3530699.24     10518091.21
#Sta/Elev= 30
  4618.3  399.19  4671.8  398.47  4695.8  397.21  4722.8  397.73  4746.5  396.90
  4771.5  394.65  4814.6  391.78  4868.3  389.80  4873.2  389.68  4949.2  387.65
  4974.9  385.75  4988.1  383.19  4996.9  378.65  4999.6  378.15  5002.9  378.65
  5028.9  385.58  5045.5  388.34  5118.5  388.20  5161.5  387.93  5192.1  390.85
  5222.7  391.72  5243.1  394.02  5298.9  395.88  5324.8  397.84  5344.5  397.44
  5365.6  398.38  5518.6  399.34  5552.3  400.51  5579.9  399.70  5623.6  400.15
#Mann=8,-1,0
  4618.3     0.1       0  4771.5    0.12       0  4868.3     0.1       0
  4873.2    0.16       0  4974.9    0.12       0  4996.9    0.07       0
  5002.9    0.12       0  5118.5    0.05       0
Bank Sta=4996.9,5002.9
Exp/Cntr=0.3,0.1

Type RM Length L Ch R = 1,12438,802,802,802
BEGIN DESCRIPTION:
SASSAFRAS BRANCH 19.0
END DESCRIPTION:
XS GIS Cut Line= 2
      3531293.91     10517344.67      3530339.03     10517596.41
#Sta/Elev= 30
  4854.8  390.42  4861.9  390.73  4887.7  389.84  4908.4  383.95  4937.6  381.94
  4949.7  384.00  4970.4  385.14  4983.1  383.47  4998.4  377.09  5001.2  376.59
  5004.4  377.09  5023.4  383.56  5053.2  386.59  5071.6  386.78  5166.9  385.27
  5179.8  383.74  5208.3  385.90  5416.0  386.03  5425.5  382.91  5435.8  386.66
  5445.1  386.06  5453.2  386.44  5486.3  387.63  5549.6  394.30  5590.9  397.01
  5704.7  399.23  5722.9  401.10  5735.7  399.99  5787.4  402.21  5842.3  402.70
#Mann=8,-1,0
  4854.8     0.1       0  4861.9    0.16       0  4998.4    0.07       0
  5004.4    0.16       0  5071.6    0.12       0  5179.8    0.05       0
  5445.1    0.12       0  5453.2    0.05       0
Bank Sta=4998.4,5004.4
Exp/Cntr=0.3,0.1

Type RM Length L Ch R = 1,11636,786,786,786
BEGIN DESCRIPTION:
SASSAFRAS BRANCH 18.0
END DESCRIPTION:
XS GIS Cut Line= 3
      3531142.12     10517191.65      3530842.11     10516991.64
      3530592.13     10516791.66
#Sta/Elev= 30
  4614.7  393.14  4679.3  391.24  4700.4  391.45  4831.1  385.50  4853.6  383.82
  4878.8  383.47  4910.7  382.40  4916.7  382.92  4946.7  379.81  4967.8  379.23
  4972.3  378.18  4978.5  378.18  4982.5  376.46  4988.9  376.74  4993.9  375.49
  4996.6  374.99  4999.9  375.49  5017.7  376.33  5046.5  380.40  5065.2  380.46
  5089.7  380.47  5116.9  379.11  5134.7  379.42  5160.2  379.51  5189.0  381.10
  5203.4  383.44  5224.2  389.17  5233.4  390.55  5273.8  395.21  5295.4  396.17
#Mann=7,-1,0
  4614.7    0.12       0  4878.8    0.07       0  4993.9    0.07       0
  4999.9    0.07       0  5065.2    0.08       0  5134.7    0.07       0
  5233.4    0.12       0
Bank Sta=4993.9,4999.9
Exp/Cntr=0.3,0.1

Type RM Length L Ch R = 1,10850,821,821,821
BEGIN DESCRIPTION:
SASSAFRAS BRANCH 16.0
END DESCRIPTION:
XS GIS Cut Line= 2
      3531508.96     10516637.84      3530676.38     10516230.23
#Sta/Elev= 30
  4618.1  395.14  4624.1  394.95  4750.8  390.22  4848.9  385.57  4904.1  380.43
  4948.6  379.11  4966.8  377.82  4980.6  376.41  4993.2  371.69  4995.5  371.63
  5000.1  371.50  5002.8  371.00  5006.1  371.50  5015.4  376.69  5037.7  379.35
  5076.2  378.03  5098.7  378.67  5104.5  380.10  5126.8  382.38  5149.2  383.51
  5211.2  388.08  5233.7  388.79  5261.8  388.47  5278.7  389.41  5284.3  388.61
  5301.2  389.95  5306.8  389.58  5338.3  391.57  5366.1  392.02  5545.1  395.21
#Mann=9,-1,0
  4618.1    0.05       0  4624.1    0.12       0  4750.8     0.1       0
  4848.9    0.16       0  4966.8    0.07       0  4995.5     0.1       0
  5000.1    0.07       0  5006.1     0.1       0  5366.1    0.05       0
Bank Sta=5000.1,5006.1
Exp/Cntr=0.3,0.1

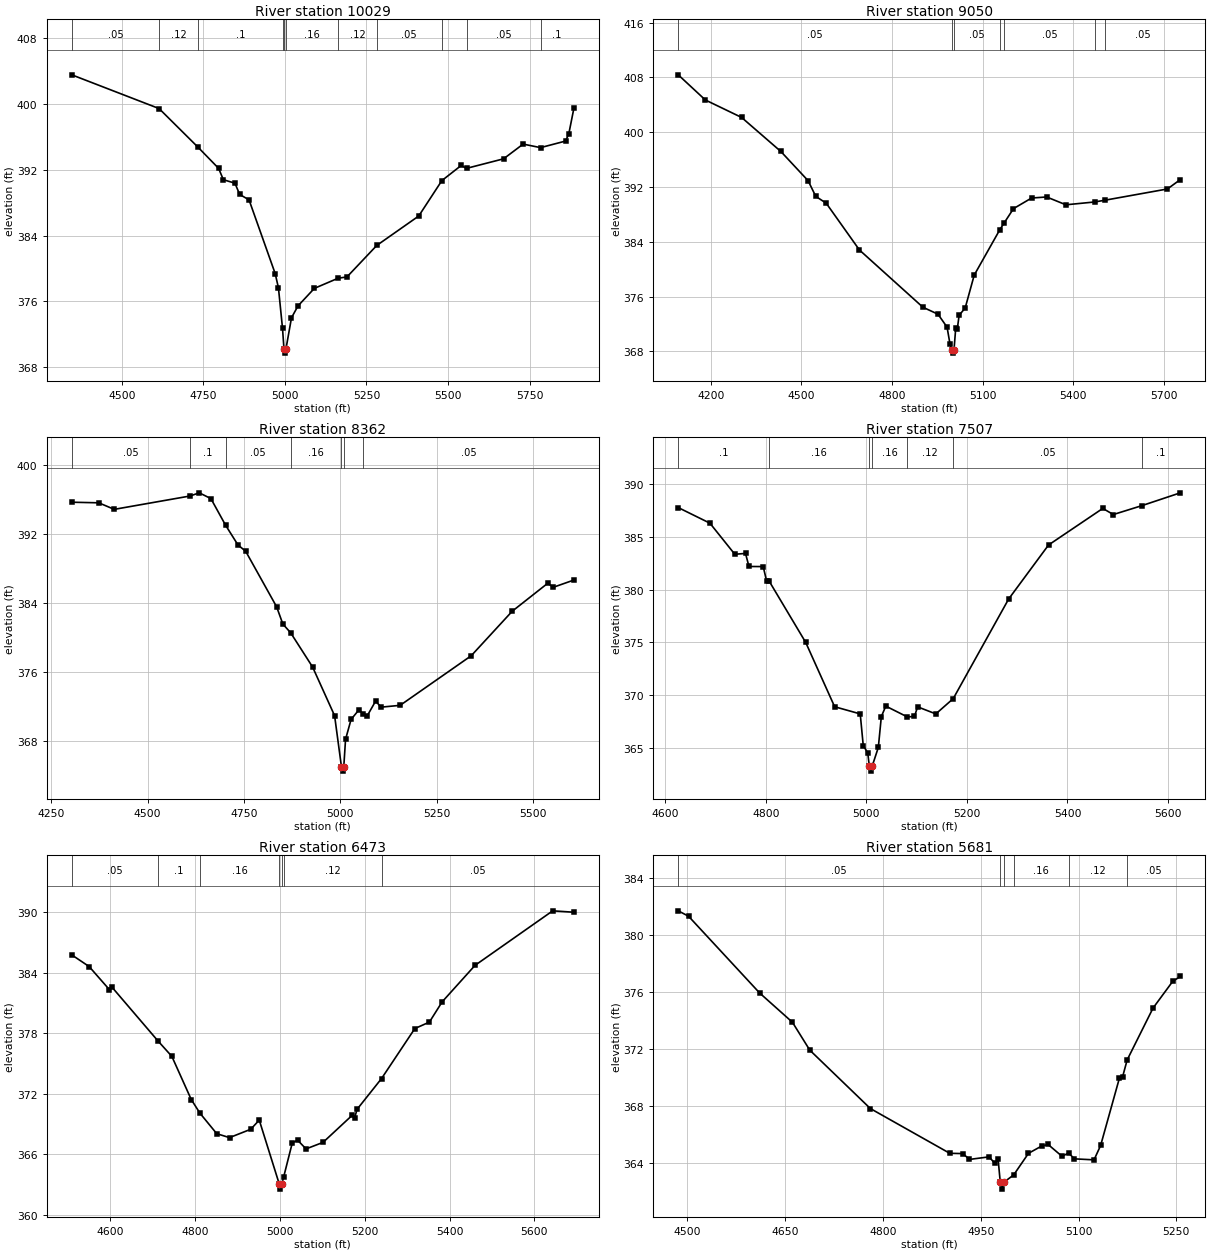
Type RM Length L Ch R = 1,10029,979,979,979
BEGIN DESCRIPTION:
SASSAFRAS BRANCH 14.0
END DESCRIPTION:
XS GIS Cut Line= 3
      3532018.76     10516255.29      3531589.03     10515934.08
      3530586.77     10515912.39
#Sta/Elev= 30
  4346.7  403.55  4614.3  399.45  4734.2  394.73  4796.8  392.18  4811.4  390.80
  4846.8  390.38  4861.4  389.01  4890.1  388.35  4970.2  379.39  4980.2  377.66
  4992.7  372.73  4997.2  370.22  4999.9  369.72  5003.2  370.22  5020.2  374.02
  5040.2  375.46  5090.2  377.59  5163.4  378.83  5190.2  378.98  5281.6  382.81
  5410.3  386.39  5481.1  390.69  5540.3  392.53  5556.7  392.18  5670.3  393.34
  5730.3  395.13  5783.6  394.70  5860.4  395.50  5870.4  396.41  5885.7  399.46
#Mann=11,-1,0
  4346.7    0.05       0  4614.3    0.12       0  4734.2     0.1       0
  4992.7    0.16       0  4997.2    0.07       0  5003.2    0.16       0
  5163.4    0.12       0  5281.6    0.05       0  5481.1    0.12       0
  5556.7    0.05       0  5783.6     0.1       0
Bank Sta=4997.2,5003.2
Exp/Cntr=0.3,0.1

Type RM Length L Ch R = 1,9050,688,688,688
BEGIN DESCRIPTION:
SASSAFRAS BRANCH 13.0
END DESCRIPTION:
XS GIS Cut Line= 3
      3532261.76     10515322.10      3531536.95     10515361.16
      3530599.47     10515387.20
#Sta/Elev= 30
  4091.6  408.37  4181.4  404.70  4301.6  402.15  4431.7  397.18  4521.9  392.92
  4547.3  390.63  4582.0  389.63  4692.1  382.80  4902.3  374.45  4952.4  373.43
  4982.4  371.54  4992.4  369.01  4999.4  368.25  5002.1  367.75  5005.4  368.25
  5011.1  371.38  5016.1  371.22  5022.4  373.28  5042.4  374.33  5072.4  379.14
  5157.3  385.77  5171.4  386.74  5202.5  388.84  5262.5  390.39  5312.5  390.54
  5376.2  389.40  5471.1  389.81  5506.9  390.08  5712.6  391.71  5755.3  393.08
#Mann=7,-1,0
  4091.6    0.05       0  4999.4   0.035       0  5005.4    0.05       0
  5157.3    0.12       0  5171.4    0.05       0  5471.1     0.1       0
  5506.9    0.05       0
Bank Sta=4999.4,5005.4
Exp/Cntr=0.3,0.1

Type RM Length L Ch R = 1,8362,855,855,855
BEGIN DESCRIPTION:
SASSAFRAS BRANCH 12.0
END DESCRIPTION:
XS GIS Cut Line= 3
      3532161.99     10514731.83      3531615.08     10514697.10
      3531046.83     10515191.61
#Sta/Elev= 30
  4303.7  395.73  4373.7  395.66  4413.8  394.90  4610.1  396.45  4634.2  396.82
  4664.3  396.15  4702.2  393.07  4734.4  390.77  4754.5  390.03  4834.7  383.58
  4850.7  381.59  4871.1  380.56  4927.9  376.59  4984.9  370.94  5002.7  365.00
  5005.5  364.50  5008.7  365.00  5013.3  368.19  5027.6  370.50  5048.5  371.65
  5058.8  371.13  5069.3  370.91  5091.2  372.63  5105.4  371.93  5154.8  372.14
  5339.0  377.90  5445.3  383.07  5537.4  386.32  5551.7  385.85  5605.0  386.69
#Mann=7,-1,0
  4303.7    0.05       0  4610.1     0.1       0  4702.2    0.05       0
  4871.1    0.16       0  5002.7    0.07       0  5008.7    0.16       0
  5058.8    0.05       0
Bank Sta=5002.7,5008.7
Exp/Cntr=0.3,0.1

Type RM Length L Ch R = 1,7507,1034,1034,1034
BEGIN DESCRIPTION:
SASSAFRAS BRANCH 10.0
END DESCRIPTION:
XS GIS Cut Line= 3
      3531415.40     10514145.91      3531237.47     10514328.18
      3530820.79     10514944.52
#Sta/Elev= 30
  4625.8  387.79  4688.8  386.31  4738.3  383.36  4759.6  383.44  4766.5  382.20
  4794.8  382.19  4801.8  380.78  4806.4  380.83  4879.4  374.99  4936.9  368.89
  4987.8  368.21  4993.8  365.21  5002.8  364.50  5005.8  363.28  5008.5  362.78
  5011.8  363.28  5023.8  365.03  5029.8  367.96  5038.7  368.95  5081.7  367.92
  5095.7  367.98  5102.0  368.88  5138.2  368.21  5172.8  369.66  5283.0  379.11
  5362.4  384.24  5470.3  387.71  5491.3  387.13  5547.8  387.97  5624.5  389.19
#Mann=7,-1,0
  4625.8     0.1       0  4806.4    0.16       0  5005.8    0.07       0
  5011.8    0.16       0  5081.7    0.12       0  5172.8    0.05       0
  5547.8     0.1       0
Bank Sta=5005.8,5011.8
Exp/Cntr=0.3,0.1

Type RM Length L Ch R = 1,6473,792,792,792
BEGIN DESCRIPTION:
SASSAFRAS BRANCH 8.0
END DESCRIPTION:
XS GIS Cut Line= 2
      3531502.98     10513820.25      3530322.45     10513902.71
#Sta/Elev= 30
  4509.5  385.79  4550.5  384.63  4598.4  382.33  4603.4  382.63  4712.3  377.27
  4745.4  375.72  4791.1  371.44  4811.7  370.08  4851.2  368.05  4881.3  367.66
  4931.4  368.49  4951.4  369.40  4998.6  363.05  5001.3  362.55  5004.6  363.05
  5008.7  363.72  5029.2  367.13  5041.7  367.41  5061.7  366.54  5101.8  367.19
  5171.1  369.90  5176.1  369.61  5182.0  370.47  5239.6  373.52  5318.1  378.48
  5352.4  379.12  5382.5  381.13  5460.0  384.75  5643.1  390.16  5692.9  390.02
#Mann=7,-1,0
  4509.5    0.05       0  4712.3     0.1       0  4811.7    0.16       0
  4998.6    0.07       0  5004.6    0.16       0  5008.7    0.12       0
  5239.6    0.05       0
Bank Sta=4998.6,5004.6
Exp/Cntr=0.3,0.1

Type RM Length L Ch R = 1,5681,507,507,507
BEGIN DESCRIPTION:
SASSAFRAS BRANCH 7.0
END DESCRIPTION:
XS GIS Cut Line= 2
      3531636.21     10513337.94      3530870.56     10513257.21
#Sta/Elev= 30
  4486.2  381.71  4502.0  381.33  4611.0  375.93  4661.3  373.87  4687.9  371.91
  4780.8  367.80  4902.6  364.65  4922.7  364.63  4932.8  364.22  4962.9  364.40
  4971.7  363.94  4976.7  364.23  4980.0  362.63  4982.8  362.13  4986.0  362.63
  5000.6  363.13  5023.3  364.65  5043.4  365.16  5053.4  365.27  5074.7  364.44
  5084.9  364.67  5093.7  364.26  5123.8  364.19  5133.9  365.20  5162.6  369.92
  5167.6  370.03  5174.6  371.22  5214.3  374.87  5244.5  376.75  5256.1  377.09
#Mann=6,-1,0
  4486.2    0.05       0  4980.0   0.035       0  4986.0    0.05       0
  5000.6    0.16       0  5084.9    0.12       0  5174.6    0.05       0
Bank Sta=4980,4986
Exp/Cntr=0.3,0.1

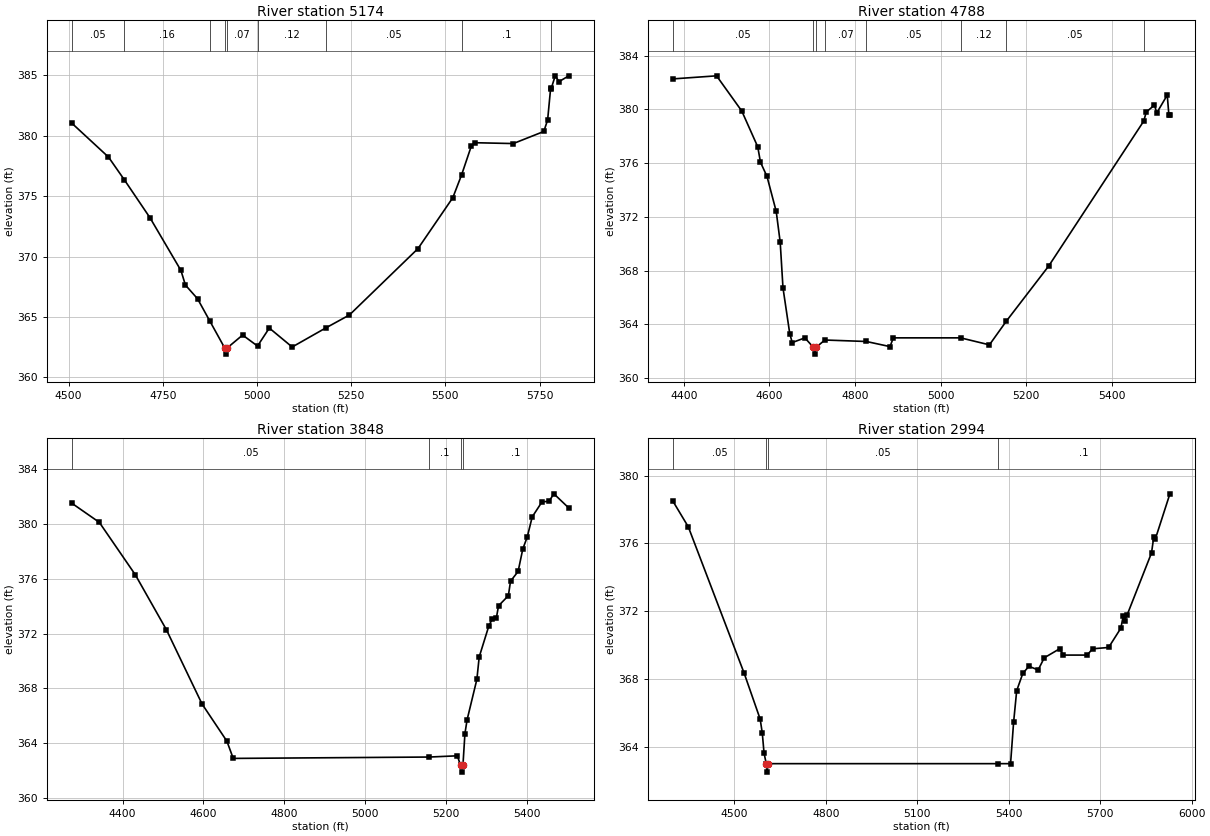
Type RM Length L Ch R = 1,5174,386,386,386
BEGIN DESCRIPTION:
SASSAFRAS BRANCH 6.0
END DESCRIPTION:
XS GIS Cut Line= 3
      3531589.03     10512618.11      3531237.47     10512804.74
      3530326.61     10512943.54
#Sta/Elev= 30
  4507.9  381.07  4606.0  378.24  4648.0  376.36  4716.0  373.22  4798.2  368.85
  4810.1  367.64  4842.2  366.51  4874.7  364.67  4914.5  362.42  4917.2  361.92
  4920.5  362.42  4961.9  363.50  5001.4  362.59  5032.7  364.08  5093.4  362.51
  5182.6  364.09  5245.2  365.16  5427.2  370.66  5519.7  374.88  5543.1  376.78
  5568.9  379.17  5578.1  379.43  5680.1  379.36  5761.0  380.36  5771.2  381.31
  5778.9  383.84  5780.8  383.93  5791.4  384.97  5801.5  384.49  5827.3  384.97
#Mann=9,-1,0
  4507.9    0.05       0  4648.0    0.16       0  4874.7    0.07       0
  4914.5    0.07       0  4920.5    0.07       0  5001.4    0.12       0
  5182.6    0.05       0  5543.1     0.1       0  5780.8    0.05       0
Bank Sta=4914.5,4920.5
Exp/Cntr=0.3,0.1

Type RM Length L Ch R = 1,4788,940,940,940
BEGIN DESCRIPTION:
SASSAFRAS BRANCH 5.0
END DESCRIPTION:
XS GIS Cut Line= 3
      3531450.13     10512257.87      3531011.78     10512509.60
      3530399.78     10512748.32
#Sta/Elev= 30
  4373.7  382.26  4476.3  382.49  4535.3  379.87  4572.6  377.21  4579.0  376.06
  4594.2  375.01  4615.8  372.40  4625.1  370.11  4631.6  366.72  4647.4  363.32
  4653.2  362.65  4682.8  363.00  4702.8  362.29  4705.6  361.79  4708.8  362.29
  4729.5  362.84  4826.5  362.73  4881.7  362.35  4889.6  363.00  5046.9  363.00
  5114.2  362.48  5153.9  364.25  5252.7  368.34  5474.9  379.12  5480.9  379.80
  5500.0  380.31  5505.4  379.73  5529.9  381.06  5533.8  379.55  5536.1  379.55
#Mann=8,-1,0
  4373.7    0.05       0  4702.8   0.033       0  4708.8    0.05       0
  4729.5    0.07       0  4826.5    0.05       0  5046.9    0.12       0
  5153.9    0.05       0  5474.9     0.1       0
Bank Sta=4702.8,4708.8
Exp/Cntr=0.3,0.1

Type RM Length L Ch R = 1,3848,854,854,854
BEGIN DESCRIPTION:
SASSAFRAS BRANCH 3.0
END DESCRIPTION:
XS GIS Cut Line= 3
      3531425.14     10511947.37      3530886.98     10511699.99
      3530296.90     10511461.36
#Sta/Elev= 30
  4273.9  381.52  4342.6  380.11  4431.3  376.30  4508.4  372.28  4596.4  366.87
  4657.8  364.16  4673.5  362.90  5157.9  363.00  5227.4  363.09  5235.2  362.40
  5238.0  361.90  5241.2  362.40  5246.1  364.71  5251.5  365.72  5275.6  368.66
  5281.4  370.30  5305.1  372.55  5313.7  373.07  5323.8  373.15  5329.2  374.03
  5353.4  374.76  5358.8  375.82  5377.5  376.53  5389.2  378.18  5400.0  379.03
  5412.4  380.51  5436.5  381.60  5453.9  381.65  5466.0  382.19  5502.7  381.16
#Mann=4,-1,0
  4273.9    0.05       0  5157.9     0.1       0  5235.2   0.033       0
  5241.2     0.1       0
Bank Sta=5235.2,5241.2
Exp/Cntr=0.3,0.1

Type RM Length L Ch R = 1,2994,0,0,0
BEGIN DESCRIPTION:
SASSAFRAS BRANCH 1.0
END DESCRIPTION:
XS GIS Cut Line= 4
      3531592.12     10511541.66      3531289.56     10511005.26
      3530928.88     10510695.32      3530392.06     10510641.64
#Sta/Elev= 30
  4297.7  378.52  4349.0  376.98  4532.4  368.33  4584.7  365.63  4591.7  364.80
  4597.4  363.63  4604.6  363.00  4607.3  362.50  4610.6  363.00  5363.3  363.00
  5406.0  363.00  5416.0  365.45  5426.1  367.31  5446.2  368.33  5466.3  368.75
  5496.4  368.53  5516.5  369.25  5566.8  369.78  5579.3  369.41  5657.2  369.41
  5674.8  369.78  5727.6  369.86  5767.8  371.00  5775.3  371.70  5780.3  371.45
  5787.9  371.76  5868.3  375.44  5875.8  376.40  5880.8  376.26  5928.6  378.93
#Mann=4,-1,0
  4297.7    0.05       0  4604.6   0.033       0  4610.6    0.05       0
  5363.3     0.1       0
Bank Sta=4604.6,4610.6
Exp/Cntr=0.3,0.1

Chan Stop Cuts=-1