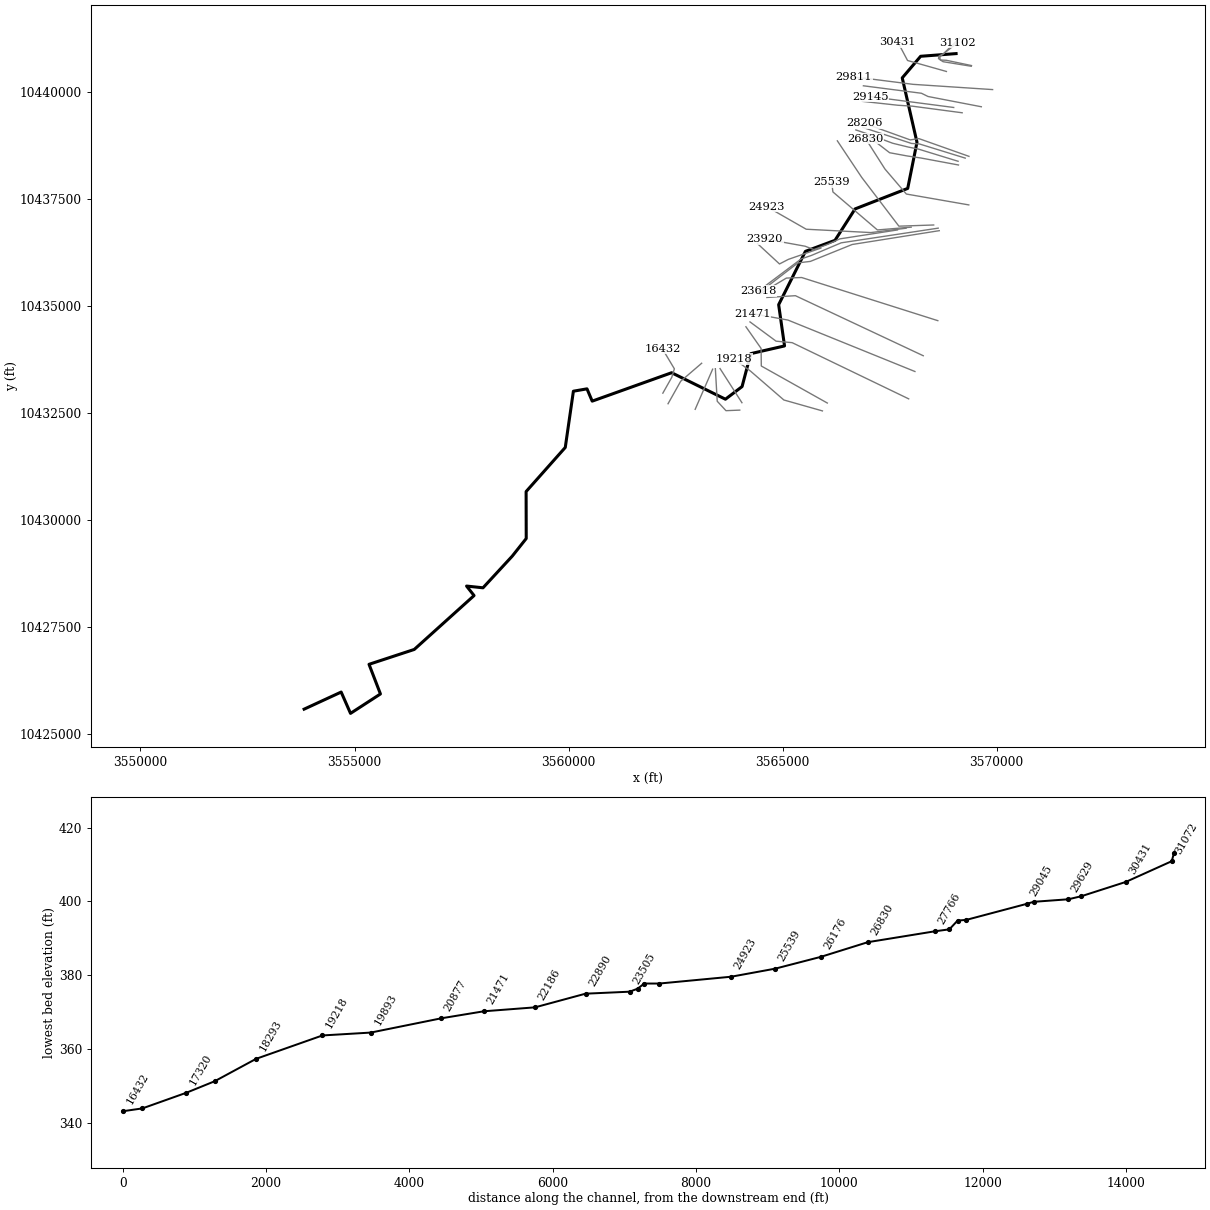
--- SOUR BRANCH.prj (project) ---

Proj Title=SOUR BRANCH Base Level Engineering
Current Plan=p01
Default Exp/Contr=0.3,0.1
English Units
Geom File=g01
Flow File=f01
Plan File=p01
Y Axis Title=Elevation
X Axis Title(PF)=Main Channel Distance
X Axis Title(XS)=Station
BEGIN DESCRIPTION:
SOUR BRANCH
END DESCRIPTION:
DSS Export Rating Curves= 0
DSS Export Rating Curve Sorted= 0
DSS Export Volume Flow Curves= 0
DXF OffsetX= 0
DXF OffsetY= 0
DXF ScaleX= 1
DXF ScaleY= 10

--- SOUR BRANCH.p01 (plan) ---

Plan Title=Multiple Run
Short Identifier=Multiple
Geom File=g01
Flow File=f01
Subcritical Flow
K Sum by GR= 0
Std Step Tol= 0.01
Critical Tol= 0.01
Num of Std Step Trials= 20
Max Error Tol= 0.3
Flow Tol Ratio= 0.001
Split Flow NTrial= 30
Split Flow Tol= 0.02
Split Flow Ratio= 0.02
Log Output Level= 0
Friction Slope Method= 1
Unsteady Friction Slope Method= 2
Unsteady Bridges Friction Slope Method= 1
Parabolic Critical Depth
Global Vel Dist=  1 , 1 , 1
Global Log Level= 0
CheckData=True
Encroach Param= -1, 0, 0, 0
BEGIN DESCRIPTION:
Multiple Run
END DESCRIPTION:

--- SOUR BRANCH.f01 (steady flow) ---

Flow Title=Multiple
Program Version=4.10
Number of Profiles= 7
Profile Names=10-year,25-year,50-year,1pct_min,100-year,1pct_plu,500-year
River Rch & RM=SOUR BRANCH,Reach-1         ,31102
     252     314     359     301     408     551     522
River Rch & RM=SOUR BRANCH,Reach-1         ,29145
     388     499     585     501     678     916     905
River Rch & RM=SOUR BRANCH,Reach-1         ,26176
    1196    1649    2022    1806    2442    3303    3556
River Rch & RM=SOUR BRANCH,Reach-1         ,23618
    1372    1901    2338    2094    2832    3831    4147
River Rch & RM=SOUR BRANCH,Reach-1         ,17320
    1886    2656    3303    2988    4041    5465    6038
River Rch & RM=SOUR BRANCH,Reach-1         ,16705
    2771    3985    5028    4611    6236    8433    9576
River Rch & RM=SOUR BRANCH,Reach-1         ,11158
    2947    4237    5343    4896    6621    8954   10149
Boundary for River Rch & Prof#=SOUR BRANCH,Reach-1         , 1
Up Type= 0
Dn Type= 3
Dn Slope=0.005
Boundary for River Rch & Prof#=SOUR BRANCH,Reach-1         , 2
Up Type= 0
Dn Type= 3
Dn Slope=0.005
Boundary for River Rch & Prof#=SOUR BRANCH,Reach-1         , 3
Up Type= 0
Dn Type= 3
Dn Slope=0.005
Boundary for River Rch & Prof#=SOUR BRANCH,Reach-1         , 4
Up Type= 0
Dn Type= 3
Dn Slope=0.005
Boundary for River Rch & Prof#=SOUR BRANCH,Reach-1         , 5
Up Type= 0
Dn Type= 3
Dn Slope=0.005
Boundary for River Rch & Prof#=SOUR BRANCH,Reach-1         , 6
Up Type= 0
Dn Type= 3
Dn Slope=0.005
Boundary for River Rch & Prof#=SOUR BRANCH,Reach-1         , 7
Up Type= 0
Dn Type= 3
Dn Slope=0.005
DSS Import GetInterval= 0
DSS Import GetPeak= 0
DSS Import FillOption= 0

--- SOUR BRANCH.g01 (geometry) ---

Geom Title=Existing Conditions
Program Version=4.10

River Reach=SOUR BRANCH     ,Reach-1
Reach XY= 30
      3569051.09     10440904.11      3568222.94     10440841.56
      3567793.26     10440336.87      3568137.45     10438833.42
       3567920.9     10437755.22      3566691.23     10437276.02
      3566222.32      10436542.3      3565531.68     10436285.07
      3564906.53     10435039.21      3565043.93     10434075.87
      3564254.76     10433895.67       3564051.8     10433126.11
      3563663.37     10432831.41      3562406.35     10433449.99
      3560551.21     10432786.18      3560429.58     10433073.59
      3560111.99     10433018.46      3559922.14     10431704.29
       3559007.5      10430674.2      3559010.24     10429577.41
      3558682.98       10429165.      3558000.69     10428426.29
      3557616.14     10428467.09      3557792.01     10428244.87
      3556394.94     10426986.31      3555338.32     10426638.85
      3555604.99     10425946.56      3554906.14     10425493.06
      3554687.55     10425991.06      3553822.11     10425591.64

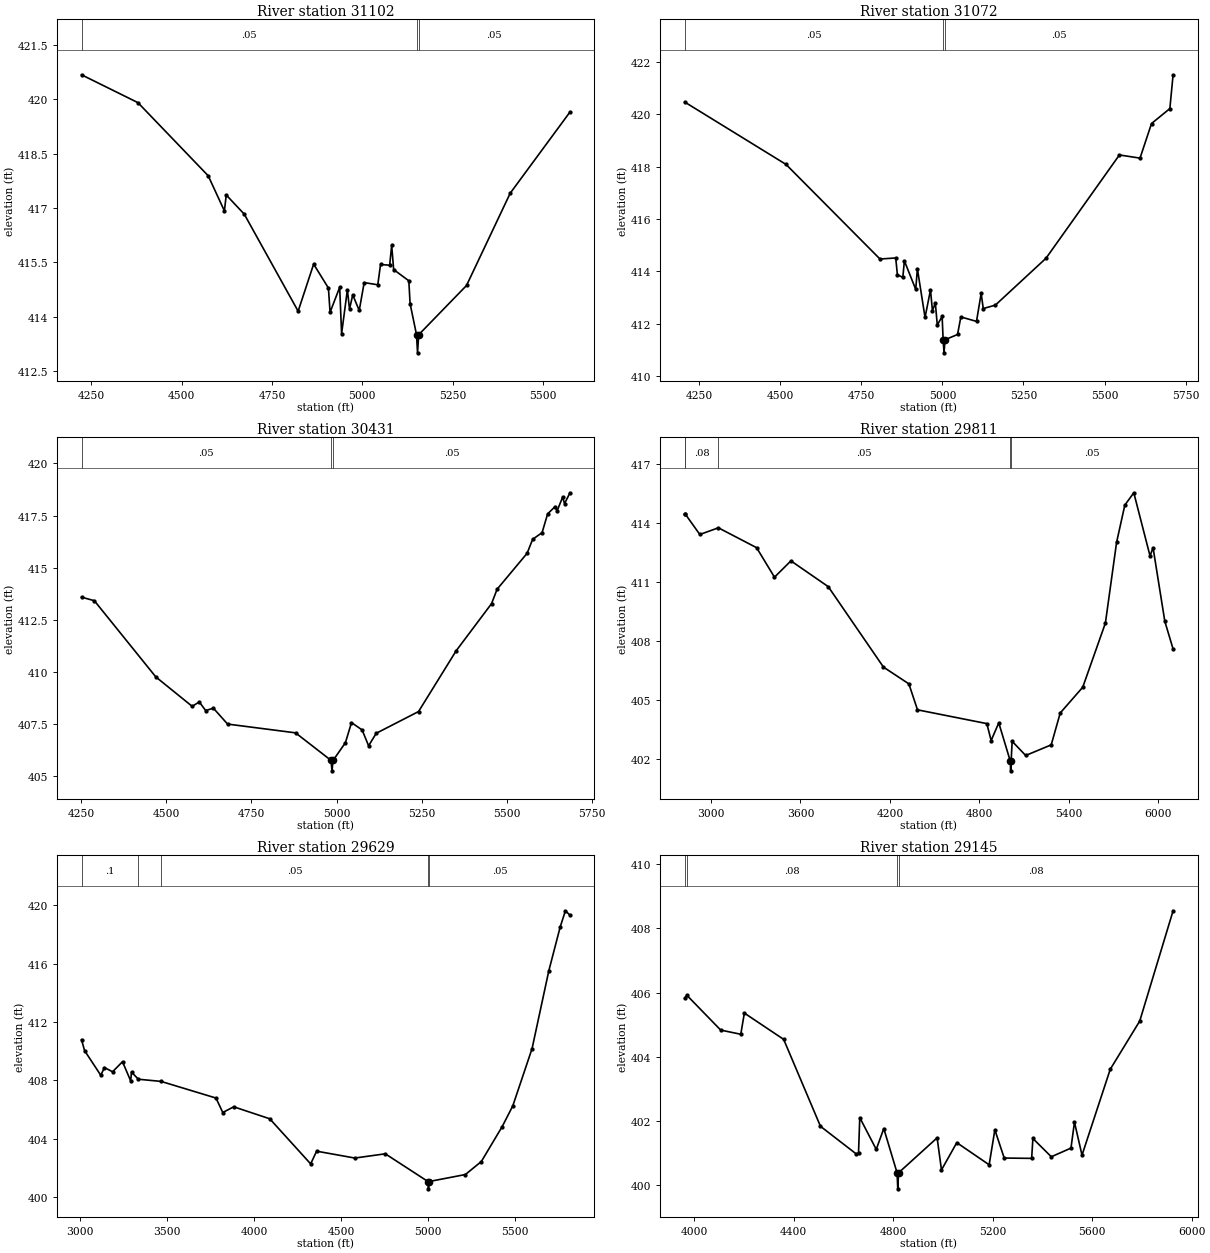
Type RM Length L Ch R = 1 ,31102   ,30,30,30
BEGIN DESCRIPTION:
SOUR BRANCH 45.1
END DESCRIPTION:
XS GIS Cut Line= 6
      3569411.06     10440624.83      3568821.26     10440748.52
      3568685.84     10440753.72      3568667.61     10440809.71
      3568696.26     10440852.68      3569086.59     10441160.47
#Sta/Elev= 30
  4222.9  420.68  4379.1  419.91  4573.6  417.89  4618.4  416.92  4623.5  417.36
  4673.4  416.83  4822.5  414.15  4865.4  415.45  4906.3  414.79  4910.9  414.12
  4937.5  414.81  4942.8  413.53  4958.8  414.74  4964.7  414.21  4973.7   414.6
  4991.6  414.17  5005.3  414.94    5043  414.88  5050.6  415.44  5075.9  415.42
  5081.4  415.97  5086.9   415.3  5128.9  414.99  5132.4  414.36  5150.2   413.5
    5153     413  5156.2   413.5  5288.6  414.86  5409.6  417.41  5574.9  419.65
#Mann= 3 ,-1 , 0
  4222.9     .05       0  5150.2     .03       0  5156.2     .05       0
Bank Sta=5150.2,5156.2
XS Rating Curve= 0 ,0
Exp/Cntr=0.3,0.1

Type RM Length L Ch R = 1 ,31072   ,641,641,641
BEGIN DESCRIPTION:
SOUR BRANCH 45.2
END DESCRIPTION:
XS GIS Cut Line= 6
      3569404.95     10440608.63      3568746.34     10440714.97
      3568640.01     10440787.67      3568650.86     10440847.34
      3568756.11      10440901.6      3569127.18     10441260.74
#Sta/Elev= 30
  4205.2  420.46  4517.7  418.08  4807.5  414.47  4856.1  414.51  4861.2  413.87
    4878  413.77  4882.8   414.4  4917.8  413.31  4922.9   414.1  4946.5  412.24
  4963.3  413.29  4969.3   412.5  4978.2  412.79  4984.3  411.95  4999.2  412.28
  5002.3  411.39    5005  410.89  5008.3  411.39  5046.7  411.59  5056.9  412.26
  5105.2  412.09  5119.6  413.16    5126  412.58  5163.3  412.71  5319.6   414.5
  5545.9  418.44  5609.5  418.32    5645  419.64  5701.5  420.21  5711.5   421.5
#Mann= 3 ,-1 , 0
  4205.2     .05       0  5002.3     .03       0  5008.3     .05       0
Bank Sta=5002.3,5008.3
XS Rating Curve= 0 ,0
Exp/Cntr=0.3,0.1

Type RM Length L Ch R = 1 ,30431   ,620,620,620
BEGIN DESCRIPTION:
SOUR BRANCH 45.0
END DESCRIPTION:
XS GIS Cut Line= 3
      3568824.69     10440486.81      3567917.61     10440742.87
      3567687.64     10441176.77
#Sta/Elev= 30
  4251.3  413.59  4288.9  413.42  4469.3  409.77  4576.1  408.36  4596.9  408.57
  4615.6  408.16  4638.4  408.27    4680  407.51  4879.5  407.09  4983.7  405.77
  4986.4  405.27  4989.7  405.77  5025.9  406.62  5043.7  407.58  5074.9  407.23
  5093.9  406.47  5116.4  407.07  5240.5  408.11  5350.9  411.02  5454.8  413.28
  5471.1  413.97  5559.1  415.69  5575.4  416.36  5603.1  416.68  5619.4  417.58
  5641.4  417.93  5647.1  417.72  5663.4  418.38  5669.1  418.07  5684.9  418.59
#Mann= 3 ,-1 , 0
  4251.3     .05       0  4983.7     .03       0  4989.7     .05       0
Bank Sta=4983.7,4989.7
XS Rating Curve= 0 ,0
Exp/Cntr=0.3,0.1

Type RM Length L Ch R = 1 ,29811   ,182,182,182
BEGIN DESCRIPTION:
SOUR BRANCH 44.3
END DESCRIPTION:
XS GIS Cut Line= 6
      3569903.71     10440063.67      3568046.91     10440186.07
       3566916.7      10440329.3       3566789.1     10440328.43
      3566802.12     10440332.77      3566667.53     10440358.82
#Sta/Elev= 30
  2822.9  414.45  2826.7  414.45  2924.7  413.41  3049.2  413.75  3305.6  412.74
  3425.8  411.24  3536.1  412.07  3786.6  410.76  4157.4  406.67  4327.8  405.82
  4385.7   404.5  4851.1   403.8  4880.1  402.94  4931.2  403.84  5008.3   401.9
  5011.1   401.4  5014.3   401.9  5021.2   402.9  5111.9  402.18  5283.3  402.72
  5343.8  404.34    5495  405.65    5647  408.91  5722.1  413.01  5777.2   414.9
  5837.6  415.53  5946.6  412.32  5966.9  412.74  6045.8     409  6101.4  407.59
#Mann= 5 ,-1 , 0
  2822.9     .15       0  2826.7     .08       0  3049.2     .05       0
  5008.3     .03       0  5014.3     .05       0
Bank Sta=5008.3,5014.3
XS Rating Curve= 0 ,0
Exp/Cntr=0.3,0.1

Type RM Length L Ch R = 1 ,29629   ,484,484,484
BEGIN DESCRIPTION:
SOUR BRANCH 44.2
END DESCRIPTION:
XS GIS Cut Line= 4
      3569640.68     10439662.63      3568395.87     10439902.21
      3568242.22     10439977.73      3566886.25     10440152.11
#Sta/Elev= 30
  3007.9  410.79  3025.4  410.04  3118.5  408.35  3139.5  408.88  3186.3  408.59
  3243.3  409.28  3290.1  407.97  3295.2  408.57  3334.2  408.08  3464.8  407.93
  3780.4  406.79  3819.4   405.8  3882.2  406.19  4089.2  405.37  4324.3  402.28
  4358.5  403.15    4578  402.68  4753.1  402.97  4998.4  401.07  5001.2  400.57
  5004.4  401.07  5213.1  401.55  5304.8  402.44  5424.9  404.84  5485.4  406.25
  5596.3  410.18  5692.3   415.5  5757.6   418.5  5787.8  419.62  5813.9  419.32
#Mann= 5 ,-1 , 0
  3007.9      .1       0  3334.2     .08       0  3464.8     .05       0
  4998.4     .03       0  5004.4     .05       0
Bank Sta=4998.4,5004.4
XS Rating Curve= 0 ,0
Exp/Cntr=0.3,0.1

Type RM Length L Ch R = 1 ,29145   ,100,100,100
BEGIN DESCRIPTION:
SOUR BRANCH 44.0
END DESCRIPTION:
XS GIS Cut Line= 2
      3568995.66     10439645.71      3567049.05     10439899.61
#Sta/Elev= 30
  3962.3  405.82  3970.5  405.92  4107.1  404.83  4187.8   404.7  4202.2  405.36
  4360.2  404.54  4508.1  401.83  4651.6  400.97    4661  400.99  4666.1   402.1
  4732.3  401.11  4762.6  401.76    4816  400.38  4818.8  399.88    4822  400.38
    4977  401.47  4994.5  400.47    5056  401.32  5186.1  400.63    5209  401.72
  5246.6  400.84  5356.9  400.83  5361.9  401.45  5435.9  400.88  5514.9  401.15
    5529  401.96  5559.3  400.93  5672.9  403.61  5791.2  405.11  5925.4  408.55
#Mann= 4 ,-1 , 0
  3962.3     .05       0  3970.5     .08       0    4816     .07       0
    4822     .08       0
Bank Sta=4816,4822
XS Rating Curve= 0 ,0
Exp/Cntr=0.3,0.1

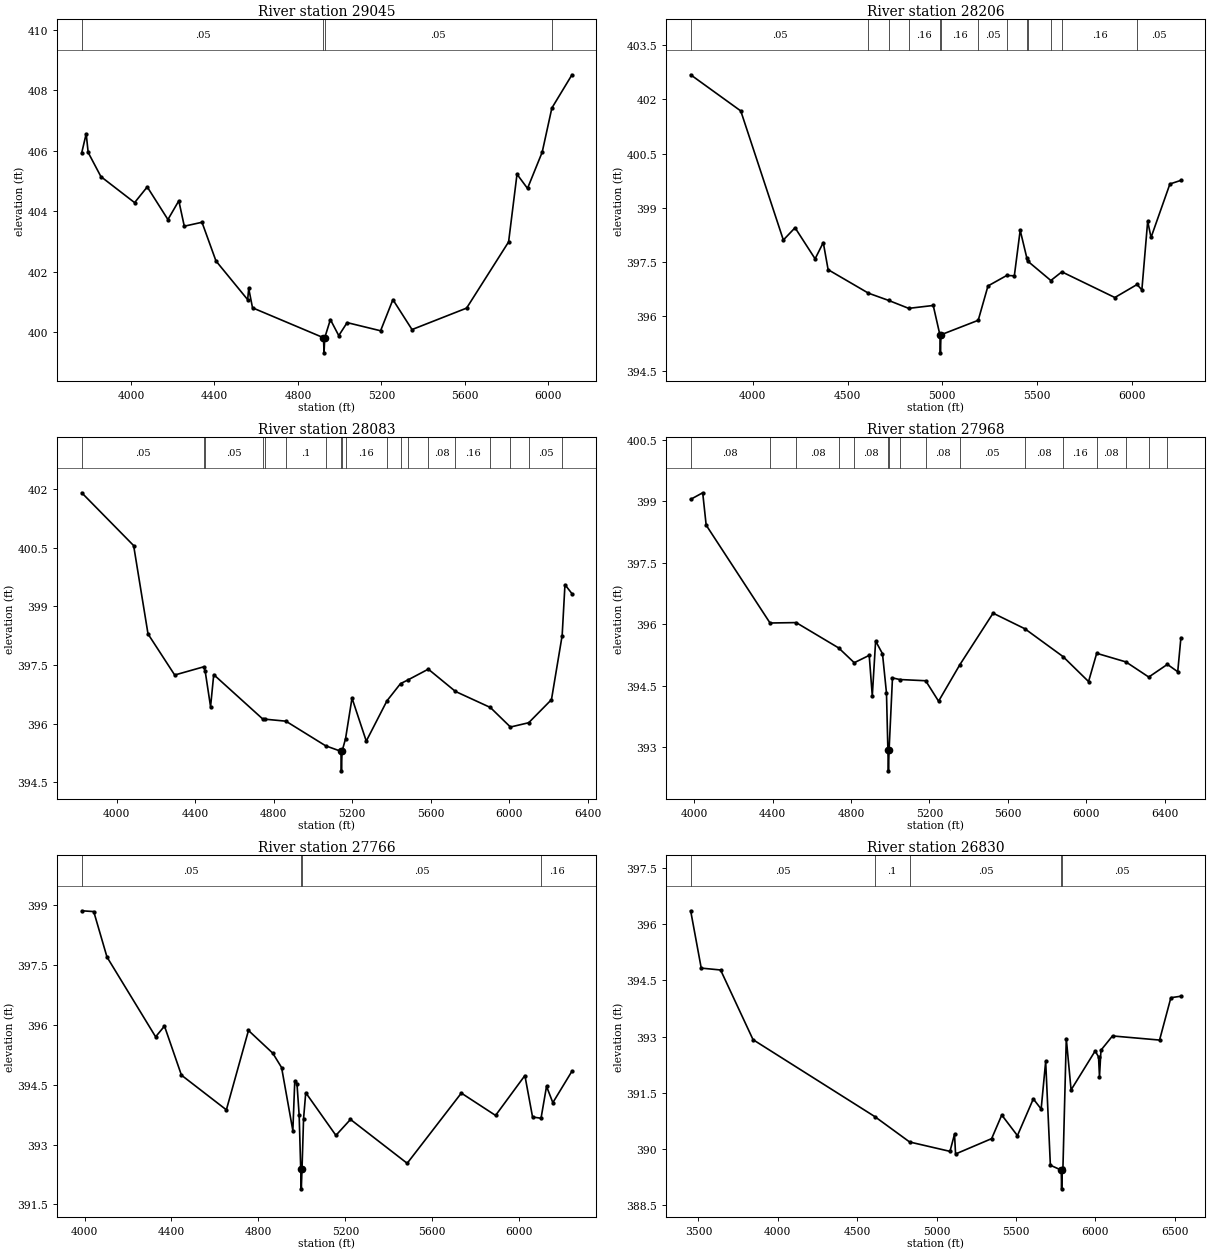
Type RM Length L Ch R = 1 ,29045   ,839,839,839
BEGIN DESCRIPTION:
SOUR BRANCH 44.1
END DESCRIPTION:
XS GIS Cut Line= 4
       3569193.2       10439522.      3568029.98     10439676.08
      3567691.44     10439697.79      3566860.24     10439788.94
#Sta/Elev= 30
  3764.3  405.93  3785.6  406.56  3795.1  405.94  3856.2  405.14  4017.6  404.28
  4078.1   404.8  4177.2  403.72  4229.4  404.34  4255.6   403.5  4340.4  403.63
  4407.4  402.35  4559.2  401.07  4564.3  401.44  4582.5   400.8  4922.5  399.81
  4925.2  399.31  4928.5  399.81  4955.6  400.41  4995.7  399.88  5035.8  400.31
  5196.1  400.04  5255.1  401.07  5346.7  400.08  5608.2  400.79  5809.4  402.98
  5849.7  405.22    5900  404.75  5970.4  405.95  6016.7  407.41  6113.1  408.51
#Mann= 4 ,-1 , 0
  3764.3     .05       0  4922.5     .03       0  4928.5     .05       0
  6016.7     .08       0
Bank Sta=4922.5,4928.5
XS Rating Curve= 0 ,0
Exp/Cntr=0.3,0.1

Type RM Length L Ch R = 1 ,28206   ,123,123,123
BEGIN DESCRIPTION:
SOUR BRANCH 43.1
END DESCRIPTION:
XS GIS Cut Line= 4
      3569351.64     10438504.19      3568181.89     10438918.71
      3567980.07     10438888.32      3566903.64     10439276.79
#Sta/Elev= 30
  3671.4  402.68  3936.1  401.68    4161  398.11  4222.8  398.45  4328.7  397.59
  4371.9  398.04  4397.5  397.29  4610.5  396.64  4716.9  396.44  4823.2  396.22
  4952.7   396.3  4987.8  395.49  4990.5  394.99  4993.8  395.49  5190.3  395.89
  5241.9  396.84  5341.1  397.13  5381.1  397.12    5412  398.38  5447.7   397.6
    5451  397.53  5573.9  396.99    5632  397.23    5912  396.52  6029.4  396.88
  6054.7  396.73  6085.4  398.63  6103.1  398.18  6202.8  399.66  6260.9  399.76
#Mann= 13 ,-1 , 0
  3671.4     .05       0  4610.5     .08       0  4716.9      .1       0
  4823.2     .16       0  4987.8     .07       0  4993.8     .16       0
  5190.3     .05       0  5341.1     .16       0  5447.7     .05       0
    5451     .16       0  5573.9     .05       0    5632     .16       0
  6029.4     .05       0
Bank Sta=4987.8,4993.8
XS Rating Curve= 0 ,0
Exp/Cntr=0.3,0.1

Type RM Length L Ch R = 1 ,28083   ,115,115,115
BEGIN DESCRIPTION:
SOUR BRANCH 42.1
END DESCRIPTION:
XS GIS Cut Line= 4
      3569264.84     10438462.96      3568197.08     10438792.84
      3568008.28     10438805.86      3566876.25     10439178.87
#Sta/Elev= 30
  3821.2   401.9  4085.7  400.55    4159  398.29    4295  397.24  4442.9  397.45
    4450  397.35  4477.8  396.43  4493.9  397.25    4745  396.11    4757  396.11
  4861.7  396.06  5064.4  395.43    5142  395.29  5144.8  394.79    5148  395.29
  5165.7  395.61  5198.7  396.65  5271.4  395.55  5376.8  396.58  5445.9  397.02
  5482.2  397.11  5587.6  397.39    5726  396.82  5903.9  396.41  6006.2  395.91
  6099.2  396.02  6215.3  396.61  6269.8  398.25  6284.1  399.55  6319.9  399.32
#Mann= 19 ,-1 , 0
  3821.2     .05       0  4442.9     .08       0    4450     .05       0
    4745     .08       0    4757     .05       0  4861.7      .1       0
  5064.4     .08       0    5142     .07       0    5148     .08       0
  5165.7     .16       0  5376.8     .08       0  5445.9     .16       0
  5482.2     .05       0  5587.6     .08       0    5726     .16       0
  5903.9     .08       0  6006.2     .16       0  6099.2     .05       0
  6269.8     .15       0
Bank Sta=5142,5148
XS Rating Curve= 0 ,0
Exp/Cntr=0.3,0.1

Type RM Length L Ch R = 1 ,27968   ,202,202,202
BEGIN DESCRIPTION:
SOUR BRANCH 43.0
END DESCRIPTION:
XS GIS Cut Line= 6
      3569097.68     10438389.19      3568173.58     10438673.11
      3567943.18     10438719.05      3567569.91      10438810.2
      3567023.19     10439014.78      3566709.94     10439121.25
#Sta/Elev= 30
    3982  399.05  4043.4  399.21  4061.1  398.42  4386.9  396.03  4520.2  396.04
  4737.2  395.42  4816.4  395.06  4892.7  395.24  4908.4  394.25  4925.4  395.59
  4960.4  395.28  4980.8  394.32    4988  392.92  4990.8  392.42    4994  392.92
  5011.4  394.69  5048.2  394.65  5180.7  394.62  5246.5  394.12  5354.8  395.01
  5524.5  396.27  5686.4  395.89  5881.3  395.21  6011.5   394.6    6053  395.29
    6202  395.08  6318.6  394.71  6413.6  395.02  6466.3  394.84  6482.5  395.67
#Mann= 16 ,-1 , 0
    3982     .08       0  4386.9     .05       0  4520.2     .08       0
  4737.2     .05       0  4816.4     .08       0    4988     .07       0
    4994     .08       0  5048.2     .05       0  5180.7     .08       0
  5354.8     .05       0  5686.4     .08       0  5881.3     .16       0
    6053     .08       0    6202     .05       0  6318.6     .15       0
  6413.6      .1       0
Bank Sta=4988,4994
XS Rating Curve= 0 ,0
Exp/Cntr=0.3,0.1

Type RM Length L Ch R = 1 ,27766   ,936,936,936
BEGIN DESCRIPTION:
SOUR BRANCH 42.0
END DESCRIPTION:
XS GIS Cut Line= 5
      3569106.33     10438302.39      3568231.81     10438465.15
      3567910.63     10438512.89       3567498.3     10438588.84
      3567005.84     10438969.28
#Sta/Elev= 30
    3987  398.86  4042.2  398.84  4103.2   397.7    4327   395.7  4367.7  395.97
  4445.7  394.74  4652.5  393.87  4754.2  395.86  4866.1  395.29  4906.6  394.93
  4958.4  393.35  4967.2  394.59  4977.3  394.53  4987.4  393.74  4994.6  392.39
  4997.3  391.89  5000.6  392.39  5007.7  393.65  5017.7   394.3  5156.5  393.23
  5223.6  393.63  5484.5  392.53  5733.6  394.29  5891.2  393.73  6026.1  394.73
  6061.4  393.69  6100.4  393.66  6125.7  394.46  6154.7  394.05  6242.8  394.84
#Mann= 4 ,-1 , 0
    3987     .05       0  4994.6     .03       0  5000.6     .05       0
  6100.4     .16       0
Bank Sta=4994.6,5000.6
XS Rating Curve= 0 ,0
Exp/Cntr=0.3,0.1

Type RM Length L Ch R = 1 ,26830   ,654,654,654
BEGIN DESCRIPTION:
SOUR BRANCH 41.0
END DESCRIPTION:
XS GIS Cut Line= 4
      3569347.76     10437369.82      3567888.64       10437624.
       3567389.5     10438207.77      3566938.91     10438914.96
#Sta/Elev= 30
  3450.8  396.36  3517.4  394.83  3639.3  394.78  3843.8  392.92  4609.8  390.87
  4830.1  390.19  5084.1  389.94  5112.7   390.4  5119.2  389.87  5346.5  390.28
  5410.2  390.91  5508.9  390.36  5608.9  391.34  5658.3  391.07  5686.8  392.34
  5716.4  389.57  5784.6  389.44  5787.3  388.94  5790.6  389.44  5795.5   389.5
  5816.6  392.95  5846.8  391.58  5998.6  392.62  6019.8  392.46  6025.7  391.93
    6035  392.64  6107.7  393.02  6404.1  392.91  6475.3  394.04  6538.5  394.08
#Mann= 5 ,-1 , 0
  3450.8     .05       0  4609.8      .1       0  4830.1     .05       0
  5784.6     .03       0  5790.6     .05       0
Bank Sta=5784.6,5790.6
XS Rating Curve= 0 ,0
Exp/Cntr=0.3,0.1

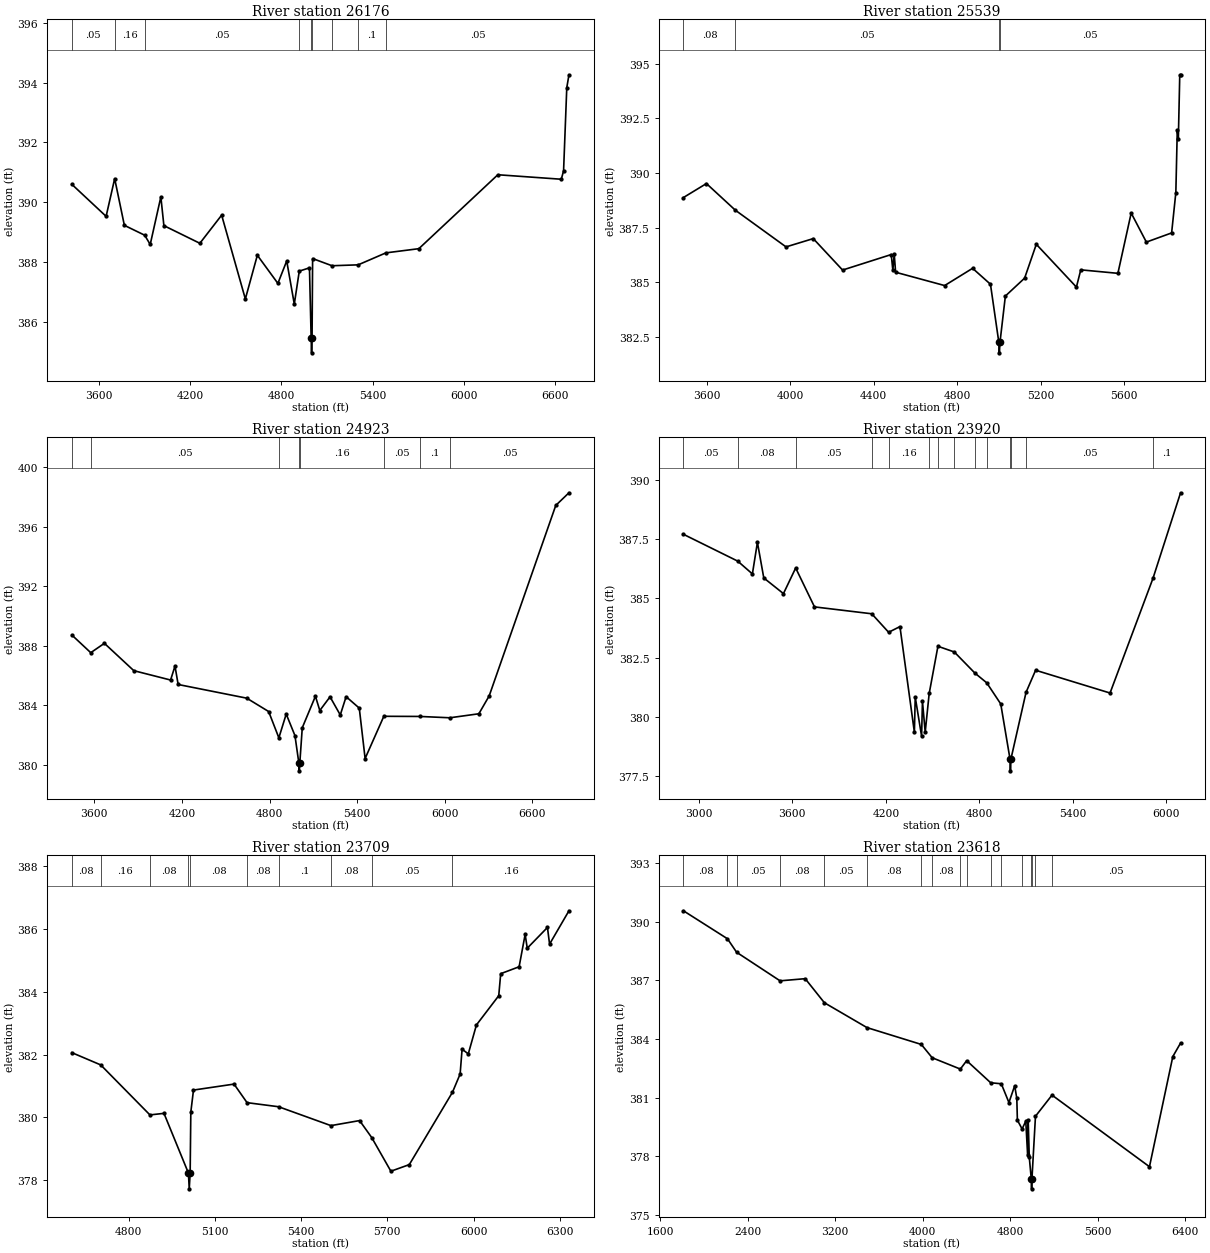
Type RM Length L Ch R = 1 ,26176   ,637,637,637
BEGIN DESCRIPTION:
SOUR BRANCH 40.2
END DESCRIPTION:
XS GIS Cut Line= 4
      3568527.59     10436901.03      3567715.08     10436873.26
      3566847.02     10438012.14      3566277.55     10438866.35
#Sta/Elev= 30
  3420.4   390.6    3646  389.53  3702.3  390.79  3766.1  389.23  3899.8   388.9
  3936.2  388.59  4006.2  390.18  4026.2  389.22  4262.9  388.63  4406.3  389.57
  4562.3  386.77  4641.2  388.23  4776.4  387.29  4834.5  388.04  4884.4   386.6
  4917.2   387.7  4984.2  387.81  4995.3  385.47  4998.1  384.97  5001.3  385.47
    5005  388.12  5132.6  387.88  5304.8  387.91  5487.2  388.31  5704.1  388.45
  6223.9  390.92  6641.5  390.77  6656.5  391.05  6677.6  393.83    6692  394.26
#Mann= 9 ,-1 , 0
  3420.4     .05       0  3702.3     .16       0  3899.8     .05       0
  4917.2      .1       0  4995.3     .07       0  5001.3      .1       0
  5132.6     .05       0  5304.8      .1       0  5487.2     .05       0
Bank Sta=4995.3,5001.3
XS Rating Curve= 0 ,0
Exp/Cntr=0.3,0.1

Type RM Length L Ch R = 1 ,25539   ,616,616,616
BEGIN DESCRIPTION:
SOUR BRANCH 40.1
END DESCRIPTION:
XS GIS Cut Line= 4
      3568001.93     10436850.15      3567212.89     10436785.05
      3566173.83     10437673.07      3566145.34     10437894.09
#Sta/Elev= 30
  3488.9  388.88  3599.1  389.52  3737.6   388.3  3980.4  386.62  4110.8     387
  4251.3  385.56  4484.4  386.27  4492.1  385.55  4498.6   386.3  4505.3  385.46
  4740.2  384.85  4874.1  385.64  4959.7  384.91  4999.5  382.27  5002.3  381.77
  5005.5  382.27  5031.1  384.37  5123.3  385.19  5179.3  386.74  5371.4  384.78
  5392.3  385.57  5570.1  385.41  5633.8  388.17  5706.5  386.84  5827.5  387.26
  5847.7  389.11  5854.6  391.97  5859.7  391.57  5866.5   394.5  5870.3   394.5
#Mann= 4 ,-1 , 0
  3488.9     .08       0  3737.6     .05       0  4999.5    .035       0
  5005.5     .05       0
Bank Sta=4999.5,5005.5
XS Rating Curve= 0 ,0
Exp/Cntr=0.3,0.1

Type RM Length L Ch R = 1 ,24923   ,1003,1003,1003
BEGIN DESCRIPTION:
SOUR BRANCH 40.0
END DESCRIPTION:
XS GIS Cut Line= 4
      3567883.53     10436825.41      3567060.62     10436723.85
       3565550.2     10436801.98      3564626.37     10437330.25
#Sta/Elev= 30
  3445.6  388.72  3575.2  387.53  3668.7  388.16  3870.2  386.32  4122.1  385.69
  4152.3  386.63  4173.9  385.39  4643.8  384.47    4794  383.57  4863.9   381.8
  4914.3   383.4  4974.2  381.95  5001.2  380.08    5004  379.58  5007.2  380.08
  5024.3  382.48  5114.4   384.6  5144.4  383.64  5214.5  384.56  5284.6  383.34
  5324.7  384.57  5414.8   383.8  5454.8  380.41    5583  383.25  5829.2  383.24
  6035.4  383.15  6234.1  383.42  6304.7  384.62    6761  397.44  6851.4  398.29
#Mann= 8 ,-1 , 0
  3445.6     .08       0  3575.2     .05       0  4863.9     .16       0
  5001.2     .07       0  5007.2     .16       0    5583     .05       0
  5829.2      .1       0  6035.4     .05       0
Bank Sta=5001.2,5007.2
XS Rating Curve= 0 ,0
Exp/Cntr=0.3,0.1

Type RM Length L Ch R = 1 ,23920   ,211,211,211
BEGIN DESCRIPTION:
SOUR BRANCH 39.1
END DESCRIPTION:
XS GIS Cut Line= 6
      3567681.25     10436784.83      3566335.79      10436576.5
       3566051.5     10436448.46      3565728.15     10436326.93
      3565524.16     10436405.06      3564586.98     10436574.85
#Sta/Elev= 30
  2901.2   387.7  3249.4  386.57  3343.7  386.03  3375.9  387.36  3416.8  385.86
  3542.9   385.2  3621.4  386.28  3742.1  384.64  4109.5  384.35  4217.8  383.57
  4290.4  383.81    4383  379.36  4388.5  380.84  4429.3  379.19  4434.8  380.66
  4452.4  379.36    4478  380.99  4534.1  382.98  4639.1  382.74  4771.3  381.85
  4847.2  381.44  4937.1  380.55  4996.5  378.23  4999.2  377.73  5002.5  378.23
  5099.5  381.04  5160.8  381.97  5638.4  381.01  5914.2  385.85  6090.8  389.45
#Mann= 14 ,-1 , 0
  2901.2     .05       0  3249.4     .08       0  3621.4     .05       0
  4109.5     .08       0  4217.8     .16       0    4478     .08       0
  4534.1     .05       0  4639.1     .16       0  4771.3     .08       0
  4847.2     .16       0  4996.5     .07       0  5002.5     .16       0
  5099.5     .05       0  5914.2      .1       0
Bank Sta=4996.5,5002.5
XS Rating Curve= 0 ,0
Exp/Cntr=0.3,0.1

Type RM Length L Ch R = 1 ,23709   ,91,91,91
BEGIN DESCRIPTION:
SOUR BRANCH 38.1
END DESCRIPTION:
XS GIS Cut Line= 4
      3565892.13     10436360.99      3565134.73     10436098.39
      3564926.25     10435990.67      3564416.47     10436461.44
#Sta/Elev= 30
  4601.9  382.06  4702.4  381.67  4873.7  380.08  4922.6  380.13  5007.7  378.23
  5010.5  377.73  5013.7  378.23    5016  380.17  5025.3  380.87  5166.4  381.06
  5211.7  380.47  5321.5  380.34  5503.6  379.74  5603.4   379.9  5645.6  379.36
  5712.3  378.29  5776.4   378.5  5926.6   380.8  5953.3  381.38  5960.1  382.17
  5981.7  382.02    6010  382.94  6087.7  383.87  6094.5  384.57  6158.6  384.79
  6179.6  385.82  6186.9  385.38  6257.2  386.04  6264.6  385.51  6332.1  386.57
#Mann= 10 ,-1 , 0
  4601.9     .08       0  4702.4     .16       0  4873.7     .08       0
  5007.7     .07       0  5013.7     .08       0  5211.7     .08       0
  5321.5      .1       0  5503.6     .08       0  5645.6     .05       0
  5926.6     .16       0
Bank Sta=5007.7,5013.7
XS Rating Curve= 0 ,0
Exp/Cntr=0.3,0.1

Type RM Length L Ch R = 1 ,23618   ,113,113,113
BEGIN DESCRIPTION:
SOUR BRANCH 39.0
END DESCRIPTION:
XS GIS Cut Line= 5
      3568633.32     10436827.15      3566367.69     10436484.27
      3565672.38       10436190.      3565430.19     10436106.66
      3564435.55     10435358.98
#Sta/Elev= 30
  1812.2  390.55  2214.9  389.12  2298.6  388.43  2696.1  386.97    2926  387.08
  3101.4  385.85    3491  384.58  3987.9  383.72  4087.2  383.04    4345  382.46
  4402.8  382.89  4622.7  381.76  4719.5  381.71  4789.3  380.75  4842.1  381.61
  4861.4  380.96  4866.6  379.85  4909.8   379.4  4943.5   379.8  4960.3  378.07
  4965.6  379.84  4975.3  377.97  4993.8  376.84  4996.6  376.34  4999.8  376.84
  5032.1  380.05  5183.4  381.13  6074.7  377.47  6288.3   383.1  6359.1  383.79
#Mann= 17 ,-1 , 0
  1812.2     .08       0  2214.9      .1       0  2298.6     .05       0
  2696.1     .08       0  3101.4     .05       0    3491     .08       0
  3987.9     .05       0  4087.2     .08       0    4345     .05       0
  4402.8     .08       0  4622.7     .05       0  4719.5     .08       0
  4909.8     .16       0  4993.8     .07       0  4999.8     .16       0
  5032.1     .08       0  5183.4     .05       0
Bank Sta=4993.8,4999.8
XS Rating Curve= 0 ,0
Exp/Cntr=0.3,0.1

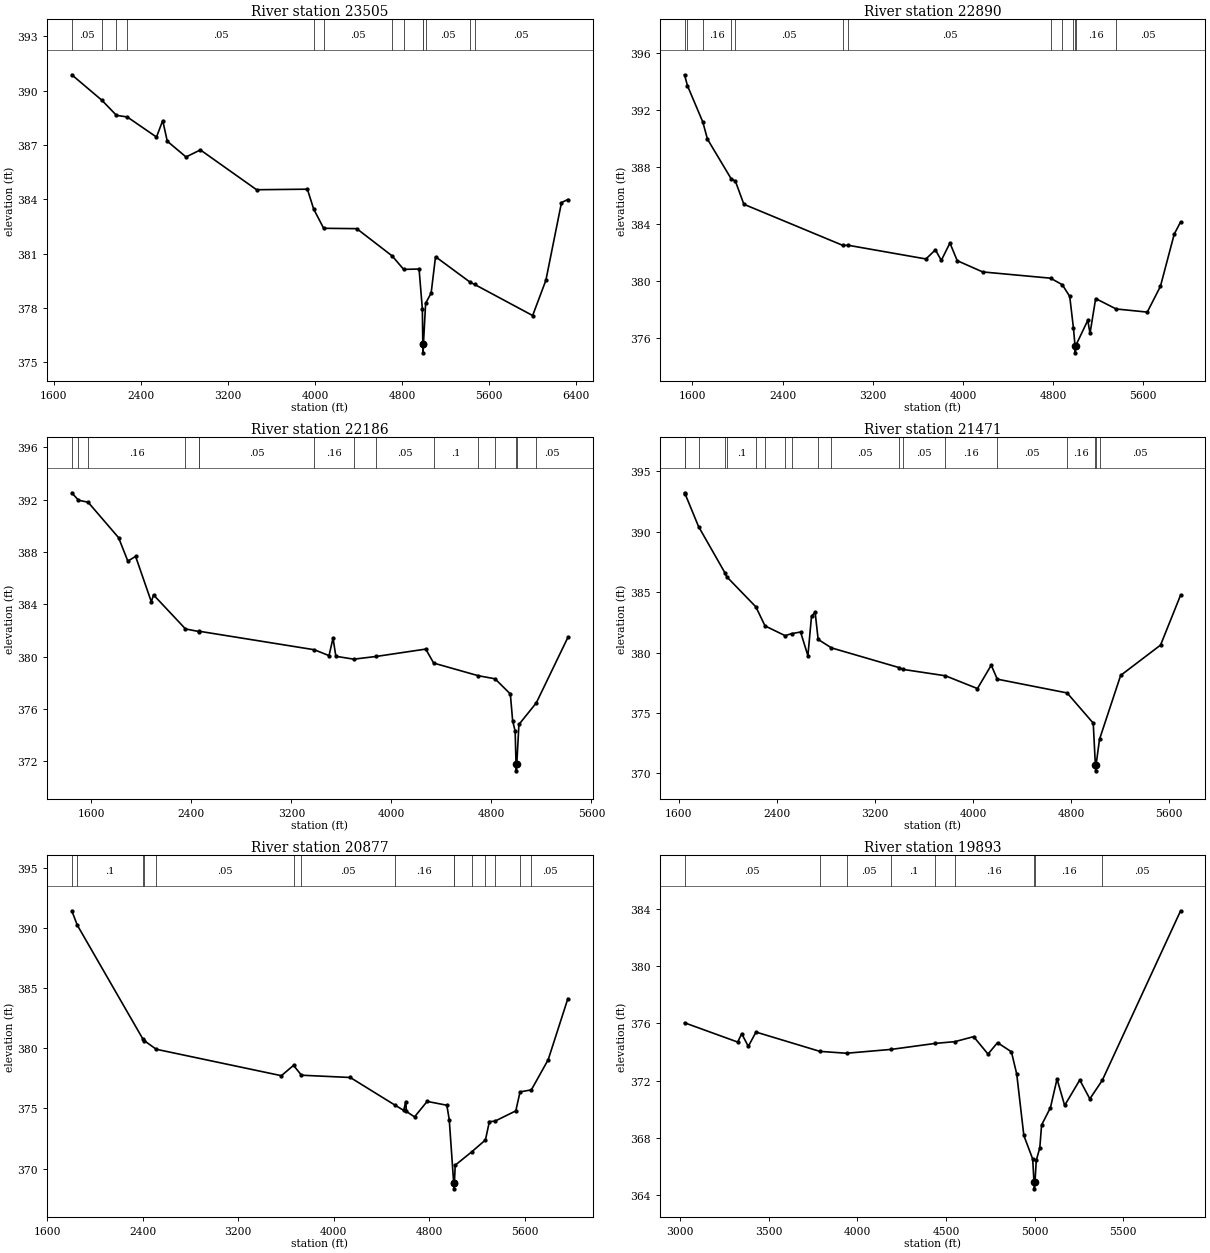
Type RM Length L Ch R = 1 ,23505   ,615,615,615
BEGIN DESCRIPTION:
SOUR BRANCH 38.0
END DESCRIPTION:
XS GIS Cut Line= 5
      3568658.16     10436768.12      3566623.77     10436445.21
      3565647.21     10436050.24      3565356.41     10436015.52
      3564445.77     10435314.58
#Sta/Elev= 30
  1766.3  390.88  2043.2  389.47  2176.3  388.64  2275.7  388.55  2544.1  387.44
  2601.3  388.35  2643.2  387.21  2815.3  386.34    2947  386.73  3463.3  384.53
  3929.7  384.56  3987.5  383.46  4079.1   382.4    4383  382.38  4708.7  380.87
  4813.6  380.13  4955.2  380.15  4985.4  377.94  4989.4  376.02  4992.1  375.52
  4995.4  376.02  5015.4  378.26    5066  378.82  5106.3  380.83  5426.7  379.41
  5464.8   379.3  5998.1  377.58  6119.7  379.53  6262.9  383.82  6321.6  383.99
#Mann= 13 ,-1 , 0
  1766.3     .05       0  2043.2     .16       0  2176.3      .1       0
  2275.7     .05       0  3987.5     .08       0  4079.1     .05       0
  4708.7     .08       0  4813.6     .16       0  4989.4     .07       0
  4995.4     .16       0  5015.4     .05       0  5426.7      .1       0
  5464.8     .05       0
Bank Sta=4989.4,4995.4
XS Rating Curve= 0 ,0
Exp/Cntr=0.3,0.1

Type RM Length L Ch R = 1 ,22890   ,704,704,704
BEGIN DESCRIPTION:
SOUR BRANCH 37.0
END DESCRIPTION:
XS GIS Cut Line= 4
       3568624.3     10434666.08      3565442.92     10435673.88
      3565087.02     10435660.86      3564478.32     10435297.96
#Sta/Elev= 30
    1530   394.5  1556.3  393.73    1692  391.19  1733.7  389.98  1943.9   387.2
  1981.1  387.04  2056.6  385.41  2935.8  382.52  2983.2  382.53  3672.2  381.57
  3756.1  382.21  3808.6  381.47  3885.1  382.69  3949.7  381.45  4175.7  380.66
  4778.4  380.22  4882.4  379.76  4948.1  378.94  4981.2  376.71  4995.1  375.48
  4997.8  374.98  5001.1  375.48  5108.2  377.26  5128.2  376.35  5178.2  378.79
  5359.9  378.06  5636.2  377.84    5753  379.65  5875.6  383.32    5932  384.17
#Mann= 13 ,-1 , 0
    1530     .08       0  1556.3     .05       0    1692     .16       0
  1943.9      .1       0  1981.1     .05       0  2935.8      .1       0
  2983.2     .05       0  4778.4      .1       0  4882.4     .05       0
  4981.2     .16       0  4995.1     .07       0  5001.1     .16       0
  5359.9     .05       0
Bank Sta=4995.1,5001.1
XS Rating Curve= 0 ,0
Exp/Cntr=0.3,0.1

Type RM Length L Ch R = 1 ,22186   ,715,715,715
BEGIN DESCRIPTION:
SOUR BRANCH 36.0
END DESCRIPTION:
XS GIS Cut Line= 3
      3568284.02     10433846.65      3565297.96      10435249.4
       3564631.3     10435207.74
#Sta/Elev= 30
  1444.3  392.52  1497.7  391.95  1574.7   391.8  1818.6  389.09  1892.5   387.3
  1954.6  387.66  2080.5  384.19  2097.8  384.72  2353.5  382.12  2460.9  381.92
  2464.8  381.94  3383.7  380.53  3501.4  380.08  3533.3  381.42  3556.1  380.03
  3699.1  379.81  3880.6  380.02  4274.8  380.58  4338.3  379.51  4693.3  378.55
  4828.9  378.31  4951.3  377.15  4969.7   375.1  4989.8  374.31  4996.8  371.78
  4999.5  371.28  5002.8  371.78  5019.8  374.82  5158.8  376.47  5411.4  381.47
#Mann= 15 ,-1 , 0
  1444.3     .08       0  1497.7      .1       0  1574.7     .16       0
  2353.5     .05       0  2460.9     .08       0  2464.8     .05       0
  3383.7     .16       0  3699.1      .1       0  3880.6     .05       0
  4338.3      .1       0  4693.3     .05       0  4828.9     .16       0
  4996.8     .07       0  5002.8     .16       0  5158.8     .05       0
Bank Sta=4996.8,5002.8
XS Rating Curve= 0 ,0
Exp/Cntr=0.3,0.1

Type RM Length L Ch R = 1 ,21471   ,594,594,594
BEGIN DESCRIPTION:
SOUR BRANCH 35.0
END DESCRIPTION:
XS GIS Cut Line= 3
      3568089.63     10433478.57      3565124.35     10434679.96
      3564291.05     10434832.73
#Sta/Elev= 30
  1645.9  393.23  1652.3   393.1  1760.6  390.43  1977.4  386.57  1990.1  386.28
  2228.4  383.78  2302.5  382.21  2466.6   381.4  2519.2  381.57  2592.7   381.7
  2652.4  379.74  2681.9  383.02  2711.4  383.33  2735.9  381.09  2844.3  380.39
  3395.4  378.76  3426.9  378.61  3773.9  378.08  4035.3  377.02  4147.9  378.96
  4196.8   377.8  4766.5  376.66  4979.8  374.16  4997.1  370.71  4999.8  370.21
  5003.1  370.71  5030.9  372.82  5203.4  378.11  5528.8  380.62  5692.5  384.76
#Mann= 19 ,-1 , 0
  1645.9     .05       0  1652.3      .1       0  1760.6     .16       0
  1977.4     .08       0  1990.1      .1       0  2228.4     .16       0
  2302.5      .1       0  2466.6     .16       0  2519.2     .12       0
  2735.9     .08       0  2844.3     .05       0  3395.4      .1       0
  3426.9     .05       0  3773.9     .16       0  4196.8     .05       0
  4766.5     .16       0  4997.1     .07       0  5003.1     .16       0
  5030.9     .05       0
Bank Sta=4997.1,5003.1
XS Rating Curve= 0 ,0
Exp/Cntr=0.3,0.1

Type RM Length L Ch R = 1 ,20877   ,984,984,984
BEGIN DESCRIPTION:
SOUR BRANCH 34.2
END DESCRIPTION:
XS GIS Cut Line= 4
      3567943.75      10432839.7      3565221.57     10434152.18
      3564846.57      10434186.9      3564237.39     10434636.86
#Sta/Elev= 30
  1805.4  391.46  1851.7  390.26  2401.3  380.78  2410.4  380.66  2513.2  379.93
  3561.3  377.73  3663.1  378.59  3729.4  377.77  4138.6  377.58  4509.6   375.3
  4586.3  374.84  4603.4  375.58  4608.9  374.75  4676.8   374.3  4782.5  375.59
  4947.4  375.27  4967.5  374.08  5004.7  368.81  5007.4  368.31  5010.7  368.81
  5017.7  370.28    5157   371.4  5270.8  372.38  5303.7  373.91  5349.5  373.94
    5525   374.8  5560.6  376.38  5655.4  376.55  5796.4  379.06  5961.4  384.15
#Mann= 15 ,-1 , 0
  1805.4     .08       0  1851.7      .1       0  2401.3     .05       0
  2410.4      .1       0  2513.2     .05       0  3663.1      .1       0
  3729.4     .05       0  4509.6     .16       0  5004.7     .07       0
  5010.7     .16       0    5157     .05       0  5270.8      .1       0
  5349.5     .05       0  5560.6      .1       0  5655.4     .05       0
Bank Sta=5004.7,5010.7
XS Rating Curve= 0 ,0
Exp/Cntr=0.3,0.1

Type RM Length L Ch R = 1 ,19893   ,675,675,675
BEGIN DESCRIPTION:
SOUR BRANCH 34.1
END DESCRIPTION:
XS GIS Cut Line= 4
      3566043.04     10432742.17      3564501.34     10433606.77
      3564496.13     10434018.23      3564141.94     10434523.47
#Sta/Elev= 30
  3026.6  376.05  3326.7   374.7  3348.7  375.29  3386.1   374.4  3429.4   375.4
  3789.7  374.05  3939.6  373.92  4192.6  374.19  4441.1  374.61  4550.3  374.73
  4656.1  375.08  4737.2  373.86  4790.7  374.66  4869.1  374.02  4899.1  372.46
  4939.1  368.17  4989.1  366.52  4996.1  364.94  4998.8  364.44  5002.1  364.94
  5009.1  366.43  5029.1  367.31  5039.1   368.9  5089.1  370.12  5126.2  372.12
  5169.1  370.27  5254.4  372.05  5311.1  370.73  5381.3  372.03  5822.7  383.88
#Mann= 9 ,-1 , 0
  3026.6     .05       0  3789.7      .1       0  3939.6     .05       0
  4192.6      .1       0  4441.1     .05       0  4550.3     .16       0
  4996.1     .07       0  5002.1     .16       0  5381.3     .05       0
Bank Sta=4996.1,5002.1
XS Rating Curve= 0 ,0
Exp/Cntr=0.3,0.1

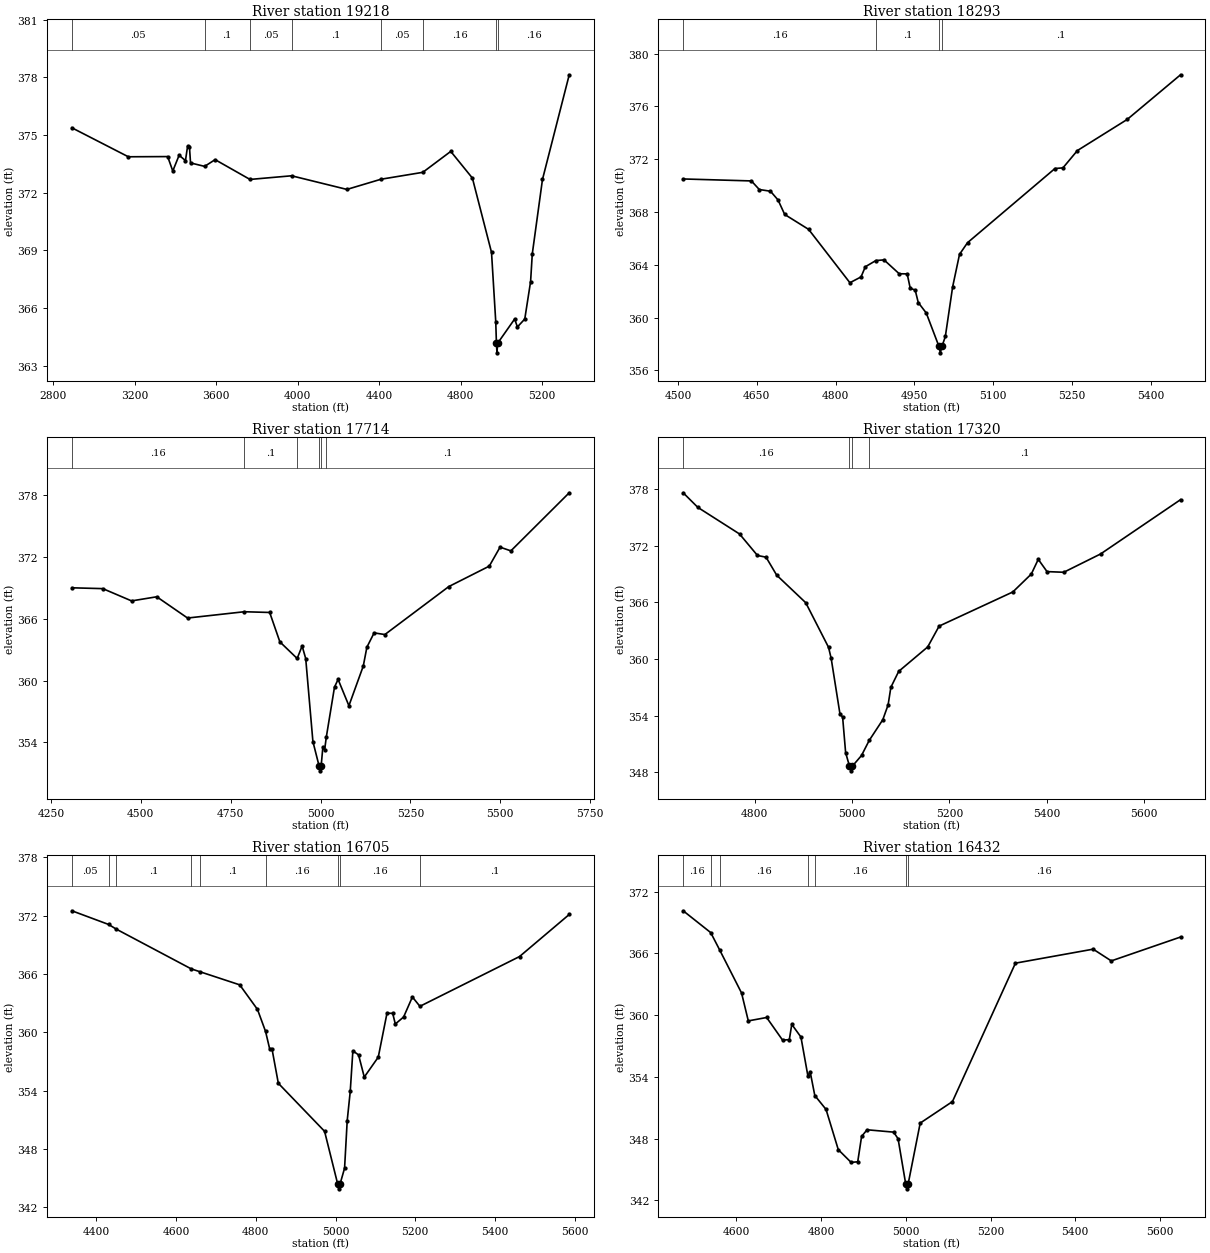
Type RM Length L Ch R = 1 ,19218   ,925,925,925
BEGIN DESCRIPTION:
SOUR BRANCH 34.0
END DESCRIPTION:
XS GIS Cut Line= 4
      3565929.03     10432558.13      3565027.98     10432813.34
      3564251.94     10433485.21      3563866.83     10433771.44
#Sta/Elev= 30
    2891  375.38  3168.4  373.87  3361.6  373.88  3386.7  373.13  3417.9  373.95
    3449  373.67  3459.4  374.42  3468.7  374.37  3473.9  373.55  3543.1  373.37
  3594.6  373.72  3765.9  372.69  3970.2  372.88  4241.9  372.17  4409.2   372.7
  4614.6  373.06  4751.9  374.15  4858.2  372.76  4952.1  368.89  4972.9  365.28
  4976.2  364.16  4978.9  363.66  4982.2  364.16  5065.6  365.42  5079.3  365.01
  5115.4  365.42    5144  367.37  5152.3  368.81  5202.4  372.69  5333.8  378.14
#Mann= 8 ,-1 , 0
    2891     .05       0  3543.1      .1       0  3765.9     .05       0
  3970.2      .1       0  4409.2     .05       0  4614.6     .16       0
  4976.2     .07       0  4982.2     .16       0
Bank Sta=4976.2,4982.2
XS Rating Curve= 0 ,0
Exp/Cntr=0.3,0.1

Type RM Length L Ch R = 1 ,18293   ,579,579,579
BEGIN DESCRIPTION:
SOUR BRANCH 33.0
END DESCRIPTION:
XS GIS Cut Line= 2
      3564048.77     10432749.57      3563537.34     10433547.06
#Sta/Elev= 30
  4509.6   370.5  4639.6  370.35  4654.6   369.7  4675.9  369.57  4690.3  368.91
    4703  367.81  4748.6  366.68  4827.2  362.64  4848.4  363.08  4856.6  363.85
  4876.7  364.32  4892.2  364.37  4921.1  363.32  4936.3  363.31  4942.2  362.21
  4951.5  362.09  4957.4  361.14  4972.6  360.35  4996.7  357.83  4999.4  357.33
  5002.7  357.83    5009  358.57  5022.9  362.33    5036  364.79  5051.2  365.67
  5217.8  371.29    5233  371.34  5260.5  372.65  5355.5  375.01    5457  378.39
#Mann= 4 ,-1 , 0
  4509.6     .16       0  4876.7      .1       0  4996.7     .07       0
  5002.7      .1       0
Bank Sta=4996.7,5002.7
XS Rating Curve= 0 ,0
Exp/Cntr=0.3,0.1

Type RM Length L Ch R = 1 ,17714   ,394,394,394
BEGIN DESCRIPTION:
SOUR BRANCH 32.0
END DESCRIPTION:
XS GIS Cut Line= 4
      3563998.18     10432576.72      3563675.89     10432563.56
      3563471.54     10432784.26      3563428.14     10433543.78
#Sta/Elev= 30
    4308  368.99  4394.1  368.91  4474.2  367.72  4544.3  368.12    4630  366.06
  4787.8  366.67  4858.5   366.6  4886.9  363.75    4935  362.14  4948.8  363.35
  4958.8  362.13  4978.8  354.09  4995.8  351.75  4998.6  351.25  5001.8  351.75
  5006.5  353.54  5011.5   353.3  5016.1  354.52  5038.9  359.37  5048.9  360.11
    5079  357.56    5119  361.41    5129  363.23  5149.1  364.62  5179.1  364.46
    5357  369.11  5469.6  371.09  5499.6  372.93  5529.7  372.57  5692.1   378.2
#Mann= 6 ,-1 , 0
    4308     .16       0  4787.8      .1       0    4935     .16       0
  4995.8     .07       0  5001.8     .16       0  5016.1      .1       0
Bank Sta=4995.8,5001.8
XS Rating Curve= 0 ,0
Exp/Cntr=0.3,0.1

Type RM Length L Ch R = 1 ,17320   ,615,615,615
BEGIN DESCRIPTION:
SOUR BRANCH 31.0
END DESCRIPTION:
XS GIS Cut Line= 2
      3562956.62     10432595.36      3563364.64     10433532.93
#Sta/Elev= 30
  4652.6  377.63  4682.8  376.08  4768.5  373.26  4805.4  370.98    4823   370.8
  4844.9  368.89  4904.6  365.97  4951.5  361.24  4956.9  360.06  4974.9  354.19
  4980.4  353.84  4986.6  350.07  4994.5  348.64  4997.3  348.14  5000.5  348.64
  5019.3  349.77    5035  351.36    5063  353.56  5073.9  355.13  5079.6     357
  5095.7  358.69  5155.3  361.28  5178.8  363.49  5330.3  367.11  5368.3  369.01
  5382.6  370.57  5400.6  369.27    5435   369.2  5510.7  371.14  5675.1   376.9
#Mann= 4 ,-1 , 0
  4652.6     .16       0  4994.5     .07       0  5000.5     .16       0
    5035      .1       0
Bank Sta=4994.5,5000.5
XS Rating Curve= 0 ,0
Exp/Cntr=0.3,0.1

Type RM Length L Ch R = 1 ,16705   ,273,273,273
BEGIN DESCRIPTION:
SOUR BRANCH 30.0
END DESCRIPTION:
XS GIS Cut Line= 3
      3562322.97     10432725.63      3562618.09     10433250.77
      3563107.82     10433671.15
#Sta/Elev= 30
  4338.4   372.5  4430.8  371.09  4449.5  370.62    4638  366.52  4661.1  366.21
  4759.5  364.88  4804.1  362.35  4824.4  360.08  4834.8  358.27  4840.5  358.29
  4856.4  354.75  4972.4  349.81  5005.3  344.39    5008  343.89  5011.3  344.39
  5022.6  346.02  5029.2  350.91  5036.8  353.91  5043.4  358.09  5057.7  357.67
    5072  355.39  5107.1  357.44    5129  361.96  5143.3  361.95  5149.9  360.85
  5170.7  361.57  5192.7  363.63  5211.6  362.67  5461.5  367.79  5586.2  372.12
#Mann= 9 ,-1 , 0
  4338.4     .05       0  4430.8     .12       0  4449.5      .1       0
    4638     .16       0  4661.1      .1       0  4824.4     .16       0
  5005.3     .07       0  5011.3     .16       0  5211.6      .1       0
Bank Sta=5005.3,5011.3
XS Rating Curve= 0 ,0
Exp/Cntr=0.3,0.1

Type RM Length L Ch R = 1 ,16432   ,1009,1009,1009
BEGIN DESCRIPTION:
SOUR BRANCH 29.0
END DESCRIPTION:
XS GIS Cut Line= 4
      3562201.41     10432972.95      3562409.76     10433341.91
      3562470.52     10433541.56      3562192.72     10434006.01
#Sta/Elev= 30
  4474.8  370.14  4539.8  368.02  4561.1  366.32  4612.6  362.15  4628.5  359.44
  4671.8  359.77  4709.4  357.57  4725.3  357.62  4731.1   359.1  4752.7  357.87
  4769.3  354.05  4774.4  354.51  4785.4  352.19  4811.9  350.84  4840.8  346.93
  4871.1  345.69  4886.7  345.75  4895.8  348.21  4908.7  348.86  4971.4  348.63
  4981.9  347.99  4999.8  343.62  5002.5  343.12  5005.8  343.62  5034.1  349.51
  5110.2   351.6  5258.8  365.05  5442.2  366.41    5485  365.27  5648.4  367.59
#Mann= 7 ,-1 , 0
  4474.8     .16       0  4539.8     .12       0  4561.1     .16       0
  4769.3      .1       0  4785.4     .16       0  4999.8     .07       0
  5005.8     .16       0
Bank Sta=4999.8,5005.8
XS Rating Curve= 0 ,0
Exp/Cntr=0.3,0.1