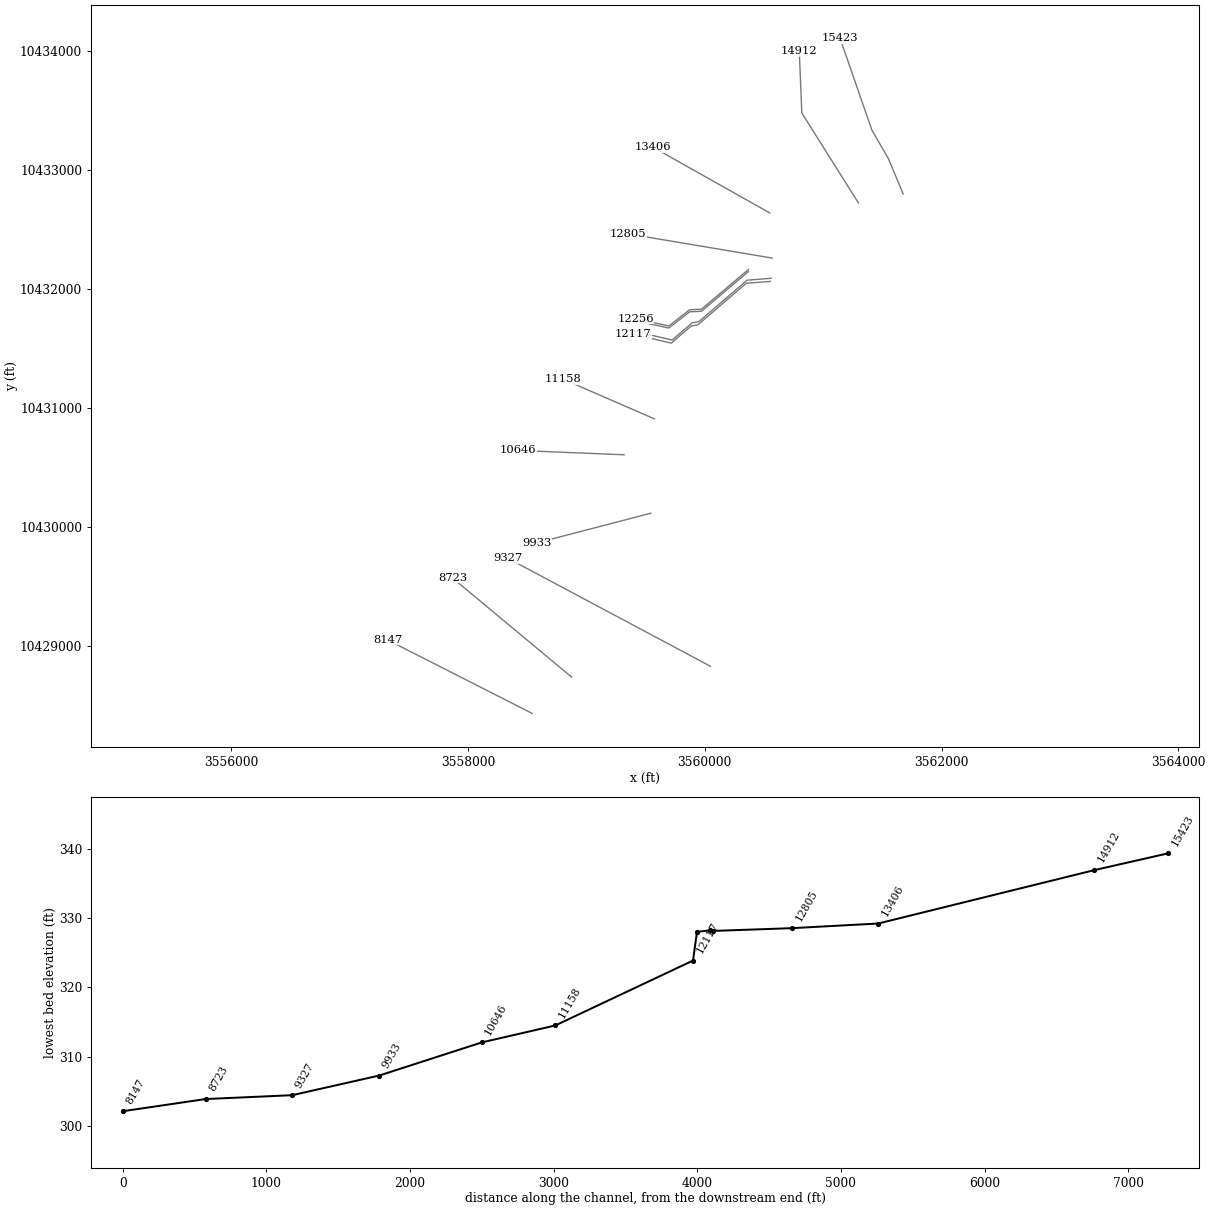
HEC-RAS study SOUR BRANCH.prj: SOUR BRANCH Base Level Engineering

--- SOUR BRANCH.g01 (geometry) --- (continued)

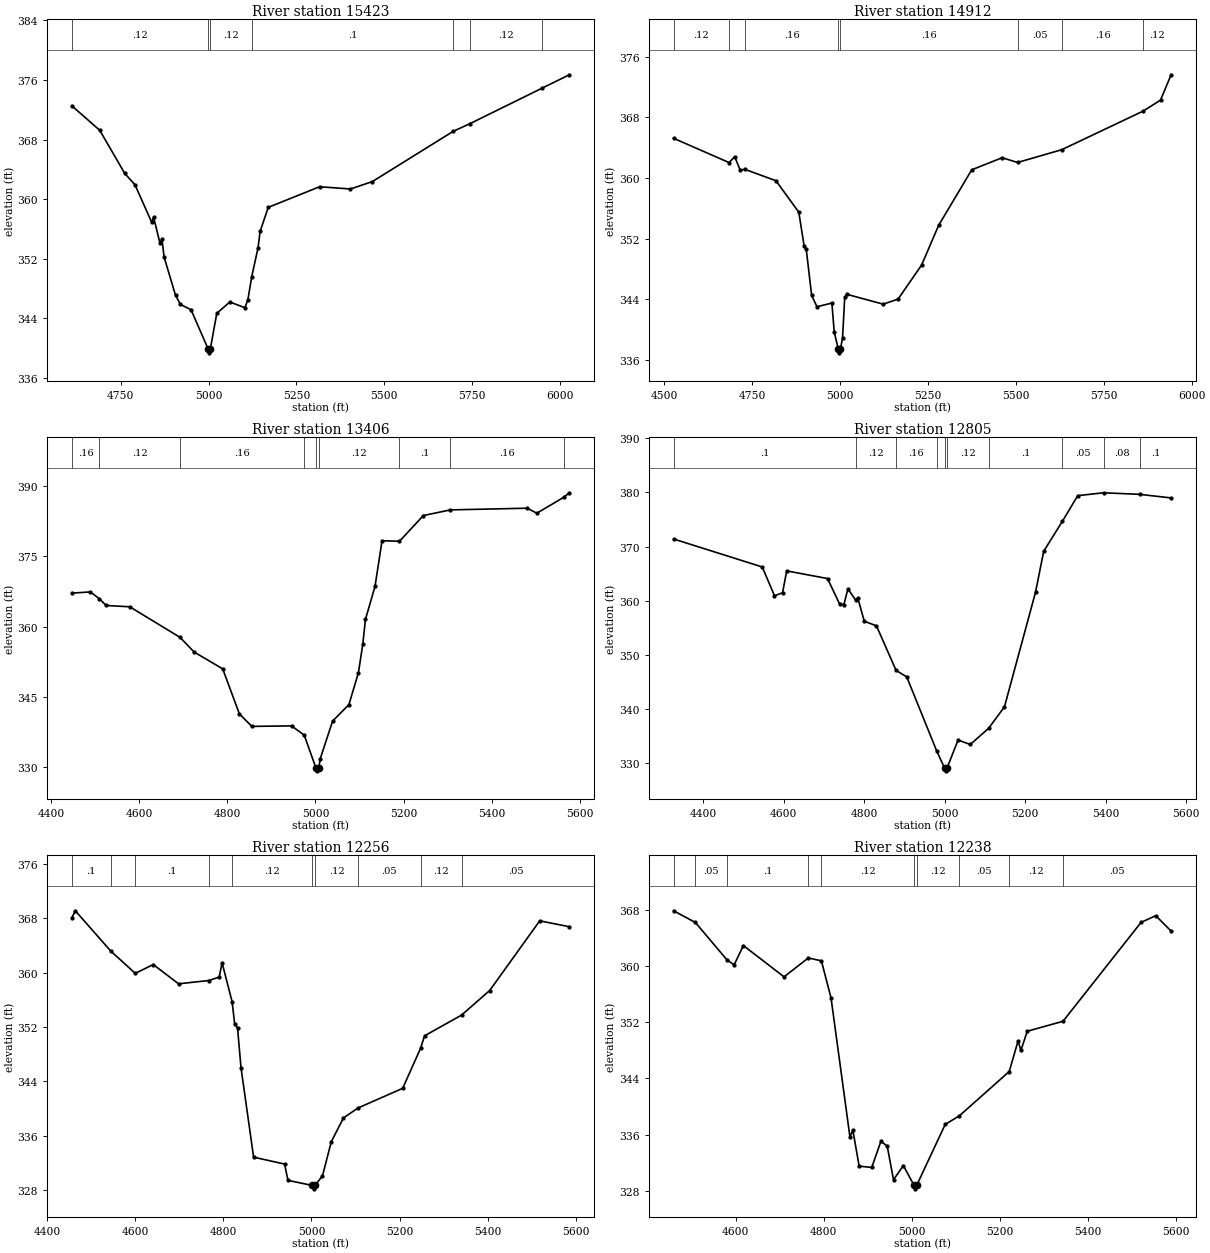
Type RM Length L Ch R = 1 ,15423   ,511,511,511
BEGIN DESCRIPTION:
SOUR BRANCH 28.0
END DESCRIPTION:
XS GIS Cut Line= 4
      3561676.25     10432799.39      3561550.38     10433098.86
      3561411.49     10433337.57      3561142.99     10434108.43
#Sta/Elev= 30
  4610.5  372.53    4690  369.24  4761.3  363.44  4790.4  361.92  4837.9  356.89
  4843.4  357.57  4861.7  354.05  4867.1  354.65  4873.3  352.21  4905.8  347.09
    4920  345.85  4950.1  345.14  4998.9  339.85  5001.6  339.35  5004.9  339.85
  5023.4  344.66  5060.6  346.18  5103.6  345.41  5112.1  346.51    5123  349.59
  5140.9  353.45  5146.8  355.65    5170  358.89  5316.2  361.66  5404.2  361.36
  5466.4  362.35  5696.8   369.1  5744.9  370.14    5950   374.9  6027.8   376.7
#Mann= 7 ,-1 , 0
  4610.5     .12       0  4998.9     .07       0  5004.9     .12       0
    5123      .1       0  5696.8     .05       0  5744.9     .12       0
    5950      .1       0
Bank Sta=4998.9,5004.9
XS Rating Curve= 0 ,0
Exp/Cntr=0.3,0.1

Type RM Length L Ch R = 1 ,14912   ,1506,1506,1506
BEGIN DESCRIPTION:
SOUR BRANCH 26.0
END DESCRIPTION:
XS GIS Cut Line= 3
      3561297.32     10432725.51      3560819.87     10433480.75
      3560798.17      10434001.6
#Sta/Elev= 30
  4526.7  365.24  4684.5  362.04  4700.5  362.81  4715.8  361.08  4730.4  361.13
  4817.9  359.64  4882.8  355.49  4898.1  350.98    4904   350.6  4919.3  344.51
  4934.5  343.02  4976.9  343.51  4983.5  339.69  4995.1  337.44  4997.9  336.94
  5001.1  337.44  5007.2  338.89  5013.4  344.28  5019.3  344.66  5122.8  343.36
  5165.1  344.03    5232  348.52  5280.4  353.75  5374.5  361.08  5461.1  362.68
  5504.9  362.05  5630.7  363.74  5862.1  368.83  5911.5  370.28  5941.5  373.62
#Mann= 8 ,-1 , 0
  4526.7     .12       0  4684.5      .1       0  4730.4     .16       0
  4995.1     .07       0  5001.1     .16       0  5504.9     .05       0
  5630.7     .16       0  5862.1     .12       0
Bank Sta=4995.1,5001.1
XS Rating Curve= 0 ,0
Exp/Cntr=0.3,0.1

Type RM Length L Ch R = 1 ,13406   ,601,601,601
BEGIN DESCRIPTION:
SOUR BRANCH 23.0
END DESCRIPTION:
XS GIS Cut Line= 2
       3560548.9     10432640.67      3559562.73     10433192.78
#Sta/Elev= 30
  4446.5  367.12  4488.7  367.39    4509  365.91  4524.5  364.49  4578.1  364.21
  4692.3  357.69  4724.2  354.57  4789.3  350.96    4827  341.38  4855.4   338.7
  4945.7  338.81  4974.5  336.82  5001.4  329.72  5004.1  329.22  5007.4  329.72
  5010.8   331.8  5038.8  339.83  5075.9  343.34  5097.6  350.18  5107.5  356.27
  5113.5  361.53  5135.2  368.55  5151.2   378.3  5190.8  378.19  5245.1  383.68
  5306.6  384.88  5481.1  385.24  5502.8  384.17  5564.6   387.6  5576.7  388.53
#Mann= 9 ,-1 , 0
  4446.5     .16       0    4509     .12       0  4692.3     .16       0
  4974.5     .12       0  5001.4     .07       0  5007.4     .12       0
  5190.8      .1       0  5306.6     .16       0  5564.6      .1       0
Bank Sta=5001.4,5007.4
XS Rating Curve= 0 ,0
Exp/Cntr=0.3,0.1

Type RM Length L Ch R = 1 ,12805   ,549,549,549
BEGIN DESCRIPTION:
SOUR BRANCH 22.0
END DESCRIPTION:
XS GIS Cut Line= 2
      3560569.48     10432261.18      3559349.82     10432465.18
#Sta/Elev= 30
  4325.9  371.39  4546.3  366.22  4576.7   360.9  4596.7  361.45  4607.1   365.5
  4708.5  364.08  4738.9  359.32  4749.1  359.25  4759.2  362.16  4778.1  360.14
  4783.9  360.47  4799.8   356.2  4830.2  355.34    4879   347.1  4905.4  345.92
  4979.8  332.24  4999.5  329.05  5002.3  328.55  5005.5  329.05    5033  334.24
  5063.4  333.42  5108.8   336.4  5148.3  340.37  5225.6  361.57  5245.9  369.13
  5292.4  374.67  5330.5   379.4  5394.6  379.93  5484.2  379.64  5562.5  378.98
#Mann= 10 ,-1 , 0
  4325.9      .1       0  4778.1     .12       0    4879     .16       0
  4979.8     .12       0  4999.5     .07       0  5005.5     .12       0
  5108.8      .1       0  5292.4     .05       0  5394.6     .08       0
  5484.2      .1       0
Bank Sta=4999.5,5005.5
XS Rating Curve= 0 ,0
Exp/Cntr=0.3,0.1

Type RM Length L Ch R = 1 ,12256   ,18,18,18
BEGIN DESCRIPTION:
SOUR BRANCH 21.3
END DESCRIPTION:
XS GIS Cut Line= 5
      3560368.82     10432165.41      3559971.71     10431831.23
      3559871.88     10431826.89       3559696.1     10431690.17
      3559415.56     10431752.03
#Sta/Elev= 30
  4456.2  368.09  4464.1  369.12  4544.4  363.19  4600.1   359.9    4641   361.2
  4698.2  358.36  4766.5  358.84  4790.6  359.35  4797.1  361.45  4819.8  355.73
  4825.7  352.45  4832.2  351.84    4840  346.02  4868.6  332.82  4938.9   331.8
  4946.6   329.4  5001.8  328.65  5004.6  328.15  5007.8  328.65  5024.9  330.06
  5044.9  335.09  5072.5   338.6  5105.7  340.07  5206.9  342.96  5247.6  348.87
  5256.6   350.7  5340.5  353.75  5404.3  357.37  5517.9  367.64  5585.1  366.77
#Mann= 10 ,-1 , 0
  4456.2      .1       0  4544.4     .05       0  4600.1      .1       0
  4766.5     .16       0  4819.8     .12       0  5001.8     .07       0
  5007.8     .12       0  5105.7     .05       0  5247.6     .12       0
  5340.5     .05       0
Bank Sta=5001.8,5007.8
XS Rating Curve= 0 ,0
Exp/Cntr=0.3,0.1

Type RM Length L Ch R = 1 ,12238   ,93,93,93
BEGIN DESCRIPTION:
SOUR BRANCH 21.0
END DESCRIPTION:
XS GIS Cut Line= 5
      3560368.86     10432148.09      3559971.71     10431813.87
      3559871.88     10431809.53       3559696.1     10431672.81
      3559415.52     10431734.68
#Sta/Elev= 30
  4459.5  367.93    4509  366.26  4581.1  360.89    4597  360.22  4617.8  362.97
  4710.2   358.5  4765.2   361.2  4794.9  360.79  4816.8   355.5  4859.7  335.65
  4866.3  336.63  4880.6  331.49  4909.2   331.3    4930  335.04  4944.3  334.34
  4958.6  329.54  4980.9  331.57  5005.2  328.75    5008  328.25  5011.2  328.75
  5075.9  337.44  5108.2  338.68  5221.2  344.99  5241.3  349.37  5247.7  348.01
  5262.1  350.74  5343.2  352.16  5520.3  366.27  5553.7  367.23  5588.5  365.04
#Mann= 10 ,-1 , 0
  4459.5      .1       0    4509     .05       0  4581.1      .1       0
  4765.2     .16       0  4794.9     .12       0  5005.2     .07       0
  5011.2     .12       0  5108.2     .05       0  5221.2     .12       0
  5343.2     .05       0
Bank Sta=5005.2,5011.2
XS Rating Curve= 0 ,0
Exp/Cntr=0.3,0.1

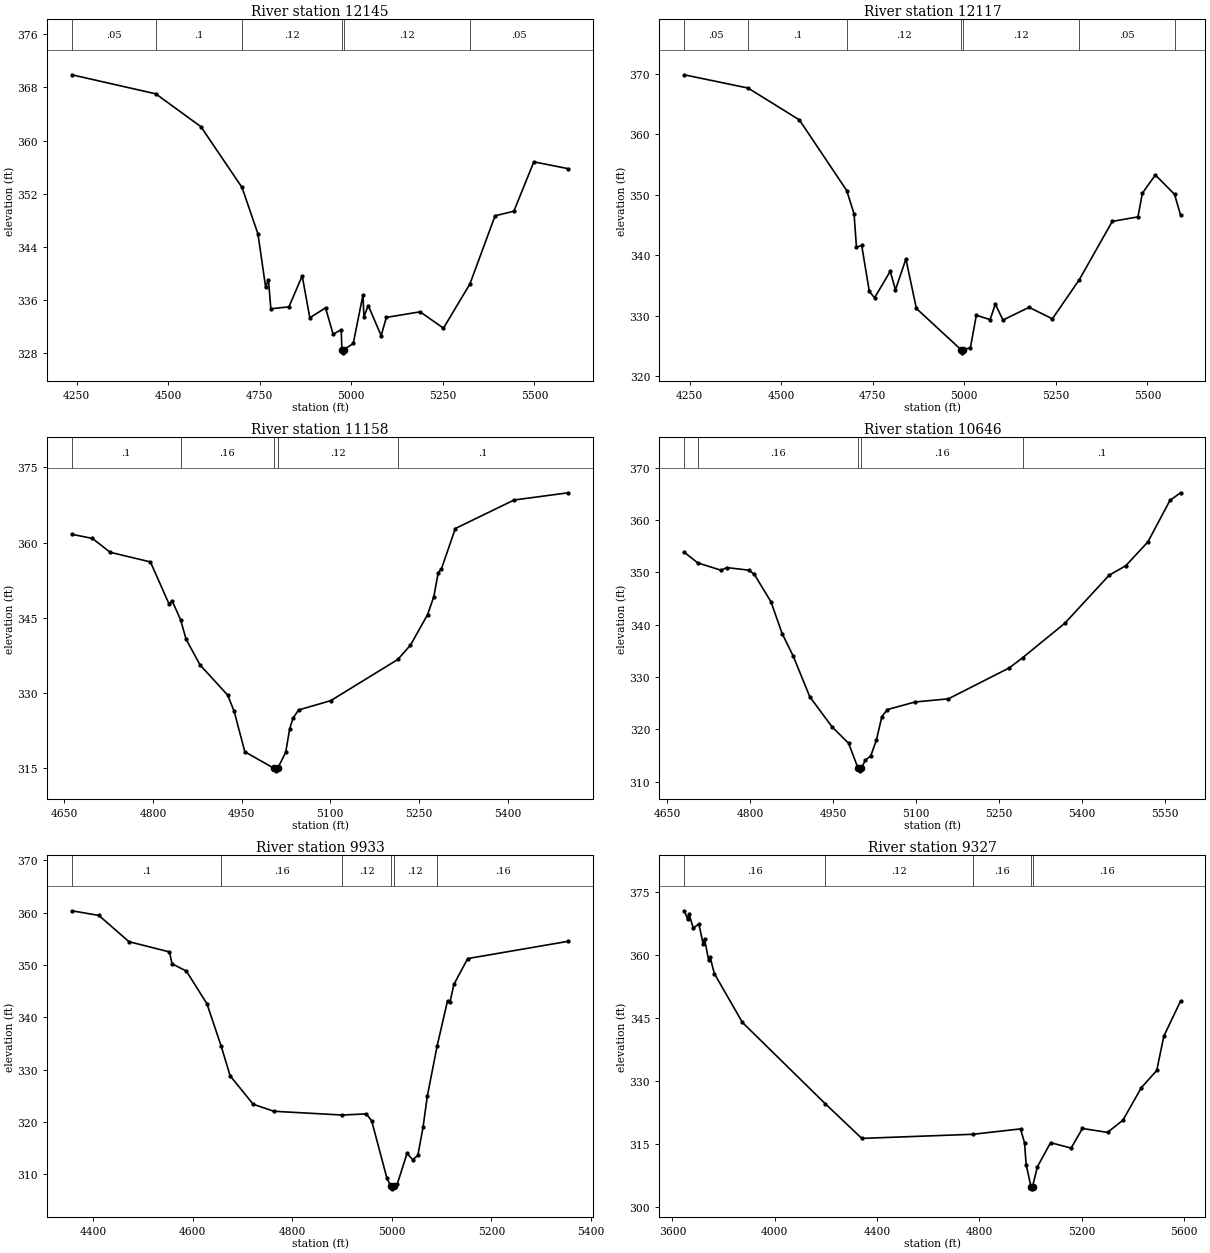
Type RM Length L Ch R = 1 ,12145   ,28,28,28
BEGIN DESCRIPTION:
SOUR BRANCH 21.1
END DESCRIPTION:
XS GIS Cut Line= 6
      3560560.64     10432091.21      3560357.56     10432075.59
      3559949.57     10431726.63      3559892.28     10431716.21
      3559723.88     10431572.12      3559397.51      10431648.5
#Sta/Elev= 30
  4236.7  369.91  4465.9  367.04  4589.2  362.09  4701.5  352.93    4745  345.93
  4765.9  337.94  4773.6  339.04  4780.2  334.65  4829.6  334.94  4865.8  339.61
  4886.6  333.29  4929.5  334.79  4950.3  330.81  4972.3   331.5  4974.2  328.51
    4977  328.01  4980.2  328.51  5005.2  329.42  5031.8  336.76  5034.3  333.45
  5046.2  335.13  5081.4  330.61  5095.6  333.35  5187.8  334.19  5251.5  331.73
  5323.9   338.4  5392.4  348.66  5443.8  349.35  5498.3  356.79  5592.3  355.76
#Mann= 6 ,-1 , 0
  4236.7     .05       0  4465.9      .1       0  4701.5     .12       0
  4974.2     .07       0  4980.2     .12       0  5323.9     .05       0
Bank Sta=4974.2,4980.2
XS Rating Curve= 0 ,0
Exp/Cntr=0.3,0.1

Type RM Length L Ch R = 1 ,12117   ,959,959,959
BEGIN DESCRIPTION:
SOUR BRANCH 21.2
END DESCRIPTION:
XS GIS Cut Line= 6
      3560553.73     10432065.17      3560350.61     10432049.55
      3559942.63     10431700.59      3559885.34     10431690.17
      3559716.93     10431546.08      3559390.51     10431622.47
#Sta/Elev= 30
  4234.9  369.81  4409.3  367.62  4549.6  362.36  4678.8  350.69  4698.9  346.84
  4705.5   341.3  4719.8  341.61  4740.6  334.02  4754.9  332.97  4797.7  337.34
    4812  334.28  4840.5  339.38  4869.1   331.2  4991.4  324.37  4994.2  323.87
  4997.4  324.37  5016.7  324.74  5032.8  330.08  5070.4  329.36  5084.7  331.92
  5105.5  329.29  5176.9  331.39  5240.5  329.49  5313.9  335.95  5404.1  345.59
  5474.1  346.33  5486.3  350.25  5521.7  353.26  5574.1  350.05  5590.6  346.62
#Mann= 7 ,-1 , 0
  4234.9     .05       0  4409.3      .1       0  4678.8     .12       0
  4991.4     .07       0  4997.4     .12       0  5313.9     .05       0
  5574.1     .16       0
Bank Sta=4991.4,4997.4
XS Rating Curve= 0 ,0
Exp/Cntr=0.3,0.1

Type RM Length L Ch R = 1 ,11158   ,512,512,512
BEGIN DESCRIPTION:
SOUR BRANCH 19.0
END DESCRIPTION:
XS GIS Cut Line= 2
      3559574.16     10430909.78      3558803.35     10431243.11
#Sta/Elev= 30
  4662.7  361.64  4697.6  360.81  4727.6  358.05  4795.7  356.13    4827  347.79
  4832.5  348.36  4846.7  344.61    4856  340.73  4879.5  335.62  4926.4  329.58
  4937.3  326.36  4955.4  318.29  5004.8  314.99  5007.6  314.49  5010.8  314.99
  5011.3  315.08  5024.5  318.17  5031.3  322.88  5036.8  324.96  5046.3  326.62
  5100.7  328.48  5214.2  336.69  5235.6  339.55  5264.5  345.62  5275.1  349.22
  5282.6  354.01    5288  354.76  5311.5  362.79  5410.9  368.47  5502.5  369.91
#Mann= 6 ,-1 , 0
  4662.7      .1       0  4846.7     .16       0  5004.8     .07       0
  5010.8     .16       0  5011.3     .12       0  5214.2      .1       0
Bank Sta=5004.8,5010.8
XS Rating Curve= 0 ,0
Exp/Cntr=0.3,0.1

Type RM Length L Ch R = 1 ,10646   ,713,713,713
BEGIN DESCRIPTION:
SOUR BRANCH 17.0
END DESCRIPTION:
XS GIS Cut Line= 2
      3559318.92     10430607.71      3558423.06     10430644.17
#Sta/Elev= 30
  4680.9  353.86  4705.5   351.8  4747.8  350.39  4757.8  350.91  4797.8  350.41
  4807.8  349.59  4837.8  344.35  4857.9  338.29  4877.9  333.98  4907.9  326.19
  4947.9  320.47    4978   317.3    4995  312.54  4997.7  312.04    5001  312.54
    5008  314.05    5018  314.91    5028  317.88    5038  322.42    5048  323.76
  5098.1  325.21  5158.1  325.81  5268.2  331.73  5292.1  333.66  5368.3  340.25
  5448.4  349.44  5478.4  351.25  5518.4  355.81  5558.4  363.77  5577.5  365.21
#Mann= 5 ,-1 , 0
  4680.9      .1       0  4705.5     .16       0    4995     .07       0
    5001     .16       0  5292.1      .1       0
Bank Sta=4995,5001
XS Rating Curve= 0 ,0
Exp/Cntr=0.3,0.1

Type RM Length L Ch R = 1 ,9933    ,606,606,606
BEGIN DESCRIPTION:
SOUR BRANCH 15.0
END DESCRIPTION:
XS GIS Cut Line= 2
      3559544.64     10430116.39      3558579.88     10429866.52
#Sta/Elev= 30
  4357.5  360.38  4411.8  359.49  4472.4  354.47  4553.6  352.52  4558.7  350.26
  4587.4  348.86  4628.7  342.64    4657  334.63  4675.4  328.84  4721.7  323.42
    4763  322.08  4900.4  321.36  4948.9  321.58  4959.6   320.2  4989.9  309.36
  4997.6  307.76  5000.3  307.26  5003.6  307.76  5010.9   308.2  5030.5  314.04
  5041.9  312.83  5052.2  313.66  5062.6  319.04  5071.1  324.93  5090.9  334.58
  5111.7  343.17  5116.8  342.98  5124.5  346.32  5152.3  351.25  5354.1  354.55
#Mann= 6 ,-1 , 0
  4357.5      .1       0    4657     .16       0  4900.4     .12       0
  4997.6     .07       0  5003.6     .12       0  5090.9     .16       0
Bank Sta=4997.6,5003.6
XS Rating Curve= 0 ,0
Exp/Cntr=0.3,0.1

Type RM Length L Ch R = 1 ,9327    ,604,604,604
BEGIN DESCRIPTION:
SOUR BRANCH 13.0
END DESCRIPTION:
XS GIS Cut Line= 2
      3560048.12     10428829.63      3558332.83     10429739.35
#Sta/Elev= 30
  3645.7  370.57  3659.4  368.64  3665.1  369.78  3681.4  366.44  3703.4  367.45
  3719.7  362.75  3725.4  363.93  3741.7  358.76  3747.4  359.54  3763.7  355.64
  3873.7     344  4198.5  324.62  4340.5  316.42    4775   317.4  4961.2  318.68
  4976.9   315.4  4983.2  310.21  5002.2  304.92    5005  304.42  5008.2  304.92
  5027.2  309.66  5078.8   315.4  5159.2  314.12  5203.3  318.78  5301.8  317.85
  5361.7  320.75  5433.7  328.47    5494  332.58  5521.7  340.73  5587.3  349.11
#Mann= 5 ,-1 , 0
  3645.7     .16       0  4198.5     .12       0    4775     .16       0
  5002.2     .07       0  5008.2     .16       0
Bank Sta=5002.2,5008.2
XS Rating Curve= 0 ,0
Exp/Cntr=0.3,0.1

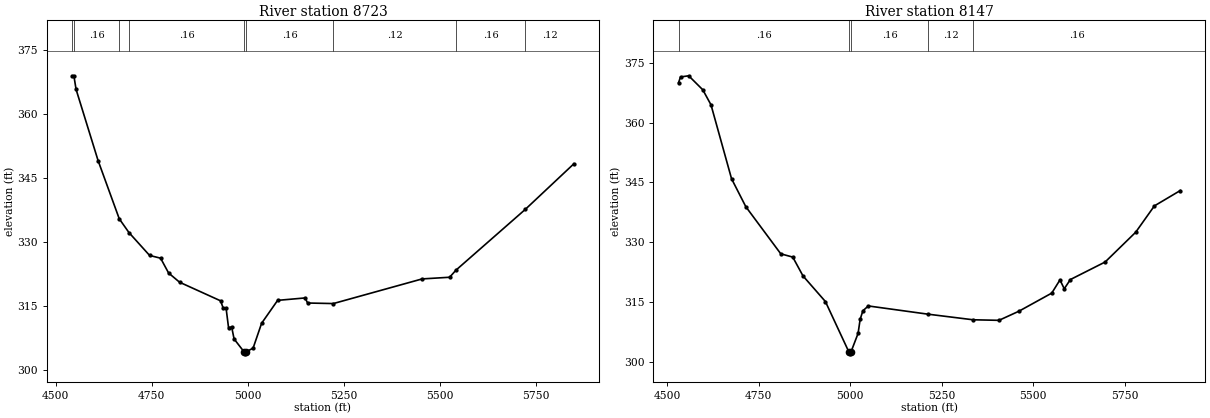
Type RM Length L Ch R = 1 ,8723    ,576,576,576
BEGIN DESCRIPTION:
SOUR BRANCH 12.0
END DESCRIPTION:
XS GIS Cut Line= 2
      3558874.45     10428739.39      3557867.55     10429572.69
#Sta/Elev= 30
  4542.6  369.07  4547.3  369.07  4553.1  365.86  4610.4  349.17  4665.5  335.53
  4690.7  332.31  4744.5  326.94  4773.2  326.29    4794  322.82  4822.7  320.65
  4929.5  316.29    4936  314.64  4943.8  314.53  4950.3  309.92  4958.2  310.19
  4964.6  307.35  4990.3  304.36  4993.1  303.86  4996.3  304.36  5014.1  305.19
  5036.3  311.03    5078   316.4  5149.6  316.97  5156.1  315.78  5223.1  315.65
  5454.4  321.43    5526  321.82  5542.7   323.5  5722.9  337.72  5849.6  348.43
#Mann= 9 ,-1 , 0
  4542.6     .12       0  4547.3     .16       0  4665.5     .12       0
  4690.7     .16       0  4990.3     .07       0  4996.3     .16       0
  5223.1     .12       0  5542.7     .16       0  5722.9     .12       0
Bank Sta=4990.3,4996.3
XS Rating Curve= 0 ,0
Exp/Cntr=0.3,0.1

Type RM Length L Ch R = 1 ,8147    ,1398,1398,1398
BEGIN DESCRIPTION:
SOUR BRANCH 11.0
END DESCRIPTION:
XS GIS Cut Line= 2
      3558541.15     10428433.81      3557318.93     10429051.86
#Sta/Elev= 30
  4531.6  369.99    4537  371.42  4559.3  371.72  4597.8  368.21  4620.2  364.45
  4676.3  345.94  4715.3  338.93  4810.7  327.14  4843.4  326.32  4871.3  321.61
  4932.5  315.19  4996.4   302.6  4999.2   302.1  5002.4   302.6  5021.7  307.23
  5027.3  310.75  5034.8  312.88  5049.6  314.09  5212.5  312.03  5335.3  310.63
  5406.2  310.49  5460.6  312.77  5550.3  317.31  5572.7  320.61  5584.4  318.39
  5601.1   320.7  5695.9  325.09  5779.4  332.55  5830.4  339.14  5901.2  342.99
#Mann= 5 ,-1 , 0
  4531.6     .16       0  4996.4     .07       0  5002.4     .16       0
  5212.5     .12       0  5335.3     .16       0
Bank Sta=4996.4,5002.4
XS Rating Curve= 0 ,0
Exp/Cntr=0.3,0.1