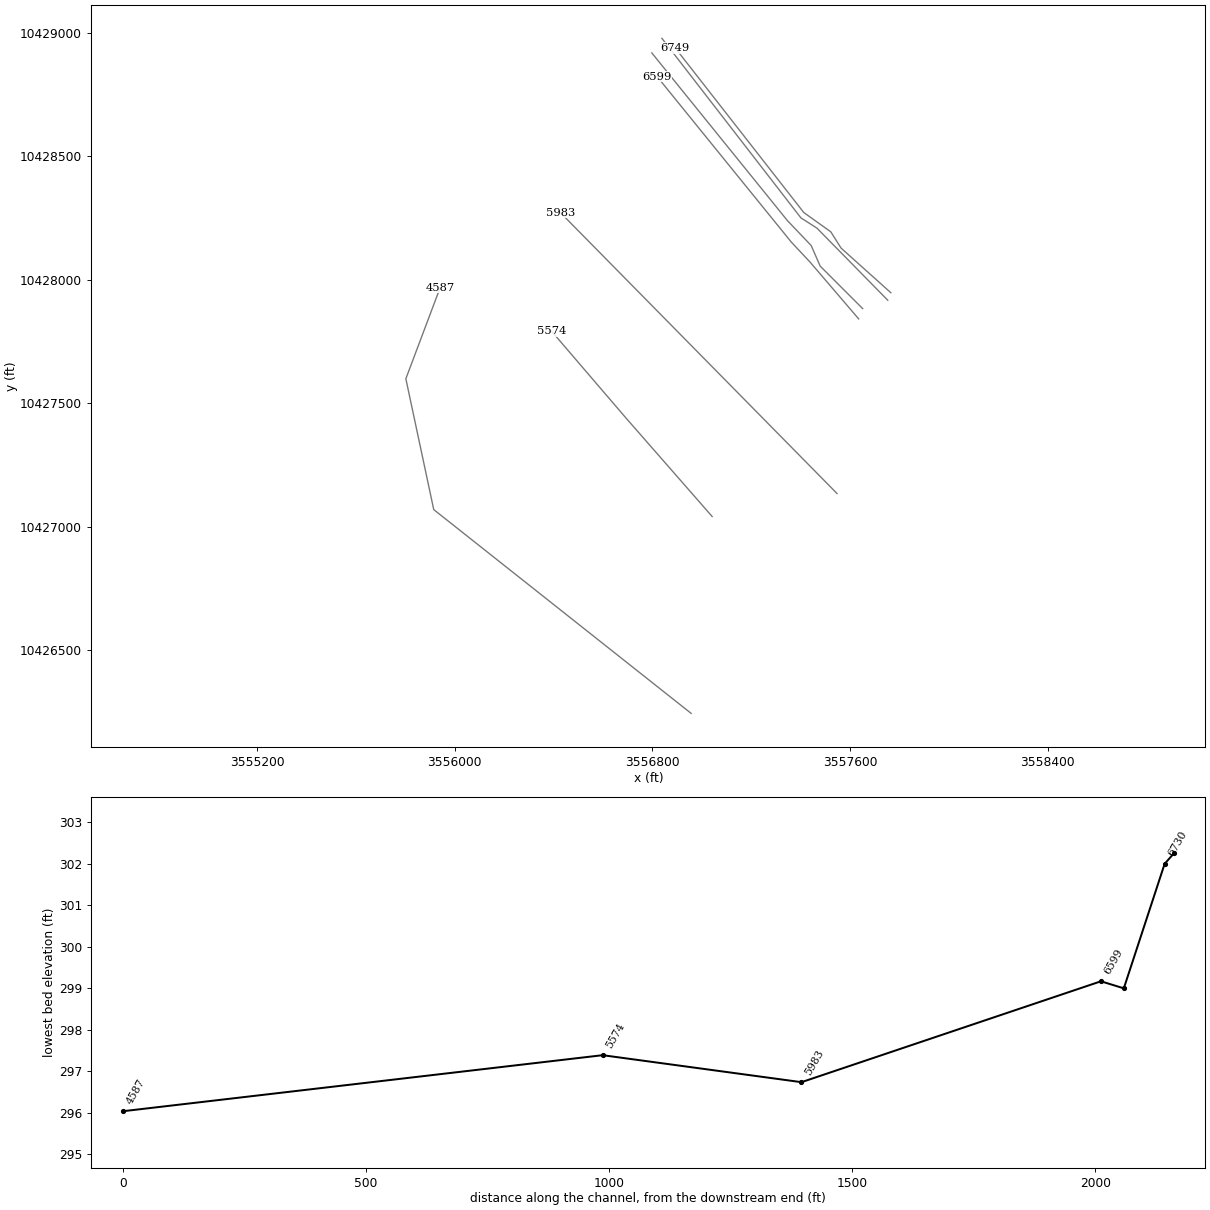
HEC-RAS study SOUR BRANCH.prj: SOUR BRANCH Base Level Engineering

--- SOUR BRANCH.g01 (geometry) --- (continued)

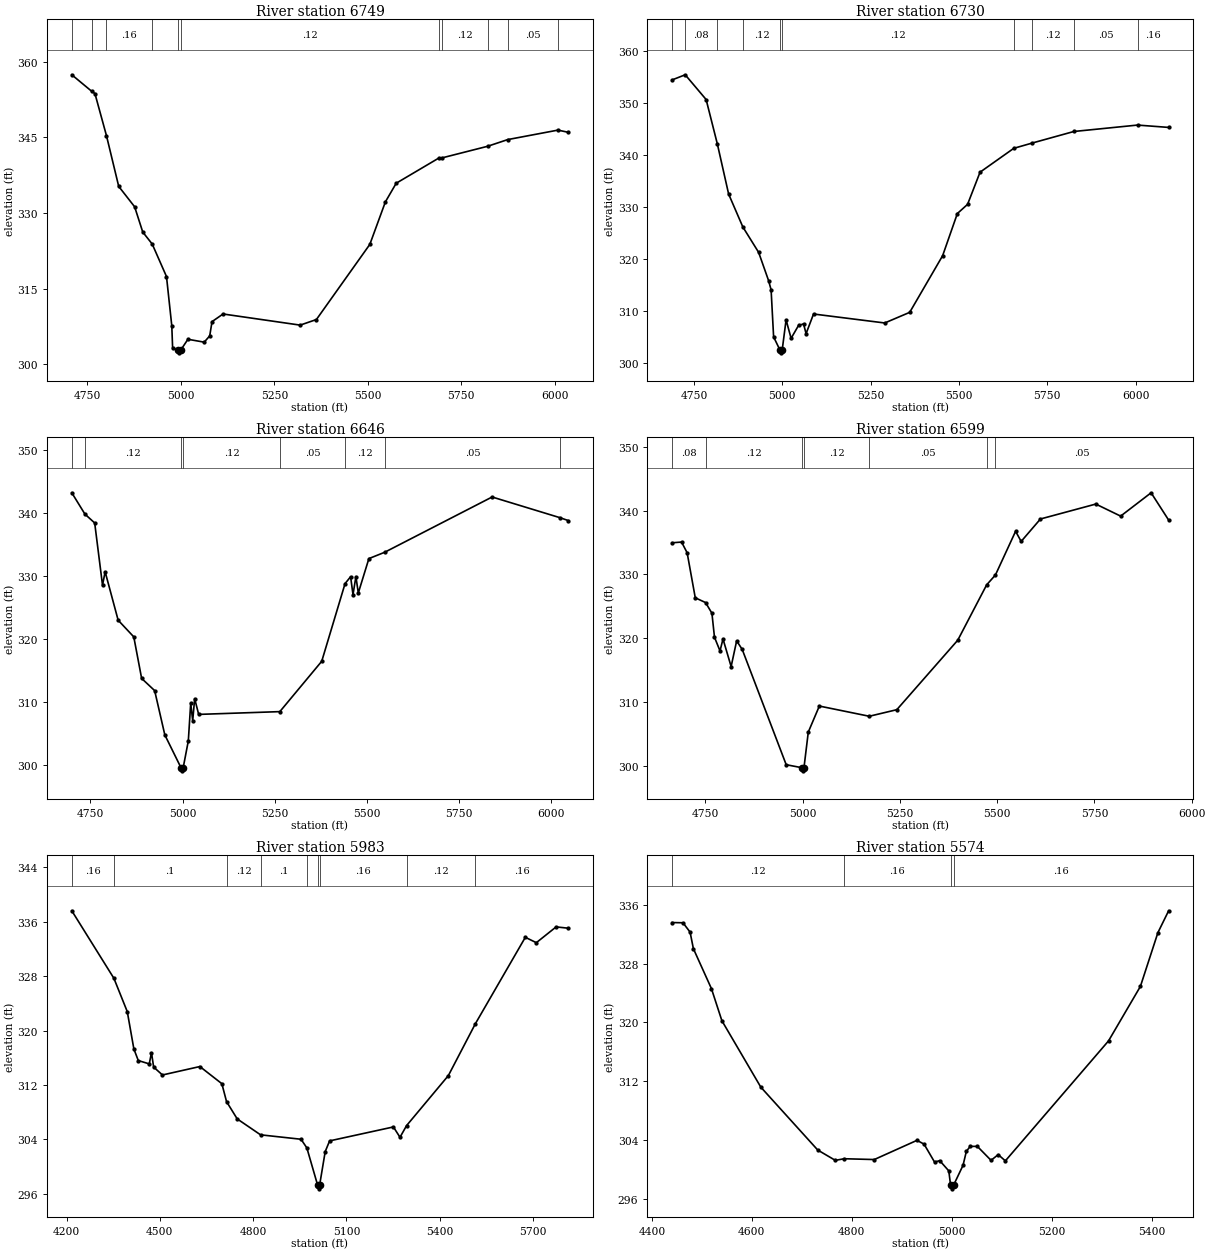
Type RM Length L Ch R = 1 ,6749    ,19,19,19
BEGIN DESCRIPTION:
SOUR BRANCH 10.1
END DESCRIPTION:
XS GIS Cut Line= 5
      3557765.29     10427947.17      3557563.89     10428127.73
      3557522.23      10428193.7      3557412.85     10428271.83
      3556892.77     10428937.53
#Sta/Elev= 30
    4708  357.43  4761.3  354.15  4769.9   353.7  4800.7  345.36  4833.5  335.28
  4876.1  331.23  4897.8  326.22  4923.1  323.84  4961.3  317.39  4975.5  307.59
  4977.7  303.17    4993  302.75  4995.8  302.25    4999  302.75  5018.6  304.94
  5062.2  304.37  5076.9  305.61  5083.1  308.44  5112.6  309.96  5318.9  307.75
  5362.3  308.86  5505.2  323.77  5546.9  332.22  5575.8  335.91  5689.9  340.91
  5699.5  340.96  5820.3  343.24  5874.1  344.57  6008.4  346.45  6035.7  346.02
#Mann= 11 ,-1 , 0
    4708      .1       0  4761.3     .08       0  4800.7     .16       0
  4923.1     .12       0    4993     .07       0    4999     .12       0
  5689.9     .05       0  5699.5     .12       0  5820.3     .16       0
  5874.1     .05       0  6008.4     .16       0
Bank Sta=4993,4999
XS Rating Curve= 0 ,0
Exp/Cntr=0.3,0.1

Type RM Length L Ch R = 1 ,6730    ,84,84,84
BEGIN DESCRIPTION:
SOUR BRANCH 10.0
END DESCRIPTION:
XS GIS Cut Line= 4
      3557752.78      10427916.8      3557466.33     10428208.46
      3557401.22     10428250.13      3556838.76     10428976.64
#Sta/Elev= 30
  4688.8  354.38  4725.4  355.35  4784.6   350.6  4816.3  342.09  4848.3  332.46
  4888.5  326.15  4933.2  321.28  4961.5  315.83  4968.5  314.09  4975.6  305.06
  4993.8   302.5  4996.5     302  4999.8   302.5  5010.9  308.32  5025.1  304.79
  5046.2  307.26  5060.4  307.55  5067.5  305.68  5088.6  309.45  5290.1  307.73
  5360.8  309.77    5454  320.64  5495.7  328.73  5524.6  330.49  5559.9  336.66
  5655.4  341.24  5707.9  342.26  5825.5  344.47  6005.6   345.7  6093.7  345.25
#Mann= 10 ,-1 , 0
  4688.8      .1       0  4725.4     .08       0  4816.3     .16       0
  4888.5     .12       0  4993.8     .07       0  4999.8     .12       0
  5655.4     .05       0  5707.9     .12       0  5825.5     .05       0
  6005.6     .16       0
Bank Sta=4993.8,4999.8
XS Rating Curve= 0 ,0
Exp/Cntr=0.3,0.1

Type RM Length L Ch R = 1 ,6646    ,47,47,47
BEGIN DESCRIPTION:
SOUR BRANCH 9.0
END DESCRIPTION:
XS GIS Cut Line= 5
      3557651.21     10427882.95      3557479.35     10428054.81
      3557442.89     10428138.15      3557346.88     10428238.84
      3556797.96     10428917.63
#Sta/Elev= 30
  4699.6  343.19  4735.2   339.8  4761.7  338.39  4782.9   328.5    4790  330.64
  4825.3  322.94  4867.7  320.29    4889  313.69  4924.3  311.75  4951.9  304.71
  4995.7   299.5  4998.4     299  5001.7   299.5  5015.6  303.76  5022.1  309.76
  5027.5  306.98  5032.8  310.47  5043.7  307.97  5263.8  308.41  5377.4  316.41
  5440.7  328.76  5455.7  329.85  5462.2  327.01  5470.1  329.87  5476.6  327.27
  5505.3  332.73  5547.9  333.73  5839.5  342.52  6024.7  339.21  6045.7  338.78
#Mann= 8 ,-1 , 0
  4699.6     .08       0  4735.2     .12       0  4995.7     .07       0
  5001.7     .12       0  5263.8     .05       0  5440.7     .12       0
  5547.9     .05       0  6024.7     .16       0
Bank Sta=4995.7,5001.7
XS Rating Curve= 0 ,0
Exp/Cntr=0.3,0.1

Type RM Length L Ch R = 1 ,6599    ,616,616,616
BEGIN DESCRIPTION:
SOUR BRANCH 9.1
END DESCRIPTION:
XS GIS Cut Line= 4
      3557635.08     10427841.26      3557438.89     10428070.44
      3557362.51     10428152.04      3556819.12     10428822.16
#Sta/Elev= 30
  4664.6  334.94  4688.5  335.05  4702.8  333.37  4723.7  326.31  4750.2  325.56
  4766.5  323.89  4773.1  320.12  4787.3  317.98    4795  319.85  4815.9  315.53
  4830.1  319.56  4844.4  318.21  4957.5  300.13  4997.2  299.67  4999.9  299.17
  5003.2  299.67  5014.3  305.25  5042.7  309.33  5171.1  307.73  5241.9  308.76
  5398.6  319.66  5472.9  328.34  5495.5  329.89  5547.3  336.74  5561.6  335.15
  5611.2  338.67  5753.5  341.01  5817.4  339.12  5895.7  342.78  5940.8   338.5
#Mann= 7 ,-1 , 0
  4664.6     .08       0  4750.2     .12       0  4997.2     .07       0
  5003.2     .12       0  5171.1     .05       0  5472.9     .12       0
  5495.5     .05       0
Bank Sta=4997.2,5003.2
XS Rating Curve= 0 ,0
Exp/Cntr=0.3,0.1

Type RM Length L Ch R = 1 ,5983    ,409,409,409
BEGIN DESCRIPTION:
SOUR BRANCH 8.0
END DESCRIPTION:
XS GIS Cut Line= 2
      3557547.43     10427134.65       3556427.6     10428271.84
#Sta/Elev= 30
  4216.9  337.62  4352.3  327.69  4395.3  322.79  4416.5   317.3  4430.7   315.6
    4466  315.11  4473.1  316.76  4480.1  314.64  4508.4  313.48  4628.7  314.72
  4699.4   312.2  4714.5  309.56  4748.8  307.02  4823.9  304.68    4954  304.03
  4972.7  302.76  5007.6  297.24  5010.3  296.74  5013.6  297.24  5031.7  302.21
  5045.9  303.79    5251  305.84  5272.2  304.32  5293.4  306.04  5427.7  313.39
  5514.9  321.04  5675.2  333.72  5710.6  332.93  5774.2  335.25  5812.9  335.06
#Mann= 9 ,-1 , 0
  4216.9     .16       0  4352.3      .1       0  4714.5     .12       0
  4823.9      .1       0  4972.7     .16       0  5007.6     .07       0
  5013.6     .16       0  5293.4     .12       0  5514.9     .16       0
Bank Sta=5007.6,5013.6
XS Rating Curve= 0 ,0
Exp/Cntr=0.3,0.1

Type RM Length L Ch R = 1 ,5574    ,987,987,987
BEGIN DESCRIPTION:
SOUR BRANCH 6.0
END DESCRIPTION:
XS GIS Cut Line= 3
      3557042.11     10427041.64      3556692.11     10427441.64
       3556392.1     10427791.65
#Sta/Elev= 30
  4440.9  333.57  4462.3  333.54  4476.5  332.27  4483.1  330.02  4519.2  324.59
  4540.1  320.23  4617.9  311.21  4731.8  302.66  4766.9  301.26  4784.7  301.48
  4844.8  301.37  4930.2  303.98  4944.4  303.46  4965.3  301.03  4975.7  301.22
  4993.8  299.83  4997.4  297.89  5000.1  297.39  5003.4  297.89  5022.3  300.59
  5028.9  302.48  5036.6  303.16  5050.9  303.16  5078.3  301.26  5092.6  302.04
  5106.9  301.19  5313.2  317.49  5376.9  324.89    5412  332.21  5433.4  335.17
#Mann= 4 ,-1 , 0
  4440.9     .12       0  4784.7     .16       0  4997.4     .07       0
  5003.4     .16       0
Bank Sta=4997.4,5003.4
XS Rating Curve= 0 ,0
Exp/Cntr=0.3,0.1

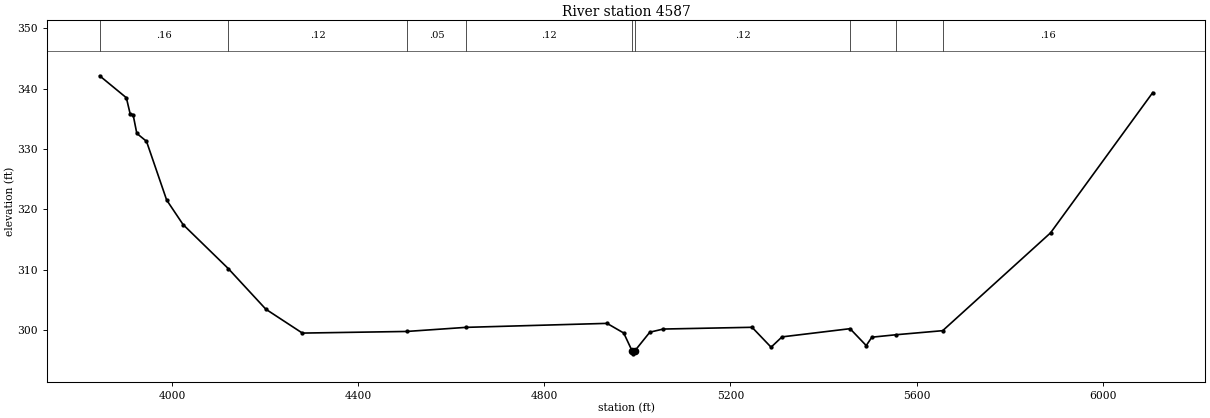
Type RM Length L Ch R = 1 ,4587    ,0,0,0
BEGIN DESCRIPTION:
SOUR BRANCH 1.0
END DESCRIPTION:
XS GIS Cut Line= 4
       3556957.1     10426244.93      3555915.46     10427069.57
      3555802.61     10427599.08      3555941.23      10427967.3
#Sta/Elev= 30
  3844.3  342.13  3901.7  338.49  3909.8  335.85  3916.2  335.69  3924.2  332.58
    3945  331.27  3988.3  321.54  4023.6  317.47  4120.7  310.18  4201.5  303.44
    4280  299.48  4504.2  299.75  4631.9  300.43  4934.8  301.09  4970.7  299.49
  4988.6  296.54  4991.3  296.04  4994.6  296.54  5026.8  299.63  5055.7  300.15
  5246.5  300.44  5287.4  297.14  5310.9  298.85  5457.1  300.21  5491.9  297.41
    5504   298.8  5556.6  299.21  5656.2  299.88    5888  316.09  6107.7  339.35
#Mann= 9 ,-1 , 0
  3844.3     .16       0  4120.7     .12       0  4504.2     .05       0
  4631.9     .12       0  4988.6     .07       0  4994.6     .12       0
  5457.1     .16       0  5556.6     .05       0  5656.2     .16       0
Bank Sta=4988.6,4994.6
XS Rating Curve= 0 ,0
Exp/Cntr=0.3,0.1

Chan Stop Cuts=-1
Use User Specified Reach Order=0
Composite Channel Slope=5