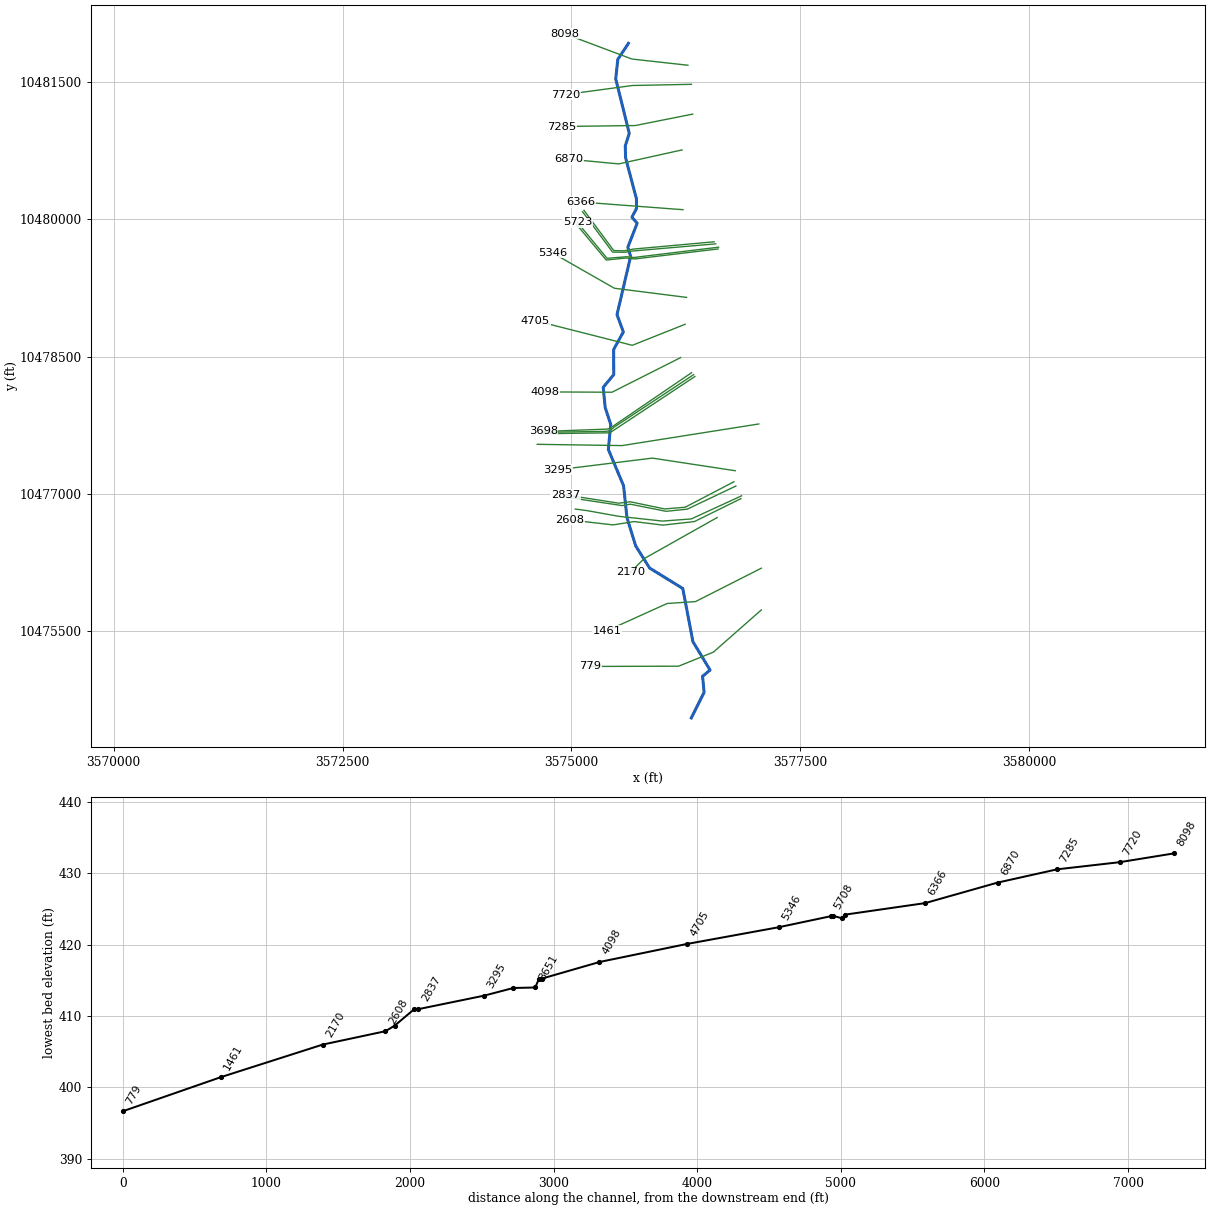
--- STARRETT BRANCH.prj (project) ---

Proj Title=STARRETT BRANCH Base Level Engineering
Current Plan=p01
Default Exp/Contr=0.3,0.1
English Units
Geom File=g01
Flow File=f01
Plan File=p01
BEGIN DESCRIPTION:
STARRETT BRANCH
END DESCRIPTION:

--- STARRETT BRANCH.p01 (plan) ---

Plan Title=Multiple Run
Short Identifier=Multiple
Geom File=g01
Flow File=f01
Subcritical Flow
K Sum by GR= 0
Std Step Tol= 0.01
Critical Tol= 0.01
Num of Std Step Trials= 20
Max Error Tol= 0.3
Flow Tol Ratio= 0.001
Split Flow NTrial= 30
Split Flow Tol= 0.02
Split Flow Ratio= 0.02
Log Output Level= 0
Friction Slope Method= 1
Unsteady Friction Slope Method= 2
Unsteady Bridges Friction Slope Method= 1
Parabolic Critical Depth
Global Vel Dist=  1 , 1 , 1
Global Log Level= 0
CheckData=True
Encroach Param= -1, 0, 0, 0
BEGIN DESCRIPTION:
Multiple Run
END DESCRIPTION:

--- STARRETT BRANCH.f01 (steady flow) ---

Flow Title=Multiple
Number of Profiles=7
Profile Names=10-year,25-year,50-year,1pct_min,100-year,1pct_plu,500-year
River Rch & RM= STARRETT BRANCH,Reach-1,8098
    1649    2337    2922    2662    3601    4869    5454
Boundary for River Rch & Prof#=STARRETT BRANCH,Reach-1,1
Up Type=0
Dn Type=3
Dn Slope=0.005
Boundary for River Rch & Prof#=STARRETT BRANCH,Reach-1,2
Up Type=0
Dn Type=3
Dn Slope=0.005
Boundary for River Rch & Prof#=STARRETT BRANCH,Reach-1,3
Up Type=0
Dn Type=3
Dn Slope=0.005
Boundary for River Rch & Prof#=STARRETT BRANCH,Reach-1,4
Up Type=0
Dn Type=3
Dn Slope=0.005
Boundary for River Rch & Prof#=STARRETT BRANCH,Reach-1,5
Up Type=0
Dn Type=3
Dn Slope=0.005
Boundary for River Rch & Prof#=STARRETT BRANCH,Reach-1,6
Up Type=0
Dn Type=3
Dn Slope=0.005
Boundary for River Rch & Prof#=STARRETT BRANCH,Reach-1,7
Up Type=0
Dn Type=3
Dn Slope=0.005

--- STARRETT BRANCH.g01 (geometry) ---

Geom Title=Existing Conditions

River Reach=STARRETT BRANCH,Reach-1
Reach XY= 30
      3575622.52     10481921.05      3575506.55     10481746.05
      3575483.64     10481533.55      3575631.55     10480937.02
      3575588.15     10480801.60      3575591.27     10480672.09
      3575710.02     10480222.09      3575710.72     10480117.23
      3575660.72     10480022.09      3575717.66     10479955.77
      3575615.93     10479694.31      3575646.48     10479593.62
      3575497.52     10478957.16      3575566.97     10478768.96
      3575460.72     10478576.60      3575462.11     10478302.30
      3575346.83     10478164.10      3575369.05     10477941.19
      3575429.17     10477758.01      3575403.00     10477484.79
      3575569.19     10477089.39      3575606.52     10476739.57
      3575701.35     10476432.40      3575853.65     10476190.10
      3576216.15     10475966.49      3576327.14     10475385.05
      3576514.26     10475075.77      3576432.01     10475007.17
      3576449.24     10474832.86      3576309.38     10474552.76

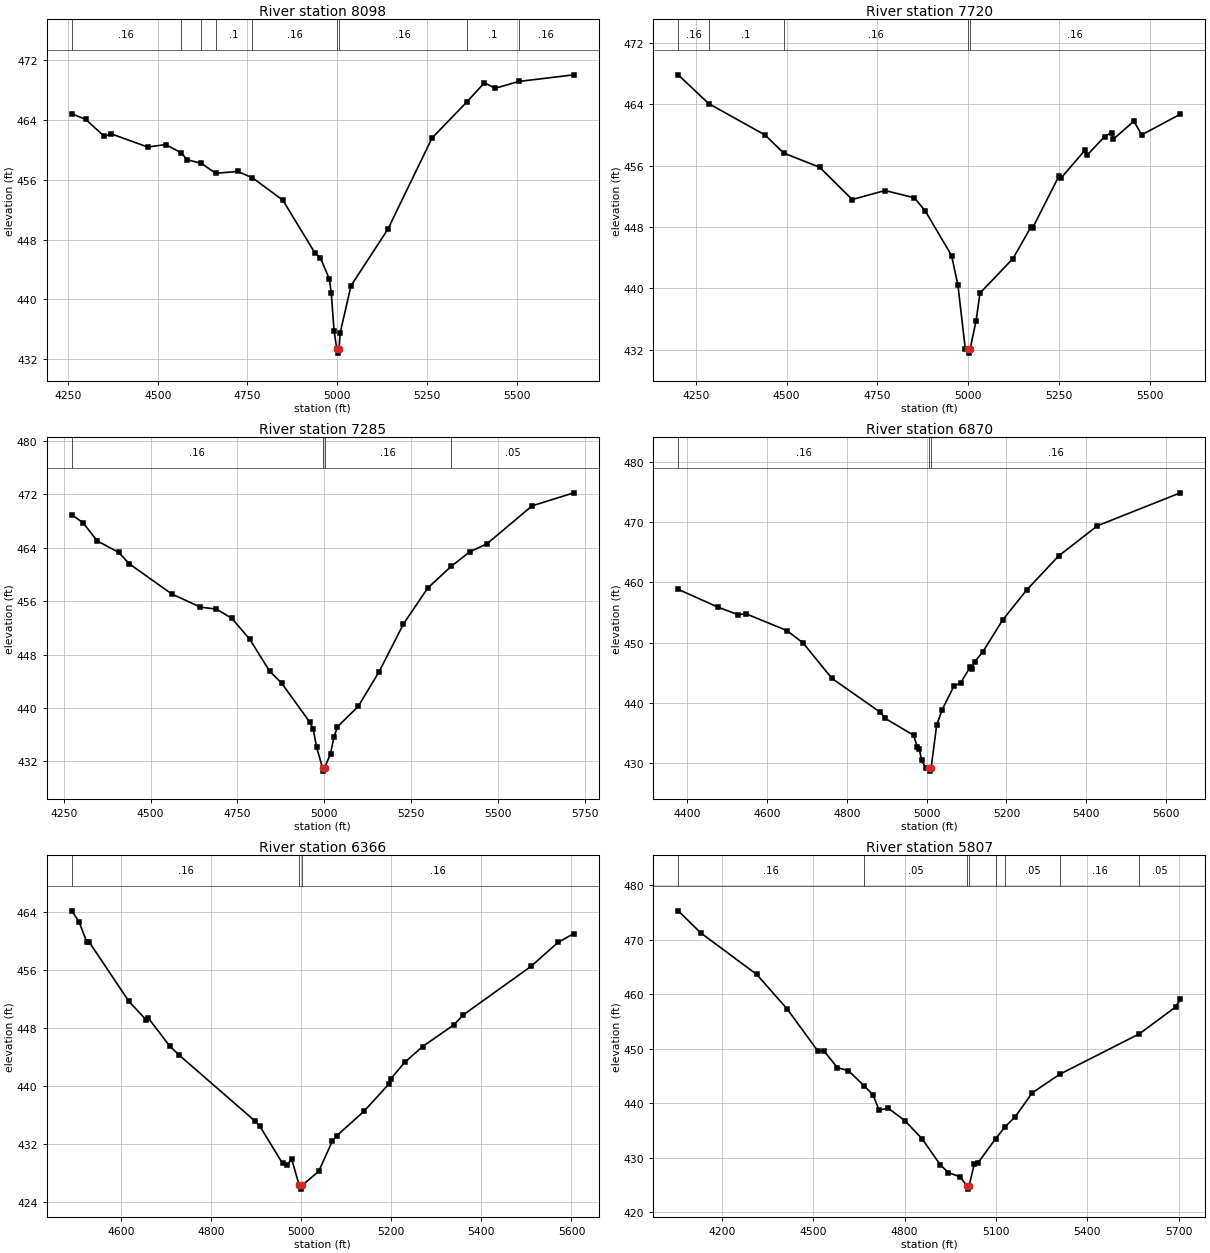
Type RM Length L Ch R = 1,8098,378,378,378
BEGIN DESCRIPTION:
STARRETT BRANCH 4.031
END DESCRIPTION:
XS GIS Cut Line= 3
      3576272.13     10481681.98      3575660.16     10481749.69
      3574926.49     10482025.47
#Sta/Elev= 30
  4260.3  464.85  4299.1  464.10  4350.9  461.83  4371.0  462.15  4471.6  460.40
  4521.9  460.72  4564.2  459.66  4582.3  458.69  4621.7  458.21  4661.1  456.88
  4723.1  457.12  4764.0  456.27  4848.6  453.28  4938.0  446.20  4953.3  445.56
  4978.2  442.72  4983.6  440.86  4991.4  435.81  4999.1  433.28  5001.9  432.78
  5005.1  433.28  5008.5  435.51  5038.7  441.82  5141.0  449.35  5264.6  461.61
  5361.6  466.44  5410.4  469.00  5440.6  468.27  5506.2  469.18  5659.8  470.07
#Mann=9,-1,0
  4260.3    0.16       0  4564.2     0.1       0  4621.7    0.16       0
  4661.1     0.1       0  4764.0    0.16       0  4999.1    0.07       0
  5005.1    0.16       0  5361.6     0.1       0  5506.2    0.16       0
Bank Sta=4999.1,5005.1
Exp/Cntr=0.3,0.1

Type RM Length L Ch R = 1,7720,435,435,435
BEGIN DESCRIPTION:
STARRETT BRANCH 4.030
END DESCRIPTION:
XS GIS Cut Line= 3
      3576311.20     10481473.64      3575665.37     10481460.62
      3574935.37     10481361.90
#Sta/Elev= 30
  4201.8  467.82  4285.6  464.07  4440.9  459.98  4491.9  457.63  4591.0  455.78
  4681.0  451.57  4771.0  452.74  4851.9  451.80  4881.9  450.09  4954.5  444.27
  4972.1  440.37  4992.3  432.09  4999.4  432.05  5002.2  431.55  5005.4  432.05
  5022.1  435.80  5032.7  439.37  5123.5  443.87  5172.4  447.93  5177.5  447.84
  5250.1  454.62  5255.2  454.33  5322.7  458.04  5327.8  457.35  5375.8  459.77
  5395.4  460.30  5400.4  459.45  5456.5  461.78  5478.1  460.00  5584.4  462.69
#Mann=5,-1,0
  4201.8    0.16       0  4285.6     0.1       0  4491.9    0.16       0
  4999.4    0.07       0  5005.4    0.16       0
Bank Sta=4999.4,5005.4
Exp/Cntr=0.3,0.1

Type RM Length L Ch R = 1,7285,415,415,415
BEGIN DESCRIPTION:
STARRETT BRANCH 4.029
END DESCRIPTION:
XS GIS Cut Line= 3
      3576324.26     10481148.13      3575696.62     10481023.12
      3574891.96     10481012.71
#Sta/Elev= 30
  4273.3  468.96  4306.1  467.71  4346.9  465.01  4408.1  463.31  4439.1  461.58
  4561.0  457.08  4643.5  455.10  4689.5  454.81  4734.3  453.41  4785.3  450.30
  4842.7  445.51  4877.1  443.73  4957.8  437.91  4967.8  436.88  4977.8  434.14
  4994.8  431.05  4997.5  430.55  5000.8  431.05  5017.8  433.13  5027.8  435.66
  5037.8  437.18  5097.8  440.26  5157.8  445.45  5227.8  452.59  5297.8  457.98
  5365.6  461.23  5418.4  463.39  5467.8  464.58  5597.8  470.27  5718.0  472.22
#Mann=4,-1,0
  4273.3    0.16       0  4994.8    0.07       0  5000.8    0.16       0
  5365.6    0.05       0
Bank Sta=4994.8,5000.8
Exp/Cntr=0.3,0.1

Type RM Length L Ch R = 1,6870,504,504,504
BEGIN DESCRIPTION:
STARRETT BRANCH 4.028
END DESCRIPTION:
XS GIS Cut Line= 3
      3576208.13     10480756.85      3575517.15     10480604.07
      3574968.58     10480656.15
#Sta/Elev= 30
  4377.3  458.84  4475.8  455.92  4526.8  454.65  4547.3  454.78  4649.7  452.01
  4690.7  449.92  4762.4  444.08  4884.0  438.45  4895.5  437.46  4967.2  434.65
  4976.4  432.75  4981.5  432.32  4987.7  430.48  4998.0  429.23  5005.2  429.19
  5007.9  428.69  5011.2  429.19  5025.1  436.27  5038.9  438.89  5068.8  442.82
  5085.0  443.29  5108.6  445.90  5113.7  445.57  5120.2  446.82  5140.3  448.41
  5190.5  453.75  5250.8  458.73  5331.1  464.39  5428.1  469.38  5636.0  474.85
#Mann=3,-1,0
  4377.3    0.16       0  5005.2    0.07       0  5011.2    0.16       0
Bank Sta=5005.2,5011.2
Exp/Cntr=0.3,0.1

Type RM Length L Ch R = 1,6366,559,559,559
BEGIN DESCRIPTION:
STARRETT BRANCH 4.027
END DESCRIPTION:
XS GIS Cut Line= 2
      3576218.53     10480104.07      3575107.45     10480187.40
#Sta/Elev= 30
  4491.1  464.14  4507.6  462.57  4524.1  459.89  4529.1  459.90  4617.9  451.67
  4656.1  449.13  4661.1  449.36  4708.1  445.56  4728.2  444.34  4898.7  435.14
  4908.7  434.46  4958.8  429.37  4968.9  429.12  4978.9  430.00  4995.9  426.32
  4998.7  425.82  5001.9  426.32  5039.1  428.26  5069.1  432.41  5079.2  433.18
  5139.3  436.52  5194.3  440.26  5199.5  441.04  5229.6  443.26  5269.7  445.45
  5339.9  448.48  5360.0  449.82  5510.4  456.50  5570.5  459.81  5605.3  461.00
#Mann=3,-1,0
  4491.1    0.16       0  4995.9    0.07       0  5001.9    0.16       0
Bank Sta=4995.9,5001.9
Exp/Cntr=0.3,0.1

Type RM Length L Ch R = 1,5807,18,18,18
BEGIN DESCRIPTION:
STARRETT BRANCH 4.023
END DESCRIPTION:
XS GIS Cut Line= 5
      3576558.66     10479753.58      3575675.02     10479673.72
      3575574.33     10479654.63      3575461.48     10479658.10
      3575136.97     10480096.53
#Sta/Elev= 30
  4057.2  475.29  4131.7  471.21  4314.8  463.62  4415.2  457.24  4515.6  449.55
  4535.7  449.55  4579.8  446.50  4616.0  445.95  4667.8  443.14  4696.4  441.51
  4716.4  438.73  4746.6  439.04  4801.3  436.77  4857.0  433.48  4917.2  428.68
  4943.4  427.25  4982.7  426.45  5005.5  424.70  5008.2  424.20  5011.5  424.70
  5028.8  428.77  5040.1  428.94  5098.9  433.44  5129.8  435.63  5163.5  437.48
  5218.9  441.86  5309.6  445.29  5571.0  452.71  5690.6  457.67  5705.3  459.03
#Mann=8,-1,0
  4057.2    0.16       0  4667.8    0.05       0  5005.5   0.035       0
  5011.5    0.05       0  5098.9    0.16       0  5129.8    0.05       0
  5309.6    0.16       0  5571.0    0.05       0
Bank Sta=5005.5,5011.5
Exp/Cntr=0.3,0.1

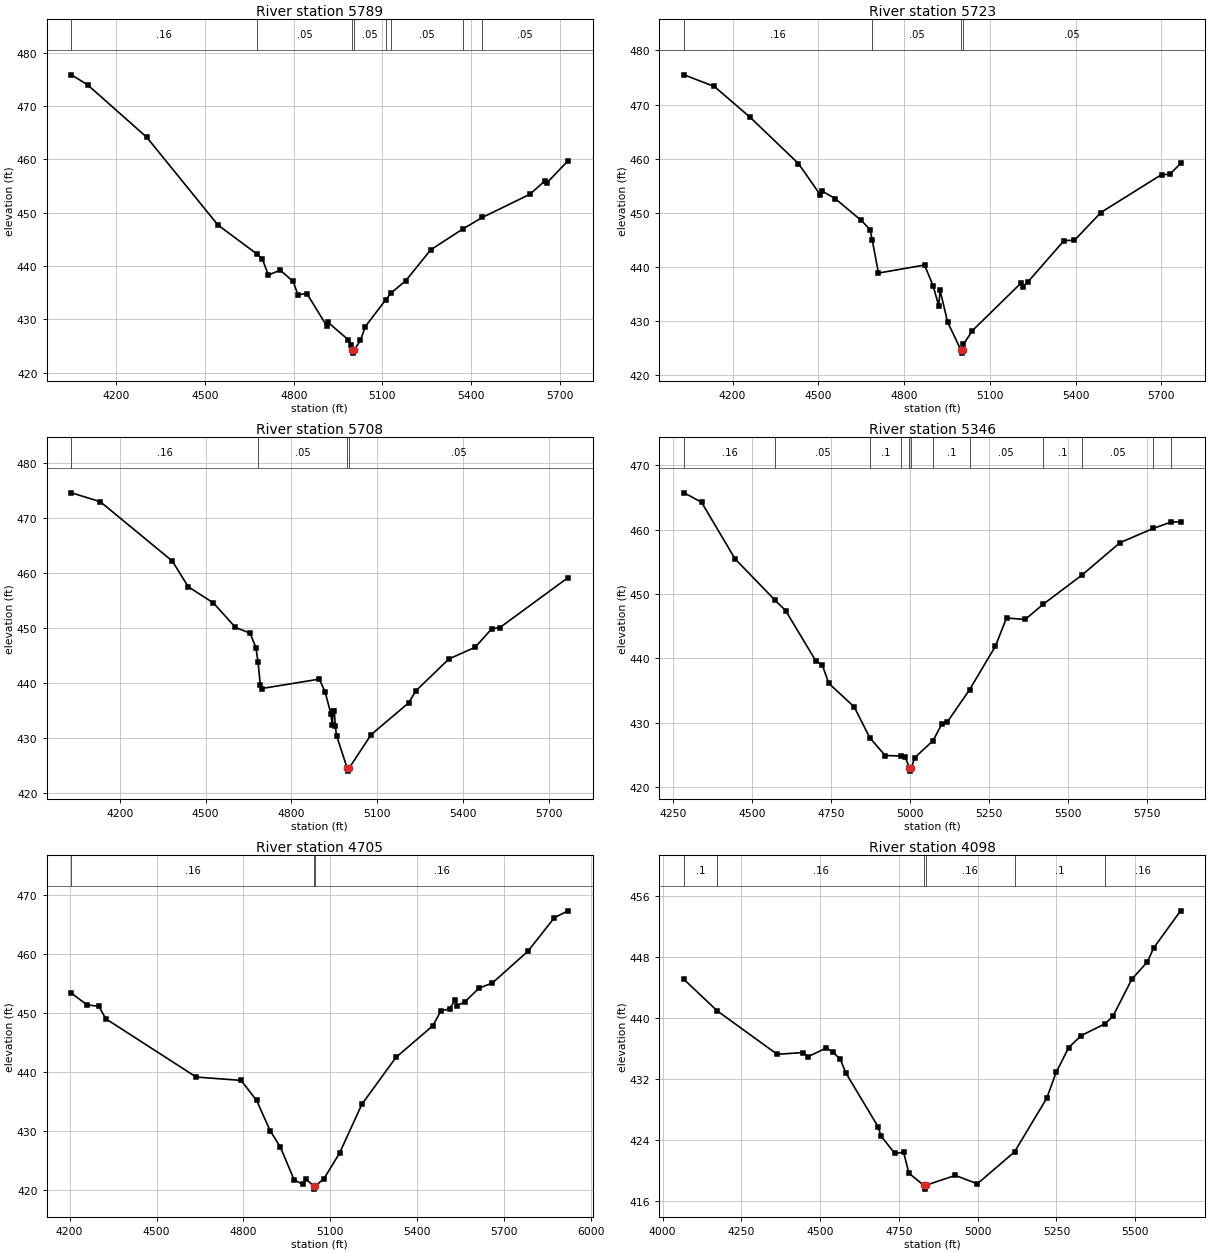
Type RM Length L Ch R = 1,5789,66,66,66
BEGIN DESCRIPTION:
STARRETT BRANCH 4.022
END DESCRIPTION:
XS GIS Cut Line= 5
      3576576.09     10479731.02      3575650.72     10479651.15
      3575584.74     10479639.00      3575449.33     10479640.74
      3575121.19     10480081.72
#Sta/Elev= 30
  4047.8  475.85  4102.8  473.95  4302.7  464.14  4543.6  447.69  4674.8  442.30
  4694.2  441.27  4714.3  438.31  4754.4  439.24  4798.0  437.11  4814.6  434.64
  4844.7  434.84  4911.4  428.82  4916.4  429.43  4985.4  426.17  4995.5  425.26
  4998.1  424.18  5000.8  423.68  5004.1  424.18  5026.0  426.07  5042.5  428.67
  5111.8  433.69  5129.4  434.95  5179.1  437.24  5263.9  443.05  5372.6  446.95
  5438.3  449.11  5599.7  453.46  5649.8  455.94  5656.0  455.53  5728.8  459.75
#Mann=8,-1,0
  4047.8    0.16       0  4674.8    0.05       0  4998.1   0.035       0
  5004.1    0.05       0  5111.8    0.16       0  5129.4    0.05       0
  5372.6    0.16       0  5438.3    0.05       0
Bank Sta=4998.1,5004.1
Exp/Cntr=0.3,0.1

Type RM Length L Ch R = 1,5723,15,15,15
BEGIN DESCRIPTION:
STARRETT BRANCH 4.020
END DESCRIPTION:
XS GIS Cut Line= 5
      3576607.36     10479694.56      3575678.49     10479581.71
      3575605.58     10479590.39      3575388.56     10479573.03
      3575064.12     10479966.87
#Sta/Elev= 30
  4030.2  475.49  4136.2  473.34  4261.9  467.62  4430.5  459.08  4507.2  453.28
  4512.2  454.04  4559.3  452.60  4650.0  448.58  4680.8  446.90  4688.5  445.00
  4710.4  438.85  4871.6  440.33  4901.8  436.47  4921.0  432.83  4926.0  435.67
  4952.2  429.80  4999.5  424.55  5002.3  424.05  5005.5  424.55  5007.6  425.65
  5038.6  428.19  5210.0  437.05  5215.0  436.32  5233.4  437.23  5359.5  444.85
  5396.1  444.91  5488.5  450.04  5701.0  457.06  5729.6  457.09  5767.3  459.12
#Mann=4,-1,0
  4030.2    0.16       0  4688.5    0.05       0  4999.5   0.035       0
  5005.5    0.05       0
Bank Sta=4999.5,5005.5
Exp/Cntr=0.3,0.1

Type RM Length L Ch R = 1,5708,362,362,362
BEGIN DESCRIPTION:
STARRETT BRANCH 4.021
END DESCRIPTION:
XS GIS Cut Line= 5
      3576602.10     10479675.46      3575692.38     10479566.08
      3575593.42     10479576.50      3575379.88     10479553.93
      3575056.19     10479941.67
#Sta/Elev= 30
  4031.5  474.62  4132.2  473.00  4384.0  462.20  4439.9  457.51  4527.1  454.60
  4604.3  450.15  4656.0  449.07  4676.1  446.46  4683.7  443.75  4691.5  439.62
  4696.5  439.01  4897.7  440.72  4917.8  438.42  4938.0  434.43  4943.1  432.30
  4945.4  434.84  4950.4  434.84  4953.1  432.25  4958.1  430.44  4995.3  424.48
  4998.1  423.98  5001.3  424.48  5078.8  430.62  5209.5  436.38  5235.4  438.60
  5350.5  444.38  5442.9  446.54  5500.2  449.88  5528.8  450.10  5767.1  459.19
#Mann=4,-1,0
  4031.5    0.16       0  4683.7    0.05       0  4995.3   0.035       0
  5001.3    0.05       0
Bank Sta=4995.3,5001.3
Exp/Cntr=0.3,0.1

Type RM Length L Ch R = 1,5346,641,641,641
BEGIN DESCRIPTION:
STARRETT BRANCH 4.025
END DESCRIPTION:
XS GIS Cut Line= 3
      3576257.03     10479146.20      3575469.29     10479246.03
      3574792.17     10479632.33
#Sta/Elev= 30
  4283.5  465.73  4338.9  464.27  4445.4  455.44  4571.9  449.03  4605.6  447.40
  4701.7  439.54  4721.9  438.92  4742.1  436.10  4822.7  432.44  4872.4  427.61
  4920.9  424.87  4972.5  424.79  4984.0  424.68  4998.0  422.94  5000.7  422.44
  5004.0  422.94  5014.2  424.51  5072.7  427.19  5101.0  429.81  5116.9  430.02
  5188.3  435.10  5270.0  441.85  5305.5  446.26  5364.6  446.03  5421.2  448.38
  5544.3  452.93  5665.6  457.99  5770.4  460.19  5828.1  461.20  5857.1  461.21
#Mann=12,-1,0
  4283.5    0.16       0  4571.9    0.05       0  4872.4     0.1       0
  4972.5    0.16       0  4998.0    0.07       0  5004.0    0.16       0
  5072.7     0.1       0  5188.3    0.05       0  5421.2     0.1       0
  5544.3    0.05       0  5770.4     0.1       0  5828.1    0.05       0
Bank Sta=4998,5004
Exp/Cntr=0.3,0.1

Type RM Length L Ch R = 1,4705,607,607,607
BEGIN DESCRIPTION:
STARRETT BRANCH 4.024
END DESCRIPTION:
XS GIS Cut Line= 3
      3576241.86     10478852.69      3575664.60     10478622.65
      3574606.34     10478891.56
#Sta/Elev= 30
  4206.6  453.31  4260.2  451.34  4300.9  451.10  4324.7  448.99  4636.9  439.10
  4791.6  438.53  4845.1  435.15  4892.5  429.95  4927.0  427.25  4975.0  421.64
  5003.7  420.93  5016.3  421.81  5041.7  420.59  5044.4  420.09  5047.7  420.59
  5078.2  421.89  5131.7  426.22  5208.4  434.47  5325.8  442.42  5454.0  447.83
  5480.6  450.29  5511.6  450.67  5530.8  452.23  5535.9  451.17  5563.1  451.82
  5612.6  454.17  5658.7  455.05  5781.6  460.44  5872.7  466.13  5919.9  467.29
#Mann=3,-1,0
  4206.6    0.16       0  5041.7    0.07       0  5047.7    0.16       0
Bank Sta=5041.7,5047.7
Exp/Cntr=0.3,0.1

Type RM Length L Ch R = 1,4098,400,400,400
BEGIN DESCRIPTION:
STARRETT BRANCH 4.019
END DESCRIPTION:
XS GIS Cut Line= 3
      3576193.00     10478488.79      3575442.96     10478110.30
      3574706.99     10478113.77
#Sta/Elev= 30
  4068.1  445.09  4173.5  440.97  4363.7  435.27  4447.3  435.50  4461.1  434.95
  4519.8  436.09  4542.1  435.51  4564.4  434.59  4581.1  432.86  4685.2  425.68
  4692.6  424.58  4737.2  422.25  4765.1  422.41  4781.8  419.66  4829.0  418.07
  4831.7  417.57  4835.0  418.07  4929.1  419.37  4999.1  418.27  5117.1  422.46
  5219.1  429.48  5249.1  432.88  5289.1  436.16  5329.1  437.73  5403.6  439.26
  5429.1  440.23  5489.1  445.10  5539.1  447.42  5559.1  449.25  5644.2  454.10
#Mann=6,-1,0
  4068.1     0.1       0  4173.5    0.16       0  4829.0    0.07       0
  4835.0    0.16       0  5117.1     0.1       0  5403.6    0.16       0
Bank Sta=4829,4835
Exp/Cntr=0.3,0.1

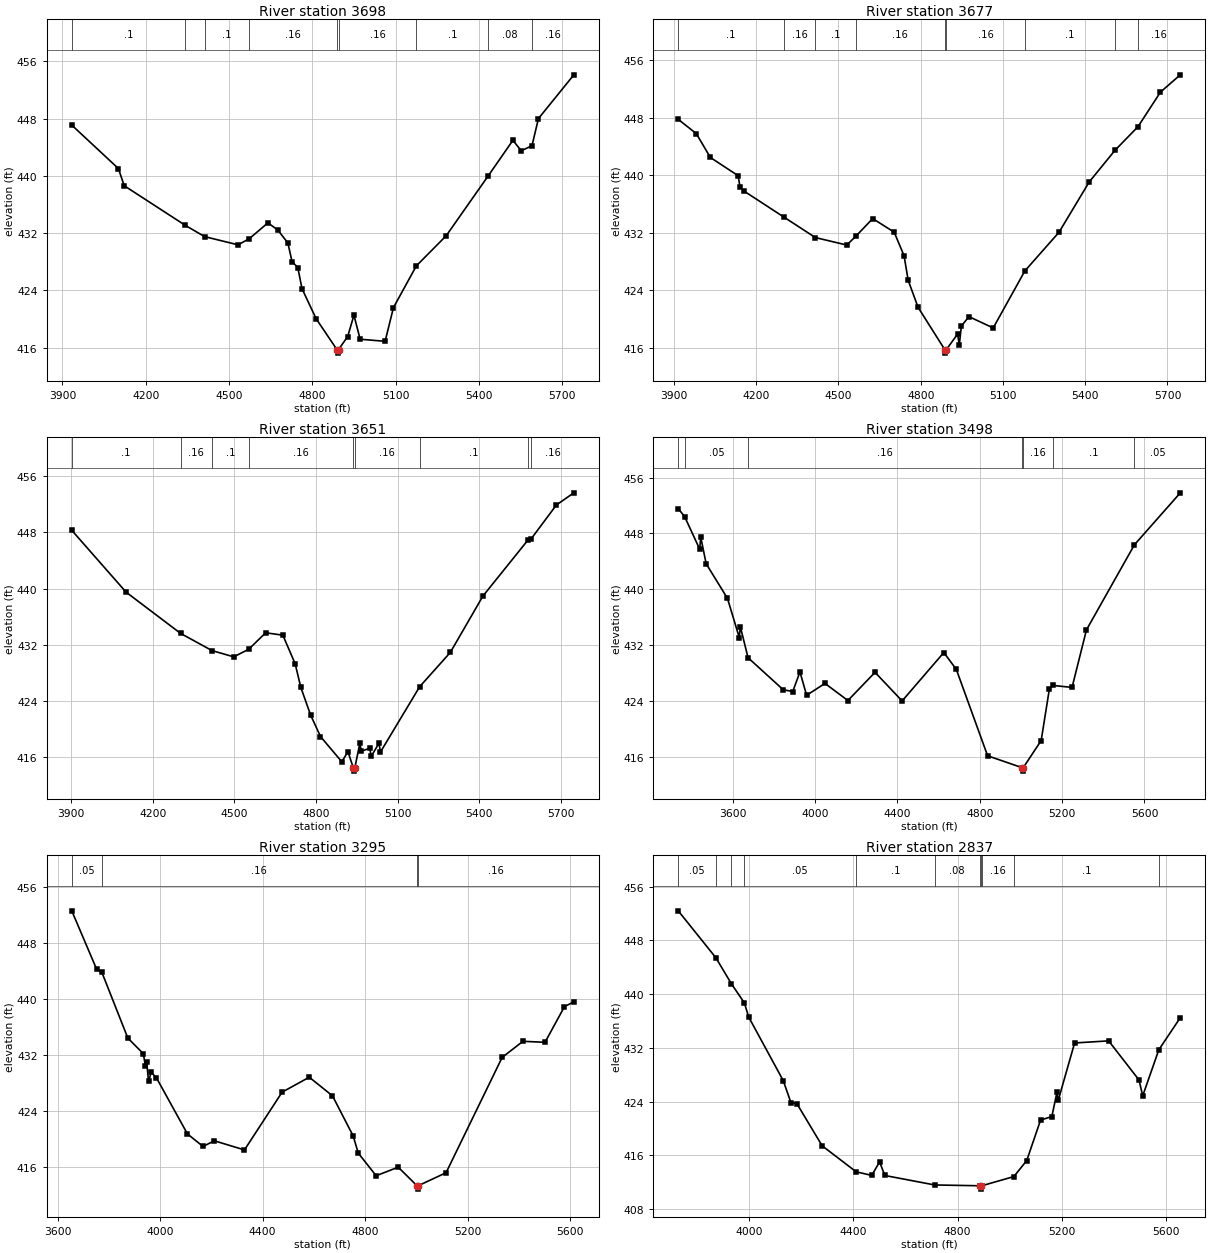
Type RM Length L Ch R = 1,3698,21,21,21
BEGIN DESCRIPTION:
STARRETT BRANCH 4.018
END DESCRIPTION:
XS GIS Cut Line= 4
      3576312.12     10478323.75      3575417.73     10477714.46
      3575389.95     10477707.52      3574692.76     10477681.83
#Sta/Elev= 30
  3933.5  447.08  4101.4  441.02  4122.4  438.62  4342.7  433.08  4412.3  431.51
  4532.4  430.37  4572.8  431.22  4640.1  433.44  4676.0  432.42  4711.9  430.63
  4726.9  428.03  4747.8  427.18  4762.8  424.25  4813.6  420.06  4888.5  415.75
  4891.2  415.25  4894.5  415.75  4927.4  417.57  4949.9  420.55  4972.2  417.19
  5062.2  416.90  5092.2  421.61  5174.9  427.44  5282.3  431.64  5433.6  440.00
  5522.5  444.96  5552.5  443.50  5591.2  444.20  5614.4  447.99  5742.0  454.10
#Mann=9,-1,0
  3933.5     0.1       0  4342.7    0.16       0  4412.3     0.1       0
  4572.8    0.16       0  4888.5    0.07       0  4894.5    0.16       0
  5174.9     0.1       0  5433.6    0.08       0  5591.2    0.16       0
Bank Sta=4888.5,4894.5
Exp/Cntr=0.3,0.1

Type RM Length L Ch R = 1,3677,26,26,26
BEGIN DESCRIPTION:
STARRETT BRANCH 4.016
END DESCRIPTION:
XS GIS Cut Line= 6
      3576334.19     10478301.78      3575463.72     10477727.38
      3575450.95     10477714.96      3575404.08     10477686.32
      3575358.94     10477681.98      3574689.71     10477672.60
#Sta/Elev= 30
  3915.6  447.75  3981.6  445.76  4032.7  442.45  4134.2  439.91  4141.0  438.30
  4156.0  437.76  4300.1  434.18  4415.8  431.31  4530.4  430.27  4563.0  431.48
  4625.0  433.95  4703.2  432.06  4739.3  428.78  4754.3  425.37  4790.4  421.61
  4887.6  415.74  4890.3  415.24  4893.6  415.74  4934.7  417.90  4940.7  416.39
  4948.3  419.00  4975.8  420.32  5064.4  418.74  5179.9  426.67  5304.5  432.05
  5414.5  439.04  5509.0  443.46  5592.6  446.73  5674.5  451.54  5746.9  453.94
#Mann=9,-1,0
  3915.6     0.1       0  4300.1    0.16       0  4415.8     0.1       0
  4563.0    0.16       0  4887.6    0.07       0  4893.6    0.16       0
  5179.9     0.1       0  5509.0    0.08       0  5592.6    0.16       0
Bank Sta=4887.6,4893.6
Exp/Cntr=0.3,0.1

Type RM Length L Ch R = 1,3651,153,153,153
BEGIN DESCRIPTION:
STARRETT BRANCH 4.017
END DESCRIPTION:
XS GIS Cut Line= 4
      3576348.64     10478281.91      3575470.36     10477700.51
      3575418.27     10477666.87      3574688.02     10477657.11
#Sta/Elev= 30
  3902.0  448.31  4101.7  439.50  4302.1  433.62  4417.7  431.17  4497.5  430.28
  4552.3  431.36  4614.7  433.71  4677.9  433.37  4723.1  429.30  4744.1  425.92
  4780.2  421.97  4816.3  418.93  4894.5  415.34  4917.2  416.76  4936.7  414.50
  4939.4  414.00  4942.7  414.50  4960.8  417.94  4966.7  416.83  4997.1  417.26
  5003.0  416.12  5031.5  417.99  5036.5  416.71  5180.9  426.03  5293.5  430.91
  5413.5  438.95  5578.5  446.90  5591.0  447.11  5683.5  451.92  5747.6  453.65
#Mann=9,-1,0
  3902.0     0.1       0  4302.1    0.16       0  4417.7     0.1       0
  4552.3    0.16       0  4936.7    0.07       0  4942.7    0.16       0
  5180.9     0.1       0  5578.5    0.08       0  5591.0    0.16       0
Bank Sta=4936.7,4942.7
Exp/Cntr=0.3,0.1

Type RM Length L Ch R = 1,3498,203,203,203
BEGIN DESCRIPTION:
STARRETT BRANCH 4.015
END DESCRIPTION:
XS GIS Cut Line= 3
      3577045.93     10477763.57      3575552.92     10477527.46
      3574626.49     10477541.34
#Sta/Elev= 30
  3335.9  451.55  3366.8  450.42  3440.1  445.74  3445.2  447.47  3471.4  443.66
  3575.0  438.69  3632.3  433.07  3637.4  434.65  3674.8  430.19  3846.0  425.59
  3892.0  425.34  3927.0  428.15  3959.4  424.80  4048.5  426.50  4159.8  424.05
  4291.5  428.09  4423.1  423.99  4625.6  430.93  4686.3  428.51  4838.2  416.13
  5005.3  414.43  5008.0  413.93  5011.3  414.43  5098.3  418.31  5138.3  425.73
  5155.4  426.21  5248.3  425.93  5318.3  434.18  5551.1  446.37  5774.0  453.82
#Mann=7,-1,0
  3335.9    0.16       0  3366.8    0.05       0  3674.8    0.16       0
  5005.3    0.07       0  5011.3    0.16       0  5155.4     0.1       0
  5551.1    0.05       0
Bank Sta=5005.3,5011.3
Exp/Cntr=0.3,0.1

Type RM Length L Ch R = 1,3295,458,458,458
BEGIN DESCRIPTION:
STARRETT BRANCH 4.026
END DESCRIPTION:
XS GIS Cut Line= 3
      3576788.44     10477252.94      3575884.48     10477390.67
      3574847.14     10477262.63
#Sta/Elev= 30
  3655.2  452.55  3752.6  444.19  3772.5  443.80  3874.0  434.40  3934.7  432.17
  3942.6  430.40  3947.6  430.95  3955.0  428.21  3965.1  429.53  3985.3  428.76
  4106.7  420.73  4167.4  418.95  4211.9  419.75  4329.2  418.45  4476.2  426.69
  4582.1  428.82  4672.7  426.17  4753.3  420.46  4773.5  417.99  4843.2  414.77
  4929.3  415.99  5002.2  413.36  5005.0  412.86  5008.2  413.36  5116.1  415.20
  5334.9  431.64  5416.1  433.94  5502.2  433.80  5578.3  438.89  5614.8  439.57
#Mann=4,-1,0
  3655.2    0.05       0  3772.5    0.16       0  5002.2    0.07       0
  5008.2    0.16       0
Bank Sta=5002.2,5008.2
Exp/Cntr=0.3,0.1

Type RM Length L Ch R = 1,2837,29,29,29
BEGIN DESCRIPTION:
STARRETT BRANCH 4.014
END DESCRIPTION:
XS GIS Cut Line= 6
      3576775.12     10477132.49      3576241.29     10476853.85
      3576017.33     10476835.62      3575642.33     10476913.75
      3575517.33     10476898.12      3574935.59     10476989.02
#Sta/Elev= 30
  3728.9  452.40  3873.1  445.42  3932.4  441.56  3982.4  438.69  3999.1  436.58
  4131.6  427.11  4161.0  423.83  4183.5  423.71  4280.6  417.42  4411.0  413.55
  4470.7  413.01  4500.8  415.03  4520.9  413.00  4712.1  411.59  4885.0  411.47
  4887.7  410.97  4891.0  411.47  4893.5  411.48  5015.5  412.84  5064.8  415.22
  5117.8  421.24  5161.2  421.78  5180.6  425.38  5185.6  424.18  5248.4  432.73
  5378.9  433.04  5495.2  427.22  5509.5  424.86  5571.2  431.71  5653.6  436.50
#Mann=11,-1,0
  3728.9    0.05       0  3873.1    0.16       0  3932.4     0.1       0
  3982.4    0.05       0  4411.0     0.1       0  4712.1    0.08       0
  4885.0    0.07       0  4891.0    0.08       0  4893.5    0.16       0
  5015.5     0.1       0  5571.2    0.16       0
Bank Sta=4885,4891
Exp/Cntr=0.3,0.1

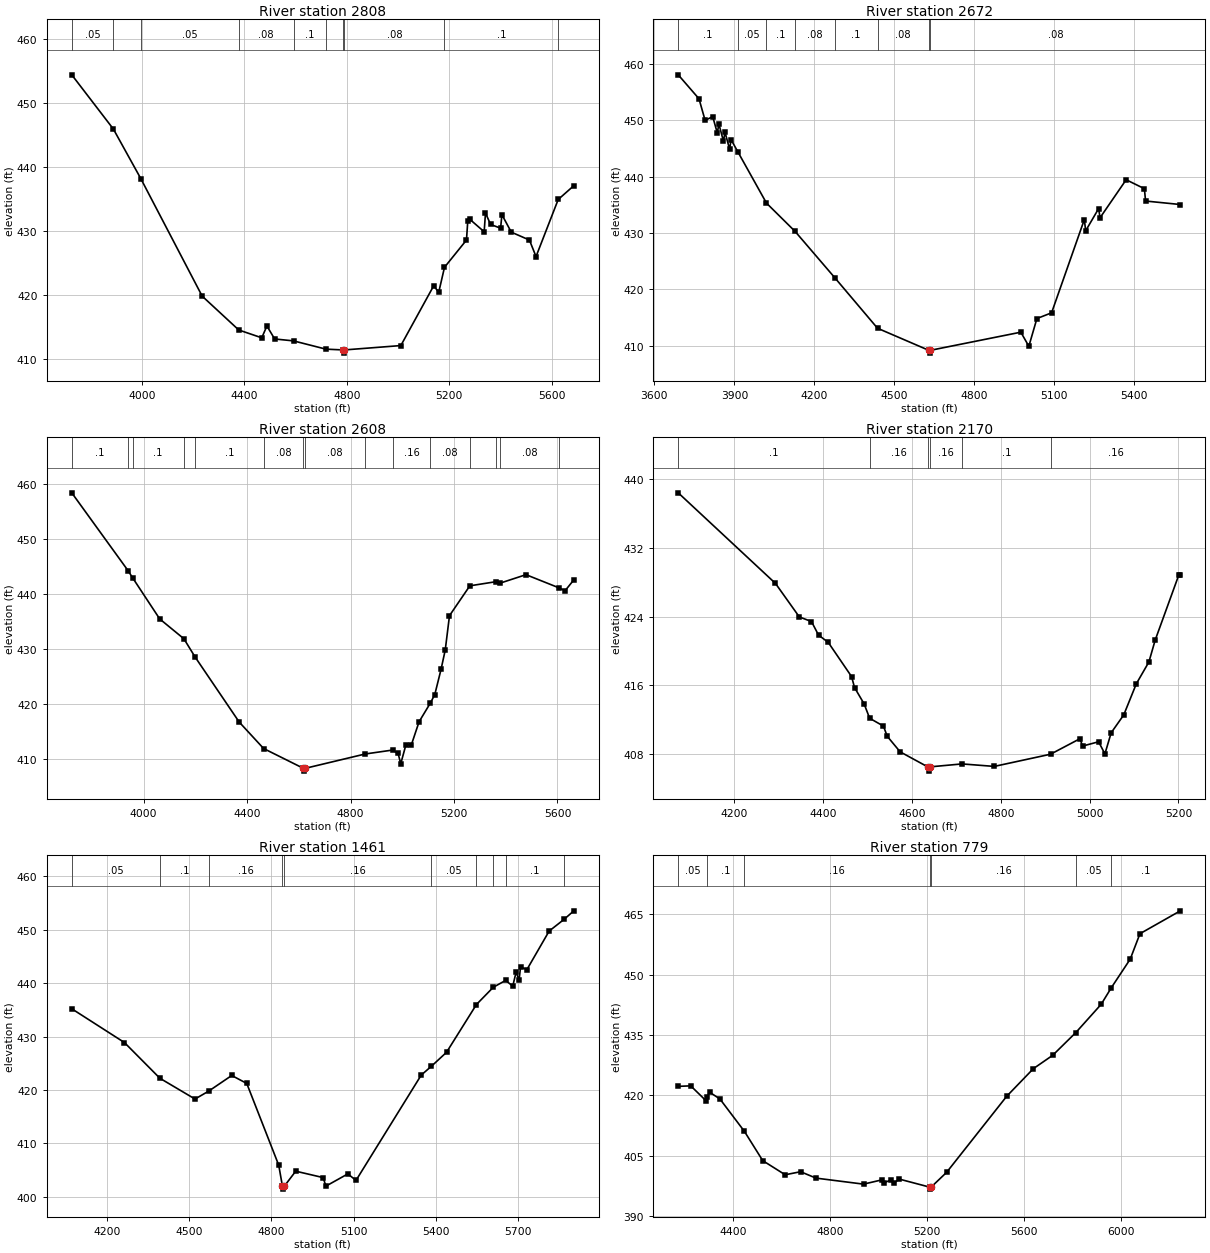
Type RM Length L Ch R = 1,2808,136,136,136
BEGIN DESCRIPTION:
STARRETT BRANCH 4.013
END DESCRIPTION:
XS GIS Cut Line= 6
      3576795.93     10477085.60      3576264.73     10476833.02
      3576032.96     10476809.58      3575642.33     10476887.71
      3575553.79     10476872.08      3574910.59     10476968.43
#Sta/Elev= 30
  3726.4  454.37  3888.8  445.91  3996.3  438.15  4235.4  419.85  4378.2  414.57
  4468.0  413.35  4488.1  415.19  4518.3  413.17  4591.9  412.87  4718.6  411.58
  4784.8  411.46  4787.5  410.96  4790.8  411.46  5010.9  412.14  5138.9  421.45
  5158.9  420.47  5181.3  424.35  5267.1  428.60  5272.1  431.54  5280.2  431.83
  5336.2  429.89  5341.3  432.83  5361.1  431.03  5400.3  430.45  5405.4  432.56
  5442.0  429.83  5512.8  428.60  5538.6  426.02  5625.2  434.93  5686.2  437.08
#Mann=10,-1,0
  3726.4    0.05       0  3888.8     0.1       0  3996.3    0.05       0
  4378.2    0.08       0  4591.9     0.1       0  4718.6    0.08       0
  4784.8    0.07       0  4790.8    0.08       0  5181.3     0.1       0
  5625.2    0.08       0
Bank Sta=4784.8,4790.8
Exp/Cntr=0.3,0.1

Type RM Length L Ch R = 1,2672,64,64,64
BEGIN DESCRIPTION:
STARRETT BRANCH 4.011
END DESCRIPTION:
XS GIS Cut Line= 6
      3576858.46     10476978.84      3576309.00     10476726.25
      3575993.89     10476702.81      3575517.33     10476754.89
      3575168.37     10476817.39      3575041.34     10476834.49
#Sta/Elev= 30
  3689.5  458.08  3767.3  453.83  3790.3  449.99  3818.8  450.66  3836.2  447.72
  3841.7  449.40  3859.2  446.27  3864.7  447.92  3882.2  444.87  3887.7  446.56
  3914.1  444.32  4020.4  435.30  4127.8  430.27  4277.3  422.01  4436.8  413.08
  4629.1  409.16  4631.9  408.66  4635.1  409.16  4974.2  412.38  5004.3  409.88
  5034.5  414.80  5089.6  415.82  5212.4  432.38  5217.4  430.38  5266.1  434.34
  5271.2  432.69  5369.2  439.45  5437.6  437.86  5442.0  435.67  5572.3  435.05
#Mann=8,-1,0
  3689.5     0.1       0  3914.1    0.05       0  4020.4     0.1       0
  4127.8    0.08       0  4277.3     0.1       0  4436.8    0.08       0
  4629.1    0.07       0  4635.1    0.08       0
Bank Sta=4629.1,4635.1
Exp/Cntr=0.3,0.1

Type RM Length L Ch R = 1,2608,438,438,438
BEGIN DESCRIPTION:
STARRETT BRANCH 4.012
END DESCRIPTION:
XS GIS Cut Line= 6
      3576850.65     10476947.60      3576342.85     10476697.60
      3575999.10     10476658.54      3575684.00     10476697.60
      3575454.83     10476661.14      3574978.29     10476715.83
#Sta/Elev= 30
  3722.1  458.34  3939.4  444.25  3957.0  442.96  4062.2  435.47  4155.6  431.88
  4198.4  428.61  4369.4  416.78  4463.8  411.98  4618.0  408.38  4620.7  407.88
  4624.0  408.38  4856.8  410.99  4962.4  411.70  4983.9  411.09  4994.0  409.21
  5014.3  412.70  5034.5  412.56  5064.9  416.83  5108.6  420.23  5125.6  421.76
  5149.8  426.32  5166.1  429.85  5182.5  436.07  5261.2  441.48  5361.2  442.22
  5377.8  441.96  5478.3  443.50  5607.0  441.09  5629.3  440.59  5663.3  442.56
#Mann=15,-1,0
  3722.1     0.1       0  3939.4    0.05       0  3957.0     0.1       0
  4155.6    0.08       0  4198.4     0.1       0  4463.8    0.08       0
  4618.0    0.07       0  4624.0    0.08       0  4856.8     0.1       0
  4962.4    0.16       0  5108.6    0.08       0  5261.2    0.16       0
  5361.2    0.05       0  5377.8    0.08       0  5607.0    0.05       0
Bank Sta=4618,4624
Exp/Cntr=0.3,0.1

Type RM Length L Ch R = 1,2170,709,709,709
BEGIN DESCRIPTION:
STARRETT BRANCH 4.0
END DESCRIPTION:
XS GIS Cut Line= 3
      3576592.09     10476741.63      3575792.11     10476291.64
      3575642.10     10476141.64
#Sta/Elev= 30
  4074.2  438.43  4293.1  427.87  4346.7  423.97  4374.1  423.43  4390.0  421.85
  4411.7  421.01  4464.3  417.02  4471.0  415.74  4492.6  413.83  4505.0  412.16
  4536.0  411.25  4544.6  410.06  4573.6  408.25  4635.6  406.50  4638.4  406.00
  4641.6  406.50  4712.9  406.84  4785.5  406.55  4912.1  407.97  4978.4  409.78
  4984.1  408.92  5020.3  409.42  5034.5  408.01  5048.6  410.47  5076.9  412.55
  5105.2  416.18  5133.5  418.72  5147.6  421.26  5200.7  428.84  5204.2  428.84
#Mann=6,-1,0
  4074.2     0.1       0  4505.0    0.16       0  4635.6    0.07       0
  4641.6    0.16       0  4712.9     0.1       0  4912.1    0.16       0
Bank Sta=4635.6,4641.6
Exp/Cntr=0.3,0.1

Type RM Length L Ch R = 1,1461,682,682,682
BEGIN DESCRIPTION:
STARRETT BRANCH 2.0
END DESCRIPTION:
XS GIS Cut Line= 4
      3577073.75     10476188.06      3576355.03     10475823.50
      3576045.14     10475802.66      3575389.86     10475506.23
#Sta/Elev= 30
  4069.9  435.21  4262.4  428.89  4392.1  422.20  4520.5  418.31  4570.8  419.80
  4654.8  422.72  4709.7  421.23  4826.6  405.92  4840.3  401.94  4843.0  401.44
  4846.3  401.94  4888.7  404.80  4989.0  403.60  4999.0  402.00  5079.2  404.29
  5109.2  403.08  5347.7  422.80  5385.1  424.46  5440.1  427.06  5549.5  436.01
  5610.9  439.23  5656.1  440.52  5682.2  439.45  5694.6  442.10  5705.3  440.57
  5710.8  443.05  5733.9  442.54  5815.3  449.76  5869.3  451.93  5905.6  453.55
#Mann=10,-1,0
  4069.9    0.05       0  4392.1     0.1       0  4570.8    0.16       0
  4840.3    0.07       0  4846.3    0.16       0  5385.1    0.05       0
  5549.5     0.1       0  5610.9    0.16       0  5656.1     0.1       0
  5869.3    0.05       0
Bank Sta=4840.3,4846.3
Exp/Cntr=0.3,0.1

Type RM Length L Ch R = 1,779,0,0,0
BEGIN DESCRIPTION:
STARRETT BRANCH 1.0
END DESCRIPTION:
XS GIS Cut Line= 4
      3577073.81     10475732.37      3576550.35     10475271.41
      3576170.14     10475117.77      3575205.52     10475115.17
#Sta/Elev= 30
  4172.0  422.23  4223.5  422.36  4287.1  418.63  4292.0  419.67  4301.3  420.78
  4344.0  419.10  4445.3  411.02  4520.7  403.76  4613.4  400.24  4677.0  401.00
  4740.5  399.41  4936.7  397.91  5014.4  399.00  5019.8  398.20  5051.0  398.99
  5061.7  398.08  5083.3  399.18  5209.7  397.17  5212.5  396.67  5215.7  397.17
  5279.6  400.84  5527.6  419.76  5637.6  426.63  5717.6  429.96  5813.1  435.62
  5917.6  442.64  5959.7  446.79  6037.6  453.89  6077.6  460.20  6244.2  465.89
#Mann=7,-1,0
  4172.0    0.05       0  4292.0     0.1       0  4445.3    0.16       0
  5209.7    0.07       0  5215.7    0.16       0  5813.1    0.05       0
  5959.7     0.1       0
Bank Sta=5209.7,5215.7
Exp/Cntr=0.3,0.1

Chan Stop Cuts=-1