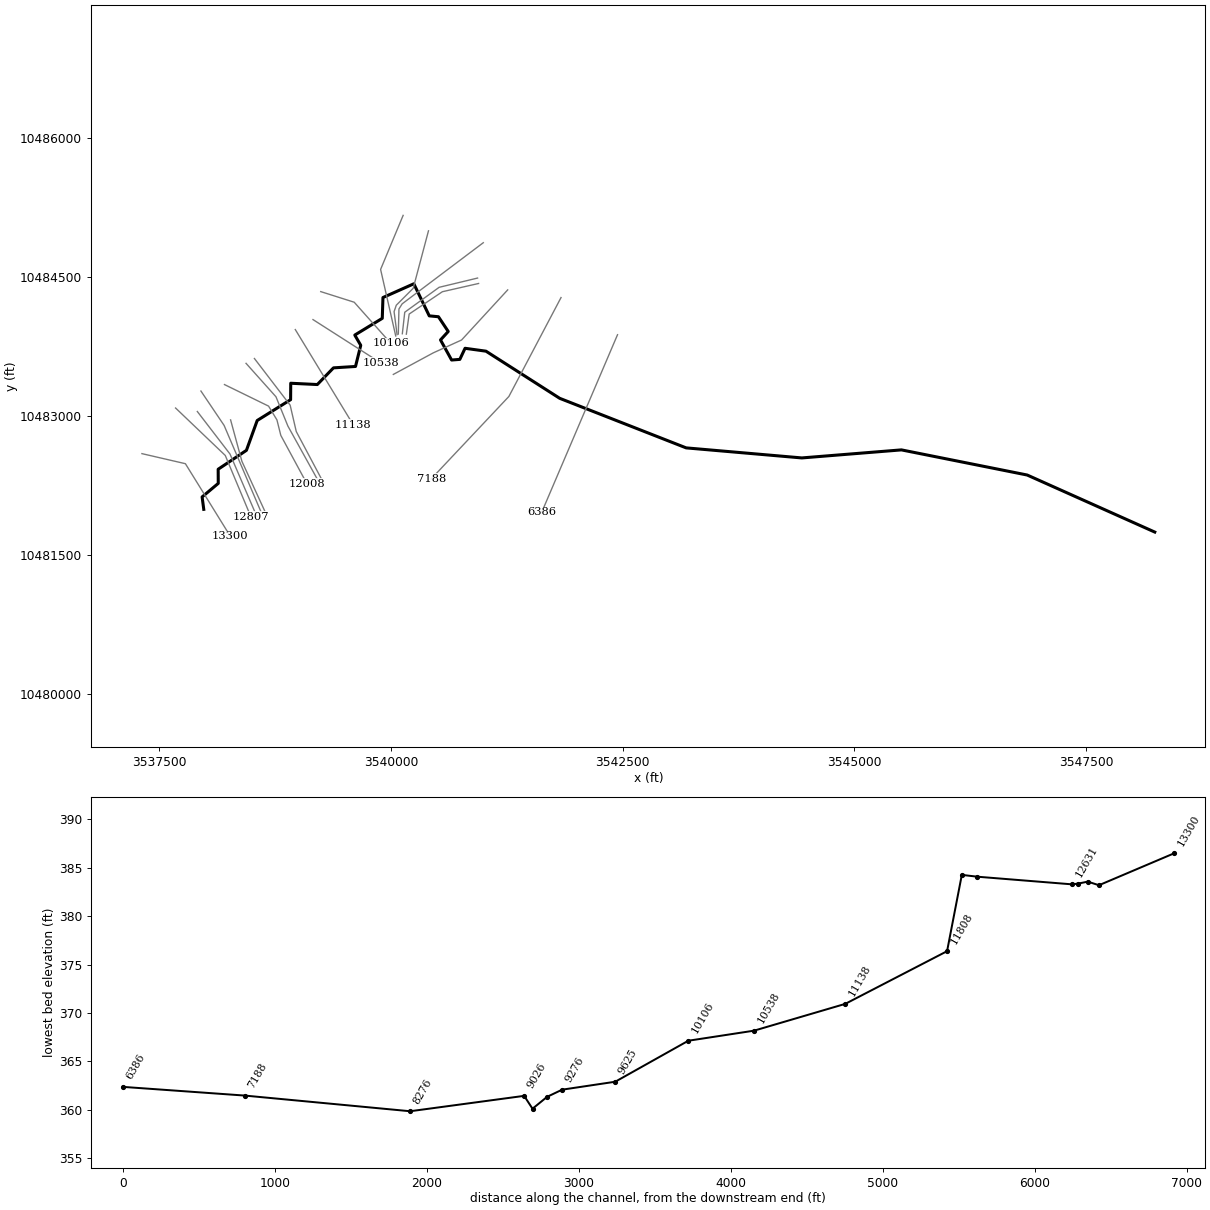
--- STEEPLETON BRANCH.prj (project) ---

Proj Title=STEEPLETON BRANCH Base Level Engineering
Current Plan=p01
Default Exp/Contr=0.3,0.1
English Units
Geom File=g01
Flow File=f01
Plan File=p01
BEGIN DESCRIPTION:
STEEPLETON BRANCH
END DESCRIPTION:

--- STEEPLETON BRANCH.p01 (plan) ---

Plan Title=Multiple Run
Short Identifier=Multiple
Geom File=g01
Flow File=f01
Subcritical Flow
K Sum by GR= 0
Std Step Tol= 0.01
Critical Tol= 0.01
Num of Std Step Trials= 20
Max Error Tol= 0.3
Flow Tol Ratio= 0.001
Split Flow NTrial= 30
Split Flow Tol= 0.02
Split Flow Ratio= 0.02
Log Output Level= 0
Friction Slope Method= 1
Unsteady Friction Slope Method= 2
Unsteady Bridges Friction Slope Method= 1
Parabolic Critical Depth
Global Vel Dist=  1 , 1 , 1
Global Log Level= 0
CheckData=True
Encroach Param= -1, 0, 0, 0
BEGIN DESCRIPTION:
Multiple Run
END DESCRIPTION:

--- STEEPLETON BRANCH.f01 (steady flow) ---

Flow Title=Multiple
Number of Profiles=7
Profile Names=10-year,25-year,50-year,1pct_min,100-year,1pct_plu,500-year
River Rch & RM= STEEPLETON BRANC,Reach-1,13300
    1087    1495    1831    1635    2212    2991    3218
River Rch & RM= STEEPLETON BRANC,Reach-1,9081
    1319    1824    2240    2004    2711    3666    3960
Boundary for River Rch & Prof#=STEEPLETON BRANC,Reach-1,1
Up Type=0
Dn Type=3
Dn Slope=0.005
Boundary for River Rch & Prof#=STEEPLETON BRANC,Reach-1,2
Up Type=0
Dn Type=3
Dn Slope=0.005
Boundary for River Rch & Prof#=STEEPLETON BRANC,Reach-1,3
Up Type=0
Dn Type=3
Dn Slope=0.005
Boundary for River Rch & Prof#=STEEPLETON BRANC,Reach-1,4
Up Type=0
Dn Type=3
Dn Slope=0.005
Boundary for River Rch & Prof#=STEEPLETON BRANC,Reach-1,5
Up Type=0
Dn Type=3
Dn Slope=0.005
Boundary for River Rch & Prof#=STEEPLETON BRANC,Reach-1,6
Up Type=0
Dn Type=3
Dn Slope=0.005
Boundary for River Rch & Prof#=STEEPLETON BRANC,Reach-1,7
Up Type=0
Dn Type=3
Dn Slope=0.005

--- STEEPLETON BRANCH.g01 (geometry) ---

Geom Title=Existing Conditions

River Reach=STEEPLETON BRANC,Reach-1
Reach XY= 30
      3537982.11     10481996.64      3537964.38     10482130.64
      3538138.45     10482276.85      3538137.59     10482429.63
      3538442.27     10482633.62      3538558.59     10482955.67
      3538918.84     10483180.50      3538920.26     10483357.83
      3539206.80     10483343.91      3539381.39     10483523.99
      3539618.99     10483539.04      3539675.49     10483767.24
      3539611.08     10483877.98      3539907.57     10484058.46
      3539915.02     10484283.10      3540247.83     10484431.54
      3540414.50     10484085.19      3540513.45     10484075.81
      3540619.13     10483916.66      3540535.80     10483825.51
      3540655.59     10483608.50      3540744.13     10483615.44
      3540800.56     10483735.24      3541026.25     10483703.99
      3541821.72     10483195.02      3543185.44     10482660.19
      3544433.27     10482551.68      3545507.49     10482638.48
      3546863.82     10482367.22      3548240.25     10481751.34

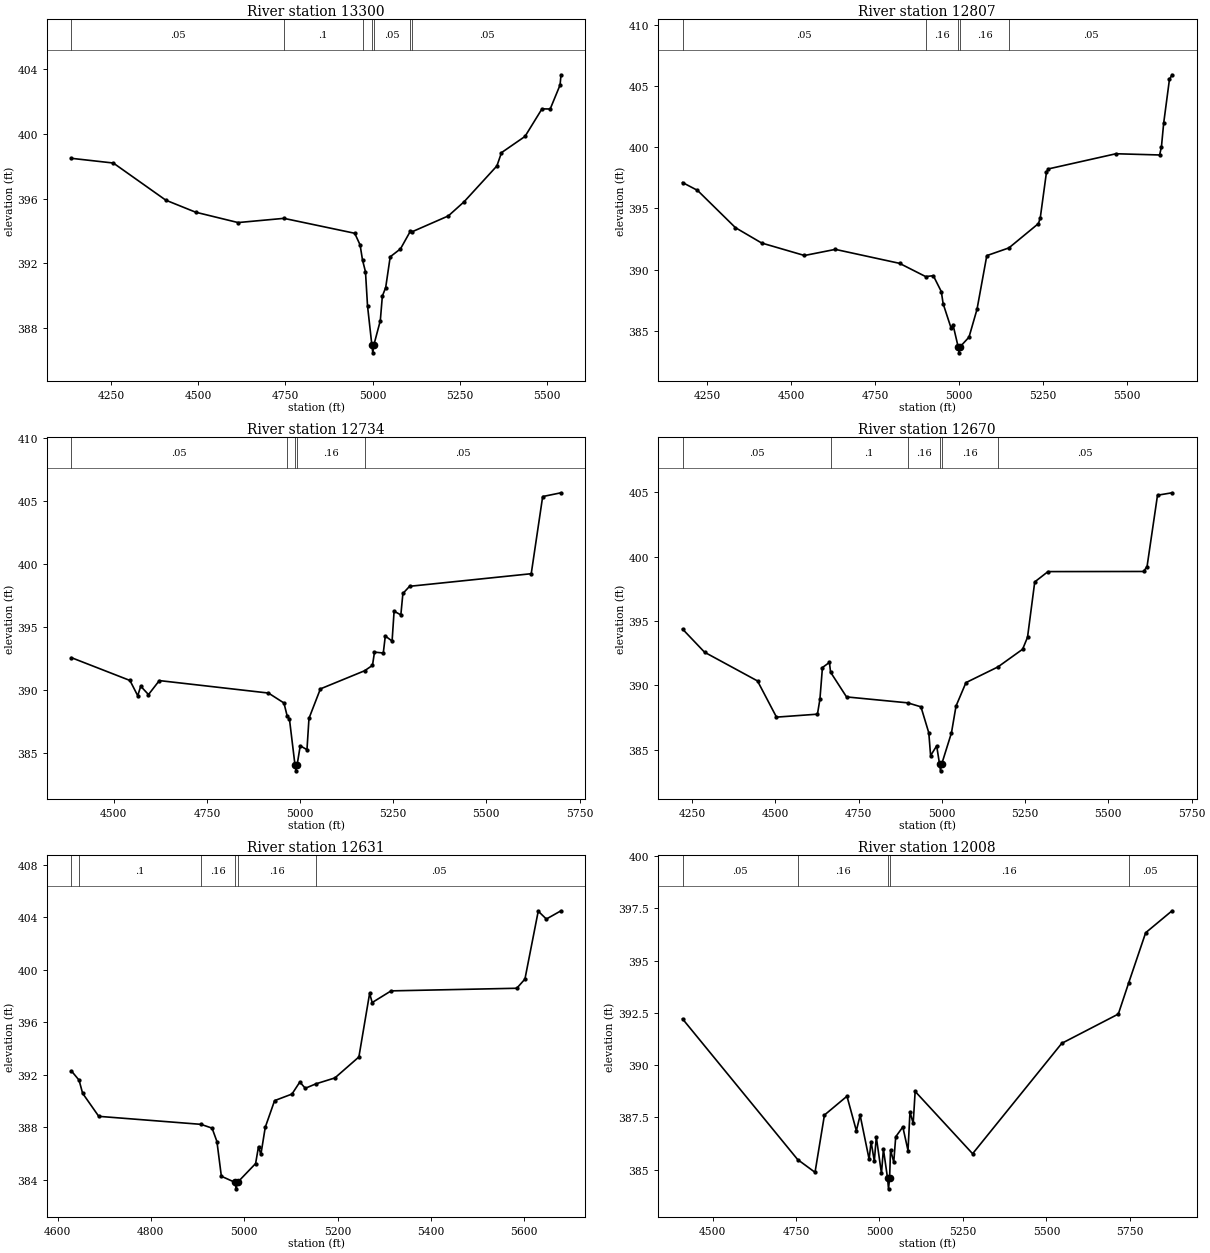
Type RM Length L Ch R = 1,13300,493,493,493
BEGIN DESCRIPTION:
STEEPLETON BRANCH 12.0
END DESCRIPTION:
XS GIS Cut Line= 3
      3537315.19     10482598.01      3537783.90     10482489.51
      3538269.15     10481705.31
#Sta/Elev= 30
  4136.6  398.48  4256.6  398.19  4407.1  395.90  4492.5  395.16  4614.2  394.52
  4745.6  394.78  4948.6  393.86  4964.0  393.14  4970.9  392.21  4979.4  391.49
  4985.3  389.38  4997.6  386.99  5000.4  386.49  5003.6  386.99  5021.9  388.47
  5027.8  389.99  5037.3  390.51  5050.3  392.41  5079.8  392.90  5107.6  393.97
  5113.8  393.96  5216.9  394.93  5262.0  395.80  5356.1  398.01  5369.3  398.83
  5436.7  399.83  5485.4  401.53  5508.9  401.52  5537.2  403.00  5539.9  403.63
#Mann=7,-1,0
  4136.6    0.05       0  4745.6     0.1       0  4970.9    0.05       0
  4997.6    0.03       0  5003.6    0.05       0  5107.6     0.1       0
  5113.8    0.05       0
Bank Sta=4997.6,5003.6
Exp/Cntr=0.3,0.1

Type RM Length L Ch R = 1,12807,73,73,73
BEGIN DESCRIPTION:
STEEPLETON BRANCH 12.02
END DESCRIPTION:
XS GIS Cut Line= 3
      3537678.12     10483090.45      3538214.13     10482578.31
      3538489.73     10481918.60
#Sta/Elev= 30
  4177.4  397.11  4221.9  396.47  4335.0  393.42  4412.8  392.17  4540.2  391.15
  4632.0  391.65  4822.9  390.51  4900.6  389.43  4923.5  389.50  4947.3  388.20
  4952.7  387.21  4976.5  385.21  4982.0  385.50  4997.3  383.70  5000.1  383.20
  5003.3  383.70  5029.6  384.48  5053.4  386.75  5082.6  391.14  5148.3  391.77
  5236.3  393.76  5241.7  394.24  5260.1  397.96  5265.5  398.22  5466.8  399.46
  5596.7  399.36  5602.1  400.03  5608.7  401.95  5625.9  405.53  5633.7  405.91
#Mann=5,-1,0
  4177.4    0.05       0  4900.6    0.16       0  4997.3    0.07       0
  5003.3    0.16       0  5148.3    0.05       0
Bank Sta=4997.3,5003.3
Exp/Cntr=0.3,0.1

Type RM Length L Ch R = 1,12734,64,64,64
BEGIN DESCRIPTION:
STEEPLETON BRANCH 12.01
END DESCRIPTION:
XS GIS Cut Line= 3
      3537912.80     10483052.69      3538265.46     10482593.14
      3538555.16     10481918.26
#Sta/Elev= 30
  4386.6  392.56  4543.5  390.75  4564.4  389.54  4572.5  390.29  4593.3  389.63
  4622.4  390.74  4915.2  389.75  4956.8  388.96  4965.6  387.91  4971.5  387.70
  4986.3  384.07  4989.0  383.57  4992.3  384.07  5000.5  385.56  5018.6  385.25
  5024.0  387.74  5054.6  390.08  5173.2  391.52  5194.4  391.95  5199.8  393.00
  5223.4  392.93  5228.8  394.28  5247.0  393.88  5252.4  396.25  5270.5  395.96
  5276.0  397.66  5294.0  398.23  5620.4  399.23  5651.1  405.36  5700.3  405.66
#Mann=5,-1,0
  4386.6    0.05       0  4965.6    0.16       0  4986.3    0.07       0
  4992.3    0.16       0  5173.2    0.05       0
Bank Sta=4986.3,4992.3
Exp/Cntr=0.3,0.1

Type RM Length L Ch R = 1,12670,39,39,39
BEGIN DESCRIPTION:
STEEPLETON BRANCH 12.03
END DESCRIPTION:
XS GIS Cut Line= 3
      3537951.56     10483273.71      3538201.54     10482902.63
      3538602.59     10481962.52
#Sta/Elev= 30
  4221.7  394.38  4287.9  392.58  4446.8  390.35  4503.8  387.54  4626.7  387.77
  4634.1  388.92  4641.7  391.39  4662.7  391.79  4666.1  391.03  4714.0  389.11
  4897.5  388.65  4937.4  388.34  4961.0  386.32  4966.4  384.55  4984.6  385.31
  4993.4  383.87  4996.1  383.37  4999.4  383.87  5029.0  386.32  5042.7  388.40
  5072.5  390.22  5168.6  391.44  5242.5  392.81  5257.3  393.74  5279.0  398.04
  5318.8  398.84  5605.7  398.85  5616.1  399.23  5647.5  404.77  5691.2  404.96
#Mann=6,-1,0
  4221.7    0.05       0  4666.1     0.1       0  4897.5    0.16       0
  4993.4    0.07       0  4999.4    0.16       0  5168.6    0.05       0
Bank Sta=4993.4,4999.4
Exp/Cntr=0.3,0.1

Type RM Length L Ch R = 1,12631,623,623,623
BEGIN DESCRIPTION:
STEEPLETON BRANCH 12.04
END DESCRIPTION:
XS GIS Cut Line= 3
      3538271.53     10482962.37      3538393.07     10482516.15
      3538637.87     10481983.15
#Sta/Elev= 30
  4629.9  392.28  4646.2  391.58  4653.8  390.58  4688.4  388.82  4907.4  388.21
  4931.2  387.92  4941.6  386.90  4951.1  384.25  4980.0  383.79  4982.8  383.29
  4986.0  383.79  5024.5  385.22  5030.7  386.51  5035.8  385.91  5045.2  387.99
  5065.2  390.02  5102.4  390.52  5119.3  391.44  5130.9  390.96  5153.8  391.30
  5194.4  391.75  5245.8  393.35  5268.8  398.20  5274.3  397.50  5314.8  398.39
  5584.1  398.59  5601.6  399.29  5630.1  404.47  5647.5  403.87  5678.9  404.50
#Mann=6,-1,0
  4629.9    0.05       0  4646.2     0.1       0  4907.4    0.16       0
  4980.0    0.07       0  4986.0    0.16       0  5153.8    0.05       0
Bank Sta=4980,4986
Exp/Cntr=0.3,0.1

Type RM Length L Ch R = 1,12008,103,103,103
BEGIN DESCRIPTION:
STEEPLETON BRANCH 12.06
END DESCRIPTION:
XS GIS Cut Line= 5
      3538205.60     10483343.57      3538681.26     10483110.95
      3538771.54     10482961.64      3538813.21     10482794.97
      3539093.80     10482275.36
#Sta/Elev= 30
  4410.0  392.21  4754.9  385.48  4806.9  384.87  4835.1  387.61  4902.6  388.51
  4930.7  386.86  4942.0  387.60  4969.0  385.49  4974.8  386.34  4984.5  385.40
  4990.4  386.56  5005.9  384.82  5011.7  385.98  5024.2  384.58  5027.0  384.08
  5030.2  384.58  5033.1  385.94  5042.7  385.36  5048.6  386.57  5069.9  387.04
  5085.4  385.91  5091.3  387.76  5100.9  387.21  5106.8  388.74  5278.9  385.76
  5545.9  391.04  5715.3  392.44  5746.1  393.92  5797.2  396.33  5876.3  397.38
#Mann=5,-1,0
  4410.0    0.05       0  4754.9    0.16       0  5024.2    0.07       0
  5030.2    0.16       0  5746.1    0.05       0
Bank Sta=5024.2,5030.2
Exp/Cntr=0.3,0.1

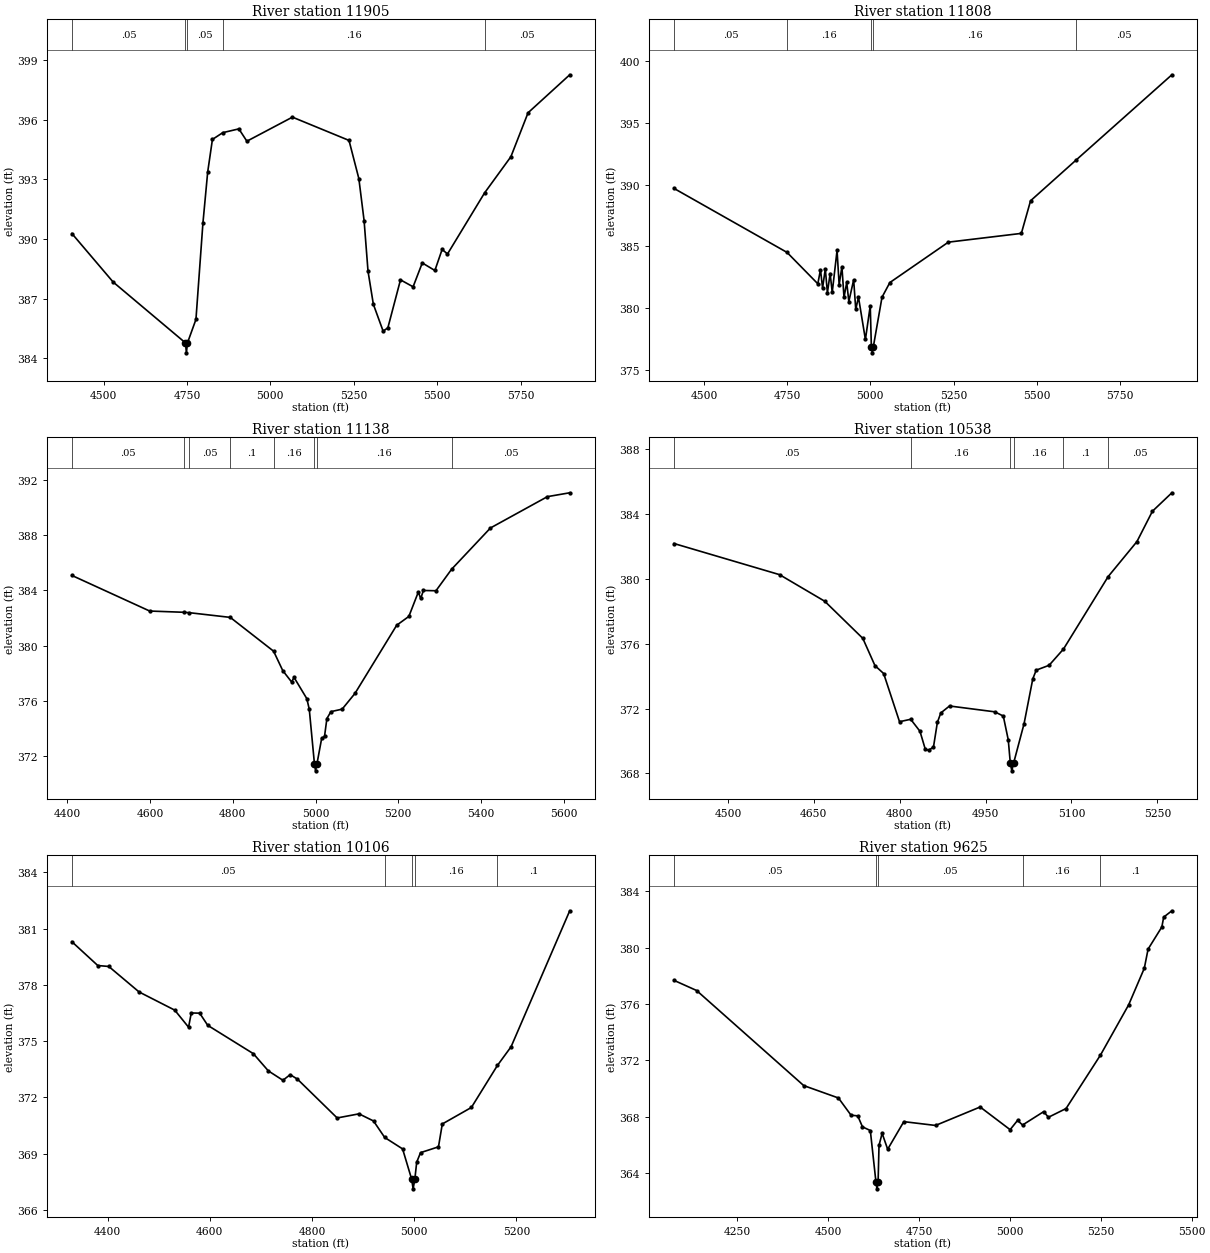
Type RM Length L Ch R = 1,11905,97,97,97
BEGIN DESCRIPTION:
STEEPLETON BRANCH 12.05
END DESCRIPTION:
XS GIS Cut Line= 4
      3538438.19     10483572.77      3538761.12     10483211.64
      3538889.59     10482895.67      3539212.51     10482312.34
#Sta/Elev= 30
  4405.1  390.27  4528.8  387.83  4745.6  384.77  4748.4  384.27  4751.6  384.77
  4777.0  385.95  4797.9  390.79  4812.2  393.36  4826.4  395.00  4857.4  395.34
  4905.6  395.53  4929.7  394.91  5066.2  396.12  5235.8  394.95  5265.3  393.03
  5281.0  390.92  5292.8  388.37  5308.8  386.71  5338.1  385.36  5352.3  385.53
  5390.1  387.94  5427.9  387.59  5455.4  388.79  5493.2  388.41  5514.9  389.47
  5531.0  389.24  5642.1  392.31  5721.0  394.13  5772.5  396.34  5897.4  398.25
#Mann=5,-1,0
  4405.1    0.05       0  4745.6    0.07       0  4751.6    0.05       0
  4857.4    0.16       0  5642.1    0.05       0
Bank Sta=4745.6,4751.6
Exp/Cntr=0.3,0.1

Type RM Length L Ch R = 1,11808,670,670,670
BEGIN DESCRIPTION:
STEEPLETON BRANCH 12.07
END DESCRIPTION:
XS GIS Cut Line= 4
      3538528.51     10483624.80      3538913.90     10483121.36
      3538979.87     10482836.64      3539247.21     10482333.21
#Sta/Elev= 30
  4410.0  389.69  4749.7  384.51  4842.2  381.97  4850.2  383.11  4856.5  381.63
  4864.7  383.18  4871.0  381.24  4879.2  382.80  4885.5  381.28  4900.0  384.67
  4906.3  381.90  4914.6  383.36  4920.9  380.87  4929.1  382.08  4935.4  380.53
  4949.9  382.29  4956.2  379.90  4964.4  380.89  4985.2  377.46  4999.8  380.19
  5003.1  376.88  5005.8  376.38  5009.1  376.88  5035.1  380.88  5058.7  382.07
  5234.5  385.34  5453.9  386.05  5481.6  388.69  5619.0  392.00  5906.3  398.89
#Mann=5,-1,0
  4410.0    0.05       0  4749.7    0.16       0  5003.1    0.07       0
  5009.1    0.16       0  5619.0    0.05       0
Bank Sta=5003.1,5009.1
Exp/Cntr=0.3,0.1

Type RM Length L Ch R = 1,11138,600,600,600
BEGIN DESCRIPTION:
STEEPLETON BRANCH 12.08
END DESCRIPTION:
XS GIS Cut Line= 2
      3538969.46     10483937.33      3539594.46     10482909.55
#Sta/Elev= 30
  4411.3  385.09  4599.3  382.51  4681.9  382.42  4695.2  382.39  4794.0  382.05
  4898.7  379.60  4920.9  378.19  4942.2  377.37  4948.1  377.70  4979.0  376.16
  4984.9  375.39  4997.4  371.43  5000.1  370.93  5003.4  371.43  5014.9  373.29
  5021.7  373.42  5027.5  374.72  5037.2  375.22  5064.3  375.40  5095.3  376.54
  5196.1  381.48  5225.5  382.12  5248.3  383.88  5254.2  383.42  5260.6  384.00
  5291.0  383.98  5328.8  385.54  5422.7  388.53  5560.3  390.80  5614.2  391.08
#Mann=8,-1,0
  4411.3    0.05       0  4681.9     0.1       0  4695.2    0.05       0
  4794.0     0.1       0  4898.7    0.16       0  4997.4    0.07       0
  5003.4    0.16       0  5328.8    0.05       0
Bank Sta=4997.4,5003.4
Exp/Cntr=0.3,0.1

Type RM Length L Ch R = 1,10538,432,432,432
BEGIN DESCRIPTION:
STEEPLETON BRANCH 12.09
END DESCRIPTION:
XS GIS Cut Line= 2
      3539160.40     10484044.99      3539892.74     10483576.43
#Sta/Elev= 30
  4405.9  382.18  4590.2  380.26  4669.1  378.62  4735.6  376.33  4756.8  374.65
  4772.0  374.16  4799.7  371.19  4819.2  371.34  4835.4  370.60  4844.7  369.49
  4850.6  369.43  4859.0  369.63  4865.8  371.15  4871.8  371.73  4887.0  372.16
  4965.9  371.80  4980.9  371.54  4989.6  370.07  4993.1  368.66  4995.8  368.16
  4999.1  368.66  5017.2  371.07  5032.4  373.83  5038.4  374.37  5060.9  374.67
  5086.0  375.67  5164.0  380.14  5214.3  382.30  5241.3  384.17  5275.3  385.31
#Mann=6,-1,0
  4405.9    0.05       0  4819.2    0.16       0  4993.1    0.07       0
  4999.1    0.16       0  5086.0     0.1       0  5164.0    0.05       0
Bank Sta=4993.1,4999.1
Exp/Cntr=0.3,0.1

Type RM Length L Ch R = 1,10106,481,481,481
BEGIN DESCRIPTION:
STEEPLETON BRANCH 12.1
END DESCRIPTION:
XS GIS Cut Line= 3
      3539243.77     10484347.05      3539604.87     10484232.47
      3540000.70     10483788.03
#Sta/Elev= 30
  4330.2  380.30  4380.9  379.03  4402.4  378.98  4461.7  377.62  4531.5  376.65
  4558.5  375.74  4563.8  376.50  4580.2  376.49  4596.0  375.84  4685.2  374.33
  4714.6  373.41  4743.1  372.91  4757.3  373.21  4771.5  372.97  4849.2  370.90
  4891.9  371.12  4920.3  370.74  4942.2  369.86  4977.2  369.25  4995.1  367.62
  4997.8  367.12  5001.1  367.62  5004.8  368.54  5012.3  369.05  5047.4  369.36
  5054.9  370.58  5111.8  371.46  5162.7  373.70  5189.5  374.70  5304.2  381.95
#Mann=5,-1,0
  4330.2    0.05       0  4942.2    0.16       0  4995.1    0.07       0
  5001.1    0.16       0  5162.7     0.1       0
Bank Sta=4995.1,5001.1
Exp/Cntr=0.3,0.1

Type RM Length L Ch R = 1,9625,349,349,349
BEGIN DESCRIPTION:
STEEPLETON BRANCH 12.11
END DESCRIPTION:
XS GIS Cut Line= 3
      3540132.64     10485169.95      3539889.59     10484586.64
      3540052.80     10483867.86
#Sta/Elev= 30
  4076.6  377.68  4138.7  376.96  4433.3  370.21  4528.7  369.33  4563.3  368.11
  4581.8  368.06  4594.8  367.28  4616.4  367.02  4631.8  363.38  4634.6  362.88
  4637.8  363.38  4640.3  365.97  4648.9  366.82  4664.1  365.69  4708.5  367.65
  4795.7  367.38  4918.4  368.69  5000.8  367.08  5021.3  367.74  5035.0  367.41
  5093.1  368.36  5106.1  367.96  5154.6  368.58  5249.1  372.37  5326.7  375.94
  5369.8  378.54  5380.2  379.90  5418.0  381.47  5423.1  382.17  5445.6  382.62
#Mann=5,-1,0
  4076.6    0.05       0  4631.8    0.03       0  4637.8    0.05       0
  5035.0    0.16       0  5249.1     0.1       0
Bank Sta=4631.8,4637.8
Exp/Cntr=0.3,0.1

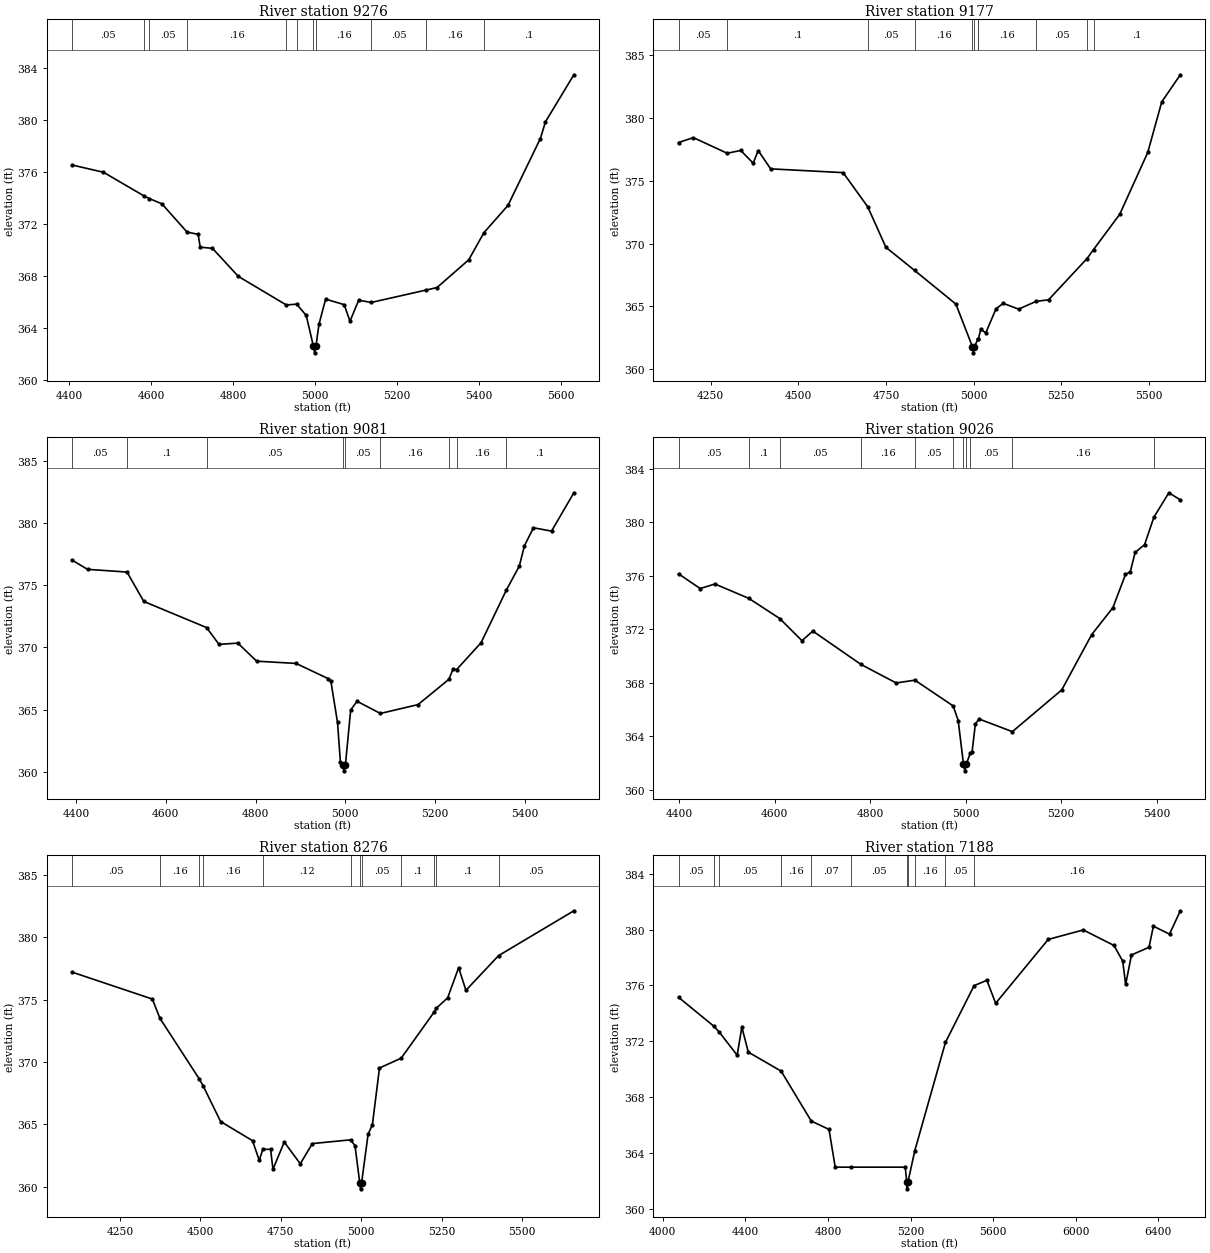
Type RM Length L Ch R = 1,9276,99,99,99
BEGIN DESCRIPTION:
STEEPLETON BRANCH 12.13
END DESCRIPTION:
XS GIS Cut Line= 5
      3540406.10     10485003.34      3540241.16     10484382.65
      3540058.87     10484200.35      3540034.99     10484130.91
      3540067.32     10483883.07
#Sta/Elev= 30
  4407.3  376.53  4483.9  375.97  4581.5  374.17  4596.0  373.94  4626.3  373.54
  4687.7  371.36  4714.6  371.19  4719.8  370.20  4749.6  370.11  4812.6  367.95
  4929.6  365.75  4954.8  365.81  4978.1  364.95  4995.8  362.56  4998.6  362.06
  5001.8  362.56  5009.2  364.25  5025.5  366.20  5070.8  365.77  5084.9  364.49
  5106.1  366.12  5136.5  365.94  5271.0  366.90  5297.1  367.09  5374.5  369.23
  5411.3  371.31  5470.1  373.42  5549.1  378.57  5561.5  379.86  5630.7  383.48
#Mann=11,-1,0
  4407.3    0.05       0  4581.5     0.1       0  4596.0    0.05       0
  4687.7    0.16       0  4929.6    0.05       0  4954.8    0.16       0
  4995.8    0.07       0  5001.8    0.16       0  5136.5    0.05       0
  5271.0    0.16       0  5411.3     0.1       0
Bank Sta=4995.8,5001.8
Exp/Cntr=0.3,0.1

Type RM Length L Ch R = 1,9177,96,96,96
BEGIN DESCRIPTION:
STEEPLETON BRANCH 12.12
END DESCRIPTION:
XS GIS Cut Line= 4
      3540997.22     10484874.82      3540122.23     10484215.11
      3540087.51     10484159.56      3540080.57     10483888.68
#Sta/Elev= 30
  4158.0  378.02  4200.3  378.41  4296.8  377.17  4335.6  377.39  4371.0  376.38
  4385.5  377.38  4420.9  375.93  4627.8  375.63  4698.0  372.92  4749.9  369.70
  4832.0  367.86  4949.7  365.19  4996.7  361.82  4999.4  361.32  5002.7  361.82
  5012.7  362.40  5013.8  362.40  5020.5  363.18  5035.1  362.91  5064.2  364.82
  5085.0  365.25  5128.7  364.79  5178.9  365.41  5214.1  365.53  5324.1  368.81
  5342.5  369.52  5417.3  372.32  5497.3  377.23  5537.3  381.25  5590.3  383.40
#Mann=11,-1,0
  4158.0    0.05       0  4296.8     0.1       0  4698.0    0.05       0
  4832.0    0.16       0  4996.7    0.07       0  5002.7    0.16       0
  5012.7    0.05       0  5013.8    0.16       0  5178.9    0.05       0
  5324.1    0.16       0  5342.5     0.1       0
Bank Sta=4996.7,5002.7
Exp/Cntr=0.3,0.1

Type RM Length L Ch R = 1,9081,55,55,55
BEGIN DESCRIPTION:
STEEPLETON BRANCH 11.0
END DESCRIPTION:
XS GIS Cut Line= 4
      3540935.59     10484493.32      3540521.10     10484393.50
      3540150.01     10484124.40      3540123.97     10483892.18
#Sta/Elev= 30
  4391.1  377.02  4425.5  376.28  4513.6  376.06  4550.9  373.70  4690.9  371.60
  4718.6  370.25  4760.6  370.35  4802.5  368.90  4890.3  368.72  4961.8  367.50
  4968.0  367.27  4982.7  363.99  4989.1  360.83  4994.4  360.59  4997.1  360.09
  5000.4  360.59  5012.1  364.98  5026.2  365.68  5078.3  364.70  5162.1  365.41
  5230.9  367.44  5240.2  368.26  5248.3  368.23  5302.8  370.39  5359.0  374.61
  5387.9  376.54  5399.4  378.18  5419.5  379.62  5459.7  379.35  5509.5  382.43
#Mann=9,-1,0
  4391.1    0.05       0  4513.6     0.1       0  4690.9    0.05       0
  4994.4    0.04       0  5000.4    0.05       0  5078.3    0.16       0
  5230.9    0.05       0  5248.3    0.16       0  5359.0     0.1       0
Bank Sta=4994.4,5000.4
Exp/Cntr=0.3,0.1

Type RM Length L Ch R = 1,9026,750,750,750
BEGIN DESCRIPTION:
STEEPLETON BRANCH 10.0
END DESCRIPTION:
XS GIS Cut Line= 4
      3540946.41     10484434.72      3540555.83     10484345.75
      3540197.75     10484104.87      3540167.37     10483887.83
#Sta/Elev= 30
  4398.2  376.15  4443.6  375.05  4474.4  375.39  4545.2  374.32  4610.2  372.81
  4656.8  371.15  4679.5  371.87  4780.2  369.38  4854.2  367.99  4893.4  368.20
  4973.7  366.27  4984.1  365.18  4995.2  361.92  4998.0  361.42  5001.2  361.92
  5009.4  362.74  5013.2  362.84  5020.2  364.95  5028.2  365.29  5097.6  364.35
  5201.0  367.47  5263.9  371.61  5308.2  373.62  5334.6  376.10  5344.7  376.31
  5354.8  377.75  5374.6  378.33  5394.2  380.39  5425.5  382.21  5449.5  381.68
#Mann=11,-1,0
  4398.2    0.05       0  4545.2     0.1       0  4610.2    0.05       0
  4780.2    0.16       0  4893.4    0.05       0  4973.7    0.12       0
  4995.2    0.07       0  5001.2    0.12       0  5009.4    0.05       0
  5097.6    0.16       0  5394.2     0.1       0
Bank Sta=4995.2,5001.2
Exp/Cntr=0.3,0.1

Type RM Length L Ch R = 1,8276,1088,1088,1088
BEGIN DESCRIPTION:
STEEPLETON BRANCH 9.0
END DESCRIPTION:
XS GIS Cut Line= 4
      3541260.44     10484365.60      3540762.95     10483824.58
      3540457.39     10483685.69      3540026.93     10483453.11
#Sta/Elev= 30
  4101.1  377.21  4350.7  375.05  4374.2  373.51  4496.1  368.66  4509.1  368.06
  4562.8  365.23  4662.1  363.69  4683.0  362.12  4694.1  363.00  4718.2  363.00
  4725.6  361.40  4760.7  363.58  4810.6  361.84  4848.0  363.46  4966.9  363.76
  4980.7  363.29  4995.3  360.33  4998.0  359.83  5001.3  360.33  5021.3  364.20
  5034.7  364.98  5056.7  369.52  5124.3  370.31  5227.3  374.03  5232.8  374.30
  5268.7  375.15  5302.8  377.57  5325.5  375.75  5426.8  378.53  5661.0  382.13
#Mann=12,-1,0
  4101.1    0.05       0  4374.2    0.16       0  4496.1    0.05       0
  4509.1    0.16       0  4694.1    0.12       0  4966.9    0.05       0
  4995.3    0.04       0  5001.3    0.05       0  5124.3     0.1       0
  5227.3    0.16       0  5232.8     0.1       0  5426.8    0.05       0
Bank Sta=4995.3,5001.3
Exp/Cntr=0.3,0.1

Type RM Length L Ch R = 1,7188,802,802,802
BEGIN DESCRIPTION:
STEEPLETON BRANCH 8.0
END DESCRIPTION:
XS GIS Cut Line= 3
      3541835.88     10484282.93      3541273.36     10483215.21
      3540434.82     10482324.58
#Sta/Elev= 30
  4076.2  375.15  4245.8  373.10  4272.8  372.67  4360.2  371.01  4382.8  373.02
  4414.0  371.23  4573.1  369.87  4718.9  366.30  4804.9  365.70  4835.0  363.00
  4912.9  363.00  5174.0  363.00  5181.4  361.95  5184.2  361.45  5187.4  361.95
  5220.4  364.18  5369.0  371.93  5507.4  375.98  5569.4  376.37  5611.9  374.72
  5866.4  379.29  6036.3  379.97  6184.8  378.86  6227.3  377.74  6241.4  376.07
  6269.8  378.18  6354.7  378.73  6375.8  380.24  6453.9  379.67  6506.3  381.34
#Mann=11,-1,0
  4076.2    0.05       0  4245.8    0.16       0  4272.8    0.05       0
  4573.1    0.16       0  4718.9    0.07       0  4912.9    0.05       0
  5181.4   0.033       0  5187.4    0.05       0  5220.4    0.16       0
  5369.0    0.05       0  5507.4    0.16       0
Bank Sta=5181.4,5187.4
Exp/Cntr=0.3,0.1

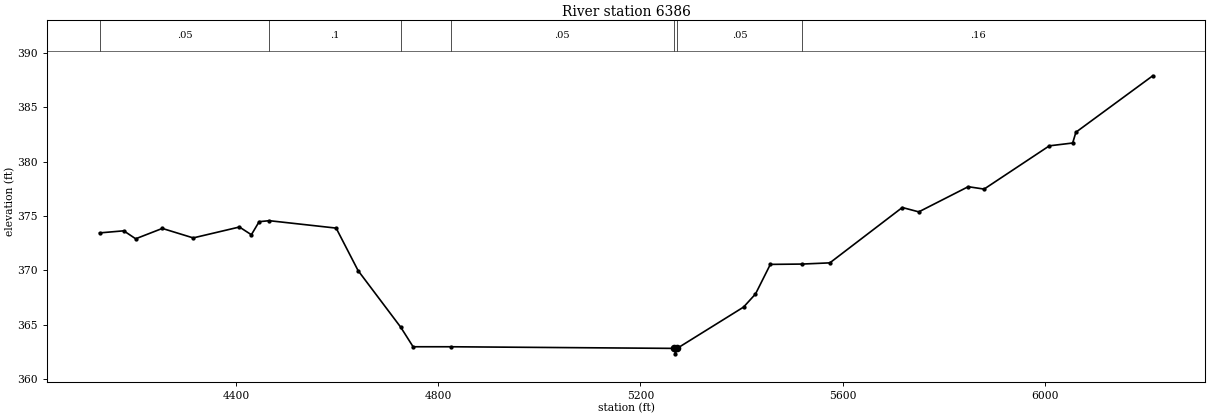
Type RM Length L Ch R = 1,6386,0,0,0
BEGIN DESCRIPTION:
STEEPLETON BRANCH 1.0
END DESCRIPTION:
XS GIS Cut Line= 2
      3542445.24     10483881.88      3541627.85     10481965.95
#Sta/Elev= 30
  4130.4  373.45  4178.1  373.64  4201.7  372.91  4254.4  373.86  4315.5  372.99
  4406.9  373.99  4430.5  373.28  4445.9  374.48  4466.0  374.57  4598.2  373.89
  4641.6  369.99  4726.0  364.79  4750.4  363.00  4824.5  363.00  5266.6  362.85
  5269.3  362.35  5272.6  362.85  5404.0  366.64  5427.6  367.84  5457.0  370.56
  5520.0  370.59  5574.7  370.70  5718.0  375.78  5750.6  375.38  5848.4  377.69
  5879.8  377.47  6008.8  381.44  6055.0  381.70  6061.4  382.69  6213.4  387.87
#Mann=7,-1,0
  4130.4    0.05       0  4466.0     0.1       0  4726.0    0.07       0
  4824.5    0.05       0  5266.6   0.033       0  5272.6    0.05       0
  5520.0    0.16       0
Bank Sta=5266.6,5272.6
Exp/Cntr=0.3,0.1

Chan Stop Cuts=-1