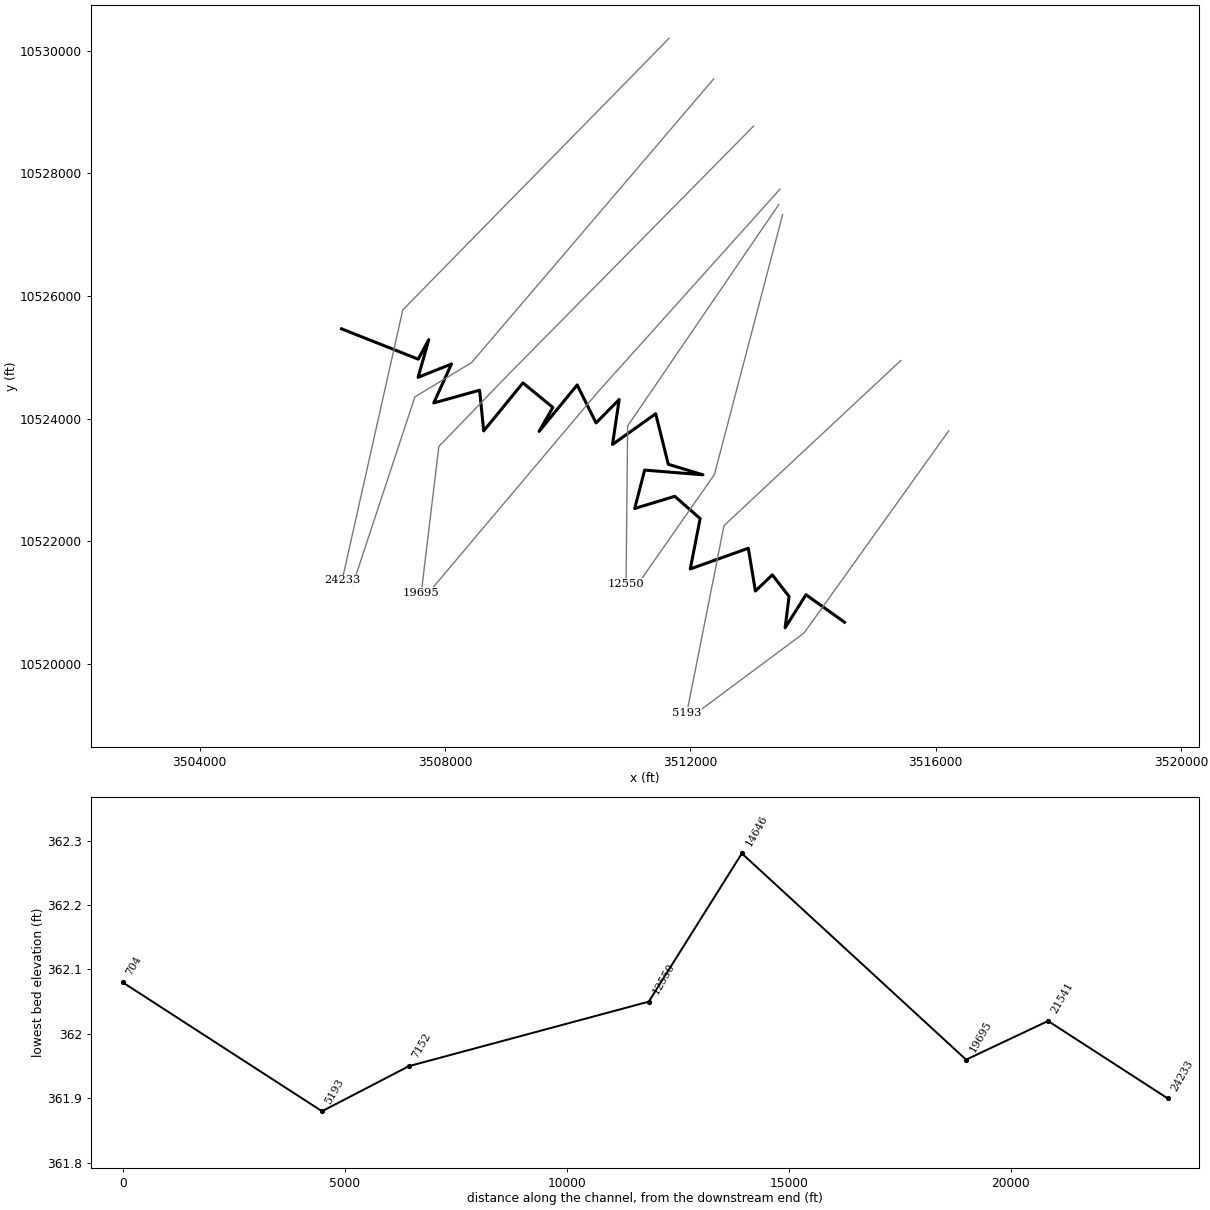
--- UNT0001 IN SAND CR.prj (project) ---

Proj Title=UNT0001 IN SAND CR Base Level Engineering
Current Plan=p01
Default Exp/Contr=0.3,0.1
English Units
Geom File=g01
Flow File=f01
Plan File=p01
BEGIN DESCRIPTION:
UNT0001 IN SAND CR
END DESCRIPTION:

--- UNT0001 IN SAND CR.p01 (plan) ---

Plan Title=Multiple Run
Short Identifier=Multiple
Geom File=g01
Flow File=f01
Subcritical Flow
K Sum by GR= 0
Std Step Tol= 0.01
Critical Tol= 0.01
Num of Std Step Trials= 20
Max Error Tol= 0.3
Flow Tol Ratio= 0.001
Split Flow NTrial= 30
Split Flow Tol= 0.02
Split Flow Ratio= 0.02
Log Output Level= 0
Friction Slope Method= 1
Unsteady Friction Slope Method= 2
Unsteady Bridges Friction Slope Method= 1
Parabolic Critical Depth
Global Vel Dist=  1 , 1 , 1
Global Log Level= 0
CheckData=True
Encroach Param= -1, 0, 0, 0
BEGIN DESCRIPTION:
Multiple Run
END DESCRIPTION:

--- UNT0001 IN SAND CR.f01 (steady flow) ---

Flow Title=Multiple
Number of Profiles=7
Profile Names=10-year,25-year,50-year,1pct_min,100-year,1pct_plu,500-year
River Rch & RM= UNT0001 IN SAND ,Reach-1,24233
   12753   18751   24021   22258   30101   40708   47123
River Rch & RM= UNT0001 IN SAND ,Reach-1,7152
   12936   19027   24381   22596   30559   41327   47862
Boundary for River Rch & Prof#=UNT0001 IN SAND ,Reach-1,1
Up Type=0
Dn Type=3
Dn Slope=0.005
Boundary for River Rch & Prof#=UNT0001 IN SAND ,Reach-1,2
Up Type=0
Dn Type=3
Dn Slope=0.005
Boundary for River Rch & Prof#=UNT0001 IN SAND ,Reach-1,3
Up Type=0
Dn Type=3
Dn Slope=0.005
Boundary for River Rch & Prof#=UNT0001 IN SAND ,Reach-1,4
Up Type=0
Dn Type=3
Dn Slope=0.005
Boundary for River Rch & Prof#=UNT0001 IN SAND ,Reach-1,5
Up Type=0
Dn Type=3
Dn Slope=0.005
Boundary for River Rch & Prof#=UNT0001 IN SAND ,Reach-1,6
Up Type=0
Dn Type=3
Dn Slope=0.005
Boundary for River Rch & Prof#=UNT0001 IN SAND ,Reach-1,7
Up Type=0
Dn Type=3
Dn Slope=0.005

--- UNT0001 IN SAND CR.g01 (geometry) ---

Geom Title=Existing Conditions

River Reach=UNT0001 IN SAND ,Reach-1
Reach XY= 30
      3506314.10     10525465.52      3507564.10     10524970.73
      3507736.85     10525288.44      3507562.37     10524674.72
      3508106.64     10524891.74      3507817.58     10524257.19
      3508564.97     10524464.65      3508631.81     10523801.46
      3509271.57     10524583.58      3509758.55     10524184.27
      3509534.59     10523792.78      3510155.25     10524550.59
      3510463.41     10523931.67      3510840.15     10524312.74
      3510731.64     10523580.97      3511435.63     10524080.80
      3511640.32     10523257.36      3512205.86     10523086.01
      3511255.34     10523162.40      3511093.01     10522536.53
      3511746.66     10522735.31      3512159.85     10522372.47
      3511998.94     10521551.03      3512945.12     10521888.70
      3513060.57     10521190.78      3513336.62     10521454.67
      3513609.19     10521103.11      3513544.95     10520590.96
      3513885.23     10521130.89      3514513.13     10520683.40

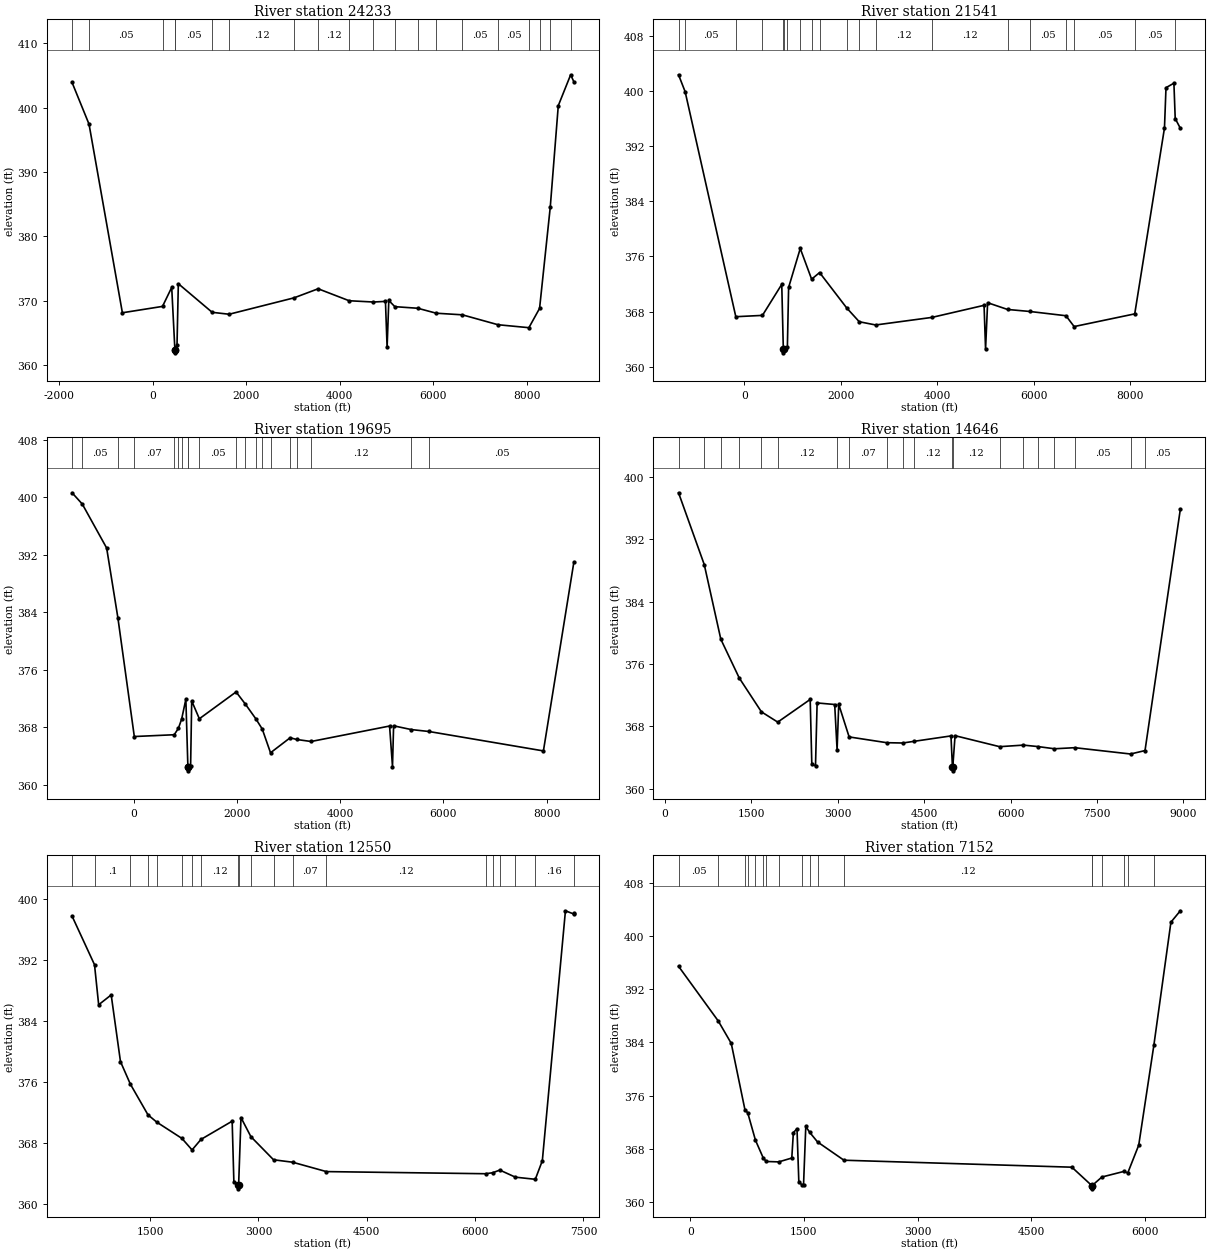
Type RM Length L Ch R = 1,24233,2692,2692,2692
BEGIN DESCRIPTION:
UNT0001 IN SAND CR 1.0
END DESCRIPTION:
XS GIS Cut Line= 3
      3511653.11     10530200.36      3507312.80     10525773.24
      3506323.57     10521365.08
#Sta/Elev= 30
 -1718.6  403.93 -1356.3  397.45  -643.9  368.13   213.1  369.12   409.6  372.07
   477.4  362.40   480.1  361.90   483.4  362.40   522.8  363.11   551.1  372.65
  1273.5  368.20  1635.9  367.90  3022.4  370.45  3537.2  371.86  4199.0  370.00
  4719.4  369.80  4974.8  369.90  5010.1  362.77  5046.5  370.04  5175.0  369.08
  5665.9  368.83  6059.8  368.06  6617.3  367.81  7378.7  366.27  8038.4  365.81
  8266.7  368.81  8494.6  384.53  8666.3  400.33  8930.6  405.13  8999.0  404.04
#Mann=20,-1,0
 -1718.6    0.05       0 -1356.3    0.05       0   213.1    0.05       0
   477.4    0.07       0   483.4    0.05       0  1273.5    0.16       0
  1635.9    0.12       0  3022.4    0.05       0  3537.2    0.12       0
  4199.0    0.05       0  4719.4    0.12       0  5175.0    0.05       0
  5665.9     0.1       0  6059.8     0.1       0  6617.3    0.05       0
  7378.7    0.05       0  8038.4    0.12       0  8266.7    0.05       0
  8494.6    0.08       0  8930.6    0.05       0
Bank Sta=477.4,483.4
Exp/Cntr=0.3,0.1

Type RM Length L Ch R = 1,21541,1846,1846,1846
BEGIN DESCRIPTION:
UNT0001 IN SAND CR 2.0
END DESCRIPTION:
XS GIS Cut Line= 4
      3512380.07     10529537.99      3508434.76     10524915.60
      3507510.28     10524355.71      3506494.65     10521282.77
#Sta/Elev= 30
 -1361.6  402.34 -1224.5  399.88  -175.1  367.26   376.5  367.45   776.6  371.95
   809.2  362.52   811.9  362.02   815.2  362.52   892.8  362.80   918.7  371.50
  1159.8  377.15  1395.3  372.70  1560.3  373.66  2123.1  368.52  2381.8  366.53
  2722.4  366.06  3888.6  367.16  4967.3  368.91  4998.3  362.55  5040.9  369.29
  5453.6  368.31  5912.3  368.02  6663.5  367.40  6833.2  365.83  8088.3  367.67
  8704.3  394.61  8736.0  400.47  8899.9  401.12  8926.9  395.99  9032.8  394.59
#Mann=20,-1,0
 -1361.6    0.05       0 -1224.5    0.05       0  -175.1    0.07       0
   376.5     0.1       0   809.2    0.07       0   815.2    0.16       0
   892.8    0.12       0  1159.8    0.05       0  1395.3    0.16       0
  1560.3     0.1       0  2123.1    0.12       0  2381.8    0.07       0
  2722.4    0.12       0  3888.6    0.12       0  5453.6     0.1       0
  5912.3    0.05       0  6663.5     0.1       0  6833.2    0.05       0
  8088.3    0.05       0  8926.9    0.05       0
Bank Sta=809.2,815.2
Exp/Cntr=0.3,0.1

Type RM Length L Ch R = 1,19695,5049,5049,5049
BEGIN DESCRIPTION:
UNT0001 IN SAND CR 3.0
END DESCRIPTION:
XS GIS Cut Line= 4
      3513031.11     10528769.76      3509072.78     10524759.35
      3507900.91     10523548.42      3507614.52     10521166.17
#Sta/Elev= 30
 -1191.5  400.62  -993.4  399.05  -521.7  392.94  -304.5  383.26    14.1  366.73
   787.3  366.98   867.8  367.87   930.8  369.15  1012.6  371.91  1052.1  362.46
  1054.8  361.96  1058.1  362.46  1104.6  362.66  1125.8  371.68  1273.8  369.20
  1985.5  372.93  2163.8  371.25  2365.4  369.22  2491.7  367.78  2652.3  364.47
  3033.0  366.56  3158.0  366.32  3438.9  366.04  4958.4  368.19  5015.0  362.56
  5036.4  368.22  5377.3  367.70  5720.2  367.43  7938.2  364.73  8527.9  390.97
#Mann=20,-1,0
 -1191.5     0.1       0  -993.4    0.05       0  -304.5     0.1       0
    14.1    0.07       0   787.3    0.16       0   867.8     0.1       0
   930.8    0.16       0  1052.1    0.07       0  1058.1    0.07       0
  1273.8    0.05       0  1985.5    0.12       0  2163.8    0.05       0
  2365.4    0.07       0  2491.7    0.12       0  2652.3    0.12       0
  3033.0    0.07       0  3158.0    0.07       0  3438.9    0.12       0
  5377.3     0.1       0  5720.2    0.05       0
Bank Sta=1052.1,1058.1
Exp/Cntr=0.3,0.1

Type RM Length L Ch R = 1,14646,2096,2096,2096
BEGIN DESCRIPTION:
UNT0001 IN SAND CR 4.0
END DESCRIPTION:
XS GIS Cut Line= 3
      3513460.79     10527741.11      3510487.71     10524429.49
      3507740.31     10521172.11
#Sta/Elev= 30
   235.4  397.95   682.0  388.74   969.7  379.16  1289.5  374.19  1674.2  369.85
  1957.7  368.53  2521.1  371.44  2549.5  363.10  2613.3  362.93  2641.4  370.99
  2946.4  370.79  2988.1  364.98  3016.7  370.81  3197.2  366.63  3850.2  365.89
  4127.3  365.85  4318.6  366.06  4965.1  366.76  4990.7  362.78  4993.4  362.28
  4996.7  362.78  5036.2  366.79  5810.0  365.38  6223.6  365.58  6479.4  365.39
  6762.2  365.11  7114.4  365.25  8082.6  364.44  8334.1  364.88  8947.1  395.83
#Mann=20,-1,0
   235.4    0.05       0   682.0    0.05       0   969.7    0.16       0
  1289.5    0.05       0  1674.2    0.16       0  1957.7    0.12       0
  2988.1    0.05       0  3197.2    0.07       0  3850.2    0.12       0
  4127.3    0.07       0  4318.6    0.12       0  4990.7    0.07       0
  4996.7    0.12       0  5810.0    0.12       0  6223.6     0.1       0
  6479.4    0.05       0  6762.2    0.12       0  7114.4    0.05       0
  8082.6    0.12       0  8334.1    0.05       0
Bank Sta=4990.7,4996.7
Exp/Cntr=0.3,0.1

Type RM Length L Ch R = 1,12550,5398,5398,5398
BEGIN DESCRIPTION:
UNT0001 IN SAND CR 5.0
END DESCRIPTION:
XS GIS Cut Line= 3
      3513443.44     10527492.72      3510978.16     10523881.61
      3510952.14     10521305.02
#Sta/Elev= 30
   418.6  397.80   729.4  391.43   786.9  386.18   960.3  387.47  1089.0  378.73
  1225.7  375.78  1469.9  371.75  1592.0  370.79  1940.0  368.66  2080.4  367.15
  2203.9  368.53  2635.7  370.92  2659.2  363.01  2719.1  362.55  2721.9  362.05
  2725.1  362.55  2758.0  371.39  2895.0  368.89  3208.6  365.86  3472.8  365.54
  3940.6  364.31  6145.4  364.03  6243.6  364.16  6341.7  364.51  6557.9  363.58
  6833.8  363.30  6931.1  365.74  7251.1  398.50  7363.0  398.09  7367.7  398.17
#Mann=20,-1,0
   418.6    0.05       0   729.4     0.1       0  1225.7    0.05       0
  1469.9     0.1       0  1592.0     0.1       0  1940.0    0.12       0
  2080.4    0.05       0  2203.9    0.12       0  2719.1    0.07       0
  2725.1    0.12       0  2895.0    0.05       0  3208.6    0.12       0
  3472.8    0.07       0  3940.6    0.12       0  6145.4     0.1       0
  6243.6    0.07       0  6341.7     0.1       0  6557.9    0.07       0
  6833.8    0.16       0  7363.0     0.1       0
Bank Sta=2719.1,2725.1
Exp/Cntr=0.3,0.1

Type RM Length L Ch R = 1,7152,1959,1959,1959
BEGIN DESCRIPTION:
UNT0001 IN SAND CR 6.0
END DESCRIPTION:
XS GIS Cut Line= 3
      3513504.20     10527327.77      3512393.09     10523091.68
      3511108.40     10521251.44
#Sta/Elev= 30
  -155.0  395.47   370.0  387.22   540.9  383.86   722.9  373.79   757.7  373.43
   860.2  369.28   965.1  366.55  1004.0  366.07  1167.7  366.01  1340.0  366.59
  1360.7  370.41  1408.7  371.01  1433.1  362.96  1475.2  362.55  1495.1  362.57
  1524.7  371.34  1577.6  370.44  1680.1  369.01  2028.4  366.26  5037.0  365.21
  5299.1  362.45  5301.9  361.95  5305.1  362.45  5433.3  363.73  5722.7  364.57
  5775.1  364.35  5919.6  368.53  6119.4  383.58  6344.5  402.11  6468.7  403.83
#Mann=18,-1,0
  -155.0    0.05       0   370.0    0.16       0   722.9    0.05       0
   757.7     0.1       0   860.2    0.12       0   965.1    0.05       0
  1004.0    0.12       0  1167.7    0.07       0  1475.2    0.05       0
  1577.6    0.07       0  1680.1    0.05       0  2028.4    0.12       0
  5299.1    0.07       0  5305.1    0.12       0  5433.3    0.07       0
  5722.7    0.12       0  5775.1    0.16       0  6119.4    0.05       0
Bank Sta=5299.1,5305.1
Exp/Cntr=0.3,0.1

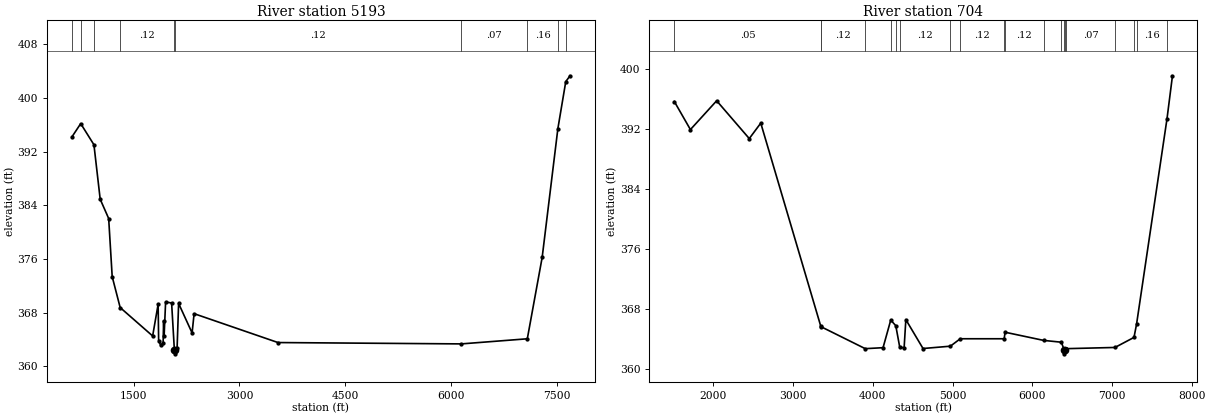
Type RM Length L Ch R = 1,5193,4489,4489,4489
BEGIN DESCRIPTION:
UNT0001 IN SAND CR 7.0
END DESCRIPTION:
XS GIS Cut Line= 3
      3515431.26     10524949.29      3512549.34     10522258.34
      3511942.10     10519204.76
#Sta/Elev= 30
   625.8  394.17   750.8  396.16   938.2  393.01  1026.8  384.90  1146.9  382.03
  1196.8  373.37  1309.8  368.77  1769.8  364.54  1847.5  369.26  1854.8  363.85
  1883.2  363.17  1918.3  363.46  1925.2  366.82  1932.5  364.59  1953.5  369.60
  2038.5  369.45  2078.0  362.38  2080.8  361.88  2084.0  362.38  2116.2  362.73
  2137.7  369.38  2328.7  364.99  2357.0  367.86  3545.6  363.56  6142.4  363.36
  7077.1  364.12  7287.6  376.24  7510.0  395.41  7621.8  402.41  7682.1  403.28
#Mann=10,-1,0
   625.8    0.05       0   750.8     0.1       0   938.2    0.05       0
  1309.8    0.12       0  2078.0    0.07       0  2084.0    0.12       0
  6142.4    0.07       0  7077.1    0.16       0  7510.0    0.05       0
  7621.8    0.16       0
Bank Sta=2078,2084
Exp/Cntr=0.3,0.1

Type RM Length L Ch R = 1,704,0,0,0
BEGIN DESCRIPTION:
UNT0001 IN SAND CR 8.0
END DESCRIPTION:
XS GIS Cut Line= 3
      3516212.54     10523803.48      3513854.32     10520507.76
      3512092.19     10519197.01
#Sta/Elev= 30
  1510.5  395.71  1712.3  391.97  2041.5  395.81  2450.6  390.77  2594.8  392.83
  3348.1  365.74  3355.5  365.67  3905.5  362.77  4128.8  362.90  4225.3  366.58
  4288.6  365.83  4338.0  362.97  4393.0  362.88  4414.7  366.64  4630.1  362.79
  4973.2  363.10  5097.4  364.09  5648.0  364.09  5659.8  364.96  6143.9  363.87
  6365.3  363.63  6401.9  362.58  6404.6  362.08  6407.9  362.58  6426.8  362.77
  7038.0  362.93  7276.7  364.27  7308.9  366.04  7690.6  393.40  7759.2  399.14
#Mann=20,-1,0
  1510.5    0.05       0  3348.1     0.1       0  3355.5    0.12       0
  3905.5    0.07       0  4225.3    0.12       0  4288.6    0.07       0
  4338.0    0.12       0  4973.2    0.07       0  5097.4    0.12       0
  5648.0    0.07       0  5659.8    0.12       0  6143.9    0.07       0
  6365.3    0.12       0  6401.9    0.07       0  6407.9    0.12       0
  6426.8    0.07       0  7038.0    0.05       0  7276.7    0.07       0
  7308.9    0.16       0  7690.6    0.05       0
Bank Sta=6401.9,6407.9
Exp/Cntr=0.3,0.1

Chan Stop Cuts=-1