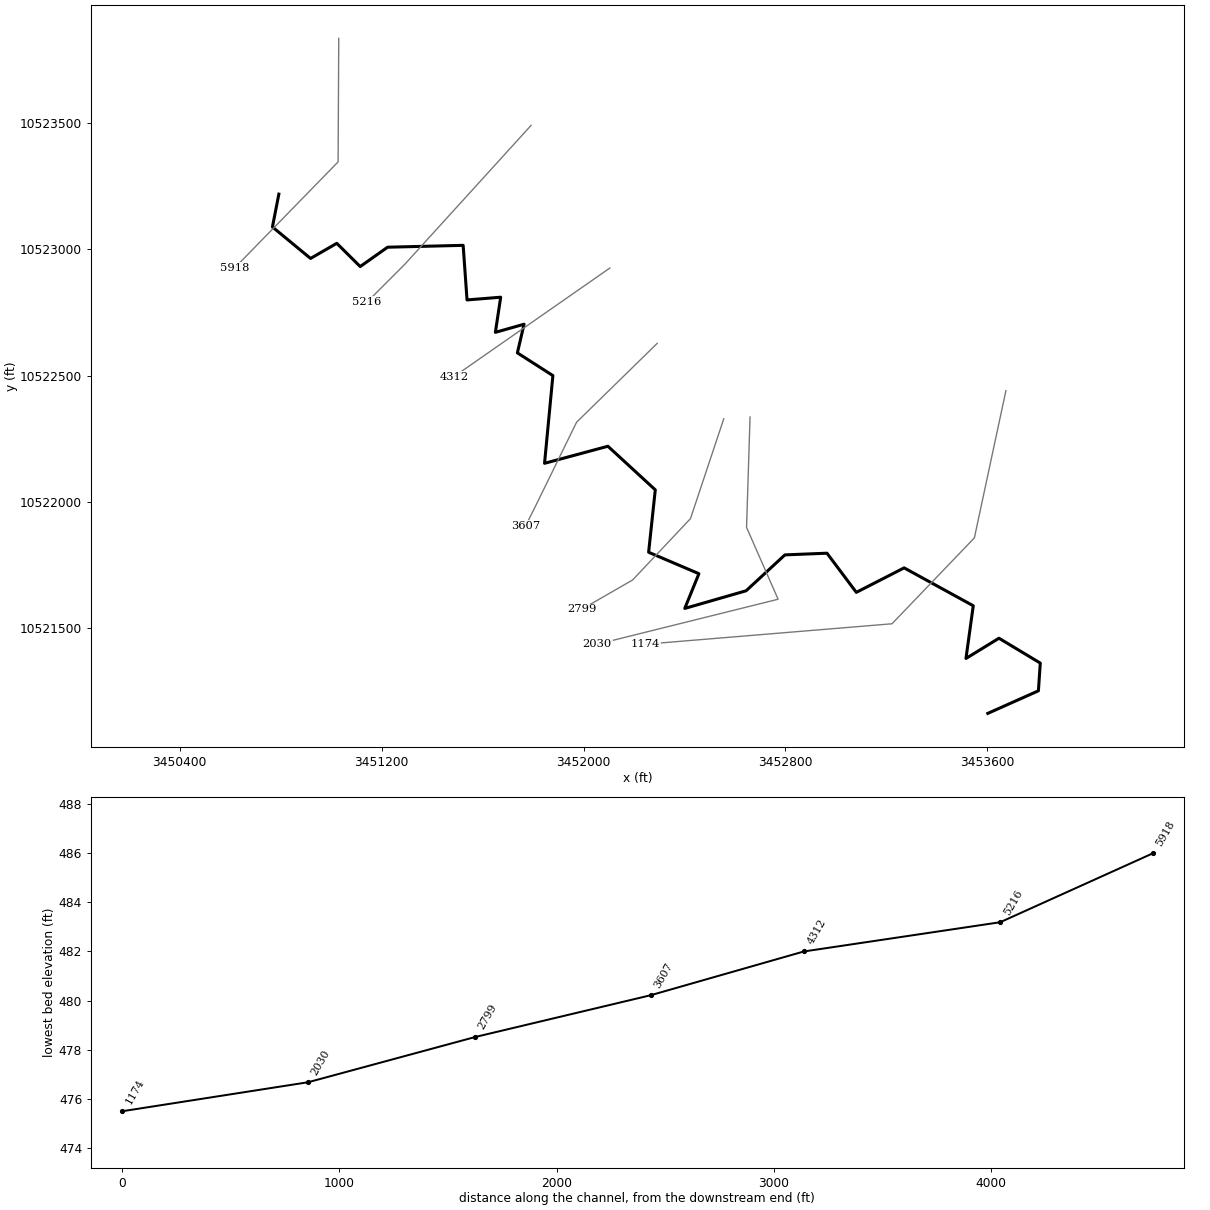
--- UNT0088 IN SAND CR.prj (project) ---

Proj Title=UNT0088 IN SAND CR Base Level Engineering
Current Plan=p01
Default Exp/Contr=0.3,0.1
English Units
Geom File=g01
Flow File=f01
Plan File=p01
Y Axis Title=Elevation
X Axis Title(PF)=Main Channel Distance
X Axis Title(XS)=Station
BEGIN DESCRIPTION:
UNT0088 IN SAND CR
END DESCRIPTION:
DSS Export Rating Curves= 0
DSS Export Rating Curve Sorted= 0
DSS Export Volume Flow Curves= 0
DXF OffsetX= 0
DXF OffsetY= 0
DXF ScaleX= 1
DXF ScaleY= 10

--- UNT0088 IN SAND CR.p01 (plan) ---

Plan Title=Multiple Run
Short Identifier=Multiple
Geom File=g01
Flow File=f01
Subcritical Flow
K Sum by GR= 0
Std Step Tol= 0.01
Critical Tol= 0.01
Num of Std Step Trials= 20
Max Error Tol= 0.3
Flow Tol Ratio= 0.001
Split Flow NTrial= 30
Split Flow Tol= 0.02
Split Flow Ratio= 0.02
Log Output Level= 0
Friction Slope Method= 1
Unsteady Friction Slope Method= 2
Unsteady Bridges Friction Slope Method= 1
Parabolic Critical Depth
Global Vel Dist=  1 , 1 , 1
Global Log Level= 0
CheckData=True
Encroach Param= -1, 0, 0, 0
BEGIN DESCRIPTION:
Multiple Run
END DESCRIPTION:

--- UNT0088 IN SAND CR.f01 (steady flow) ---

Flow Title=Multiple
Number of Profiles=7
Profile Names=10-year,25-year,50-year,1pct_min,100-year,1pct_plu,500-year
River Rch & RM= UNT0088 IN SAND ,Reach-1,5918
     746     997    1197    1049    1418    1918    1984
River Rch & RM= UNT0088 IN SAND ,Reach-1,4312
     807    1082    1301    1142    1544    2088    2167
Boundary for River Rch & Prof#=UNT0088 IN SAND ,Reach-1,1
Up Type=0
Dn Type=3
Dn Slope=0.005
Boundary for River Rch & Prof#=UNT0088 IN SAND ,Reach-1,2
Up Type=0
Dn Type=3
Dn Slope=0.005
Boundary for River Rch & Prof#=UNT0088 IN SAND ,Reach-1,3
Up Type=0
Dn Type=3
Dn Slope=0.005
Boundary for River Rch & Prof#=UNT0088 IN SAND ,Reach-1,4
Up Type=0
Dn Type=3
Dn Slope=0.005
Boundary for River Rch & Prof#=UNT0088 IN SAND ,Reach-1,5
Up Type=0
Dn Type=3
Dn Slope=0.005
Boundary for River Rch & Prof#=UNT0088 IN SAND ,Reach-1,6
Up Type=0
Dn Type=3
Dn Slope=0.005
Boundary for River Rch & Prof#=UNT0088 IN SAND ,Reach-1,7
Up Type=0
Dn Type=3
Dn Slope=0.005

--- UNT0088 IN SAND CR.g01 (geometry) ---

Geom Title=Existing Conditions
Program Version=4.10

River Reach=UNT0088 IN SAND ,Reach-1
Reach XY= 30
      3450792.65     10523219.39      3450767.26     10523089.19
      3450918.28     10522964.44      3451022.29     10523024.42
      3451115.04      10522932.3      3451223.58     10523008.96
      3451523.03     10523016.39       3451538.4     10522800.06
      3451671.72     10522810.79       3451650.7     10522671.56
      3451764.43     10522703.77      3451737.93     10522590.29
      3451878.63     10522500.17      3451845.53     10522152.57
      3452096.68      10522220.2      3452284.38     10522047.46
      3452258.01      10521800.1      3452457.31     10521715.14
      3452401.18     10521577.48      3452644.36      10521647.5
      3452798.06      10521789.7      3452964.74      10521796.4
      3453081.05     10521641.19      3453270.55     10521738.24
      3453544.46     10521588.12      3453515.59     10521379.22
      3453646.33     10521459.45      3453810.08      10521360.9
      3453802.64     10521251.06      3453602.11     10521161.64

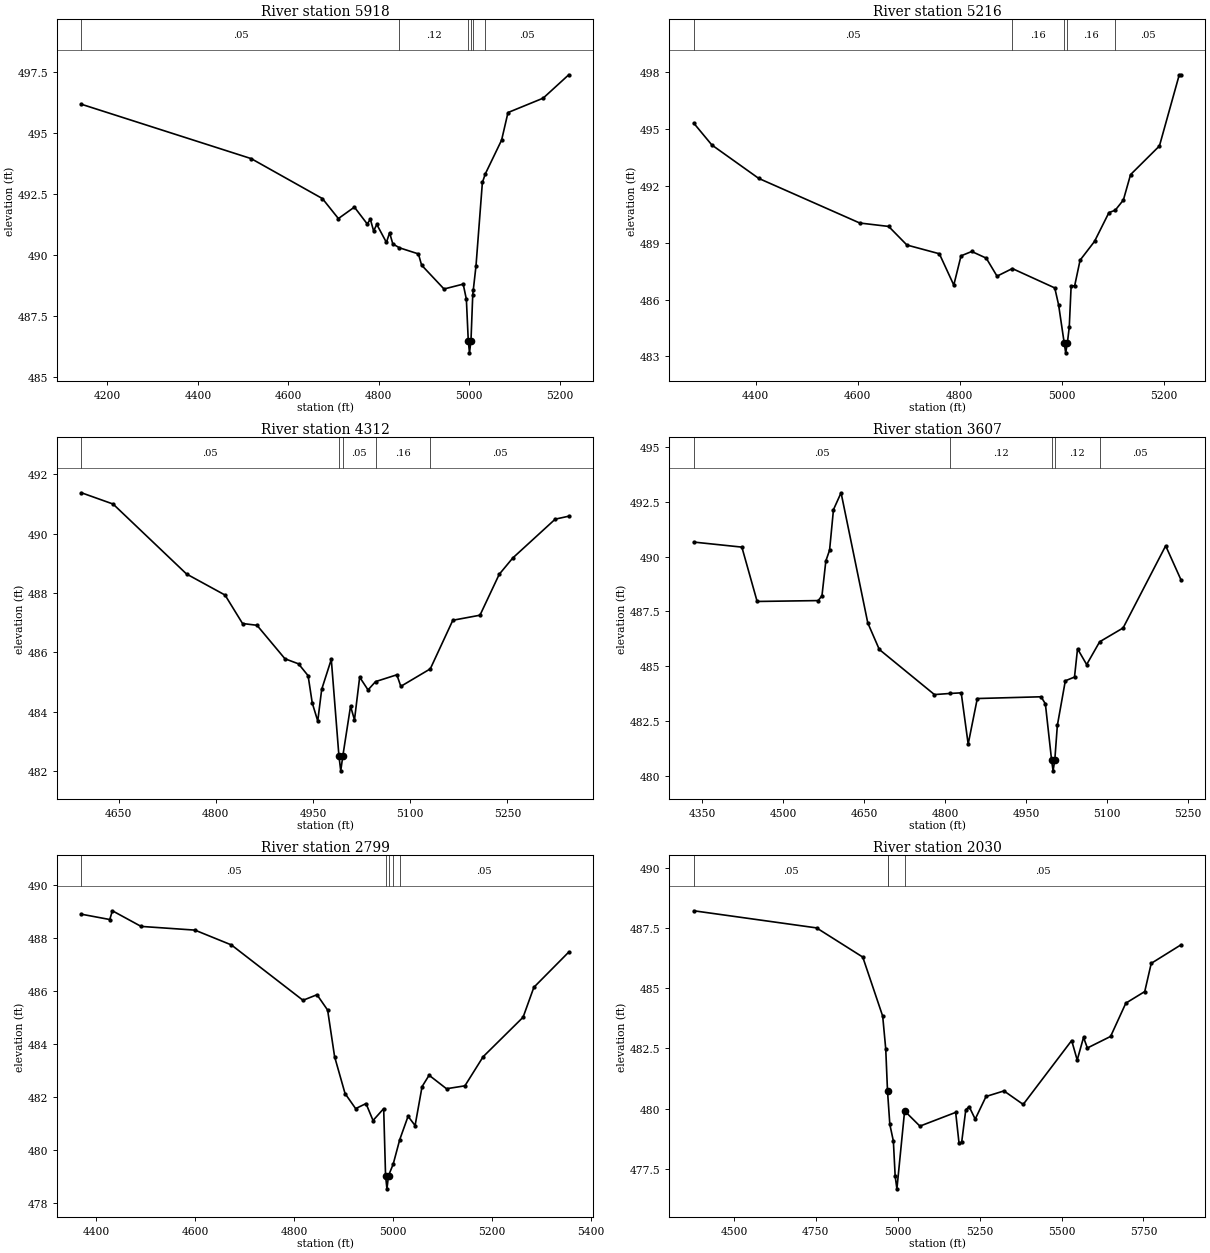
Type RM Length L Ch R = 1 ,5918    ,702,702,702
BEGIN DESCRIPTION:
UNT0088 IN SAND CR 1.1
END DESCRIPTION:
XS GIS Cut Line= 3
      3451030.04      10523836.7      3451027.44     10523347.08
      3450617.26     10522926.52
#Sta/Elev= 30
  4142.7  496.19  4517.8  493.96  4675.3  492.32  4710.6   491.5    4746  491.97
  4774.3  491.28  4781.3  491.47  4788.5  490.99  4795.5  491.26  4816.8  490.52
  4823.8  490.92  4830.9  490.46  4845.6   490.3  4887.5  490.05  4894.5  489.59
  4944.1  488.61  4986.5  488.81  4993.5  488.19  4997.7  486.49  5000.4  485.99
  5003.7  486.49  5007.6  488.37  5008.7  488.55  5014.8  489.56  5028.9  492.98
  5035.3  493.33  5071.4  494.72  5085.5  495.85  5163.2  496.44  5219.8   497.4
#Mann= 6 ,-1 , 0
  4142.7     .05       0  4845.6     .12       0  4997.7     .07       0
  5003.7     .12       0  5008.7     .16       0  5035.3     .05       0
Bank Sta=4997.7,5003.7
XS Rating Curve= 0 ,0
Exp/Cntr=0.3,0.1

Type RM Length L Ch R = 1 ,5216    ,904,904,904
BEGIN DESCRIPTION:
UNT0088 IN SAND CR 1.0
END DESCRIPTION:
XS GIS Cut Line= 3
       3451792.1     10523491.64      3451292.11     10522941.64
      3451142.13     10522791.67
#Sta/Elev= 30
  4278.9  495.29  4314.4  494.14  4406.3  492.38  4604.3  490.03    4661  489.85
  4696.8  488.87  4760.4  488.41  4788.7  486.76  4802.9   488.3  4823.9  488.53
  4852.3  488.18  4873.5  487.23  4903.5  487.63  4986.7  486.61  4994.2  485.72
  5005.3  483.69  5008.1  483.19  5011.3  483.69  5015.1  484.54  5018.8  486.72
  5025.7  486.72  5036.3  488.07  5064.6  489.06  5092.9  490.58  5105.1   490.7
  5121.2  491.24  5135.3  492.58  5191.9  494.09  5230.8  497.84  5234.3  497.84
#Mann= 5 ,-1 , 0
  4278.9     .05       0  4903.5     .16       0  5005.3     .07       0
  5011.3     .16       0  5105.1     .05       0
Bank Sta=5005.3,5011.3
XS Rating Curve= 0 ,0
Exp/Cntr=0.3,0.1

Type RM Length L Ch R = 1 ,4312    ,705,705,705
BEGIN DESCRIPTION:
ROCKY CREEK 55.3
END DESCRIPTION:
XS GIS Cut Line= 2
       3452104.4     10522926.44      3451487.28     10522496.53
#Sta/Elev= 30
  4592.6  491.38  4641.4     491  4754.8  488.64  4814.2  487.93  4841.2  486.97
  4863.5  486.91  4906.7  485.78  4927.6  485.61  4942.4  485.21  4948.8  484.29
  4957.3  483.68  4963.4  484.75  4978.2  485.76    4990   482.5  4992.8     482
    4996   482.5  5007.9  484.18    5014  483.72    5022  485.16  5034.9  484.73
  5046.5  485.01  5079.4  485.24  5085.5  484.85    5131  485.44  5165.8  487.08
  5207.7  487.25  5237.4  488.63  5258.3  489.18  5323.8  490.49  5344.7  490.59
#Mann= 5 ,-1 , 0
  4592.6     .05       0    4990    .035       0    4996     .05       0
  5046.5     .16       0    5131     .05       0
Bank Sta=4990,4996
XS Rating Curve= 0 ,0
Exp/Cntr=0.3,0.1

Type RM Length L Ch R = 1 ,3607    ,808,808,808
BEGIN DESCRIPTION:
ROCKY CREEK 53.2
END DESCRIPTION:
XS GIS Cut Line= 4
       3452291.9     10522627.82      3451972.46     10522315.32
      3451812.73     10521988.93      3451771.34     10521906.15
#Sta/Elev= 30
  4334.7  490.66  4423.8  490.43  4452.1  487.95  4565.2  487.99  4572.2  488.21
  4579.4   489.8  4586.3  490.29  4593.5  492.14  4607.6  492.91  4657.1  486.97
  4678.4  485.76  4780.6   483.7  4808.7  483.75  4830.2  483.78  4843.1  481.44
    4860  483.52  4978.1   483.6  4986.1  483.28  4997.6  480.72  5000.4  480.22
  5003.6  480.72  5008.3  482.29  5023.1  484.33  5040.1   484.5  5045.7  485.79
  5062.6  485.07  5086.7  486.11  5130.1  486.74    5209  490.49  5237.5  488.93
#Mann= 5 ,-1 , 0
  4334.7     .05       0  4808.7     .12       0  4997.6     .07       0
  5003.6     .12       0  5086.7     .05       0
Bank Sta=4997.6,5003.6
XS Rating Curve= 0 ,0
Exp/Cntr=0.3,0.1

Type RM Length L Ch R = 1 ,2799    ,769,769,769
BEGIN DESCRIPTION:
ROCKY CREEK 55.2
END DESCRIPTION:
XS GIS Cut Line= 4
      3452555.79      10522329.2      3452423.85     10521933.38
      3452194.68     10521690.32      3451992.14      10521573.7
#Sta/Elev= 30
  4369.8  488.89    4427  488.69  4432.3  489.02  4490.3  488.43  4599.1  488.29
  4672.9  487.73  4817.6  485.64  4845.9  485.85  4867.4  485.27  4881.5  483.51
  4902.6  482.12    4924  481.55    4945  481.74  4959.2   481.1  4980.7  481.55
  4984.5  479.02  4987.3  478.52  4990.5  479.02  4999.9  479.45  5013.2  480.38
    5030  481.26  5044.2  480.91  5058.3  482.38  5072.5  482.81  5107.7   482.3
  5144.9  482.41  5181.8  483.51  5262.5     485  5284.3  486.13  5354.8  487.46
#Mann= 5 ,-1 , 0
  4369.8     .05       0  4984.5     .07       0  4990.5     .05       0
  4999.9      .1       0  5013.2     .05       0
Bank Sta=4984.5,4990.5
XS Rating Curve= 0 ,0
Exp/Cntr=0.3,0.1

Type RM Length L Ch R = 1 ,2030    ,856,856,856
BEGIN DESCRIPTION:
ROCKY CREEK 53.1
END DESCRIPTION:
XS GIS Cut Line= 4
      3452659.96      10522336.2      3452646.07     10521898.66
      3452771.07     10521613.93      3452054.63     10521435.69
#Sta/Elev= 30
  4377.6  488.21  4752.3   487.5  4893.3  486.29  4954.1  483.84  4963.4  482.48
  4968.8  480.74  4975.9  479.35  4986.7  478.66  4992.2   477.2  4997.5  476.68
    5021  479.91  5067.7  479.28  5176.8  479.85  5187.1  478.57  5195.1  478.61
  5207.7  479.96    5218  480.09  5236.4  479.57  5269.5  480.51  5324.2  480.74
  5382.9  480.18  5530.8  482.83  5547.7  482.02    5567  482.96  5578.7  482.52
  5649.6     483  5696.1  484.38  5753.8  484.86  5773.6  486.03  5864.6   486.8
#Mann= 4 ,-1 , 0
  4377.6     .05       0  4968.8     .16       0  4968.8    .035       0
    5021     .05       0
Bank Sta=4968.8,5021
XS Rating Curve= 0 ,0
Exp/Cntr=0.3,0.1

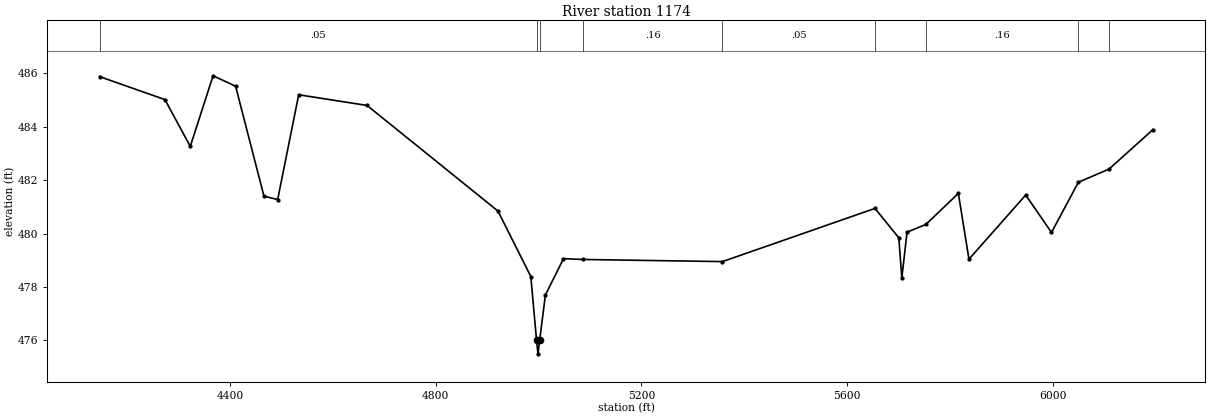
Type RM Length L Ch R = 1 ,1174    ,0,0,0
BEGIN DESCRIPTION:
ROCKY CREEK 52.1
END DESCRIPTION:
XS GIS Cut Line= 4
      3453673.85     10522440.35      3453548.85     10521856.99
      3453222.46     10521516.71      3452245.91     10521435.79
#Sta/Elev= 30
  4146.2  485.87  4273.3  485.01  4322.7  483.26    4367   485.9  4410.8  485.51
  4465.9   481.4  4492.6  481.27  4533.5  485.19  4666.5  484.79    4921  480.84
  4984.9  478.39    4996     476  4998.8   475.5    5002     476  5013.2   477.7
  5048.4  479.06  5085.8  479.03  5357.5  478.95  5654.1  480.94  5700.4  479.84
  5706.3  478.34  5716.4  480.05    5753  480.34  5816.2   481.5  5836.8  479.04
  5947.2  481.44  5997.3  480.04  6049.7  481.92  6109.2  482.41  6194.2  483.88
#Mann= 9 ,-1 , 0
  4146.2     .05       0    4996    .035       0    5002     .05       0
  5085.8     .16       0  5357.5     .05       0  5654.1      .1       0
    5753     .16       0  6049.7      .1       0  6109.2     .05       0
Bank Sta=4996,5002
XS Rating Curve= 0 ,0
Exp/Cntr=0.3,0.1

Chan Stop Cuts=-1
Use User Specified Reach Order=0
Composite Channel Slope=5