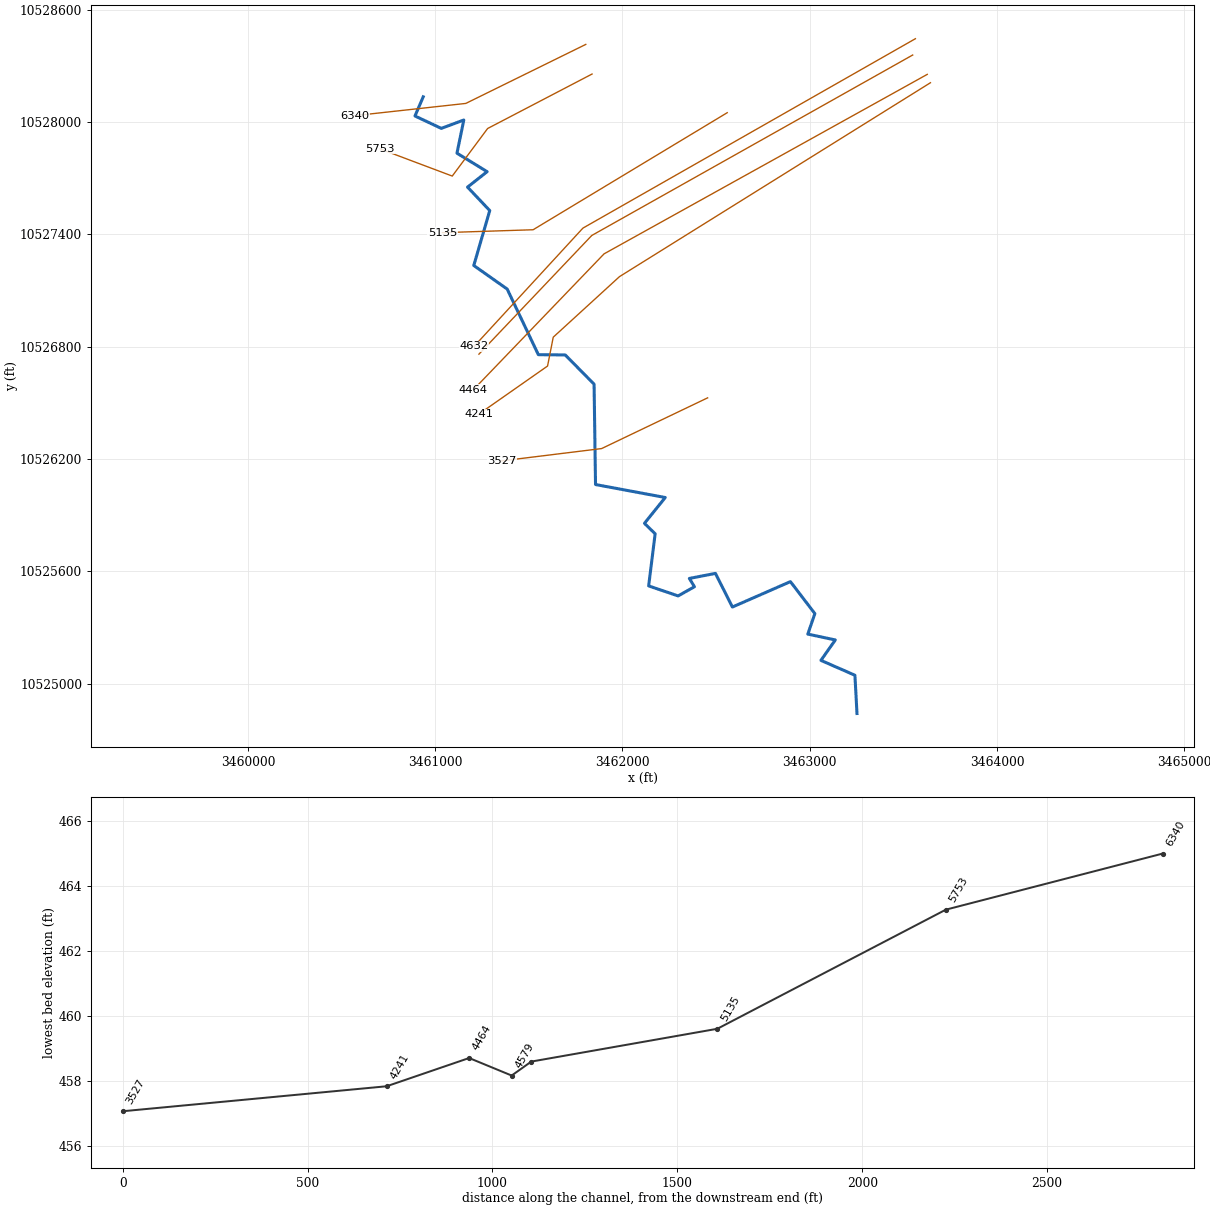
--- UNT0090 IN SAND CR.prj (project) ---

Proj Title=UNT0090 IN SAND CR Base Level Engineering
Current Plan=p01
Default Exp/Contr=0.3,0.1
English Units
Geom File=g01
Flow File=f01
Plan File=p01
BEGIN DESCRIPTION:
UNT0090 IN SAND CR
END DESCRIPTION:

--- UNT0090 IN SAND CR.p01 (plan) ---

Plan Title=Multiple Run
Short Identifier=Multiple
Geom File=g01
Flow File=f01
Subcritical Flow
K Sum by GR= 0
Std Step Tol= 0.01
Critical Tol= 0.01
Num of Std Step Trials= 20
Max Error Tol= 0.3
Flow Tol Ratio= 0.001
Split Flow NTrial= 30
Split Flow Tol= 0.02
Split Flow Ratio= 0.02
Log Output Level= 0
Friction Slope Method= 1
Unsteady Friction Slope Method= 2
Unsteady Bridges Friction Slope Method= 1
Parabolic Critical Depth
Global Vel Dist=  1 , 1 , 1
Global Log Level= 0
CheckData=True
Encroach Param= -1, 0, 0, 0
BEGIN DESCRIPTION:
Multiple Run
END DESCRIPTION:

--- UNT0090 IN SAND CR.f01 (steady flow) ---

Flow Title=Multiple
Number of Profiles=7
Profile Names=10-year,25-year,50-year,1pct_min,100-year,1pct_plu,500-year
River Rch & RM= UNT0090 IN SAND ,Reach-1,6340
    1141    1573    1931    1728    2337    3160    3414
River Rch & RM= UNT0090 IN SAND ,Reach-1,5135
    1490    2081    2574    2319    3137    4242    4647
Boundary for River Rch & Prof#=UNT0090 IN SAND ,Reach-1,1
Up Type=0
Dn Type=3
Dn Slope=0.005
Boundary for River Rch & Prof#=UNT0090 IN SAND ,Reach-1,2
Up Type=0
Dn Type=3
Dn Slope=0.005
Boundary for River Rch & Prof#=UNT0090 IN SAND ,Reach-1,3
Up Type=0
Dn Type=3
Dn Slope=0.005
Boundary for River Rch & Prof#=UNT0090 IN SAND ,Reach-1,4
Up Type=0
Dn Type=3
Dn Slope=0.005
Boundary for River Rch & Prof#=UNT0090 IN SAND ,Reach-1,5
Up Type=0
Dn Type=3
Dn Slope=0.005
Boundary for River Rch & Prof#=UNT0090 IN SAND ,Reach-1,6
Up Type=0
Dn Type=3
Dn Slope=0.005
Boundary for River Rch & Prof#=UNT0090 IN SAND ,Reach-1,7
Up Type=0
Dn Type=3
Dn Slope=0.005

--- UNT0090 IN SAND CR.g01 (geometry) ---

Geom Title=Existing Conditions

River Reach=UNT0090 IN SAND ,Reach-1
Reach XY= 30
      3460936.23     10528134.26      3460892.18     10528031.91
      3461032.67     10527965.75      3461152.88     10528010.41
      3461116.41     10527833.28      3461277.44     10527734.61
      3461172.84     10527652.14      3461291.49     10527526.86
      3461206.08     10527233.72      3461384.44     10527107.92
      3461550.85     10526757.49      3461694.49     10526756.12
      3461848.43     10526600.03      3461856.13     10526064.20
      3462228.41     10525994.90      3462117.41     10525856.99
      3462174.45     10525801.26      3462139.81     10525522.88
      3462297.14     10525469.58      3462384.38     10525518.53
      3462357.04     10525562.81      3462496.39     10525589.71
      3462586.99     10525410.20      3462896.69     10525545.84
      3463027.24     10525374.93      3462989.60     10525265.69
      3463136.36     10525234.35      3463059.65     10525125.34
      3463241.08     10525046.01      3463252.11     10524841.64

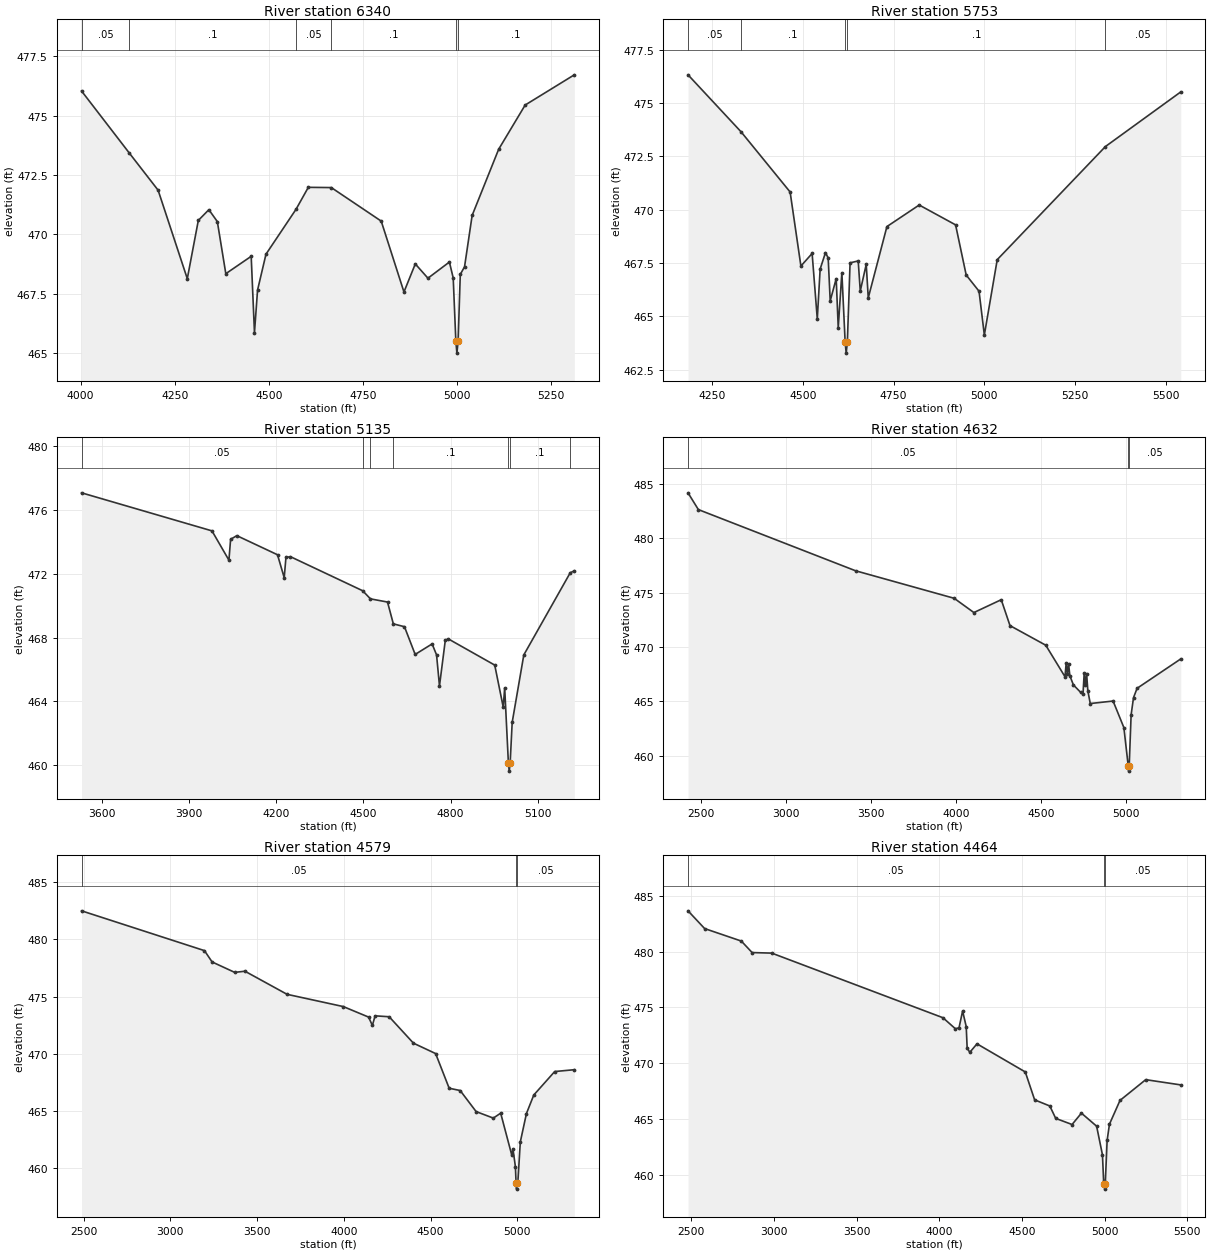
Type RM Length L Ch R = 1,6340,587,587,587
BEGIN DESCRIPTION:
UNT0090 IN SAND CR 1.1
END DESCRIPTION:
XS GIS Cut Line= 3
      3461804.12     10528414.09      3461163.53     10528099.00
      3460572.39     10528033.90
#Sta/Elev= 30
  4002.4  476.03  4128.8  473.43  4205.7  471.86  4283.2  468.14  4312.5  470.59
  4340.5  471.04  4363.0  470.54  4385.5  468.35  4452.9  469.08  4461.6  465.87
  4469.8  467.66  4492.2  469.17  4572.1  471.06  4604.6  471.98  4665.7  471.97
  4798.2  470.56  4858.6  467.58  4888.7  468.76  4922.3  468.16  4979.3  468.84
  4989.4  468.17  4996.4  465.51  4999.2  465.01  5002.4  465.51  5008.2  468.32
  5019.5  468.64  5039.7  470.80  5110.1  473.58  5180.5  475.44  5311.0  476.71
#Mann=6,-1,0
  4002.4    0.05       0  4128.8     0.1       0  4572.1    0.05       0
  4665.7     0.1       0  4996.4    0.07       0  5002.4     0.1       0
Bank Sta=4996.4,5002.4
Exp/Cntr=0.3,0.1

Type RM Length L Ch R = 1,5753,618,618,618
BEGIN DESCRIPTION:
UNT0090 IN SAND CR 1.2
END DESCRIPTION:
XS GIS Cut Line= 4
      3461837.76     10528256.01      3461280.03     10527965.03
      3461091.23     10527711.12      3460705.99     10527856.12
#Sta/Elev= 30
  4184.0  476.32  4330.1  473.65  4465.2  470.83  4494.9  467.36  4525.8  467.95
  4540.0  464.88  4547.9  467.22  4562.6  467.99  4570.0  467.74  4575.6  465.73
  4592.1  466.77  4597.7  464.48  4607.7  467.05  4616.8  463.78  4619.6  463.28
  4622.8  463.78  4630.3  467.51  4652.7  467.60  4658.4  466.19  4674.8  467.44
  4680.4  465.87  4731.8  469.21  4820.7  470.22  4920.9  469.29  4950.1  466.94
  4985.5  466.18  5000.1  464.13  5035.6  467.66  5333.6  472.96  5541.1  475.52
#Mann=5,-1,0
  4184.0    0.05       0  4330.1     0.1       0  4616.8    0.07       0
  4622.8     0.1       0  5333.6    0.05       0
Bank Sta=4616.8,4622.8
Exp/Cntr=0.3,0.1

Type RM Length L Ch R = 1,5135,503,503,503
BEGIN DESCRIPTION:
UNT0090 IN SAND CR 1.3
END DESCRIPTION:
XS GIS Cut Line= 3
      3462559.33     10528049.50      3461522.90     10527424.52
      3461038.53     10527408.90
#Sta/Elev= 30
  3530.9  477.09  3979.5  474.70  4037.8  472.86  4043.6  474.17  4065.0  474.40
  4204.9  473.20  4228.0  471.76  4233.9  473.03  4249.4  473.08  4497.8  470.94
  4524.6  470.43  4583.3  470.23  4603.3  468.86  4641.6  468.68  4678.4  466.94
  4736.7  467.60  4752.0  466.91  4762.0  464.96  4782.0  467.82  4792.0  467.92
  4952.1  466.27  4981.3  463.63  4986.3  464.84  4999.1  460.11  5001.9  459.61
  5005.1  460.11  5012.1  462.67  5052.1  466.91  5211.8  472.07  5225.8  472.19
#Mann=7,-1,0
  3530.9    0.05       0  4497.8     0.1       0  4524.6    0.05       0
  4603.3     0.1       0  4999.1    0.07       0  5005.1     0.1       0
  5211.8    0.05       0
Bank Sta=4999.1,5005.1
Exp/Cntr=0.3,0.1

Type RM Length L Ch R = 1,4632,53,53,53
BEGIN DESCRIPTION:
UNT0090 IN SAND CR 1.0
END DESCRIPTION:
XS GIS Cut Line= 3
      3463564.01     10528444.53      3461788.82     10527433.24
      3461208.30     10526802.45
#Sta/Elev= 30
  2422.0  484.17  2482.9  482.63  3407.9  477.01  3988.6  474.48  4104.5  473.17
  4265.6  474.35  4317.1  471.97  4527.5  470.17  4640.9  467.27  4647.7  468.53
  4655.1  467.49  4661.9  468.47  4669.3  467.37  4690.3  466.52  4732.8  465.84
  4747.0  465.72  4753.8  467.62  4761.2  466.48  4768.0  467.56  4775.3  465.98
  4789.5  464.81  4923.9  465.04  4987.4  462.60  5012.8  459.10  5015.5  458.60
  5018.8  459.10  5030.0  463.77  5044.1  465.35  5065.2  466.21  5322.3  468.91
#Mann=3,-1,0
  2422.0    0.05       0  5012.8    0.03       0  5018.8    0.05       0
Bank Sta=5012.8,5018.8
Exp/Cntr=0.3,0.1

Type RM Length L Ch R = 1,4579,115,115,115
BEGIN DESCRIPTION:
UNT0090 IN SAND CR 2.0
END DESCRIPTION:
XS GIS Cut Line= 3
      3463549.54     10528357.44      3461835.99     10527393.89
      3461233.57     10526760.23
#Sta/Elev= 30
  2488.6  482.50  3197.0  479.02  3241.1  478.03  3371.2  477.12  3430.4  477.22
  3673.3  475.20  3997.2  474.13  4143.1  473.21  4164.8  472.48  4180.7  473.32
  4261.7  473.24  4401.6  470.93  4529.5  470.02  4607.5  466.99  4671.0  466.79
  4762.8  464.95  4861.9  464.38  4904.4  464.81  4968.1  461.16  4975.2  461.68
  4989.3  460.13  4993.2  458.67  4996.0  458.17  4999.2  458.67  5003.5  458.81
  5017.6  462.30  5052.9  464.78  5095.3  466.40  5215.8  468.45  5328.8  468.61
#Mann=3,-1,0
  2488.6    0.05       0  4993.2    0.03       0  4999.2    0.05       0
Bank Sta=4993.2,4999.2
Exp/Cntr=0.3,0.1

Type RM Length L Ch R = 1,4464,223,223,223
BEGIN DESCRIPTION:
UNT0090 IN SAND CR 3.0
END DESCRIPTION:
XS GIS Cut Line= 3
      3463627.33     10528254.11      3461901.67     10527295.80
      3461203.78     10526570.13
#Sta/Elev= 30
  2480.7  483.65  2581.2  482.06  2803.1  480.94  2868.4  479.91  2987.3  479.86
  4022.7  474.07  4098.2  473.08  4120.0  473.17  4141.7  474.67  4163.5  473.28
  4169.2  471.35  4185.2  470.97  4228.7  471.73  4520.8  469.21  4577.4  466.71
  4669.3  466.16  4704.8  465.05  4803.8  464.50  4860.4  465.52  4952.3  464.35
  4987.6  461.79  4994.7  459.42  4998.7  459.21  5001.4  458.71  5004.7  459.21
  5015.8  463.07  5030.0  464.53  5093.8  466.66  5249.4  468.52  5461.4  468.05
#Mann=3,-1,0
  2480.7    0.05       0  4998.7    0.04       0  5004.7    0.05       0
Bank Sta=4998.7,5004.7
Exp/Cntr=0.3,0.1

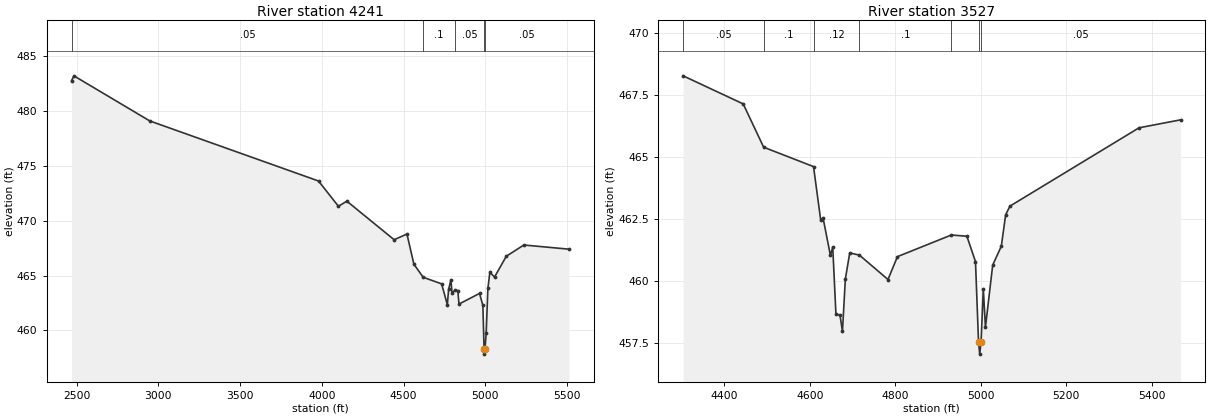
Type RM Length L Ch R = 1,4241,714,714,714
BEGIN DESCRIPTION:
UNT0090 IN SAND CR 4.0
END DESCRIPTION:
XS GIS Cut Line= 5
      3463644.29     10528209.43      3461984.14     10527174.27
      3461630.40     10526850.92      3461600.02     10526696.84
      3461231.07     10526438.58
#Sta/Elev= 30
  2468.8  482.74  2483.2  483.19  2947.6  479.08  3979.8  473.61  4101.5  471.31
  4153.4  471.77  4442.4  468.26  4520.8  468.78  4563.3  466.03  4620.1  464.84
  4732.9  464.24  4768.0  462.34  4775.5  463.73  4789.6  464.60  4796.4  463.44
  4816.1  463.65  4832.2  463.63  4839.0  462.40  4964.9  463.37  4985.3  462.27
  4992.5  458.34  4995.2  457.84  4998.5  458.34  5005.7  459.81  5015.9  463.82
  5028.0  465.30  5056.5  464.86  5128.9  466.76  5236.1  467.78  5511.9  467.40
#Mann=5,-1,0
  2468.8    0.05       0  4620.1     0.1       0  4816.1    0.05       0
  4992.5   0.035       0  4998.5    0.05       0
Bank Sta=4992.5,4998.5
Exp/Cntr=0.3,0.1

Type RM Length L Ch R = 1,3527,0,0,0
BEGIN DESCRIPTION:
UNT0090 IN SAND CR 5.0
END DESCRIPTION:
XS GIS Cut Line= 3
      3462454.74     10526527.07      3461888.81     10526256.25
      3461355.64     10526190.47
#Sta/Elev= 30
  4303.4  468.26  4444.1  467.13  4491.9  465.39  4608.7  464.61  4625.5  462.46
  4631.0  462.55  4648.2  461.04  4653.7  461.37  4661.1  458.70  4670.8  458.63
  4676.4  457.98  4683.2  460.09  4693.5  461.14  4716.3  461.05  4783.0  460.07
  4805.2  460.99  4931.4  461.86  4967.8  461.81  4987.9  460.79  4995.0  457.57
  4997.8  457.07  5001.0  457.57  5006.2  459.70  5011.2  458.15  5028.2  460.65
  5048.4  461.41  5058.5  462.67  5068.5  463.02  5370.8  466.17  5468.0  466.49
#Mann=7,-1,0
  4303.4    0.05       0  4491.9     0.1       0  4608.7    0.12       0
  4716.3     0.1       0  4931.4    0.05       0  4995.0   0.035       0
  5001.0    0.05       0
Bank Sta=4995,5001
Exp/Cntr=0.3,0.1

Chan Stop Cuts=-1