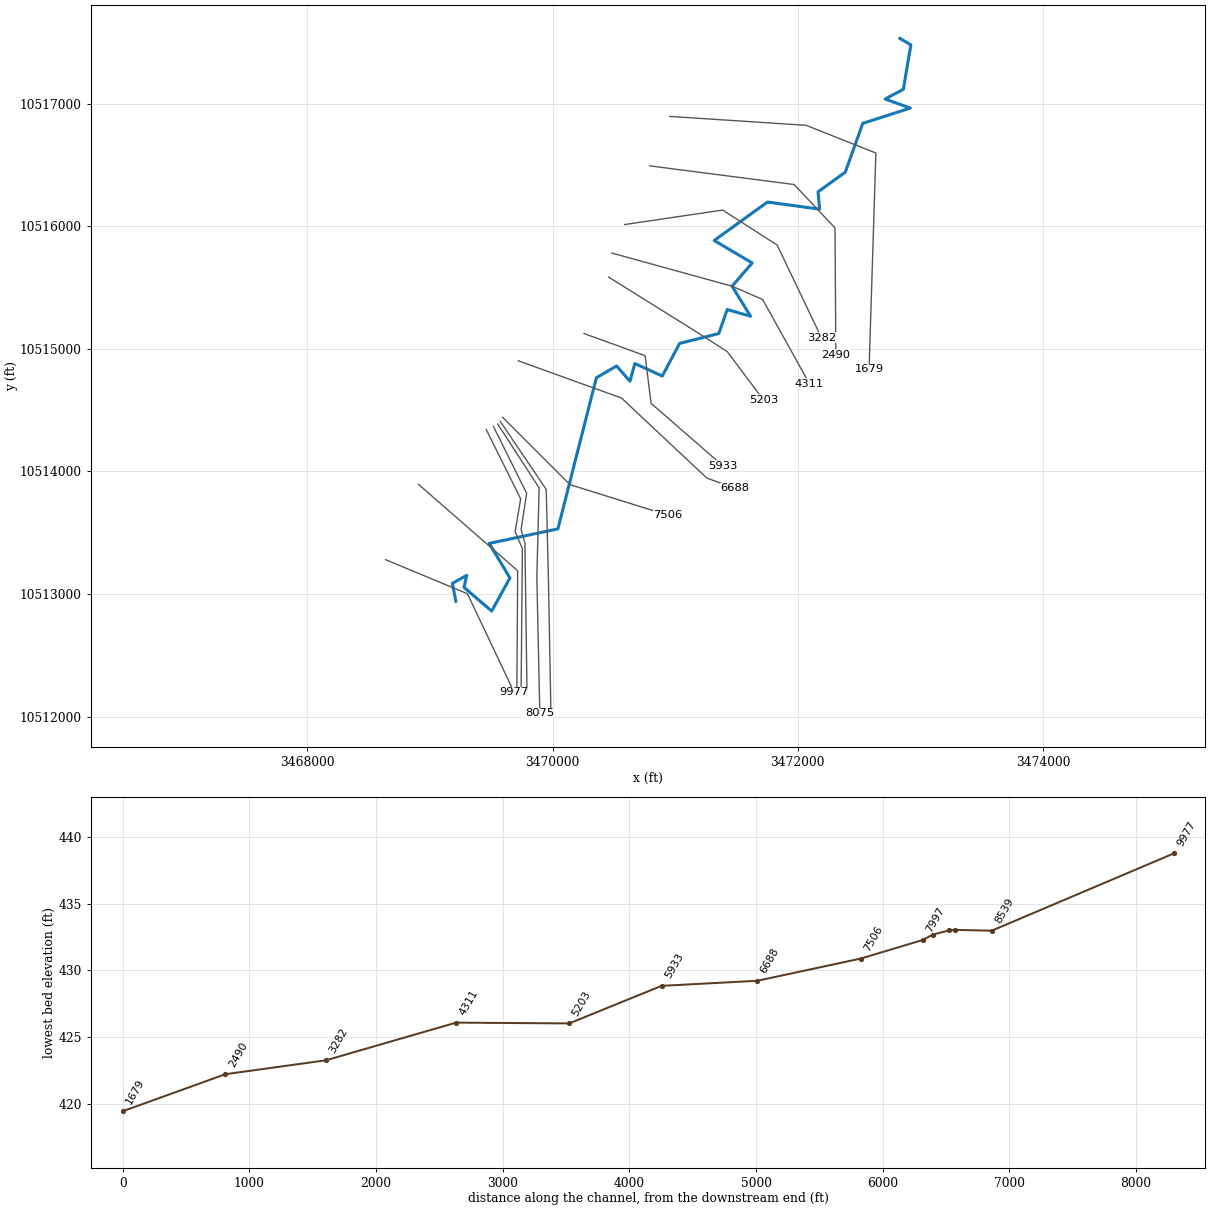
--- UNT0091 IN SAND CR.prj (project) ---

Proj Title=UNT0091 IN SAND CR Base Level Engineering
Current Plan=p01
Default Exp/Contr=0.3,0.1
English Units
Geom File=g01
Flow File=f01
Plan File=p01
BEGIN DESCRIPTION:
UNT0091 IN SAND CR
END DESCRIPTION:

--- UNT0091 IN SAND CR.p01 (plan) ---

Plan Title=Multiple Run
Short Identifier=Multiple
Geom File=g01
Flow File=f01
Subcritical Flow
K Sum by GR= 0
Std Step Tol= 0.01
Critical Tol= 0.01
Num of Std Step Trials= 20
Max Error Tol= 0.3
Flow Tol Ratio= 0.001
Split Flow NTrial= 30
Split Flow Tol= 0.02
Split Flow Ratio= 0.02
Log Output Level= 0
Friction Slope Method= 1
Unsteady Friction Slope Method= 2
Unsteady Bridges Friction Slope Method= 1
Parabolic Critical Depth
Global Vel Dist=  1 , 1 , 1
Global Log Level= 0
CheckData=True
Encroach Param= -1, 0, 0, 0
BEGIN DESCRIPTION:
Multiple Run
END DESCRIPTION:

--- UNT0091 IN SAND CR.f01 (steady flow) ---

Flow Title=Multiple
Number of Profiles=7
Profile Names=10-year,25-year,50-year,1pct_min,100-year,1pct_plu,500-year
River Rch & RM= UNT0091 IN SAND ,Reach-1,9977
    1929    2752    3456    3161    4275    5781    6525
River Rch & RM= UNT0091 IN SAND ,Reach-1,6688
    1823    2576    3212    2915    3942    5331    5927
Boundary for River Rch & Prof#=UNT0091 IN SAND ,Reach-1,1
Up Type=0
Dn Type=3
Dn Slope=0.005
Boundary for River Rch & Prof#=UNT0091 IN SAND ,Reach-1,2
Up Type=0
Dn Type=3
Dn Slope=0.005
Boundary for River Rch & Prof#=UNT0091 IN SAND ,Reach-1,3
Up Type=0
Dn Type=3
Dn Slope=0.005
Boundary for River Rch & Prof#=UNT0091 IN SAND ,Reach-1,4
Up Type=0
Dn Type=3
Dn Slope=0.005
Boundary for River Rch & Prof#=UNT0091 IN SAND ,Reach-1,5
Up Type=0
Dn Type=3
Dn Slope=0.005
Boundary for River Rch & Prof#=UNT0091 IN SAND ,Reach-1,6
Up Type=0
Dn Type=3
Dn Slope=0.005
Boundary for River Rch & Prof#=UNT0091 IN SAND ,Reach-1,7
Up Type=0
Dn Type=3
Dn Slope=0.005

--- UNT0091 IN SAND CR.g01 (geometry) ---

Geom Title=Existing Conditions

River Reach=UNT0091 IN SAND ,Reach-1
Reach XY= 30
      3469210.94     10512940.35      3469182.73     10513086.61
      3469299.92     10513152.59      3469277.78     10513054.06
      3469503.04     10512860.49      3469652.35     10513130.88
      3469483.08     10513412.57      3470043.30     10513530.84
      3470357.04     10514763.37      3470522.21     10514859.51
      3470630.68     10514735.10      3470671.41     10514879.19
      3470894.71     10514777.57      3471036.06     10515043.73
      3471355.65     10515124.14      3471423.91     10515319.52
      3471614.19     10515265.75      3471463.74     10515509.99
      3471628.23     10515699.75      3471317.92     10515882.70
      3471752.66     10516196.65      3472177.80     10516138.37
      3472165.34     10516280.22      3472386.74     10516439.52
      3472529.55     10516838.05      3472917.94     10516963.02
      3472711.96     10517036.78      3472860.79     10517116.39
      3472922.04     10517478.12      3472832.11     10517531.64

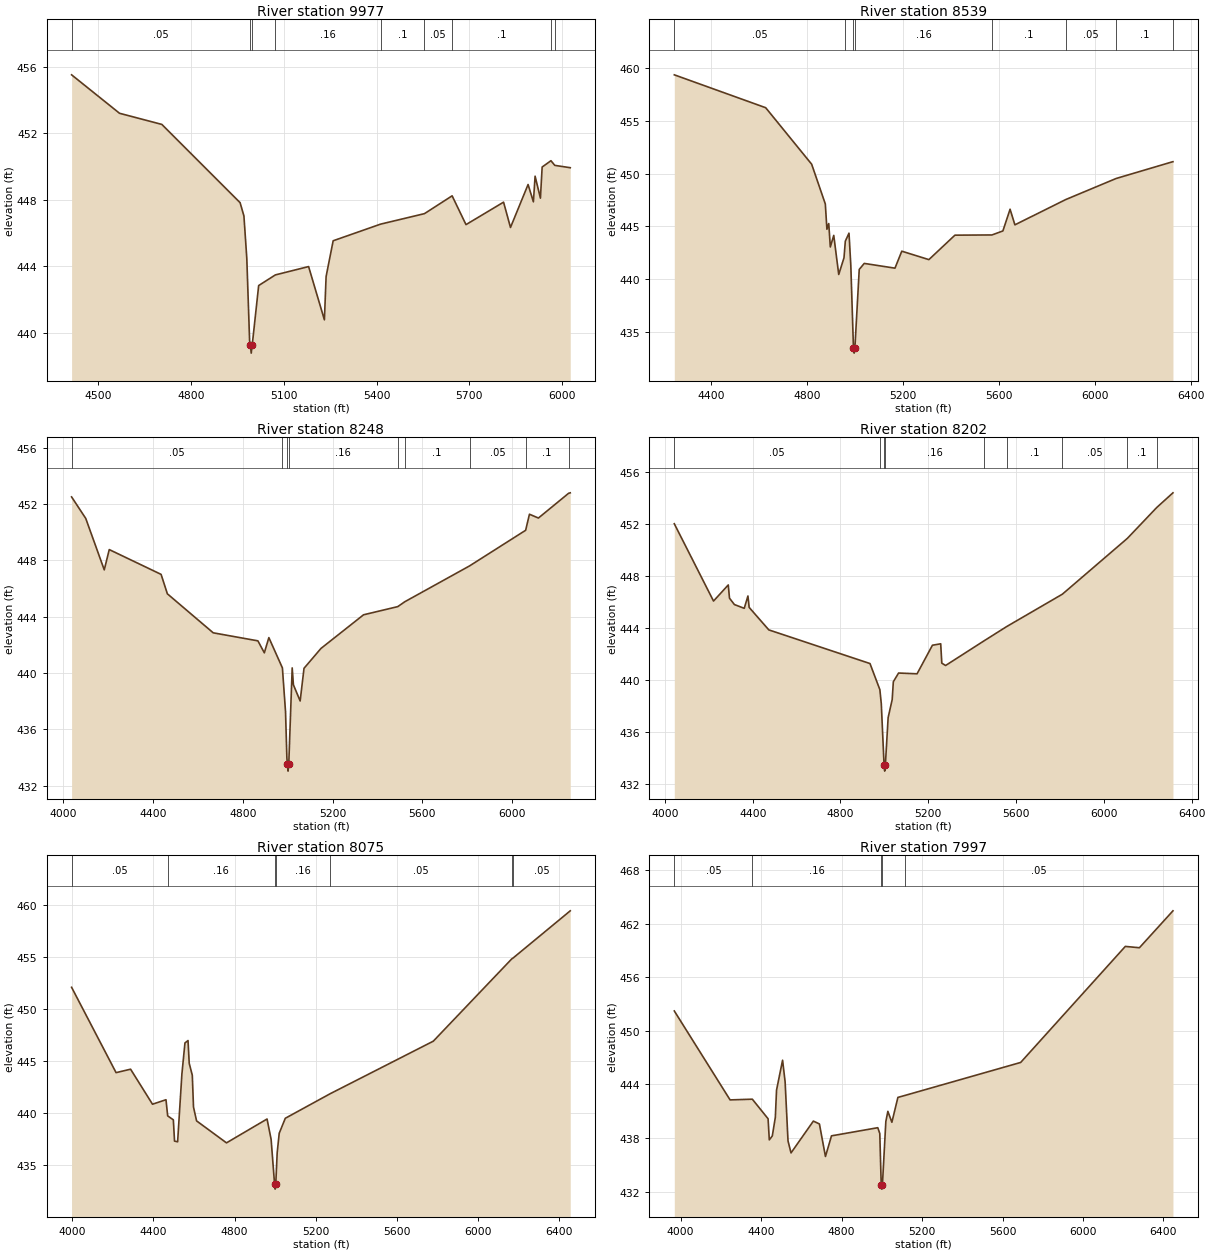
Type RM Length L Ch R = 1,9977,1438,1438,1438
BEGIN DESCRIPTION:
UNT0091 IN SAND CR 11.06
END DESCRIPTION:
XS GIS Cut Line= 3
      3468638.99     10513279.56      3469305.67     10513001.77
      3469687.25     10512196.98
#Sta/Elev= 30
  4413.3  455.50  4568.3  453.19  4705.3  452.52  4958.3  447.82  4970.7  447.02
  4980.0  444.47  4989.1  439.51  4991.6  439.28  4994.3  438.78  4997.6  439.28
  5018.4  442.84  5072.5  443.48  5179.9  443.98  5231.0  440.78  5236.5  443.38
  5259.3  445.53  5412.9  446.53  5554.7  447.16  5644.1  448.23  5689.0  446.50
  5810.5  447.85  5832.9  446.33  5889.8  448.91  5907.0  447.87  5912.5  449.41
  5929.7  448.09  5935.3  449.96  5963.8  450.34  5976.2  450.06  6026.2  449.92
#Mann=9,-1,0
  4413.3    0.05       0  4991.6    0.03       0  4997.6    0.05       0
  5072.5    0.16       0  5412.9     0.1       0  5554.7    0.05       0
  5644.1     0.1       0  5963.8    0.12       0  5976.2     0.1       0
Bank Sta=4991.6,4997.6
Exp/Cntr=0.3,0.1

Type RM Length L Ch R = 1,8539,291,291,291
BEGIN DESCRIPTION:
UNT0091 IN SAND CR 11.05
END DESCRIPTION:
XS GIS Cut Line= 3
      3468906.36     10513894.13      3469715.39     10513189.27
      3469708.44     10512182.31
#Sta/Elev= 30
  4246.8  459.38  4628.0  456.26  4819.8  450.90  4876.7  447.13  4883.4  444.73
  4891.0  445.27  4897.6  443.05  4911.9  444.15  4932.7  440.44  4954.6  442.02
  4960.2  443.60  4975.5  444.36  4983.1  441.29  4994.1  433.48  4996.9  432.98
  5000.1  433.48  5018.2  440.92  5039.1  441.49  5167.3  441.04  5195.7  442.65
  5308.7  441.85  5417.4  444.17  5571.8  444.19  5617.4  444.57  5647.4  446.63
  5667.5  445.15  5879.8  447.55  6090.2  449.55  6326.4  451.14  6326.8  451.14
#Mann=8,-1,0
  4246.8    0.05       0  4960.2    0.16       0  4994.1    0.07       0
  5000.1    0.16       0  5571.8     0.1       0  5879.8    0.05       0
  6090.2     0.1       0  6326.4    0.05       0
Bank Sta=4994.1,5000.1
Exp/Cntr=0.3,0.1

Type RM Length L Ch R = 1,8248,46,46,46
BEGIN DESCRIPTION:
UNT0091 IN SAND CR 11.04
END DESCRIPTION:
XS GIS Cut Line= 5
      3469458.43     10514342.08      3469739.69     10513776.08
      3469694.55     10513508.72      3469753.58     10513369.83
      3469743.17     10512199.67
#Sta/Elev= 30
  4036.2  452.51  4099.4  450.98  4181.9  447.33  4204.2  448.77  4435.4  447.01
  4463.4  445.63  4667.9  442.86  4867.2  442.29  4895.9  441.44  4916.1  442.52
  4976.5  440.37  4990.5  437.25  4996.5  433.97  4998.9  433.54  5001.7  433.04
  5004.9  433.54  5020.2  440.37  5025.6  439.17  5055.7  438.02  5072.9  440.34
  5148.5  441.75  5338.5  444.14  5491.1  444.72  5522.9  445.07  5811.3  447.61
  6061.5  450.14  6078.5  451.28  6118.5  451.01  6253.4  452.77  6260.5  452.80
#Mann=9,-1,0
  4036.2    0.05       0  4976.5    0.16       0  4998.9    0.07       0
  5004.9    0.16       0  5491.1    0.05       0  5522.9     0.1       0
  5811.3    0.05       0  6061.5     0.1       0  6253.4    0.05       0
Bank Sta=4998.9,5004.9
Exp/Cntr=0.3,0.1

Type RM Length L Ch R = 1,8202,127,127,127
BEGIN DESCRIPTION:
UNT0091 IN SAND CR 11.03
END DESCRIPTION:
XS GIS Cut Line= 5
      3469517.45     10514366.40      3469788.30     10513821.22
      3469743.17     10513526.08      3469774.42     10513414.97
      3469791.76     10512165.83
#Sta/Elev= 30
  4042.8  452.04  4221.5  446.09  4288.7  447.33  4294.3  446.31  4316.7  445.82
  4361.5  445.53  4378.3  446.48  4383.9  445.60  4473.5  443.87  4934.4  441.28
  4979.4  439.27  4985.9  438.19  4998.5  433.50  5001.3  433.00  5004.5  433.50
  5017.1  437.12  5035.6  438.51  5040.8  439.88  5064.7  440.55  5148.9  440.49
  5218.9  442.69  5256.6  442.80  5261.6  441.31  5278.9  441.13  5453.4  443.02
  5557.6  444.13  5811.1  446.62  6107.4  450.92  6240.9  453.29  6314.8  454.42
#Mann=9,-1,0
  4042.8    0.05       0  4979.4    0.16       0  4998.5    0.07       0
  5004.5    0.16       0  5453.4    0.05       0  5557.6     0.1       0
  5811.1    0.05       0  6107.4     0.1       0  6240.9    0.05       0
Bank Sta=4998.5,5004.5
Exp/Cntr=0.3,0.1

Type RM Length L Ch R = 1,8075,78,78,78
BEGIN DESCRIPTION:
UNT0091 IN SAND CR 11.01
END DESCRIPTION:
XS GIS Cut Line= 4
      3469552.51     10514385.63      3469890.29     10513865.68
      3469871.64     10513137.19      3469895.94     10512026.32
#Sta/Elev= 30
  3996.2  452.06  4215.6  443.87  4287.2  444.20  4395.3  440.84  4461.8  441.27
  4470.2  439.72  4498.1  439.34  4504.0  437.30  4519.2  437.23  4540.3  443.73
  4555.4  446.72  4570.5  446.95  4576.5  444.76  4591.6  443.62  4597.6  440.56
  4612.7  439.24  4760.3  437.13  4960.4  439.42  4980.4  437.47  4997.4  433.19
  5000.2  432.69  5003.4  433.19  5010.4  436.19  5020.4  438.05  5050.4  439.49
  5272.2  441.85  5780.6  446.89  6167.7  454.79  6174.1  454.87  6456.1  459.40
#Mann=7,-1,0
  3996.2    0.05       0  4470.2    0.16       0  4997.4    0.07       0
  5003.4    0.16       0  5272.2    0.05       0  6167.7     0.1       0
  6174.1    0.05       0
Bank Sta=4997.4,5003.4
Exp/Cntr=0.3,0.1

Type RM Length L Ch R = 1,7997,491,491,491
BEGIN DESCRIPTION:
UNT0091 IN SAND CR 11.02
END DESCRIPTION:
XS GIS Cut Line= 4
      3469573.00     10514408.06      3469948.03     10513852.47
      3469965.39     10513151.08      3469986.19     10512045.00
#Sta/Elev= 30
  3968.9  452.22  4246.2  442.27  4356.7  442.35  4435.0  440.16  4441.0  437.80
  4456.0  438.24  4471.0  440.32  4477.0  443.36  4507.0  446.71  4519.6  444.30
  4534.0  437.69  4549.0  436.34  4660.0  439.90  4690.1  439.58  4720.1  435.94
  4750.1  438.25  4980.1  439.16  4990.1  438.52  4997.2  432.79  4999.9  432.29
  5003.2  432.79  5020.2  439.85  5030.2  440.99  5050.2  439.77  5080.2  442.55
  5113.7  442.76  5690.3  446.46  6210.4  459.44  6280.4  459.29  6447.1  463.42
#Mann=5,-1,0
  3968.9    0.05       0  4356.7    0.16       0  4997.2    0.07       0
  5003.2    0.16       0  5113.7    0.05       0
Bank Sta=4997.2,5003.2
Exp/Cntr=0.3,0.1

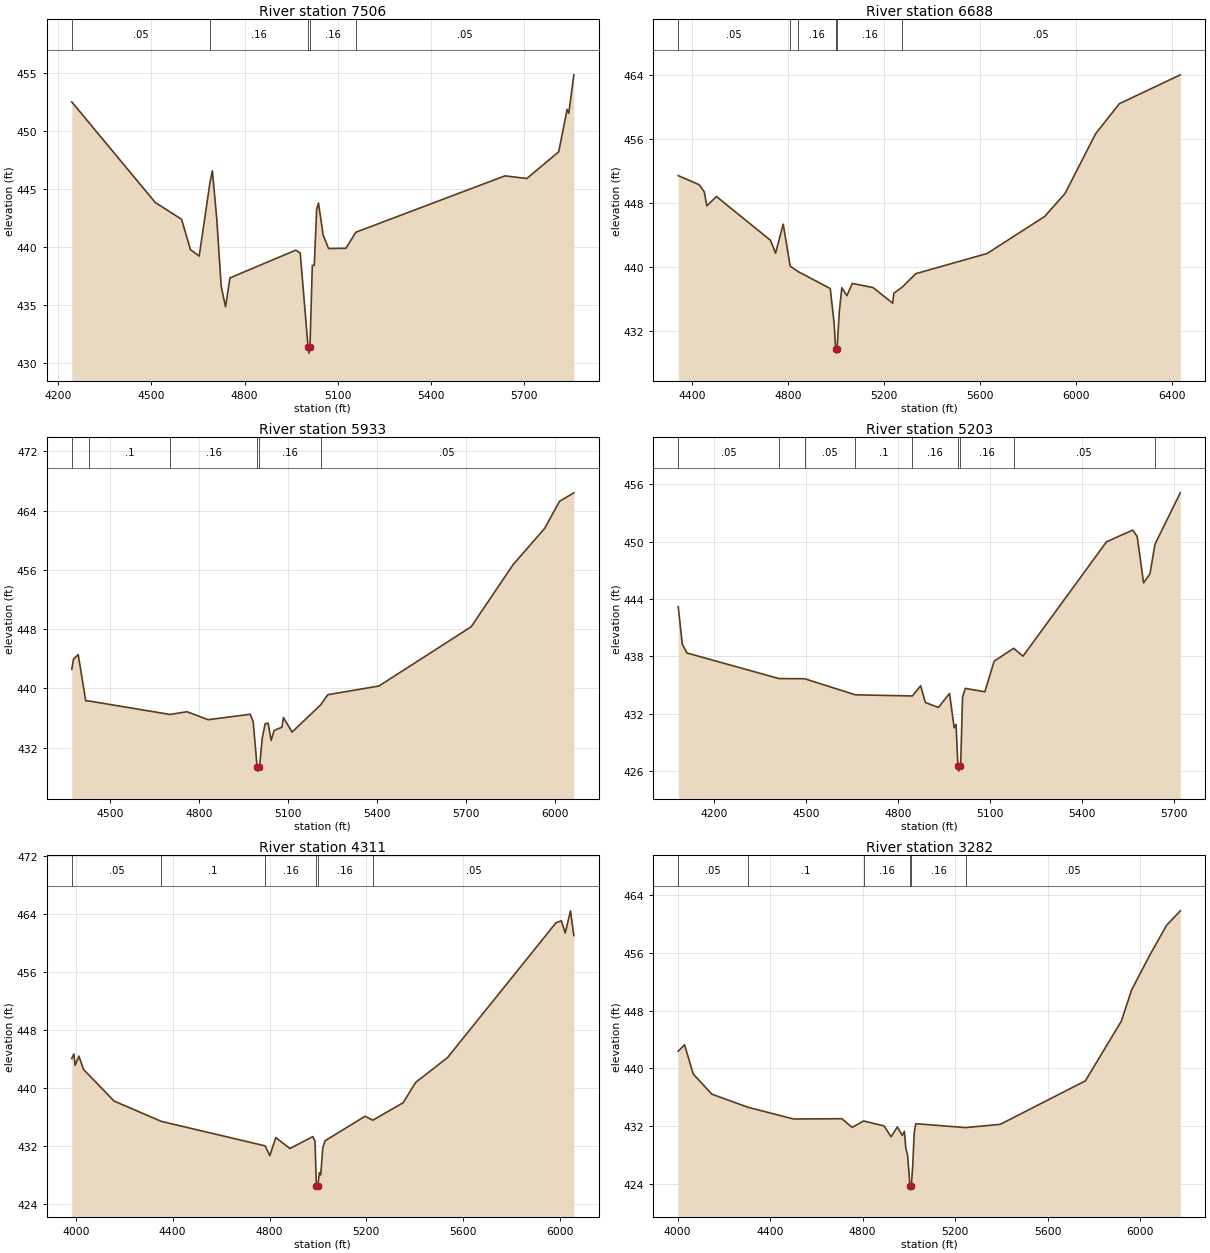
Type RM Length L Ch R = 1,7506,818,818,818
BEGIN DESCRIPTION:
UNT0091 IN SAND CR 11.0
END DESCRIPTION:
XS GIS Cut Line= 3
      3469592.14     10514441.61      3470142.11     10513891.64
      3470942.08     10513641.65
#Sta/Elev= 30
  4243.7  452.50  4512.4  443.85  4597.2  442.40  4625.5  439.80  4653.8  439.24
  4688.2  445.51  4696.2  446.57  4710.3  442.47  4724.5  436.66  4738.6  434.87
  4752.8  437.36  4964.9  439.75  4979.0  439.50  5004.3  431.39  5007.1  430.89
  5010.3  431.39  5017.9  438.44  5024.1  438.44  5031.9  443.27  5037.7  443.80
  5052.9  441.03  5070.2  439.89  5126.2  439.91  5157.9  441.29  5638.0  446.14
  5708.2  445.91  5810.9  448.21  5838.1  451.86  5843.4  451.53  5859.6  454.83
#Mann=5,-1,0
  4243.7    0.05       0  4688.2    0.16       0  5004.3    0.07       0
  5010.3    0.16       0  5157.9    0.05       0
Bank Sta=5004.3,5010.3
Exp/Cntr=0.3,0.1

Type RM Length L Ch R = 1,6688,755,755,755
BEGIN DESCRIPTION:
UNT0091 IN SAND CR 9.0
END DESCRIPTION:
XS GIS Cut Line= 4
      3469719.97     10514901.86      3470561.90     10514598.09
      3471258.07     10513945.43      3471488.96     10513860.87
#Sta/Elev= 30
  4340.8  451.40  4428.1  450.27  4449.6  449.37  4460.0  447.62  4500.4  448.79
  4725.8  443.32  4747.0  441.72  4778.9  445.34  4807.9  440.09  4841.7  439.40
  4975.3  437.29  4991.6  432.87  4997.6  429.72  5000.4  429.22  5003.6  429.72
  5012.8  434.35  5023.5  437.39  5044.7  436.40  5067.3  437.93  5154.0  437.41
  5235.9  435.46  5240.5  436.70  5275.3  437.46  5332.3  439.15  5629.8  441.67
  5870.1  446.30  5955.1  449.18  6082.6  456.64  6181.7  460.39  6436.0  464.00
#Mann=6,-1,0
  4340.8    0.05       0  4807.9     0.1       0  4841.7    0.16       0
  4997.6    0.07       0  5003.6    0.16       0  5275.3    0.05       0
Bank Sta=4997.6,5003.6
Exp/Cntr=0.3,0.1

Type RM Length L Ch R = 1,5933,730,730,730
BEGIN DESCRIPTION:
UNT0091 IN SAND CR 8.0
END DESCRIPTION:
XS GIS Cut Line= 4
      3470256.44     10515123.99      3470754.68     10514943.54
      3470803.29     10514554.65      3471386.65     10514047.68
#Sta/Elev= 30
  4369.7  442.58  4375.7  443.97  4391.5  444.57  4416.8  438.33  4428.7  438.30
  4701.2  436.49  4758.6  436.86  4829.8  435.78  4972.1  436.52  4982.1  435.50
  4995.5  429.34  4998.3  428.84  5001.5  429.34  5003.6  429.38  5012.4  433.25
  5022.5  435.24  5032.5  435.31  5042.6  433.00  5052.7  434.33  5079.1  434.77
  5084.2  436.08  5113.2  434.11  5209.7  437.78  5234.1  439.16  5406.5  440.33
  5717.9  448.33  5859.6  456.73  5965.8  461.60  6016.1  465.27  6064.4  466.41
#Mann=6,-1,0
  4369.7    0.05       0  4428.7     0.1       0  4701.2    0.16       0
  4995.5    0.07       0  5001.5    0.16       0  5209.7    0.05       0
Bank Sta=4995.5,5001.5
Exp/Cntr=0.3,0.1

Type RM Length L Ch R = 1,5203,892,892,892
BEGIN DESCRIPTION:
UNT0091 IN SAND CR 6.0
END DESCRIPTION:
XS GIS Cut Line= 4
      3470456.93     10515584.23      3471150.51     10515151.87
      3471424.70     10514976.46      3471719.97     10514582.41
#Sta/Elev= 30
  4084.6  443.20  4097.8  439.28  4113.1  438.36  4412.5  435.69  4496.2  435.67
  4661.7  433.99  4847.1  433.87  4874.2  434.94  4889.5  433.19  4931.8  432.67
  4968.2  434.13  4983.4  430.54  4989.3  430.89  4995.6  426.52  4998.4  426.02
  5001.6  426.52  5004.5  426.73  5010.6  433.75  5019.8  434.66  5083.2  434.31
  5113.6  437.51  5176.9  438.85  5207.5  438.03  5479.3  449.97  5564.8  451.20
  5579.3  450.54  5600.2  445.69  5621.0  446.63  5637.3  449.72  5719.8  455.09
#Mann=9,-1,0
  4084.6    0.05       0  4412.5     0.1       0  4496.2    0.05       0
  4661.7     0.1       0  4847.1    0.16       0  4995.6    0.07       0
  5001.6    0.16       0  5176.9    0.05       0  5637.3    0.16       0
Bank Sta=4995.6,5001.6
Exp/Cntr=0.3,0.1

Type RM Length L Ch R = 1,4311,1029,1029,1029
BEGIN DESCRIPTION:
UNT0091 IN SAND CR 4.0
END DESCRIPTION:
XS GIS Cut Line= 4
      3470483.67     10515780.44      3471463.74     10515509.99
      3471713.01     10515401.87      3472094.34     10514715.49
#Sta/Elev= 30
  3983.3  444.07  3992.0  444.71  3997.4  443.14  4012.8  444.41  4031.8  442.58
  4158.0  438.22  4353.1  435.42  4782.1  432.04  4801.2  430.69  4825.9  433.19
  4884.2  431.68  4978.9  433.32  4987.9  432.68  4993.6  426.58  4996.3  426.08
  4999.6  426.58  5006.0  428.35  5011.5  428.05  5020.0  431.79  5029.5  432.75
  5194.4  436.12  5226.7  435.58  5352.0  437.99  5403.6  440.79  5535.1  444.21
  5983.6  462.81  6005.3  463.06  6021.3  461.39  6043.1  464.44  6056.9  461.02
#Mann=6,-1,0
  3983.3    0.05       0  4353.1     0.1       0  4782.1    0.16       0
  4993.6    0.07       0  4999.6    0.16       0  5226.7    0.05       0
Bank Sta=4993.6,4999.6
Exp/Cntr=0.3,0.1

Type RM Length L Ch R = 1,3282,792,792,792
BEGIN DESCRIPTION:
UNT0091 IN SAND CR 3.0
END DESCRIPTION:
XS GIS Cut Line= 4
      3470588.02     10516012.98      3471386.63     10516131.04
      3471831.07     10515846.31      3472192.11     10515091.63
#Sta/Elev= 30
  4002.4  442.37  4029.6  443.26  4067.2  439.21  4148.1  436.41  4303.8  434.60
  4501.5  432.97  4710.2  433.01  4754.6  431.81  4804.4  432.70  4892.7  432.01
  4923.1  430.51  4950.2  431.87  4971.3  430.69  4980.6  431.27  4986.5  428.98
  4994.3  427.99  5004.7  423.75  5007.4  423.25  5010.7  423.75  5016.9  426.59
  5022.9  430.96  5030.0  432.32  5245.2  431.78  5395.2  432.23  5763.5  438.26
  5919.1  446.54  5963.5  450.87  6041.1  455.63  6114.6  459.82  6174.1  461.83
#Mann=6,-1,0
  4002.4    0.05       0  4303.8     0.1       0  4804.4    0.16       0
  5004.7    0.07       0  5010.7    0.16       0  5245.2    0.05       0
Bank Sta=5004.7,5010.7
Exp/Cntr=0.3,0.1

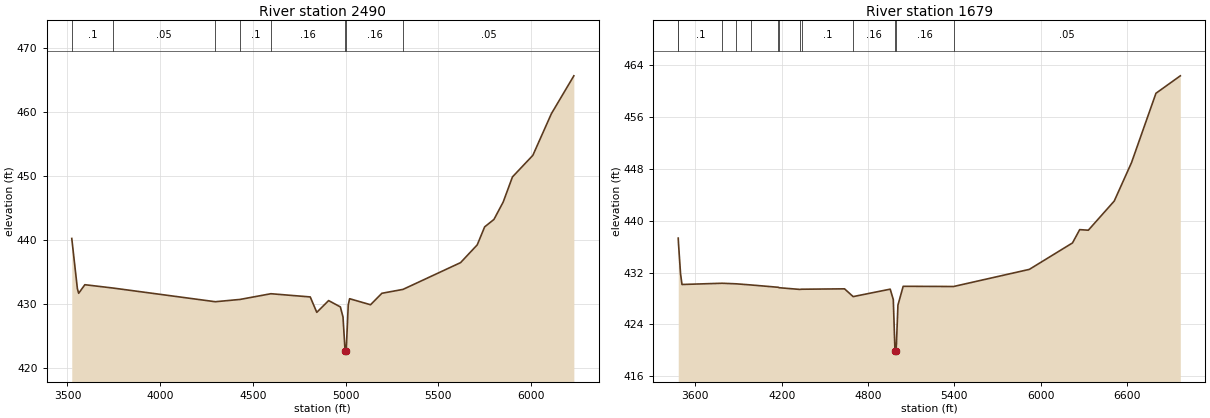
Type RM Length L Ch R = 1,2490,811,811,811
BEGIN DESCRIPTION:
UNT0091 IN SAND CR 2.0
END DESCRIPTION:
XS GIS Cut Line= 4
      3470792.08     10516491.65      3471969.96     10516339.37
      3472303.29     10515985.20      3472310.24     10514950.47
#Sta/Elev= 30
  3523.1  440.29  3553.4  432.44  3560.3  431.72  3593.7  433.06  3745.6  432.54
  4297.7  430.40  4431.0  430.76  4597.4  431.65  4809.7  431.15  4845.0  428.74
  4908.8  430.58  4972.3  429.59  4986.5  428.01  4997.7  422.71  5000.4  422.21
  5003.7  422.71  5014.8  429.91  5022.1  430.87  5135.0  429.93  5196.2  431.72
  5310.3  432.33  5620.7  436.51  5710.7  439.29  5750.7  442.10  5800.7  443.26
  5850.7  445.98  5900.7  449.91  6010.7  453.28  6110.7  459.79  6231.9  465.71
#Mann=8,-1,0
  3523.1     0.1       0  3745.6    0.05       0  4297.7    0.16       0
  4431.0     0.1       0  4597.4    0.16       0  4997.7    0.07       0
  5003.7    0.16       0  5310.3    0.05       0
Bank Sta=4997.7,5003.7
Exp/Cntr=0.3,0.1

Type RM Length L Ch R = 1,1679,0,0,0
BEGIN DESCRIPTION:
UNT0091 IN SAND CR 1.0
END DESCRIPTION:
XS GIS Cut Line= 4
      3470956.06     10516894.92      3472067.54     10516822.25
      3472636.63     10516596.31      3472581.07     10514832.44
#Sta/Elev= 30
  3480.8  437.32  3482.6  436.49  3496.9  431.82  3506.9  430.17  3786.2  430.36
  3885.5  430.27  3984.9  430.10  4175.8  429.74  4183.6  429.67  4326.4  429.41
  4338.3  429.44  4637.1  429.50  4696.9  428.30  4954.6  429.45  4976.1  427.85
  4987.8  419.93  4990.5  419.43  4993.8  419.93  4997.7  420.87  5008.4  426.99
  5044.8  429.89  5395.5  429.86  5922.0  432.50  6222.1  436.58  6272.1  438.63
  6332.2  438.54  6512.3  443.04  6632.3  448.96  6802.4  459.66  6971.7  462.35
#Mann=13,-1,0
  3480.8    0.05       0  3482.6     0.1       0  3786.2    0.12       0
  3885.5     0.1       0  3984.9    0.05       0  4175.8    0.16       0
  4183.6     0.1       0  4326.4    0.12       0  4338.3     0.1       0
  4696.9    0.16       0  4987.8    0.07       0  4993.8    0.16       0
  5395.5    0.05       0
Bank Sta=4987.8,4993.8
Exp/Cntr=0.3,0.1

Chan Stop Cuts=-1