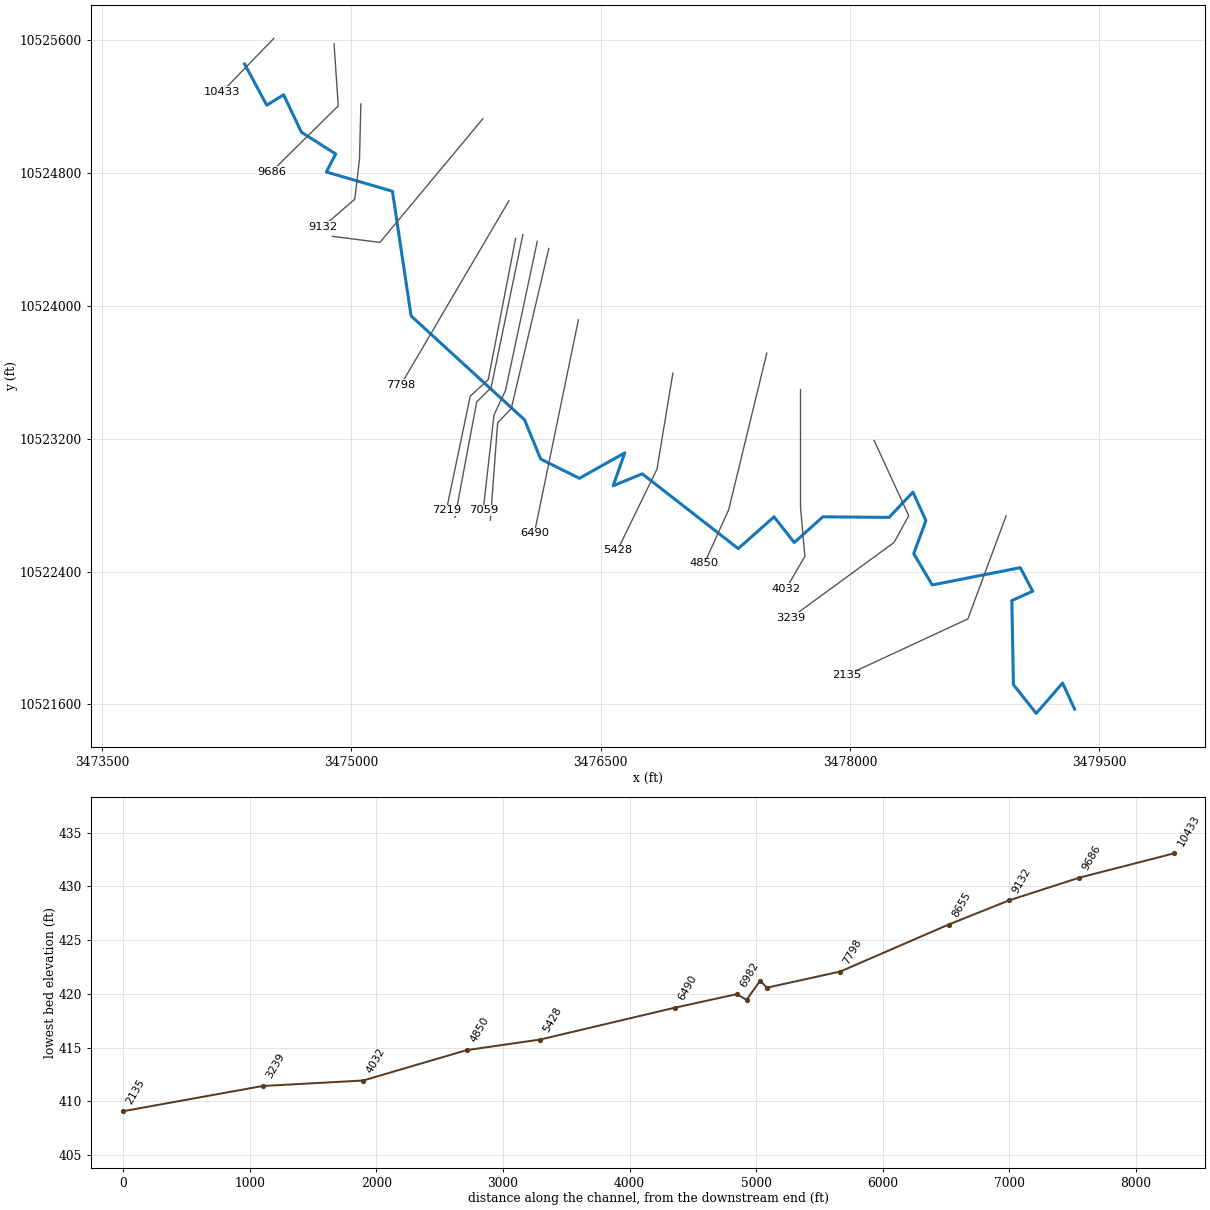
--- UNT0092 IN SAND CR.prj (project) ---

Proj Title=UNT0092 IN SAND CR Base Level Engineering
Current Plan=p01
Default Exp/Contr=0.3,0.1
English Units
Geom File=g01
Flow File=f01
Plan File=p01
BEGIN DESCRIPTION:
UNT0092 IN SAND CR
END DESCRIPTION:

--- UNT0092 IN SAND CR.p01 (plan) ---

Plan Title=Multiple Run
Short Identifier=Multiple
Geom File=g01
Flow File=f01
Subcritical Flow
K Sum by GR= 0
Std Step Tol= 0.01
Critical Tol= 0.01
Num of Std Step Trials= 20
Max Error Tol= 0.3
Flow Tol Ratio= 0.001
Split Flow NTrial= 30
Split Flow Tol= 0.02
Split Flow Ratio= 0.02
Log Output Level= 0
Friction Slope Method= 1
Unsteady Friction Slope Method= 2
Unsteady Bridges Friction Slope Method= 1
Parabolic Critical Depth
Global Vel Dist=  1 , 1 , 1
Global Log Level= 0
CheckData=True
Encroach Param= -1, 0, 0, 0
BEGIN DESCRIPTION:
Multiple Run
END DESCRIPTION:

--- UNT0092 IN SAND CR.f01 (steady flow) ---

Flow Title=Multiple
Number of Profiles=7
Profile Names=10-year,25-year,50-year,1pct_min,100-year,1pct_plu,500-year
River Rch & RM= UNT0092 IN SAND ,Reach-1,10433
     539     710     844     735     994    1344    1369
River Rch & RM= UNT0092 IN SAND ,Reach-1,8655
    1475    2053    2534    2278    3081    4166    4542
Boundary for River Rch & Prof#=UNT0092 IN SAND ,Reach-1,1
Up Type=0
Dn Type=3
Dn Slope=0.005
Boundary for River Rch & Prof#=UNT0092 IN SAND ,Reach-1,2
Up Type=0
Dn Type=3
Dn Slope=0.005
Boundary for River Rch & Prof#=UNT0092 IN SAND ,Reach-1,3
Up Type=0
Dn Type=3
Dn Slope=0.005
Boundary for River Rch & Prof#=UNT0092 IN SAND ,Reach-1,4
Up Type=0
Dn Type=3
Dn Slope=0.005
Boundary for River Rch & Prof#=UNT0092 IN SAND ,Reach-1,5
Up Type=0
Dn Type=3
Dn Slope=0.005
Boundary for River Rch & Prof#=UNT0092 IN SAND ,Reach-1,6
Up Type=0
Dn Type=3
Dn Slope=0.005
Boundary for River Rch & Prof#=UNT0092 IN SAND ,Reach-1,7
Up Type=0
Dn Type=3
Dn Slope=0.005

--- UNT0092 IN SAND CR.g01 (geometry) ---

Geom Title=Existing Conditions

River Reach=UNT0092 IN SAND ,Reach-1
Reach XY= 30
      3474357.57     10525456.32      3474490.94     10525208.25
      3474592.59     10525270.73      3474699.67     10525045.23
      3474906.04     10524914.58      3474849.57     10524806.00
      3475247.21     10524690.02      3475359.51     10523939.10
      3476042.26     10523313.62      3476139.48     10523077.16
      3476372.12     10522961.19      3476645.39     10523114.31
      3476575.50     10522916.34      3476750.42     10522988.27
      3477328.16     10522538.01      3477543.57     10522729.04
      3477665.40     10522574.59      3477837.23     10522729.44
      3478235.65     10522725.81      3478379.73     10522878.00
      3478457.53     10522706.32      3478384.07     10522507.27
      3478495.83     10522319.08      3479025.29     10522423.14
      3479100.17     10522281.11      3478974.66     10522225.32
      3478984.15     10521718.26      3479121.25     10521545.66
      3479279.91     10521728.31      3479352.11     10521571.64

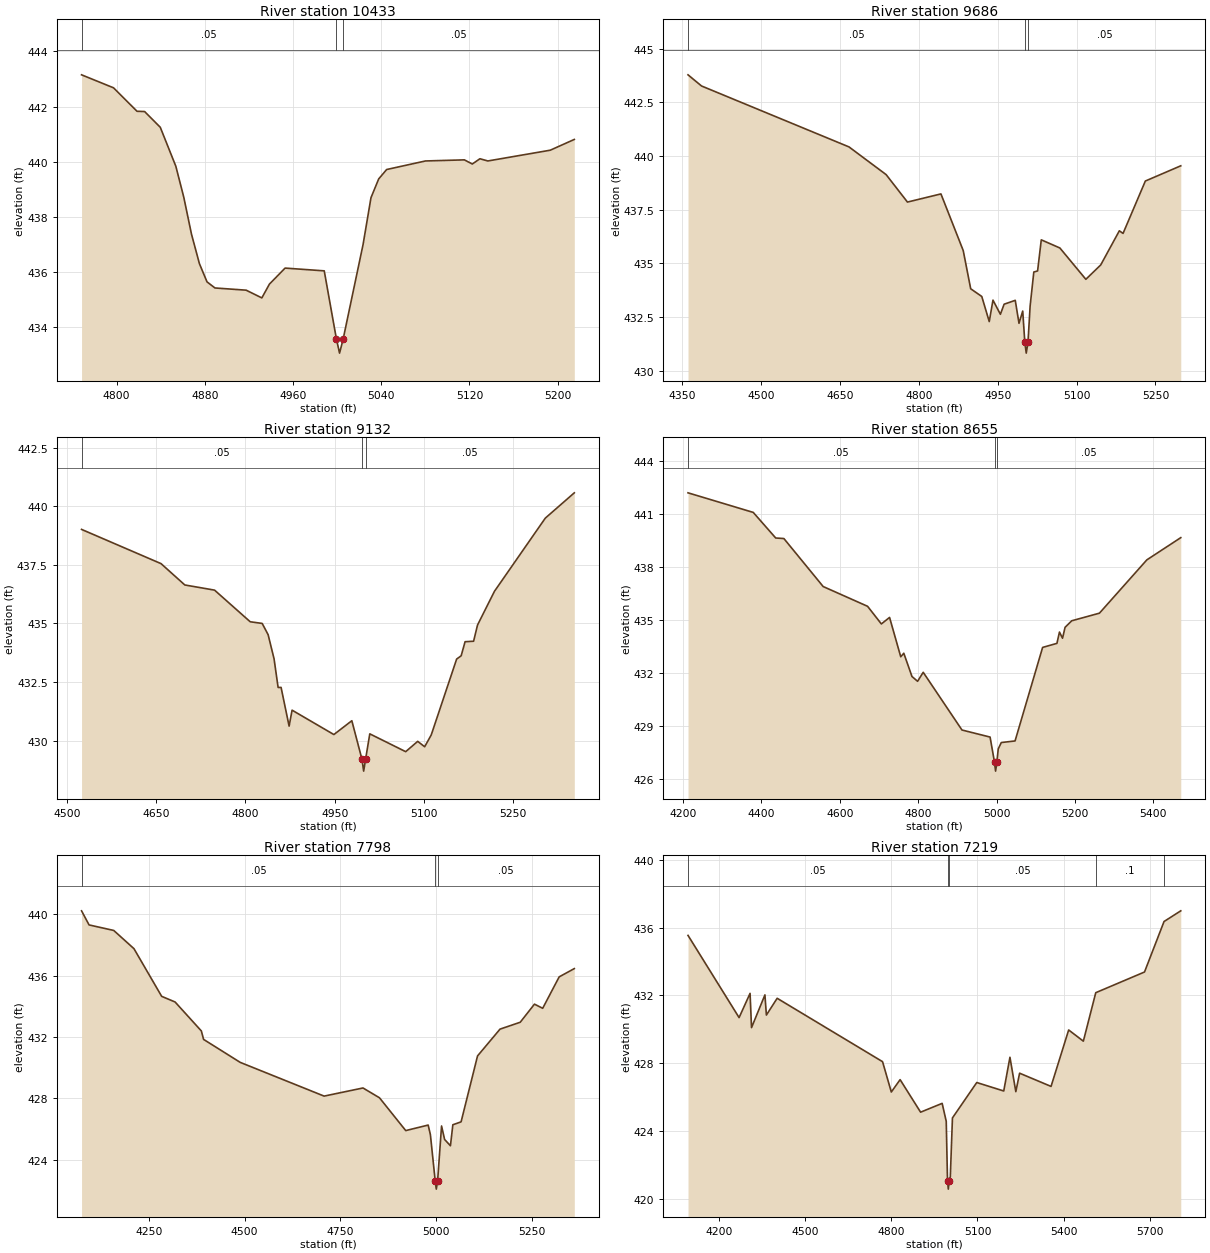
Type RM Length L Ch R = 1,10433,747,747,747
BEGIN DESCRIPTION:
UNT0507 IN SAND CR 1.0
END DESCRIPTION:
XS GIS Cut Line= 2
      3474533.96     10525610.83      3474223.21     10525289.66
#Sta/Elev= 30
  4768.2  443.15  4797.2  442.68  4818.5  441.83  4825.4  441.82  4839.6  441.25
  4853.7  439.84  4860.9  438.72  4867.9  437.38  4875.1  436.31  4882.0  435.65
  4889.2  435.43  4917.5  435.35  4931.7  435.07  4938.6  435.57  4952.8  436.15
  4988.3  436.05  4999.4  433.57  5002.2  433.07  5005.4  433.57  5023.5  437.00
  5030.7  438.70  5037.7  439.38  5044.9  439.72  5080.1  440.03  5115.4  440.07
  5122.6  439.92  5129.5  440.11  5136.7  440.03  5193.3  440.42  5215.1  440.81
#Mann=3,-1,0
  4768.2    0.05       0  4999.4   0.035       0  5005.4    0.05       0
Bank Sta=4999.4,5005.4
Exp/Cntr=0.3,0.1

Type RM Length L Ch R = 1,9686,554,554,554
BEGIN DESCRIPTION:
UNT0092 IN SAND CR 7.0
END DESCRIPTION:
XS GIS Cut Line= 3
      3474895.97     10525577.27      3474921.20     10525204.14
      3474520.13     10524808.29
#Sta/Elev= 30
  4360.7  443.78  4386.4  443.26  4667.0  440.42  4737.6  439.13  4778.2  437.85
  4841.9  438.23  4884.3  435.59  4898.5  433.81  4919.6  433.45  4933.8  432.28
  4940.9  433.28  4955.0  432.62  4962.1  433.09  4983.3  433.27  4990.4  432.20
  4997.5  432.77  5001.5  431.31  5004.2  430.81  5007.5  431.31  5011.6  433.01
  5018.6  434.59  5025.8  434.64  5032.8  436.09  5068.2  435.71  5117.6  434.25
  5145.9  434.92  5181.3  436.51  5188.4  436.39  5230.8  438.83  5298.2  439.54
#Mann=3,-1,0
  4360.7    0.05       0  5001.5   0.035       0  5007.5    0.05       0
Bank Sta=5001.5,5007.5
Exp/Cntr=0.3,0.1

Type RM Length L Ch R = 1,9132,477,477,477
BEGIN DESCRIPTION:
UNT0092 IN SAND CR 10.0
END DESCRIPTION:
XS GIS Cut Line= 4
      3475057.27     10525215.30      3475049.07     10524882.99
      3475020.81     10524642.36      3474828.61     10524476.14
#Sta/Elev= 30
  4524.3  439.01  4658.0  437.55  4698.0  436.64  4748.0  436.42  4808.0  435.07
  4828.1  435.00  4838.1  434.52  4848.1  433.49  4854.9  432.27  4859.9  432.27
  4873.4  430.62  4878.4  431.30  4948.7  430.26  4978.9  430.85  4996.0  429.20
  4998.8  428.70  5002.0  429.20  5009.1  430.29  5069.5  429.53  5089.7  429.97
  5101.4  429.74  5112.4  430.24  5155.2  433.48  5162.8  433.62  5169.4  434.22
  5183.7  434.24  5190.3  434.93  5218.8  436.37  5304.3  439.49  5353.1  440.57
#Mann=3,-1,0
  4524.3    0.05       0  4996.0   0.035       0  5002.0    0.05       0
Bank Sta=4996,5002
Exp/Cntr=0.3,0.1

Type RM Length L Ch R = 1,8655,857,857,857
BEGIN DESCRIPTION:
UNT0092 IN SAND CR 11.0
END DESCRIPTION:
XS GIS Cut Line= 3
      3475791.67     10525126.77      3475171.85     10524381.95
      3474886.24     10524418.30
#Sta/Elev= 30
  4212.9  442.22  4379.3  441.11  4436.6  439.66  4457.4  439.63  4557.6  436.91
  4670.9  435.79  4706.1  434.79  4727.0  435.16  4755.5  432.93  4763.3  433.13
  4784.2  431.81  4798.5  431.54  4812.8  432.05  4911.7  428.78  4983.4  428.38
  4994.7  426.95  4997.4  426.45  5000.7  426.95  5004.2  427.71  5012.0  428.07
  5047.1  428.16  5117.4  433.46  5153.9  433.69  5160.4  434.33  5168.2  433.98
  5174.7  434.60  5191.7  434.97  5262.3  435.40  5383.2  438.42  5469.8  439.68
#Mann=3,-1,0
  4212.9    0.05       0  4994.7   0.035       0  5000.7    0.05       0
Bank Sta=4994.7,5000.7
Exp/Cntr=0.3,0.1

Type RM Length L Ch R = 1,7798,579,579,579
BEGIN DESCRIPTION:
UNT0092 IN SAND CR 9.0
END DESCRIPTION:
XS GIS Cut Line= 2
      3475947.90     10524631.97      3475296.96     10523522.77
#Sta/Elev= 30
  4074.3  440.23  4093.9  439.31  4158.3  438.95  4211.1  437.76  4283.4  434.65
  4318.5  434.28  4387.0  432.39  4392.8  431.84  4488.5  430.34  4707.4  428.14
  4808.9  428.67  4851.9  428.03  4920.4  425.89  4979.0  426.25  4984.8  425.62
  4997.5  422.57  5000.2  422.07  5003.5  422.57  5013.9  426.19  5021.9  425.31
  5037.1  424.90  5043.4  426.27  5064.9  426.46  5107.8  430.76  5166.5  432.51
  5219.3  432.96  5256.4  434.14  5277.9  433.87  5320.9  435.92  5360.4  436.46
#Mann=3,-1,0
  4074.3    0.05       0  4997.5   0.035       0  5003.5    0.05       0
Bank Sta=4997.5,5003.5
Exp/Cntr=0.3,0.1

Type RM Length L Ch R = 1,7219,52,52,52
BEGIN DESCRIPTION:
UNT0092 IN SAND CR 8.1
END DESCRIPTION:
XS GIS Cut Line= 4
      3475988.67     10524406.14      3475823.73     10523555.43
      3475715.23     10523455.60      3475571.99     10522769.80
#Sta/Elev= 30
  4092.8  435.54  4270.5  430.69  4308.7  432.12  4313.8  430.10  4360.4  432.03
  4365.5  430.84  4403.0  431.83  4769.7  428.09  4800.2  426.30  4830.8  427.03
  4902.1  425.11  4977.1  425.63  4991.3  424.57  4995.7  421.07  4998.5  420.57
  5001.7  421.07  5005.5  421.30  5012.9  424.77  5097.5  426.86  5191.4  426.36
  5213.0  428.35  5233.4  426.32  5246.6  427.41  5356.0  426.63  5417.3  429.96
  5468.4  429.30  5511.6  432.16  5681.2  433.38  5749.2  436.36  5807.4  436.99
#Mann=5,-1,0
  4092.8    0.05       0  4995.7   0.035       0  5001.7    0.05       0
  5511.6     0.1       0  5749.2    0.05       0
Bank Sta=4995.7,5001.7
Exp/Cntr=0.3,0.1

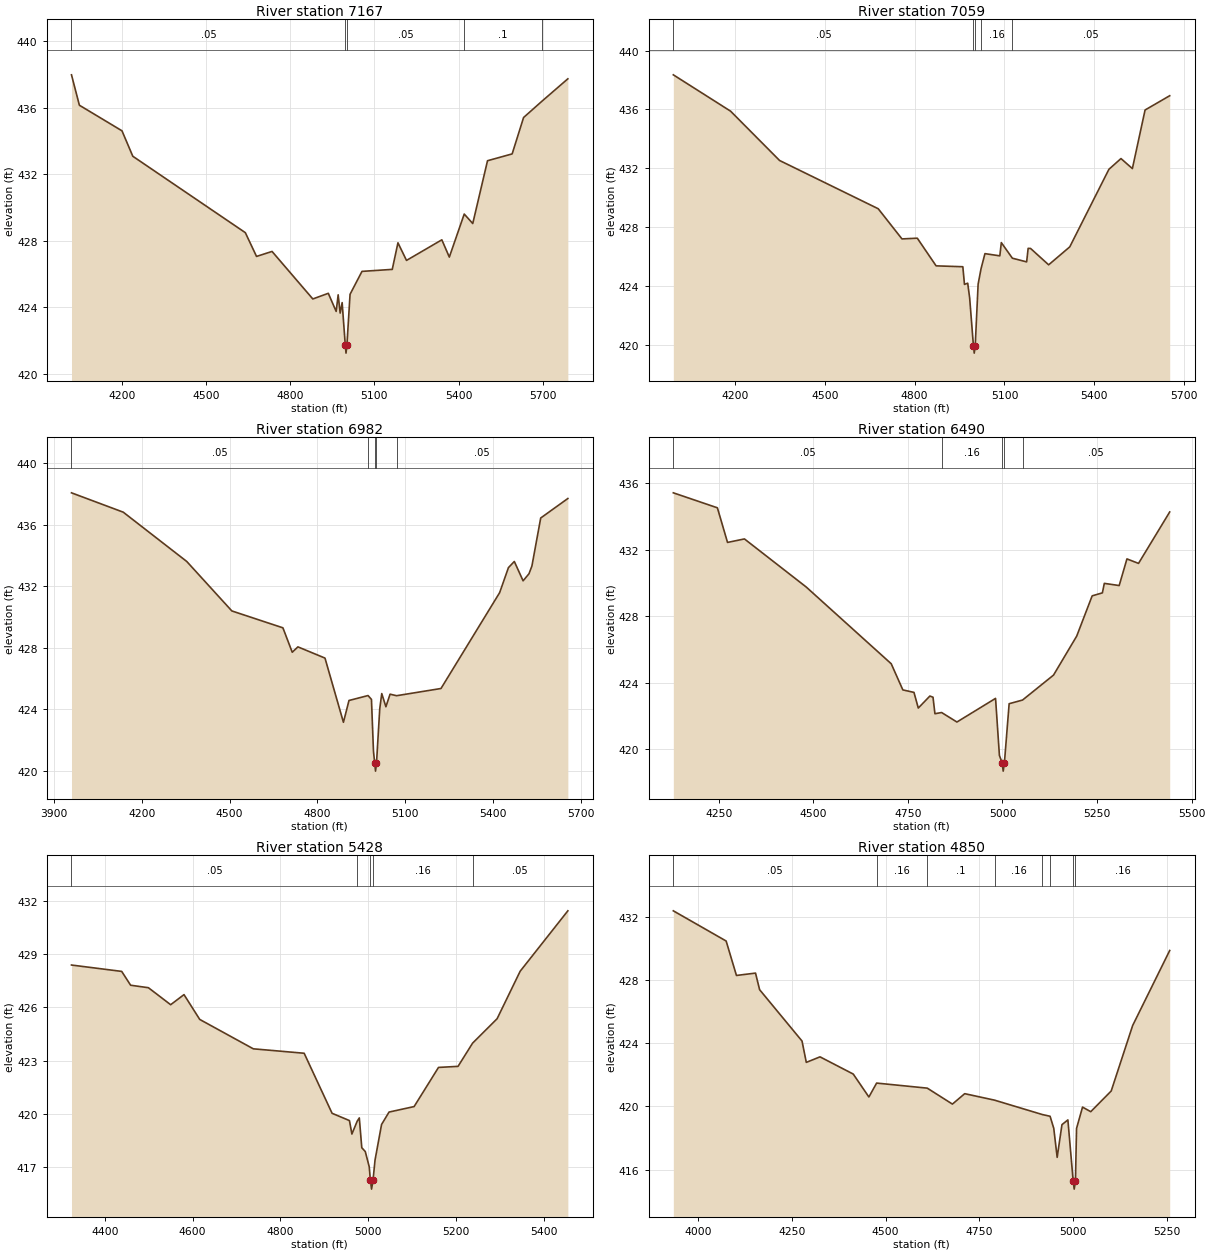
Type RM Length L Ch R = 1,7167,108,108,108
BEGIN DESCRIPTION:
UNT0092 IN SAND CR 8.0
END DESCRIPTION:
XS GIS Cut Line= 4
      3476032.07     10524427.86      3475841.09     10523507.68
      3475754.29     10523420.88      3475624.10     10522726.52
#Sta/Elev= 30
  4020.7  437.98  4048.9  436.15  4200.7  434.61  4239.2  433.08  4640.3  428.48
  4680.2  427.05  4735.5  427.35  4880.8  424.49  4936.0  424.83  4964.0  423.74
  4971.1  424.74  4978.2  423.64  4985.3  424.27  4996.4  421.73  4999.1  421.23
  5002.4  421.73  5013.5  424.77  5056.0  426.15  5163.9  426.27  5184.2  427.87
  5214.7  426.81  5340.6  428.05  5367.3  427.01  5420.4  429.60  5450.8  429.03
  5503.4  432.81  5591.2  433.22  5631.9  435.41  5696.6  436.38  5789.7  437.74
#Mann=5,-1,0
  4020.7    0.05       0  4996.4   0.035       0  5002.4    0.05       0
  5420.4     0.1       0  5696.6    0.05       0
Bank Sta=4996.4,5002.4
Exp/Cntr=0.3,0.1

Type RM Length L Ch R = 1,7059,77,77,77
BEGIN DESCRIPTION:
UNT0092 IN SAND CR 6.1
END DESCRIPTION:
XS GIS Cut Line= 4
      3476118.88     10524388.79      3475927.90     10523490.32
      3475858.46     10523342.75      3475793.36     10522769.87
#Sta/Elev= 30
  3993.9  438.35  4185.2  435.88  4348.8  432.53  4678.4  429.25  4757.7  427.20
  4808.9  427.25  4871.7  425.37  4961.0  425.31  4966.5  424.11  4977.3  424.19
  4983.8  423.19  4996.4  419.94  4999.1  419.44  5002.4  419.94  5012.1  424.13
  5021.9  425.18  5034.9  426.20  5084.6  426.05  5089.6  426.95  5126.5  425.89
  5174.2  425.64  5179.2  426.56  5187.4  426.55  5247.7  425.44  5318.2  426.66
  5449.0  431.93  5489.3  432.66  5527.4  431.98  5569.8  435.96  5652.1  436.93
#Mann=5,-1,0
  3993.9    0.05       0  4996.4   0.035       0  5002.4    0.05       0
  5021.9    0.16       0  5126.5    0.05       0
Bank Sta=4996.4,5002.4
Exp/Cntr=0.3,0.1

Type RM Length L Ch R = 1,6982,492,492,492
BEGIN DESCRIPTION:
UNT0092 IN SAND CR 6.2
END DESCRIPTION:
XS GIS Cut Line= 4
      3476188.32     10524345.39      3475962.62     10523381.81
      3475880.16     10523295.01      3475836.76     10522709.10
#Sta/Elev= 30
  3959.7  438.09  4136.7  436.83  4353.8  433.62  4507.9  430.40  4682.5  429.30
  4714.4  427.71  4733.8  428.06  4826.3  427.33  4889.4  423.15  4908.4  424.57
  4973.5  424.89  4985.2  424.64  4992.1  421.26  4996.4  420.47  4999.1  419.97
  5002.4  420.47  5013.5  424.02  5020.4  425.02  5034.6  424.16  5048.8  424.98
  5071.0  424.88  5222.9  425.35  5423.4  431.59  5453.5  433.22  5473.6  433.62
  5503.6  432.36  5523.7  432.82  5533.7  433.32  5563.8  436.45  5656.6  437.72
#Mann=5,-1,0
  3959.7    0.05       0  4973.5    0.16       0  4996.4    0.07       0
  5002.4    0.16       0  5071.0    0.05       0
Bank Sta=4996.4,5002.4
Exp/Cntr=0.3,0.1

Type RM Length L Ch R = 1,6490,1062,1062,1062
BEGIN DESCRIPTION:
UNT0092 IN SAND CR 6.0
END DESCRIPTION:
XS GIS Cut Line= 2
      3476366.26     10523915.63      3476101.51     10522630.93
#Sta/Elev= 30
  4130.3  435.42  4246.7  434.52  4273.5  432.44  4318.2  432.65  4481.5  429.76
  4706.1  425.15  4736.8  423.58  4766.2  423.43  4777.6  422.49  4808.2  423.21
  4816.5  423.14  4821.6  422.15  4839.3  422.22  4879.7  421.65  4981.8  423.07
  4992.0  419.64  4999.2  419.20  5002.0  418.70  5005.2  419.20  5017.7  422.75
  5053.1  422.97  5135.0  424.47  5196.2  426.81  5237.1  429.23  5264.1  429.41
  5269.2  429.98  5308.5  429.85  5329.0  431.45  5359.6  431.18  5442.0  434.27
#Mann=5,-1,0
  4130.3    0.05       0  4839.3    0.16       0  4999.2    0.07       0
  5005.2    0.16       0  5053.1    0.05       0
Bank Sta=4999.2,5005.2
Exp/Cntr=0.3,0.1

Type RM Length L Ch R = 1,5428,578,578,578
BEGIN DESCRIPTION:
UNT0092 IN SAND CR 5.0
END DESCRIPTION:
XS GIS Cut Line= 3
      3476934.85     10523594.49      3476839.36     10523017.23
      3476600.63     10522526.75
#Sta/Elev= 30
  4324.1  428.39  4438.5  428.03  4458.8  427.25  4499.3  427.11  4550.0  426.15
  4580.4  426.72  4616.2  425.32  4738.3  423.66  4854.1  423.41  4917.7  420.02
  4957.2  419.61  4962.8  418.85  4974.8  419.57  4979.7  419.76  4985.3  418.08
  4993.3  417.86  5002.3  417.00  5004.9  416.24  5007.6  415.74  5010.9  416.24
  5015.5  417.38  5030.4  419.39  5047.4  420.09  5104.5  420.40  5160.1  422.61
  5204.6  422.67  5237.7  423.98  5293.6  425.36  5346.1  428.04  5454.7  431.45
#Mann=5,-1,0
  4324.1    0.05       0  4974.8    0.16       0  5004.9    0.07       0
  5010.9    0.16       0  5237.7    0.05       0
Bank Sta=5004.9,5010.9
Exp/Cntr=0.3,0.1

Type RM Length L Ch R = 1,4850,818,818,818
BEGIN DESCRIPTION:
UNT0092 IN SAND CR 4.0
END DESCRIPTION:
XS GIS Cut Line= 3
      3477499.98     10523715.30      3477270.81     10522772.57
      3477124.97     10522449.66
#Sta/Elev= 30
  3933.6  432.37  4074.5  430.46  4102.0  428.28  4152.9  428.43  4163.8  427.38
  4277.0  424.13  4288.4  422.78  4325.0  423.13  4413.7  422.04  4455.4  420.59
  4476.0  421.47  4611.2  421.15  4678.3  420.14  4711.1  420.80  4790.7  420.39
  4918.1  419.48  4938.9  419.37  4948.7  418.61  4957.8  416.77  4970.6  418.84
  4986.4  419.14  5000.6  415.26  5003.3  414.76  5006.6  415.26  5009.5  418.60
  5025.5  419.95  5047.4  419.66  5102.0  420.97  5159.2  425.11  5258.1  429.86
#Mann=8,-1,0
  3933.6    0.05       0  4476.0    0.16       0  4611.2     0.1       0
  4790.7    0.16       0  4918.1    0.12       0  4938.9    0.16       0
  5000.6    0.07       0  5006.6    0.16       0
Bank Sta=5000.6,5006.6
Exp/Cntr=0.3,0.1

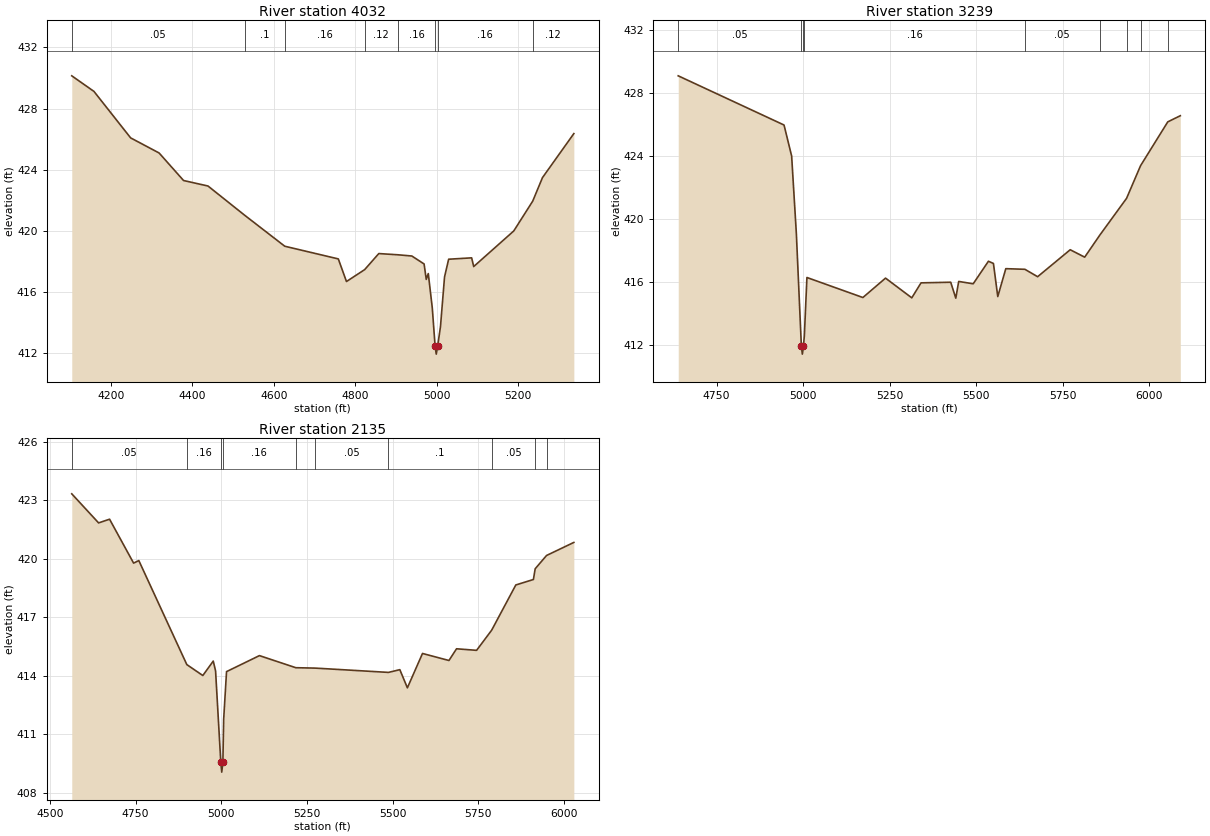
Type RM Length L Ch R = 1,4032,793,793,793
BEGIN DESCRIPTION:
UNT0092 IN SAND CR 3.0
END DESCRIPTION:
XS GIS Cut Line= 4
      3477702.84     10523496.17      3477703.10     10522782.99
      3477729.14     10522491.32      3477615.51     10522295.05
#Sta/Elev= 30
  4104.0  430.14  4158.5  429.12  4248.5  426.08  4318.5  425.09  4378.5  423.29
  4438.5  422.93  4528.9  421.01  4627.0  418.99  4758.5  418.16  4778.5  416.68
  4823.2  417.46  4857.9  418.51  4904.9  418.43  4939.0  418.35  4969.1  417.83
  4974.4  416.82  4979.4  417.20  4989.2  414.96  4996.2  412.43  4999.0  411.93
  5002.2  412.43  5009.3  413.72  5019.3  416.98  5029.4  418.14  5085.9  418.23
  5090.9  417.66  5189.3  419.99  5235.8  421.94  5259.8  423.48  5336.8  426.36
#Mann=8,-1,0
  4104.0    0.05       0  4528.9     0.1       0  4627.0    0.16       0
  4823.2    0.12       0  4904.9    0.16       0  4996.2    0.07       0
  5002.2    0.16       0  5235.8    0.12       0
Bank Sta=4996.2,5002.2
Exp/Cntr=0.3,0.1

Type RM Length L Ch R = 1,3239,1104,1104,1104
BEGIN DESCRIPTION:
UNT0092 IN SAND CR 2.0
END DESCRIPTION:
XS GIS Cut Line= 4
      3478145.81     10523189.22      3478354.14     10522736.11
      3478265.60     10522574.66      3477646.47     10522122.01
#Sta/Elev= 30
  4639.5  429.07  4945.0  425.95  4967.0  423.98  4980.6  419.06  4995.1  411.92
  4997.9  411.42  5001.1  411.92  5003.7  412.59  5011.1  416.28  5172.7  415.01
  5238.1  416.24  5313.9  414.99  5340.6  415.94  5426.3  415.98  5441.0  414.97
  5449.4  416.03  5491.2  415.88  5535.2  417.31  5549.7  417.17  5562.2  415.07
  5585.4  416.84  5640.5  416.80  5677.3  416.33  5771.4  418.04  5813.2  417.57
  5856.6  418.96  5934.1  421.30  5974.5  423.37  6053.1  426.15  6089.3  426.54
#Mann=9,-1,0
  4639.5    0.05       0  4995.1   0.035       0  5001.1    0.05       0
  5003.7    0.16       0  5640.5    0.05       0  5856.6    0.16       0
  5934.1    0.12       0  5974.5    0.16       0  6053.1     0.1       0
Bank Sta=4995.1,5001.1
Exp/Cntr=0.3,0.1

Type RM Length L Ch R = 1,2135,0,0,0
BEGIN DESCRIPTION:
UNT0092 IN SAND CR 1.0
END DESCRIPTION:
XS GIS Cut Line= 3
      3478940.05     10522735.11      3478710.02     10522114.45
      3477981.61     10521776.26
#Sta/Elev= 30
  4563.9  423.33  4642.2  421.84  4674.2  422.03  4744.3  419.78  4759.6  419.91
  4899.6  414.58  4946.3  414.02  4976.7  414.76  4983.5  414.26  4998.8  409.57
  5001.5  409.07  5004.8  409.57  5007.1  411.77  5015.5  414.22  5111.5  415.04
  5217.7  414.42  5273.9  414.40  5487.9  414.18  5521.2  414.32  5543.2  413.39
  5587.3  415.15  5664.5  414.79  5686.6  415.39  5745.1  415.31  5789.0  416.34
  5859.6  418.66  5910.9  418.94  5916.1  419.49  5949.2  420.17  6028.9  420.84
#Mann=10,-1,0
  4563.9    0.05       0  4899.6    0.16       0  4998.8    0.07       0
  5004.8    0.16       0  5217.7     0.1       0  5273.9    0.05       0
  5487.9     0.1       0  5789.0    0.05       0  5916.1    0.12       0
  5949.2    0.05       0
Bank Sta=4998.8,5004.8
Exp/Cntr=0.3,0.1

Chan Stop Cuts=-1