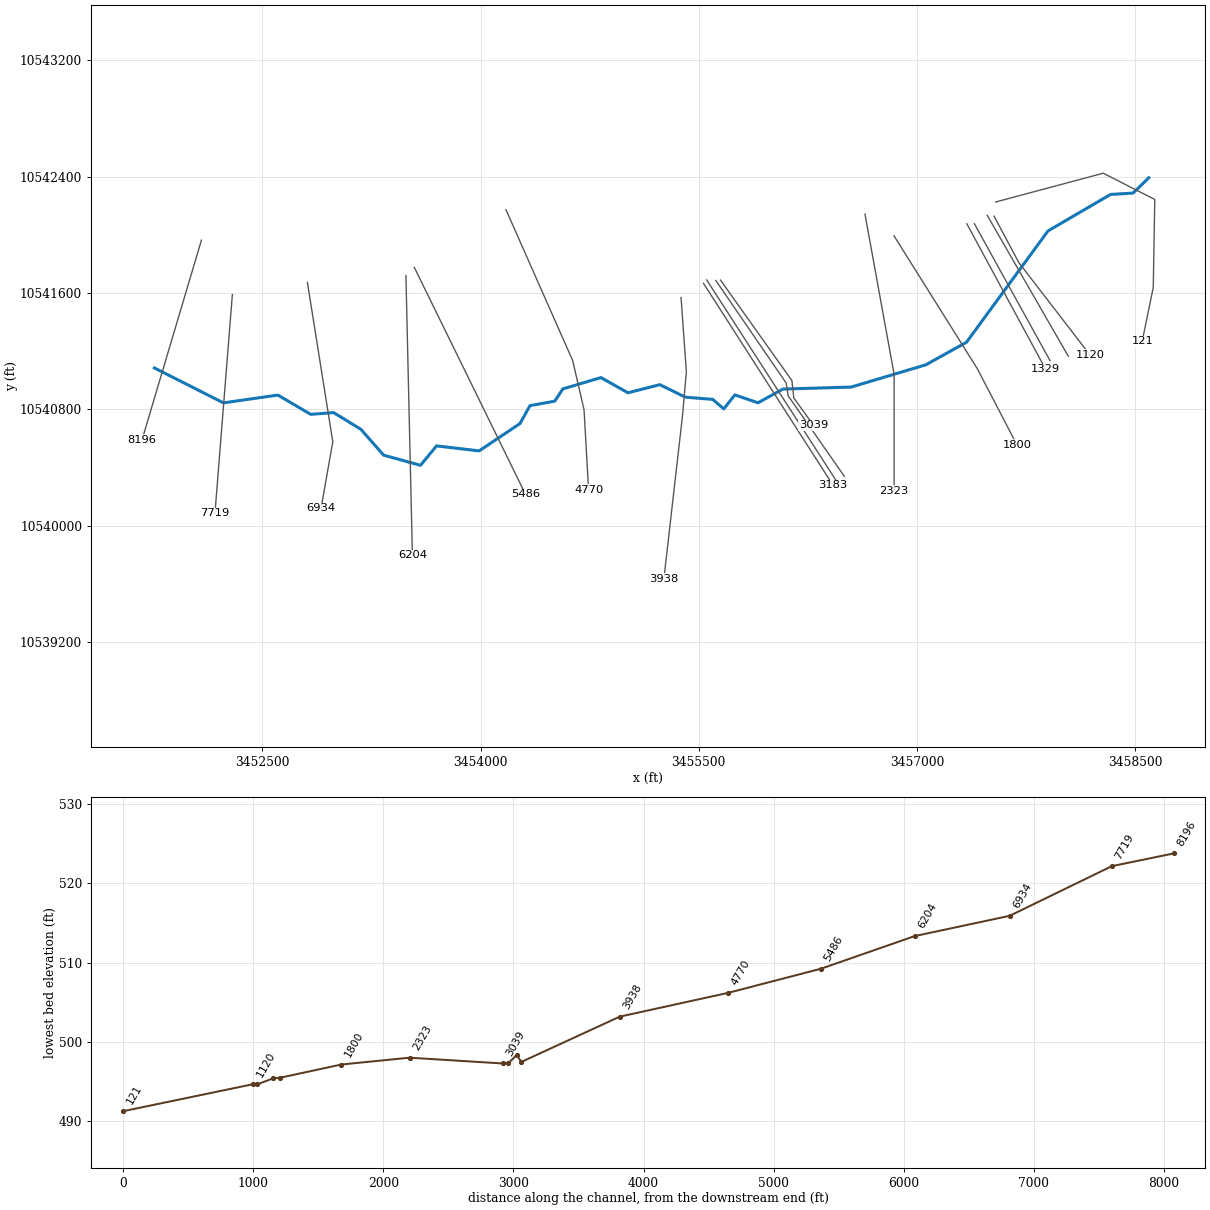
--- UNT0093 IN SAND CR.prj (project) ---

Proj Title=UNT0093 IN SAND CR Base Level Engineering
Current Plan=p01
Default Exp/Contr=0.3,0.1
English Units
Geom File=g01
Flow File=f01
Plan File=p01
Y Axis Title=Elevation
X Axis Title(PF)=Main Channel Distance
X Axis Title(XS)=Station
BEGIN DESCRIPTION:
UNT0093 IN SAND CR
END DESCRIPTION:
DSS Export Rating Curves= 0
DSS Export Rating Curve Sorted= 0
DSS Export Volume Flow Curves= 0
DXF OffsetX= 0
DXF OffsetY= 0
DXF ScaleX= 1
DXF ScaleY= 10

--- UNT0093 IN SAND CR.p01 (plan) ---

Plan Title=Multiple Run
Short Identifier=Multiple
Geom File=g01
Flow File=f01
Subcritical Flow
K Sum by GR= 0
Std Step Tol= 0.01
Critical Tol= 0.01
Num of Std Step Trials= 20
Max Error Tol= 0.3
Flow Tol Ratio= 0.001
Split Flow NTrial= 30
Split Flow Tol= 0.02
Split Flow Ratio= 0.02
Log Output Level= 0
Friction Slope Method= 1
Unsteady Friction Slope Method= 2
Unsteady Bridges Friction Slope Method= 1
Parabolic Critical Depth
Global Vel Dist=  1 , 1 , 1
Global Log Level= 0
CheckData=True
Encroach Param= -1, 0, 0, 0
BEGIN DESCRIPTION:
Multiple Run
END DESCRIPTION:

--- UNT0093 IN SAND CR.f01 (steady flow) ---

Flow Title=Multiple
Number of Profiles=7
Profile Names=10-year,25-year,50-year,1pct_min,100-year,1pct_plu,500-year
River Rch & RM= UNT0093 IN SAND ,Reach-1,8196
    1059    1459    1789    1600    2164    2926    3158
River Rch & RM= UNT0093 IN SAND ,Reach-1,121
    1957    2773    3465    3151    4261    5763    6431
Boundary for River Rch & Prof#=UNT0093 IN SAND ,Reach-1,1
Up Type=0
Dn Type=3
Dn Slope=0.005
Boundary for River Rch & Prof#=UNT0093 IN SAND ,Reach-1,2
Up Type=0
Dn Type=3
Dn Slope=0.005
Boundary for River Rch & Prof#=UNT0093 IN SAND ,Reach-1,3
Up Type=0
Dn Type=3
Dn Slope=0.005
Boundary for River Rch & Prof#=UNT0093 IN SAND ,Reach-1,4
Up Type=0
Dn Type=3
Dn Slope=0.005
Boundary for River Rch & Prof#=UNT0093 IN SAND ,Reach-1,5
Up Type=0
Dn Type=3
Dn Slope=0.005
Boundary for River Rch & Prof#=UNT0093 IN SAND ,Reach-1,6
Up Type=0
Dn Type=3
Dn Slope=0.005
Boundary for River Rch & Prof#=UNT0093 IN SAND ,Reach-1,7
Up Type=0
Dn Type=3
Dn Slope=0.005

--- UNT0093 IN SAND CR.g01 (geometry) ---

Geom Title=Existing Conditions
Program Version=4.10

River Reach=UNT0093 IN SAND ,Reach-1
Reach XY= 30
      3451759.27     10541084.75      3452233.53     10540845.23
      3452607.81     10540898.48      3452832.97     10540766.35
      3452990.68     10540778.19      3453177.79     10540663.45
      3453334.25     10540485.82      3453587.56     10540415.78
      3453698.01     10540549.57      3453990.49     10540515.02
      3454271.24     10540702.75      3454339.74     10540825.98
      3454510.59     10540856.93      3454565.49     10540940.87
      3454827.72     10541018.77      3455013.32     10540914.28
      3455232.13     10540970.15      3455408.57     10540883.96
      3455595.48     10540869.16      3455671.88     10540803.61
      3455747.74     10540899.83      3455907.01     10540845.63
      3456078.07     10540939.88      3456546.59     10540953.53
       3457059.7      10541106.4      3457339.61     10541261.61
      3457899.62     10542026.62      3458329.28     10542277.16
      3458484.56     10542286.93      3458592.11     10542391.64

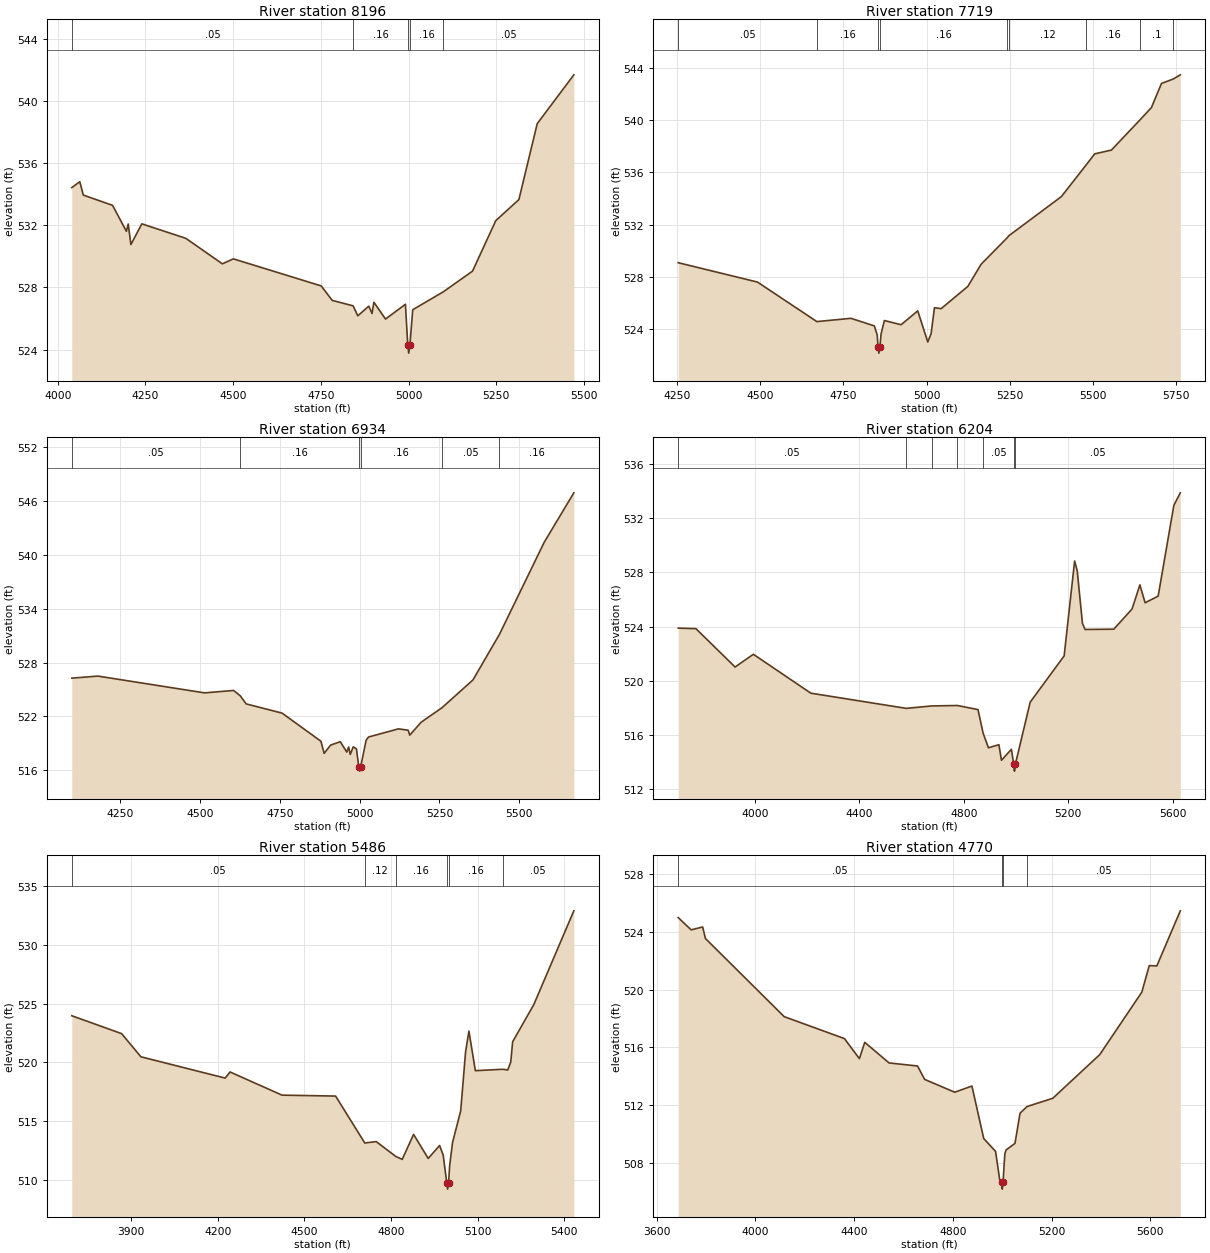
Type RM Length L Ch R = 1 ,8196    ,477,477,477
BEGIN DESCRIPTION:
UNT0093 IN SAND CR 16.0
END DESCRIPTION:
XS GIS Cut Line= 2
      3452082.29     10541963.13      3451674.28     10540591.53
#Sta/Elev= 30
  4039.9  534.42  4062.8   534.8  4072.8  533.94  4156.2  533.28  4195.6  531.61
  4200.8  532.08  4208.4  530.76  4239.7  532.09  4364.9  531.16  4469.2  529.52
  4500.5  529.84  4750.9   528.1  4782.2  527.17  4841.8  526.82  4855.2  526.18
  4886.5   526.8  4895.8  526.33    4901  527.05  4934.2  525.97  4990.9  526.92
  4997.6  524.28  5000.3  523.78  5003.6  524.28  5011.7  526.57  5098.8  527.72
  5182.1  529.05  5248.5   532.3  5314.3  533.65  5366.5  538.53  5470.9  541.67
#Mann= 5 ,-1 , 0
  4039.9     .05       0  4841.8     .16       0  4997.6     .07       0
  5003.6     .16       0  5098.8     .05       0
Bank Sta=4997.6,5003.6
XS Rating Curve= 0 ,0
Exp/Cntr=0.3,0.1

Type RM Length L Ch R = 1 ,7719    ,785,785,785
BEGIN DESCRIPTION:
UNT0093 IN SAND CR 15.0
END DESCRIPTION:
XS GIS Cut Line= 2
      3452294.84     10541589.11      3452175.16     10540085.26
#Sta/Elev= 30
  4253.6  529.08  4491.8   527.6  4670.1  524.58  4772.7  524.83  4842.9  524.25
  4851.6  523.55  4853.7  522.67  4856.4  522.17  4859.7  522.67    4863  523.62
    4873  524.66  4923.2  524.34  4973.3   525.4  5003.4  523.02  5013.5  523.67
  5023.5  525.64  5043.6  525.57  5123.8  527.27  5163.9  528.97  5242.2  530.99
  5247.4  531.15  5404.7  534.13  5478.9  536.54    5505   537.4  5555.2  537.69
  5642.3  540.03  5675.5  540.94  5705.6  542.78    5741  543.12  5762.2  543.44
#Mann= 9 ,-1 , 0
  4253.6     .05       0  4670.1     .16       0  4853.7     .07       0
  4859.7     .16       0  5242.2     .05       0  5247.4     .12       0
  5478.9     .16       0  5642.3      .1       0    5741     .16       0
Bank Sta=4853.7,4859.7
XS Rating Curve= 0 ,0
Exp/Cntr=0.3,0.1

Type RM Length L Ch R = 1 ,6934    ,730,730,730
BEGIN DESCRIPTION:
UNT0093 IN SAND CR 13.0
END DESCRIPTION:
XS GIS Cut Line= 3
      3452810.47     10541672.49      3452984.98      10540577.4
      3452904.22     10540120.39
#Sta/Elev= 30
  4098.1  526.26    4180  526.49  4514.1  524.62  4605.3  524.89    4626  524.29
  4644.7  523.39  4757.2  522.36  4878.7  519.23  4888.8  517.88  4909.1   518.8
  4939.4  519.18  4959.7  518.02  4965.5  518.59  4970.6  517.76  4979.9   518.6
  4990.1  518.38  4997.2   516.4  4999.9   515.9  5003.2   516.4  5020.4  519.35
  5027.7   519.7  5121.7  520.61    5152  520.46  5157.1  519.91  5192.6  521.35
  5257.9  522.96    5355  526.06  5437.9  531.13  5578.4  541.41  5671.1  546.91
#Mann= 6 ,-1 , 0
  4098.1     .05       0    4626     .16       0  4997.2     .07       0
  5003.2     .16       0  5257.9     .05       0  5437.9     .16       0
Bank Sta=4997.2,5003.2
XS Rating Curve= 0 ,0
Exp/Cntr=0.3,0.1

Type RM Length L Ch R = 1 ,6204    ,718,718,718
BEGIN DESCRIPTION:
UNT0093 IN SAND CR 12.0
END DESCRIPTION:
XS GIS Cut Line= 2
      3453487.55     10541719.39      3453531.99      10539796.9
#Sta/Elev= 30
  3706.6  523.89  3774.4  523.85  3924.4  521.02  3994.4  521.96  4214.5  519.09
  4580.1  517.97  4678.1  518.15  4776.1  518.18  4854.7  517.88  4874.2  516.15
  4894.7  515.06  4934.7  515.29  4944.7  514.14  4982.6  514.95  4991.7  513.84
  4994.4  513.34  4997.7  513.84  5054.7  518.43  5184.7  521.84  5224.8  528.84
  5234.8  528.12  5254.8  524.24  5264.8  523.79  5374.8  523.81  5444.8   525.3
  5474.8  527.08  5494.8  525.76  5544.8  526.25  5604.9  532.95  5629.6  533.87
#Mann= 7 ,-1 , 0
  3706.6     .05       0  4580.1     .16       0  4678.1     .12       0
  4776.1     .16       0  4874.2     .05       0  4991.7    .035       0
  4997.7     .05       0
Bank Sta=4991.7,4997.7
XS Rating Curve= 0 ,0
Exp/Cntr=0.3,0.1

Type RM Length L Ch R = 1 ,5486    ,716,716,716
BEGIN DESCRIPTION:
UNT0093 IN SAND CR 11.0
END DESCRIPTION:
XS GIS Cut Line= 2
      3453544.83     10541776.66      3454309.84     10540215.41
#Sta/Elev= 30
  3694.1  523.97  3866.7  522.45  3933.5  520.48  4225.3  518.67  4242.2  519.19
  4422.2  517.22  4607.8  517.14  4708.8  513.15  4748.4  513.27    4816  512.01
  4838.4  511.76  4877.8  513.88  4928.4  511.84  4967.8  512.94  4980.3  512.12
  4992.9  509.73  4995.6  509.23  4998.9  509.73  5002.6  511.22  5012.8  513.21
  5040.9  515.88  5057.8   520.9  5069.4  522.66  5091.7   519.3  5186.1  519.42
  5203.9  519.36  5214.2  520.03  5220.8  521.76  5293.9  524.91  5432.7  532.89
#Mann= 6 ,-1 , 0
  3694.1     .05       0  4708.8     .12       0    4816     .16       0
  4992.9     .07       0  4998.9     .16       0  5186.1     .05       0
Bank Sta=4992.9,4998.9
XS Rating Curve= 0 ,0
Exp/Cntr=0.3,0.1

Type RM Length L Ch R = 1 ,4770    ,832,832,832
BEGIN DESCRIPTION:
UNT0093 IN SAND CR 9.0
END DESCRIPTION:
XS GIS Cut Line= 4
      3454175.06     10542172.46      3454633.39     10541136.01
      3454711.51     10540797.47      3454742.72     10540246.06
#Sta/Elev= 30
    3688     525  3740.3  524.15  3786.9  524.35  3798.2  523.55  4117.1  518.13
    4361  516.61  4421.5  515.22  4443.3  516.35  4541.8  514.92    4657  514.71
  4685.7  513.78  4807.7  512.89  4877.1  513.32    4925  509.68  4972.9  508.79
    4990  506.79  4997.2  506.67    5000  506.17  5003.2  506.67  5010.5  508.61
  5015.7  508.89  5051.5  509.34  5072.1  511.44  5100.9   511.9  5204.6  512.47
  5394.9   515.5  5565.2  519.83  5595.2  521.67  5625.9  521.65    5721  525.47
#Mann= 4 ,-1 , 0
    3688     .05       0  4997.2     .07       0  5003.2     .05       0
  5100.9     .05       0
Bank Sta=4997.2,5003.2
XS Rating Curve= 0 ,0
Exp/Cntr=0.3,0.1

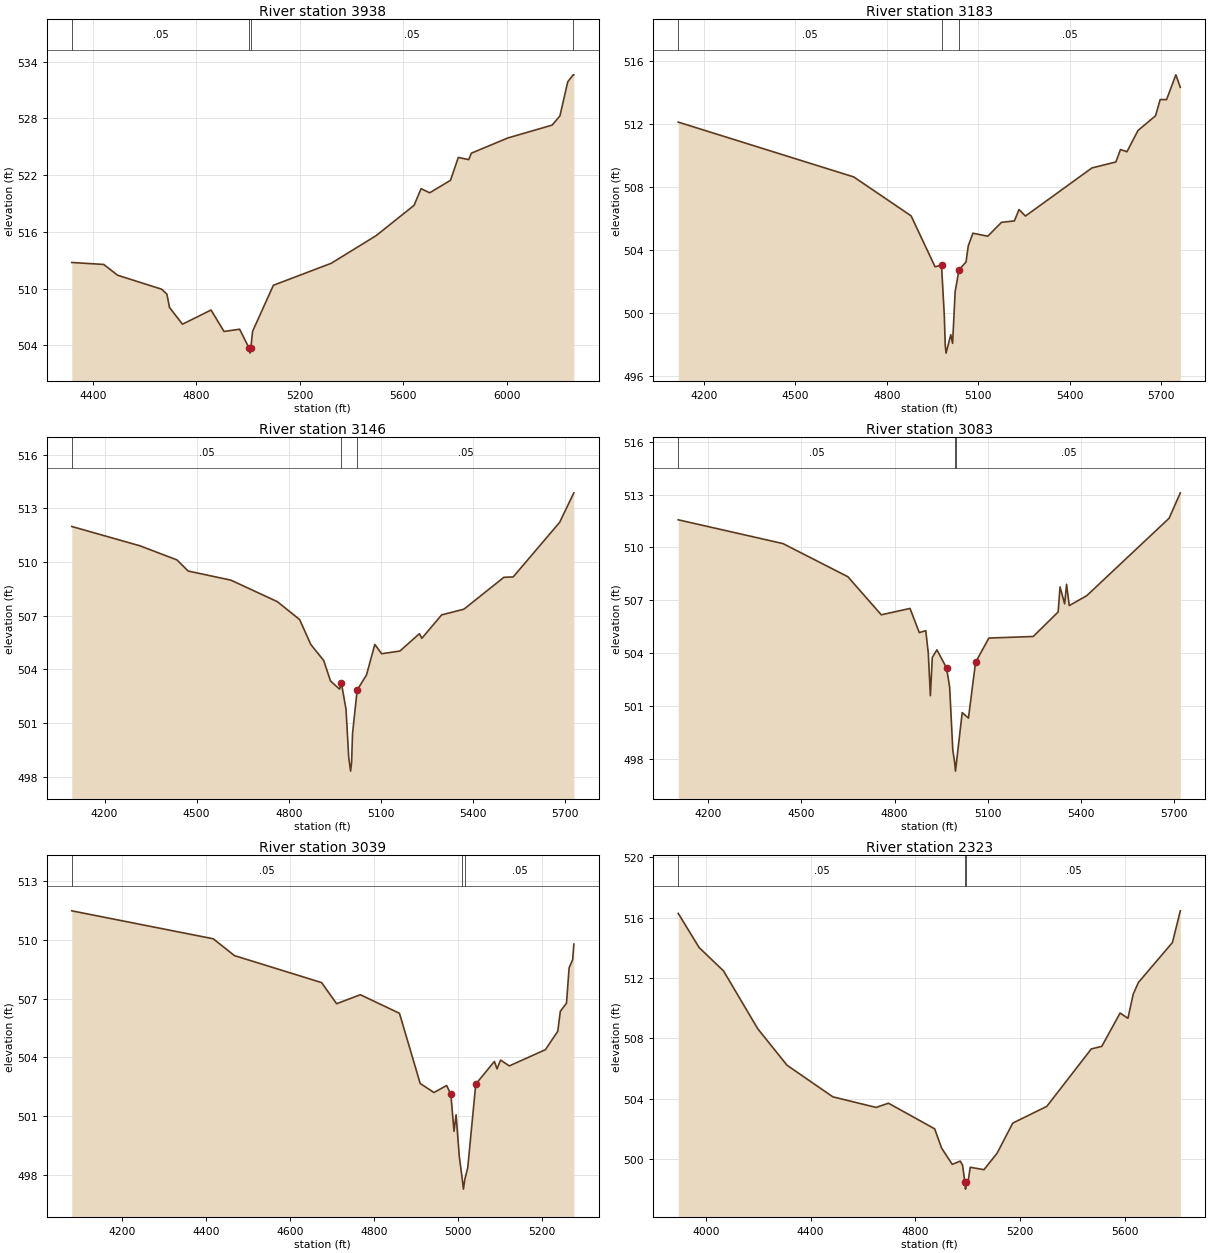
Type RM Length L Ch R = 1 ,3938    ,755,755,755
BEGIN DESCRIPTION:
UNT0093 IN SAND CR 8.0
END DESCRIPTION:
XS GIS Cut Line= 4
      3455378.18     10541568.32      3455414.64     10541057.88
       3455388.6     10540761.01      3455260.44     10539638.15
#Sta/Elev= 30
  4318.8  512.76  4442.4  512.55  4495.9  511.41  4666.4  509.93  4686.4  509.41
  4696.4     508  4746.6  506.23  4856.9  507.73  4907.1  505.46  4967.3   505.7
  5004.5  503.67  5007.2  503.17  5010.5  503.67  5017.5  505.48  5097.8  510.35
  5321.1  512.67  5494.9   515.6  5641.2   518.8  5668.6  520.57  5701.6  520.13
  5782.1  521.45  5812.3  523.87  5852.6  523.64  5862.7  524.32  6003.6  525.93
  6174.7  527.29  6204.9  528.26  6235.1  531.87  6256.1  532.61  6258.7  532.61
#Mann= 4 ,-1 , 0
  4318.8     .05       0  5004.5    .035       0  5010.5     .05       0
  6256.1     .08       0
Bank Sta=5004.5,5010.5
XS Rating Curve= 0 ,0
Exp/Cntr=0.3,0.1

Type RM Length L Ch R = 1 ,3183    ,37,37,37
BEGIN DESCRIPTION:
UNT0093 IN SAND CR 7.1
END DESCRIPTION:
XS GIS Cut Line= 2
      3455532.27     10541666.49      3456422.01     10540279.79
#Sta/Elev= 30
  4115.5  512.12  4691.6  508.64  4879.7  506.17  4958.3  502.94  4979.5  503.04
  4988.6  499.87  4991.7  497.96  4994.4  497.46  5009.9  498.63  5015.8  498.08
  5024.3  501.37    5037  502.76  5059.9  503.24  5067.3  504.27  5082.5  505.07
  5131.2  504.88  5176.4  505.76  5218.6  505.85  5233.8  506.57    5255  506.16
    5473  509.21  5551.6  509.59  5566.8  510.38    5588  510.24  5624.3  511.59
  5681.8  512.52    5697  513.55  5718.1  513.55  5748.5  515.12  5763.1  514.33
#Mann= 3 , 0 , 0
  4115.5     .05       0  4979.5    .035       0    5037     .05       0
Bank Sta=4979.5,5037
XS Rating Curve= 0 ,0
Exp/Cntr=0.3,0.1

Type RM Length L Ch R = 1 ,3146    ,63,63,63
BEGIN DESCRIPTION:
UNT0093 IN SAND CR 7.0
END DESCRIPTION:
XS GIS Cut Line= 2
      3455554.48     10541689.69      3456440.86     10540315.57
#Sta/Elev= 30
  4093.4  511.99  4315.4  510.91  4436.2  510.12  4472.5   509.5  4611.8  508.99
  4762.9  507.79  4835.5  506.79  4871.8   505.4    4914   504.5    4936  503.36
  4965.5   502.9  4971.7  503.22  4986.6  501.78  4995.5  499.07  5001.6  498.32
  5004.8  498.82  5007.8  500.41  5022.9  502.85  5053.3  503.69  5080.4   505.4
  5102.6  504.88  5162.1  505.03  5225.6     506  5233.5  505.74  5298.1  507.05
  5370.7  507.37  5500.8  509.15    5531  509.17  5682.3  512.22  5728.6  513.87
#Mann= 3 , 0 , 0
  4093.4     .05       0  4971.7    .035       0  5022.9     .05       0
Bank Sta=4971.7,5022.9
XS Rating Curve= 0 ,0
Exp/Cntr=0.3,0.1

Type RM Length L Ch R = 1 ,3083    ,44,44,44
BEGIN DESCRIPTION:
UNT0093 IN SAND CR 7.2
END DESCRIPTION:
XS GIS Cut Line= 4
      3455616.89     10541686.04      3456100.83     10540980.75
      3456113.85     10540893.94      3456500.13     10540340.56
#Sta/Elev= 30
    4103  511.57  4440.5  510.22  4649.7  508.34  4757.3  506.18    4850  506.54
  4879.8  505.17  4900.7  505.28  4908.8  504.01  4915.6  501.59  4921.7  503.76
  4936.6  504.19  4967.6  503.17  4977.7  502.07  4987.8  498.51  4993.7  497.81
  4996.5  497.31  4999.7  497.81  5018.1  500.63  5038.3  500.32  5061.1  503.48
    5104  504.86  5247.1  504.95  5327.3  506.34  5333.4  507.76  5348.3   506.8
  5354.4  507.91  5363.1   506.7  5419.8  507.27    5685  511.66    5721   513.1
#Mann= 3 ,-1 , 0
    4103     .05       0  4993.7    .035       0  4999.7     .05       0
Bank Sta=4967.6,5061.1
XS Rating Curve= 0 ,0
Exp/Cntr=0.3,0.1

Type RM Length L Ch R = 1 ,3039    ,716,716,716
BEGIN DESCRIPTION:
UNT0093 IN SAND CR 7.3
END DESCRIPTION:
XS GIS Cut Line= 4
      3455649.46     10541688.18       3456139.9     10540998.11
      3456152.92     10540878.75      3456287.27     10540692.39
#Sta/Elev= 30
  4079.3  511.49  4416.5  510.06  4466.9   509.2  4674.7  507.82  4710.4  506.74
    4767   507.2  4860.2  506.25  4909.6  502.66  4942.5   502.2  4972.6  502.56
  4982.7   502.1  4990.1  500.22  4995.1  501.06  5002.8  498.92  5009.9  497.76
  5012.6  497.26  5015.9  497.76  5022.9  498.36    5042  502.63  5086.4  503.79
  5092.6  503.41  5101.1  503.86    5122  503.56  5207.9  504.39  5237.4  505.33
  5243.5  506.35  5258.2  506.77  5264.4  508.57  5272.9  508.99  5275.7  509.79
#Mann= 3 ,-1 , 0
  4079.3     .05       0  5009.9    .035       0  5015.9     .05       0
Bank Sta=4982.7,5042
XS Rating Curve= 0 ,0
Exp/Cntr=0.3,0.1

Type RM Length L Ch R = 1 ,2323    ,523,523,523
BEGIN DESCRIPTION:
UNT0093 IN SAND CR 5.0
END DESCRIPTION:
XS GIS Cut Line= 3
       3456642.1     10542141.65      3456842.11     10541041.64
      3456842.11     10540241.68
#Sta/Elev= 30
  3894.7  516.28  3974.7  514.01  4067.5  512.47  4198.4  508.63  4310.2  506.21
  4485.5  504.11  4650.6  503.41  4697.7  503.69  4874.3  501.99  4900.9  500.71
  4941.6  499.63  4972.1  499.85    4981  499.57  4989.4  498.49  4992.2  497.99
  4995.4  498.49  5002.6  498.56  5010.2  499.44  5062.7  499.28  5112.7  500.37
  5172.7  502.37  5302.7  503.48  5472.7  507.29  5512.7  507.46  5582.7  509.67
  5612.7  509.32  5632.7  510.92  5652.7   511.7  5782.7  514.35  5812.7  516.45
#Mann= 3 ,-1 , 0
  3894.7     .05       0  4989.4     .03       0  4995.4     .05       0
Bank Sta=4989.4,4995.4
XS Rating Curve= 0 ,0
Exp/Cntr=0.3,0.1

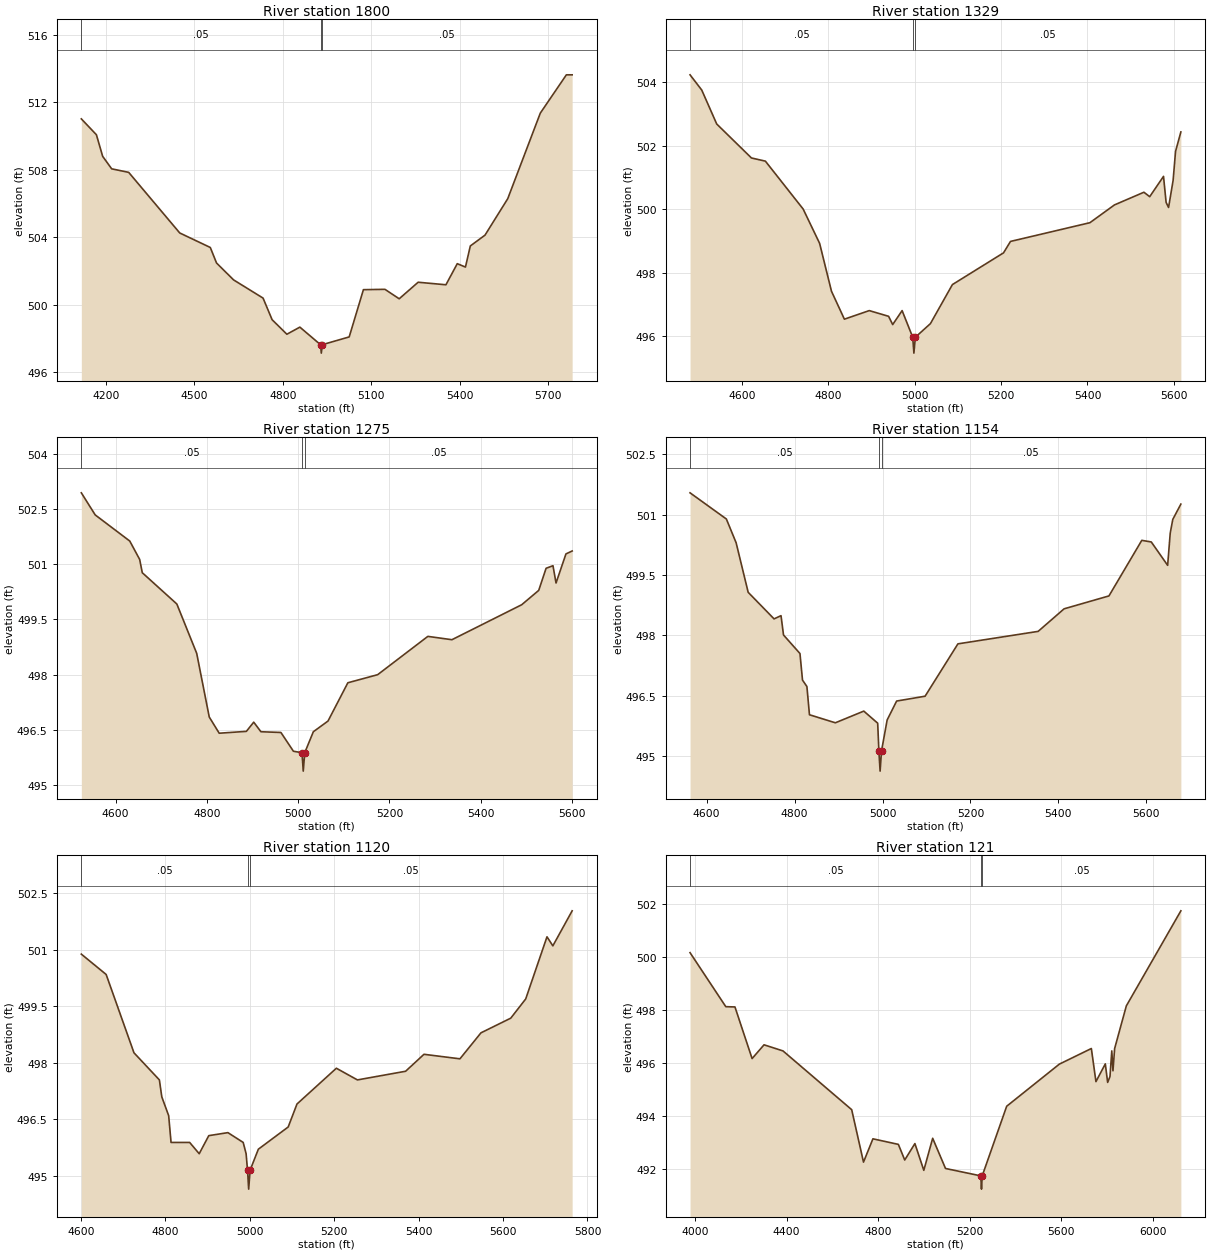
Type RM Length L Ch R = 1 ,1800    ,471,471,471
BEGIN DESCRIPTION:
UNT0093 IN SAND CR 4.0
END DESCRIPTION:
XS GIS Cut Line= 3
      3456841.59     10541992.68      3457414.64     10541078.72
      3457685.47     10540557.88
#Sta/Elev= 30
    4116  511.01  4167.2  510.07  4188.4  508.79    4219  508.05  4276.8  507.84
    4450  504.25  4553.7  503.39  4574.9  502.47  4632.7  501.47  4732.8  500.39
  4763.5  499.11  4813.6  498.25  4857.7  498.67  4927.8  497.63  4930.5  497.13
  4933.8  497.63  5025.1  498.09  5073.4  500.89  5146.5  500.91  5194.8  500.35
  5259.1  501.33  5353.4  501.18  5391.9  502.43  5419.7  502.23  5436.2  503.48
    5486  504.12  5563.2  506.28  5673.7  511.35  5762.2  513.62  5781.8  513.62
#Mann= 3 ,-1 , 0
    4116     .05       0  4927.8     .03       0  4933.8     .05       0
Bank Sta=4927.8,4933.8
XS Rating Curve= 0 ,0
Exp/Cntr=0.3,0.1

Type RM Length L Ch R = 1 ,1329    ,54,54,54
BEGIN DESCRIPTION:
UNT0093 IN SAND CR 1.2
END DESCRIPTION:
XS GIS Cut Line= 2
      3457341.75       10542076.      3457883.23     10541076.33
#Sta/Elev= 30
  4479.5  504.23  4506.6  503.75  4541.3  502.68  4621.7  501.61    4654  501.51
  4741.5     500  4779.6  498.92  4807.1  497.41    4837  496.53  4894.6   496.8
  4939.4  496.62  4948.9  496.36  4970.7   496.8  4995.3  495.96    4998  495.46
  5001.3  495.96  5036.3  496.39  5087.2  497.62  5205.6  498.62  5221.8  498.98
  5405.7  499.57  5462.5  500.13  5530.8  500.53  5544.2  500.39  5576.2  501.03
  5582.2  500.21  5587.9  500.05  5598.4   500.9  5604.1  501.82  5616.4  502.43
#Mann= 3 ,-1 , 0
  4479.5     .05       0  4995.3     .03       0  5001.3     .05       0
Bank Sta=4995.3,5001.3
XS Rating Curve= 0 ,0
Exp/Cntr=0.3,0.1

Type RM Length L Ch R = 1 ,1275    ,121,121,121
BEGIN DESCRIPTION:
UNT0093 IN SAND CR 1.1
END DESCRIPTION:
XS GIS Cut Line= 2
      3457393.86     10542075.95      3457913.76     10541134.92
#Sta/Elev= 30
  4525.1  502.94  4555.5  502.34  4631.2  501.63  4652.9  501.13  4658.6  500.77
  4734.3  499.92  4777.8  498.58  4805.3  496.85  4827.1  496.41  4886.6  496.46
  4902.7  496.71  4918.5  496.45  4962.3  496.43  4989.7  495.92  5008.5  495.88
  5011.2  495.38  5014.5  495.88  5033.3  496.45  5065.4  496.74  5108.9  497.78
  5174.2     498  5284.1  499.04  5336.9  498.95  5489.7   499.9    5527  500.29
  5543.1  500.89  5558.2  500.96  5564.9  500.49  5586.6  501.28  5600.2  501.36
#Mann= 3 ,-1 , 0
  4525.1     .05       0  5008.5     .03       0  5014.5     .05       0
Bank Sta=5008.5,5014.5
XS Rating Curve= 0 ,0
Exp/Cntr=0.3,0.1

Type RM Length L Ch R = 1 ,1154    ,34,34,34
BEGIN DESCRIPTION:
UNT0093 IN SAND CR 1.3
END DESCRIPTION:
XS GIS Cut Line= 2
      3457482.39     10542133.26      3458039.08     10541165.56
#Sta/Elev= 30
  4562.2  501.54  4644.8  500.89    4667   500.3  4694.4  499.07  4753.3  498.41
  4769.1  498.49  4774.8  498.01  4812.2  497.55    4818  496.89    4828  496.73
  4833.8  496.03  4892.7  495.83  4957.4  496.12    4989  495.82  4991.7  495.13
  4994.5  494.63  4997.7  495.13  5010.5   495.9  5032.1  496.37  5096.8  496.49
  5171.5  497.79    5354   498.1    5413  498.66    5515  498.98  5589.7  500.36
  5611.3  500.32  5648.5  499.74  5654.4  500.54  5660.2  500.88  5678.6  501.26
#Mann= 3 ,-1 , 0
  4562.2     .05       0  4991.7     .03       0  4997.7     .05       0
Bank Sta=4991.7,4997.7
XS Rating Curve= 0 ,0
Exp/Cntr=0.3,0.1

Type RM Length L Ch R = 1 ,1120    ,999,999,999
BEGIN DESCRIPTION:
UNT0093 IN SAND CR 1.4
END DESCRIPTION:
XS GIS Cut Line= 3
      3457529.24     10542128.09       3457699.4     10541808.61
      3458188.06      10541174.4
#Sta/Elev= 30
  4601.2  500.88    4660  500.34  4725.9  498.26  4786.1  497.54  4791.8  497.09
  4808.1  496.59  4813.7  495.88  4857.8  495.88  4880.4  495.58  4903.1  496.06
  4948.4  496.14  4984.6  495.88  4991.5  495.58  4994.9  495.14  4997.6  494.64
  5000.9  495.14  5020.5   495.7  5091.2  496.29    5112   496.9  5205.3  497.85
  5255.2  497.54  5369.3  497.77  5412.8  498.22    5498   498.1  5547.8  498.79
  5618.4  499.18  5653.8  499.69  5704.2  501.34  5718.1   501.1  5763.8  502.03
#Mann= 3 ,-1 , 0
  4601.2     .05       0  4994.9     .03       0  5000.9     .05       0
Bank Sta=4994.9,5000.9
XS Rating Curve= 0 ,0
Exp/Cntr=0.3,0.1

Type RM Length L Ch R = 1 ,121     ,0,0,0
BEGIN DESCRIPTION:
UNT0093 IN SAND CR 1.0
END DESCRIPTION:
XS GIS Cut Line= 5
      3457539.71     10542225.29      3458279.26     10542423.19
      3458633.43     10542242.64      3458623.01     10541638.47
      3458546.86     10541268.08
#Sta/Elev= 30
  3978.3  500.16  4134.6  498.12  4174.6  498.11  4249.5  496.16  4301.7  496.68
  4384.5  496.45  4684.9  494.23  4736.5  492.25  4777.7  493.13  4888.9  492.92
  4916.7  492.33  4961.2  492.95  5000.1  491.94  5038.9  493.15    5095  492.01
  5249.4  491.73  5252.2  491.23  5255.4  491.73  5362.4  494.36  5592.5  495.95
  5732.5  496.54  5752.6  495.29  5793.5  495.96  5803.7  495.26  5813.9  495.48
  5821.8  496.45  5826.9   495.7  5834.3  496.54  5885.4  498.15  6123.8  501.74
#Mann= 3 ,-1 , 0
  3978.3     .05       0  5249.4     .03       0  5255.4     .05       0
Bank Sta=5249.4,5255.4
XS Rating Curve= 0 ,0
Exp/Cntr=0.3,0.1

Chan Stop Cuts=-1
Use User Specified Reach Order=0
Composite Channel Slope=5