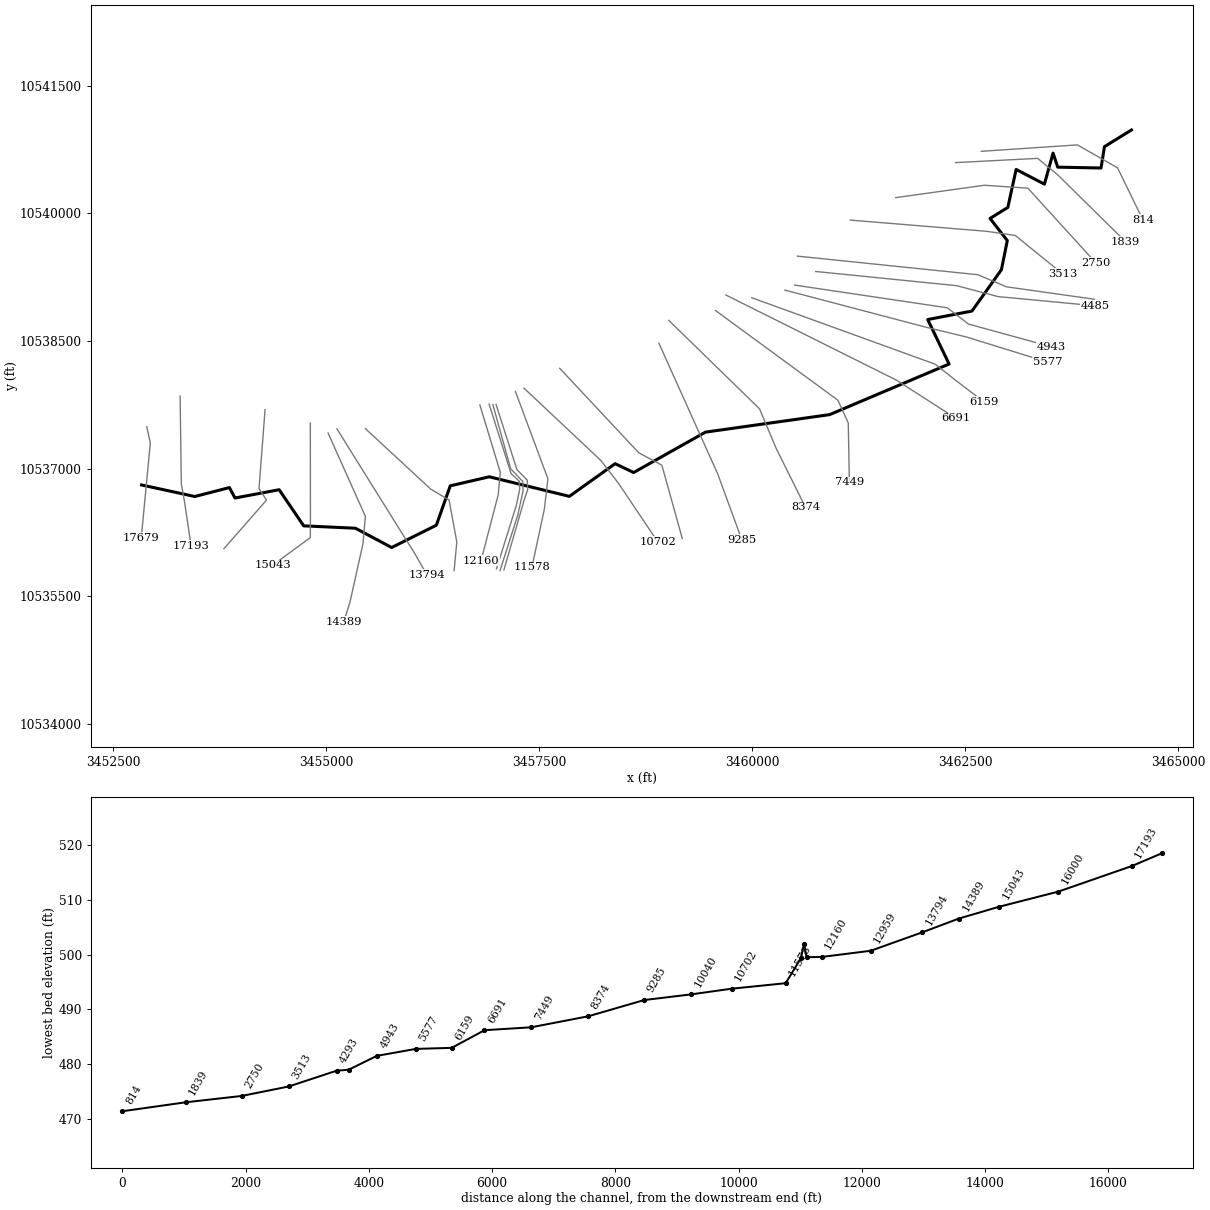
--- UNT0095 IN SAND CR.prj (project) ---

Proj Title=UNT0095 IN SAND CR Base Level Engineering
Current Plan=p01
Default Exp/Contr=0.3,0.1
English Units
Geom File=g01
Flow File=f01
Plan File=p01
BEGIN DESCRIPTION:
UNT0095 IN SAND CR
END DESCRIPTION:

--- UNT0095 IN SAND CR.p01 (plan) ---

Plan Title=Multiple Run
Short Identifier=Multiple
Geom File=g01
Flow File=f01
Subcritical Flow
K Sum by GR= 0
Std Step Tol= 0.01
Critical Tol= 0.01
Num of Std Step Trials= 20
Max Error Tol= 0.3
Flow Tol Ratio= 0.001
Split Flow NTrial= 30
Split Flow Tol= 0.02
Split Flow Ratio= 0.02
Log Output Level= 0
Friction Slope Method= 1
Unsteady Friction Slope Method= 2
Unsteady Bridges Friction Slope Method= 1
Parabolic Critical Depth
Global Vel Dist=  1 , 1 , 1
Global Log Level= 0
CheckData=True
Encroach Param= -1, 0, 0, 0
BEGIN DESCRIPTION:
Multiple Run
END DESCRIPTION:

--- UNT0095 IN SAND CR.f01 (steady flow) ---

Flow Title=Multiple
Number of Profiles=7
Profile Names=10-year,25-year,50-year,1pct_min,100-year,1pct_plu,500-year
River Rch & RM= UNT0095 IN SAND ,Reach-1,17679
     867    1180    1434    1272    1720    2327    2469
River Rch & RM= UNT0095 IN SAND ,Reach-1,12160
    1396    1938    2388    2143    2898    3919    4258
River Rch & RM= UNT0095 IN SAND ,Reach-1,4485
    1568    2187    2703    2432    3290    4449    4860
Boundary for River Rch & Prof#=UNT0095 IN SAND ,Reach-1,1
Up Type=0
Dn Type=3
Dn Slope=0.005
Boundary for River Rch & Prof#=UNT0095 IN SAND ,Reach-1,2
Up Type=0
Dn Type=3
Dn Slope=0.005
Boundary for River Rch & Prof#=UNT0095 IN SAND ,Reach-1,3
Up Type=0
Dn Type=3
Dn Slope=0.005
Boundary for River Rch & Prof#=UNT0095 IN SAND ,Reach-1,4
Up Type=0
Dn Type=3
Dn Slope=0.005
Boundary for River Rch & Prof#=UNT0095 IN SAND ,Reach-1,5
Up Type=0
Dn Type=3
Dn Slope=0.005
Boundary for River Rch & Prof#=UNT0095 IN SAND ,Reach-1,6
Up Type=0
Dn Type=3
Dn Slope=0.005
Boundary for River Rch & Prof#=UNT0095 IN SAND ,Reach-1,7
Up Type=0
Dn Type=3
Dn Slope=0.005

--- UNT0095 IN SAND CR.g01 (geometry) ---

Geom Title=Existing Conditions

River Reach=UNT0095 IN SAND ,Reach-1
Reach XY= 30
      3452836.56     10536808.07      3453461.70     10536672.21
      3453867.38     10536777.28      3453932.94     10536654.59
      3454450.90     10536752.02      3454739.33     10536327.21
      3455346.03     10536299.29      3455771.10     10536072.46
      3456295.55     10536334.65      3456458.94     10536797.77
      3456916.90     10536904.05      3457856.34     10536673.97
      3458393.69     10537058.11      3458610.66     10536954.23
      3459453.54     10537428.95      3460911.01     10537635.08
      3462312.19     10538229.95      3462061.50     10538752.86
      3462580.80     10538852.84      3462926.51     10539339.08
      3462995.48     10539681.55      3462792.94     10539941.61
      3463001.75     10540071.44      3463098.96     10540517.39
      3463430.73     10540344.85      3463532.34     10540709.81
      3463587.11     10540544.50      3464095.20     10540534.42
      3464135.27     10540785.28      3464452.11     10540981.64

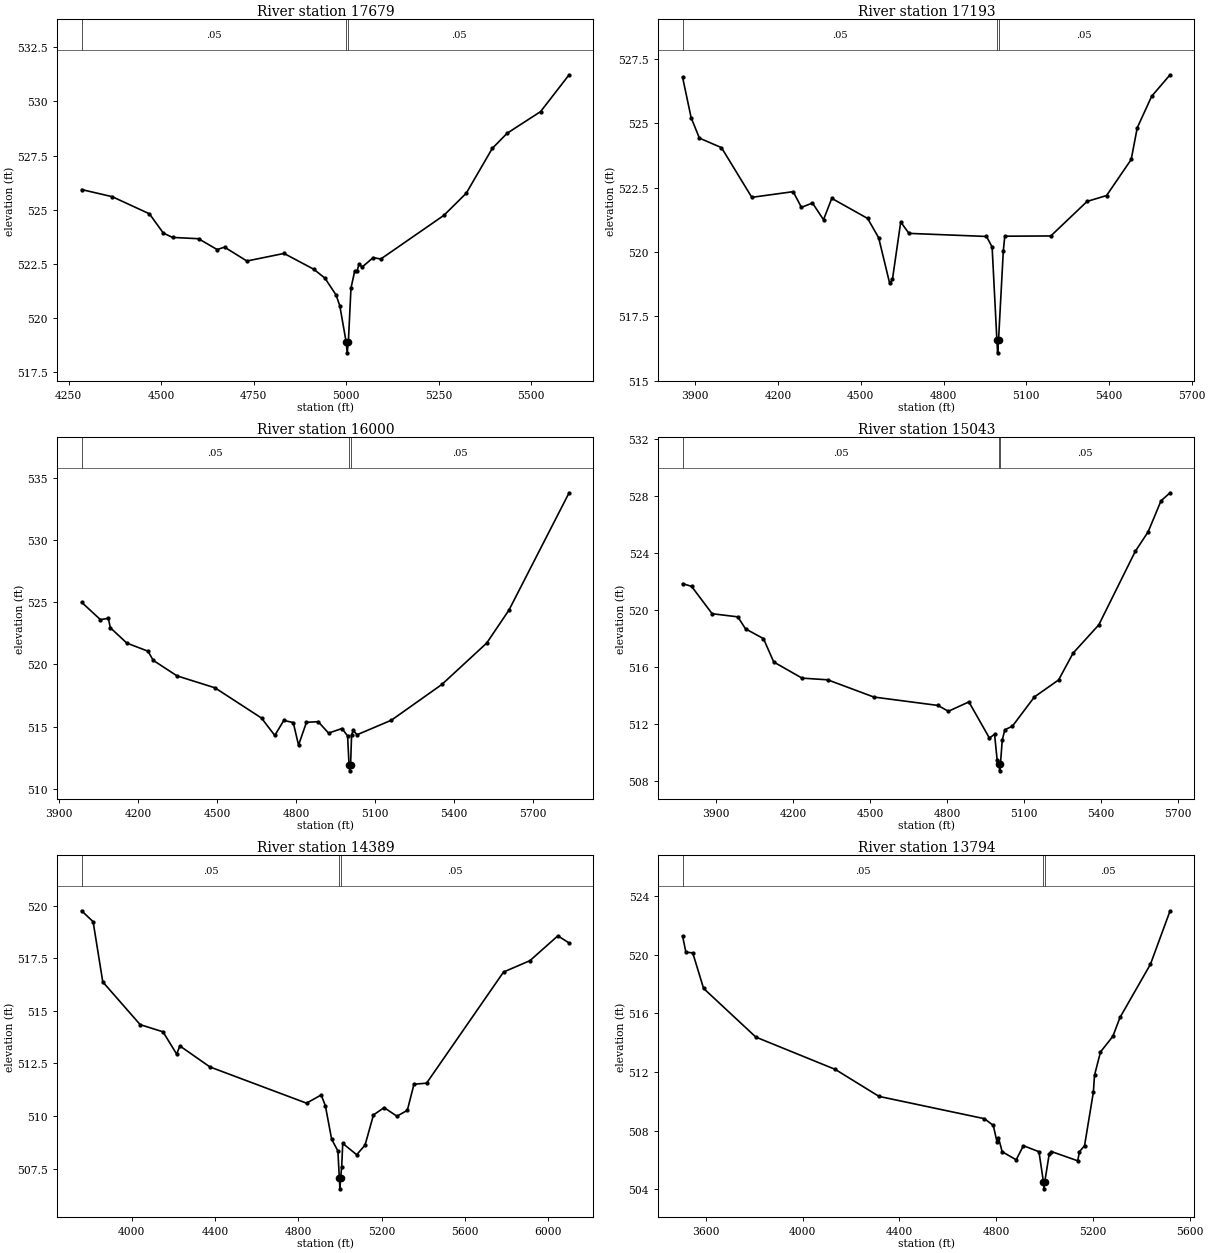
Type RM Length L Ch R = 1,17679,486,486,486
BEGIN DESCRIPTION:
UNT0095 IN SAND CR 31.1
END DESCRIPTION:
XS GIS Cut Line= 3
      3452897.72     10537492.54      3452939.39     10537299.84
      3452832.77     10536184.98
#Sta/Elev= 30
  4285.1  525.93  4367.9  525.60  4468.3  524.81  4505.9  523.92  4530.7  523.72
  4601.0  523.66  4651.2  523.16  4671.3  523.27  4731.6  522.63  4832.0  522.98
  4912.4  522.25  4942.5  521.84  4972.7  521.06  4982.7  520.56  4999.8  518.89
  5002.6  518.39  5005.8  518.89  5012.9  521.38  5022.9  522.16  5029.7  522.19
  5034.7  522.49  5043.0  522.35  5073.1  522.79  5093.2  522.72  5264.0  524.74
  5324.3  525.76  5394.6  527.83  5434.8  528.53  5525.2  529.53  5602.2  531.23
#Mann=3,-1,0
  4285.1    0.05       0  4999.8    0.03       0  5005.8    0.05       0
Bank Sta=4999.8,5005.8
Exp/Cntr=0.3,0.1

Type RM Length L Ch R = 1,17193,1193,1193,1193
BEGIN DESCRIPTION:
UNT0095 IN SAND CR 31.0
END DESCRIPTION:
XS GIS Cut Line= 4
      3453289.08     10537852.60      3453302.96     10536821.36
      3453341.04     10536607.75      3453417.33     10536093.69
#Sta/Elev= 30
  3853.8  526.78  3884.8  525.21  3914.8  524.42  3994.8  524.05  4104.8  522.12
  4254.8  522.34  4284.8  521.73  4324.8  521.90  4364.8  521.25  4394.8  522.08
  4524.8  521.30  4564.8  520.55  4604.8  518.78  4614.8  518.93  4644.8  521.16
  4674.8  520.72  4955.9  520.60  4976.3  520.19  4993.6  516.58  4996.3  516.08
  4999.6  516.58  5016.9  520.04  5022.3  520.61  5189.2  520.62  5320.6  521.96
  5391.4  522.19  5480.7  523.59  5502.6  524.82  5555.2  526.05  5621.8  526.88
#Mann=3,-1,0
  3853.8    0.05       0  4993.6    0.03       0  4999.6    0.05       0
Bank Sta=4993.6,4999.6
Exp/Cntr=0.3,0.1

Type RM Length L Ch R = 1,16000,957,957,957
BEGIN DESCRIPTION:
UNT0095 IN SAND CR 29.0
END DESCRIPTION:
XS GIS Cut Line= 4
      3454285.60     10537692.86      3454214.67     10536765.76
      3454302.96     10536630.38      3453803.30     10536058.43
#Sta/Elev= 30
  3985.4  525.01  4056.8  523.61  4086.9  523.72  4094.4  522.96  4157.1  521.72
  4237.3  521.07  4257.4  520.33  4347.7  519.08  4491.6  518.12  4668.6  515.68
  4718.8  514.28  4753.0  515.49  4789.0  515.32  4809.0  513.50  4839.1  515.34
  4883.8  515.39  4922.9  514.47  4974.2  514.84  4995.3  514.24  5000.7  511.93
  5003.4  511.43  5006.7  511.93  5010.4  514.32  5016.4  514.68  5031.5  514.34
  5161.6  515.51  5353.3  518.39  5523.3  521.72  5607.7  524.37  5836.3  533.83
#Mann=3,-1,0
  3985.4    0.05       0  5000.7    0.03       0  5006.7    0.05       0
Bank Sta=5000.7,5006.7
Exp/Cntr=0.3,0.1

Type RM Length L Ch R = 1,15043,654,654,654
BEGIN DESCRIPTION:
UNT0095 IN SAND CR 27.0
END DESCRIPTION:
XS GIS Cut Line= 4
      3454816.85     10537536.64      3454817.93     10536436.70
      3454816.85     10536189.41      3454372.37     10535862.99
#Sta/Elev= 30
  3769.9  521.83  3804.9  521.64  3884.9  519.72  3984.9  519.50  4014.9  518.66
  4084.9  517.97  4124.9  516.33  4234.9  515.20  4334.9  515.08  4514.9  513.87
  4764.9  513.28  4804.9  512.87  4884.9  513.53  4964.9  510.99  4984.9  511.26
  4994.9  509.47  5001.9  509.19  5004.7  508.69  5007.9  509.19  5014.9  510.85
  5024.9  511.57  5054.6  511.83  5140.2  513.88  5234.3  515.07  5290.6  516.95
  5391.0  518.94  5533.0  524.10  5583.1  525.47  5633.3  527.65  5668.6  528.21
#Mann=3,-1,0
  3769.9    0.05       0  5001.9    0.03       0  5007.9    0.05       0
Bank Sta=5001.9,5007.9
Exp/Cntr=0.3,0.1

Type RM Length L Ch R = 1,14389,595,595,595
BEGIN DESCRIPTION:
UNT0095 IN SAND CR 25.0
END DESCRIPTION:
XS GIS Cut Line= 5
      3455025.19     10537418.56      3455462.69     10536439.41
      3455434.91     10536119.97      3455282.13     10535429.00
      3455209.23     10535199.87
#Sta/Elev= 30
  3758.7  519.75  3814.0  519.23  3860.4  516.37  4040.1  514.34  4149.6  514.00
  4215.3  512.94  4230.5  513.33  4375.2  512.33  4838.9  510.61  4909.2  511.00
  4929.3  510.49  4959.4  508.90  4989.5  508.34  4996.5  507.04  4999.3  506.54
  5002.5  507.04  5007.8  507.60  5012.8  508.70  5079.9  508.16  5120.0  508.62
  5160.3  510.05  5211.5  510.40  5273.0  509.99  5323.0  510.27  5354.9  511.51
  5415.4  511.56  5785.0  516.84  5911.7  517.38  6045.9  518.56  6099.9  518.22
#Mann=3,-1,0
  3758.7    0.05       0  4996.5    0.03       0  5002.5    0.05       0
Bank Sta=4996.5,5002.5
Exp/Cntr=0.3,0.1

Type RM Length L Ch R = 1,13794,835,835,835
BEGIN DESCRIPTION:
UNT0095 IN SAND CR 24.0
END DESCRIPTION:
XS GIS Cut Line= 4
      3455129.36     10537467.19      3455855.05     10536300.52
      3456032.13     10536019.27      3456184.89     10535751.94
#Sta/Elev= 30
  3504.6  521.25  3518.1  520.16  3546.5  520.11  3591.3  517.69  3807.4  514.37
  4135.3  512.17  4316.1  510.33  4751.7  508.81  4788.3  508.35  4803.7  507.22
  4809.6  507.52  4824.9  506.56  4882.8  506.01  4912.7  506.97  4977.0  506.56
  4995.2  504.53  4997.9  504.03  5001.2  504.53  5019.4  506.41  5028.7  506.57
  5137.2  505.94  5144.1  506.56  5165.3  506.97  5201.8  510.62  5206.5  511.77
  5231.2  513.36  5282.2  514.42  5311.8  515.71  5437.7  519.34  5518.8  522.98
#Mann=3,-1,0
  3504.6    0.05       0  4995.2    0.03       0  5001.2    0.05       0
Bank Sta=4995.2,5001.2
Exp/Cntr=0.3,0.1

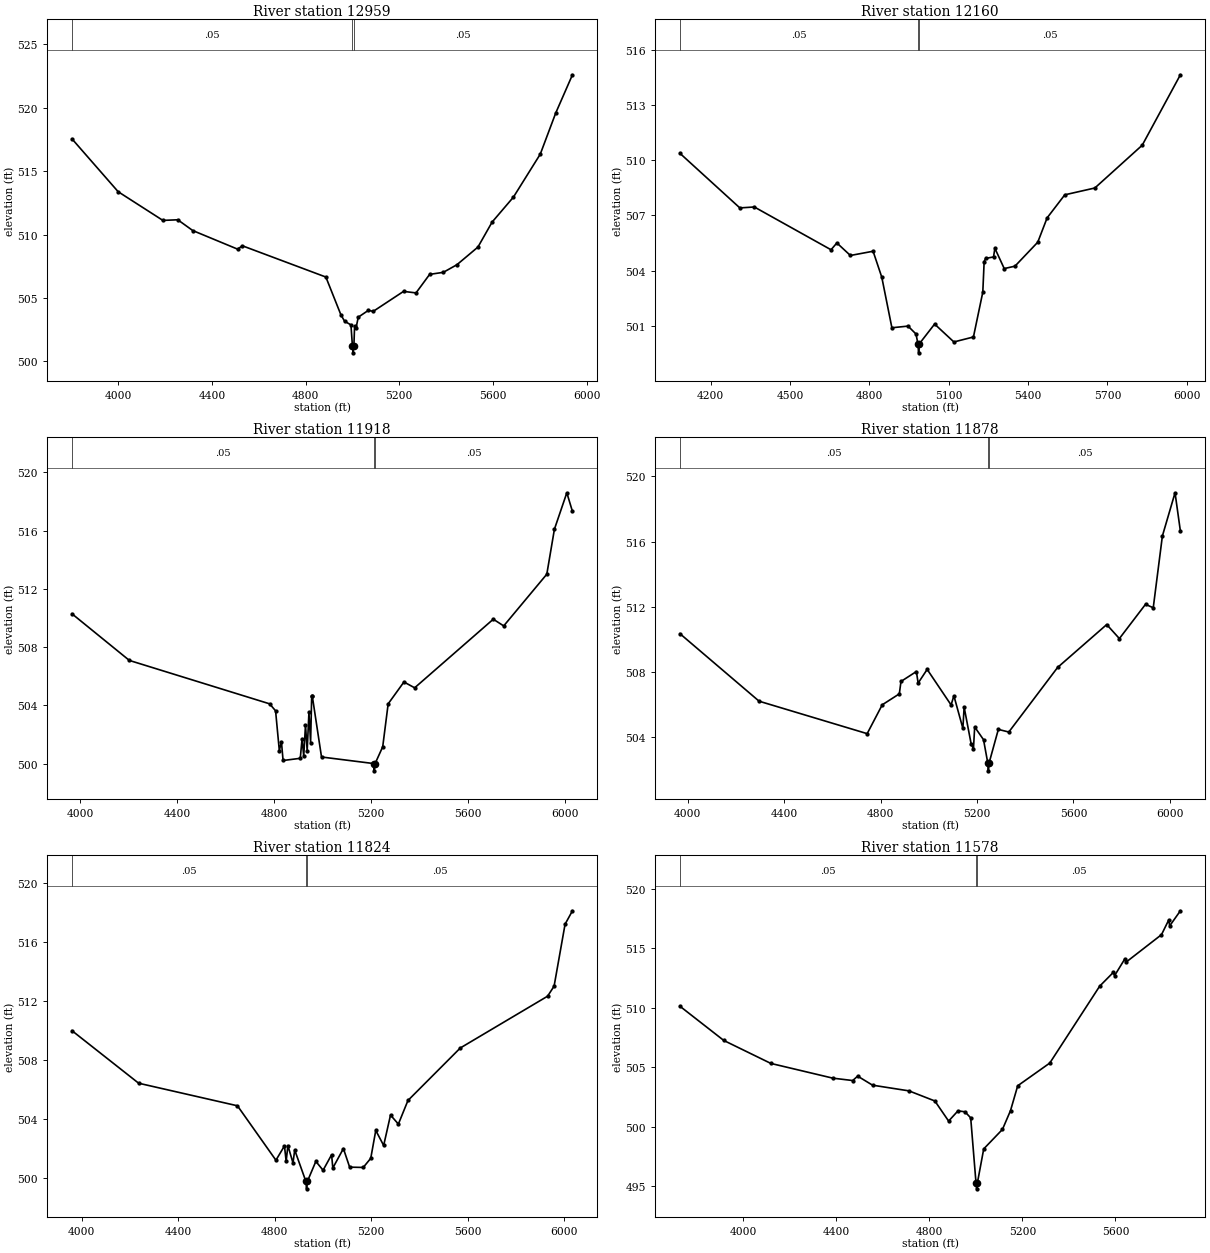
Type RM Length L Ch R = 1,12959,799,799,799
BEGIN DESCRIPTION:
UNT0095 IN SAND CR 23.0
END DESCRIPTION:
XS GIS Cut Line= 5
      3455462.66     10537470.69      3456230.05     10536758.86
      3456445.33     10536630.38      3456535.60     10536137.33
      3456504.35     10535800.53
#Sta/Elev= 30
  3802.5  517.53  3999.6  513.37  4190.6  511.11  4254.1  511.16  4318.2  510.31
  4509.2  508.85  4530.2  509.11  4886.5  506.65  4950.8  503.67  4966.4  503.17
  4993.6  502.88  5000.0  501.18  5002.7  500.68  5006.0  501.18  5009.2  502.80
  5015.0  502.61  5024.8  503.49  5067.6  504.02  5089.0  503.95  5218.2  505.52
  5271.4  505.40  5329.6  506.86  5387.9  507.02  5446.1  507.62  5535.8  509.01
  5596.4  510.98  5687.2  512.94  5802.0  516.33  5868.0  519.57  5939.4  522.58
#Mann=3,-1,0
  3802.5    0.05       0  5000.0    0.03       0  5006.0    0.05       0
Bank Sta=5000,5006
Exp/Cntr=0.3,0.1

Type RM Length L Ch R = 1,12160,242,242,242
BEGIN DESCRIPTION:
UNT0095 IN SAND CR 22.0
END DESCRIPTION:
XS GIS Cut Line= 4
      3456806.43     10537748.48      3457046.02     10536956.77
      3457021.71     10536692.88      3456820.34     10535918.62
#Sta/Elev= 30
  4083.7  510.37  4310.2  507.41  4365.0  507.46  4655.0  505.14  4677.0  505.51
  4728.2  504.83  4814.0  505.06  4846.9  503.65  4885.1  500.91  4946.1  501.00
  4976.3  500.57  4983.3  500.05  4986.1  499.55  4989.3  500.05  5046.6  501.11
  5119.5  500.14  5193.4  500.41  5228.8  502.84  5233.9  504.49  5239.2  504.67
  5269.3  504.75  5274.5  505.22  5309.8  504.12  5350.4  504.25  5436.6  505.55
  5472.0  506.87  5538.8  508.12  5652.5  508.49  5831.6  510.81  5975.9  514.63
#Mann=3,-1,0
  4083.7    0.05       0  4983.3    0.03       0  4989.3    0.05       0
Bank Sta=4983.3,4989.3
Exp/Cntr=0.3,0.1

Type RM Length L Ch R = 1,11918,40,40,40
BEGIN DESCRIPTION:
UNT0095 IN SAND CR 21.01
END DESCRIPTION:
XS GIS Cut Line= 6
      3456914.60     10537758.25      3457173.27     10536940.57
      3457268.75     10536852.03      3457273.96     10536758.28
      3457234.03     10536567.31      3457001.38     10535820.75
#Sta/Elev= 30
  3966.8  510.29  4203.2  507.09  4781.3  504.11  4805.8  503.63  4821.2  500.90
  4829.9  501.51  4836.7  500.22  4907.6  500.37  4915.0  501.72  4921.8  500.52
  4929.1  502.67  4936.0  500.89  4943.3  503.53  4950.1  501.45  4954.6  504.62
  4957.3  504.62  4995.1  500.46  5210.0  500.01  5212.7  499.51  5216.0  500.01
  5247.3  501.16  5269.8  504.11  5334.8  505.61  5379.0  505.21  5703.0  509.92
  5746.0  509.46  5923.6  513.01  5955.0  516.10  6006.1  518.60  6029.3  517.32
#Mann=3,-1,0
  3966.8    0.05       0  5210.0    0.03       0  5216.0    0.05       0
Bank Sta=5210,5216
Exp/Cntr=0.3,0.1

Type RM Length L Ch R = 1,11878,54,54,54
BEGIN DESCRIPTION:
UNT0095 IN SAND CR 21.0
END DESCRIPTION:
XS GIS Cut Line= 6
      3456959.23     10537751.86      3457167.55     10536998.44
      3457309.91     10536849.13      3457313.38     10536738.02
      3457250.88     10536453.30      3457042.54     10535800.50
#Sta/Elev= 30
  3967.8  510.36  4296.2  506.22  4744.4  504.23  4807.0  506.00  4877.8  506.67
  4884.7  507.43  4948.6  508.04  4955.8  507.33  4993.3  508.17  5092.5  505.99
  5104.2  506.55  5141.5  504.55  5146.6  505.86  5175.9  503.59  5185.3  503.30
  5190.4  504.64  5227.1  503.86  5244.5  502.45  5247.3  501.95  5250.5  502.45
  5288.5  504.49  5332.0  504.33  5534.4  508.29  5738.1  510.92  5790.6  510.06
  5899.0  512.16  5931.1  511.95  5969.0  516.35  6021.5  519.00  6043.7  516.65
#Mann=3,-1,0
  3967.8    0.05       0  5244.5    0.03       0  5250.5    0.05       0
Bank Sta=5244.5,5250.5
Exp/Cntr=0.3,0.1

Type RM Length L Ch R = 1,11824,246,246,246
BEGIN DESCRIPTION:
UNT0095 IN SAND CR 21.02
END DESCRIPTION:
XS GIS Cut Line= 6
      3456996.17     10537754.84      3457240.98     10536989.18
      3457362.50     10536864.18      3457367.71     10536753.07
      3457331.25     10536647.17      3457088.19     10535808.60
#Sta/Elev= 30
  3960.1  510.01  4236.4  506.45  4645.9  504.92  4805.4  501.23  4840.8  502.20
  4847.8  501.16  4855.0  502.22  4876.1  501.05  4883.3  501.92  4929.7  499.79
  4932.4  499.29  4935.7  499.79  4970.9  501.15  5000.9  500.55  5036.2  501.60
  5041.2  500.70  5085.1  502.02  5111.0  500.76  5167.3  500.74  5198.5  501.36
  5219.3  503.25  5252.0  502.23  5280.4  504.29  5313.0  503.68  5352.7  505.28
  5569.8  508.84  5931.6  512.35  5958.5  513.03  6004.0  517.23  6034.6  518.14
#Mann=3,-1,0
  3960.1    0.05       0  4929.7    0.03       0  4935.7    0.05       0
Bank Sta=4929.7,4935.7
Exp/Cntr=0.3,0.1

Type RM Length L Ch R = 1,11578,876,876,876
BEGIN DESCRIPTION:
UNT0095 IN SAND CR 20.0
END DESCRIPTION:
XS GIS Cut Line= 4
      3457223.10     10537908.16      3457605.05     10536880.38
      3457563.38     10536526.22      3457417.54     10535842.15
#Sta/Elev= 30
  3727.1  510.14  3915.8  507.26  4118.1  505.33  4384.8  504.09  4470.2  503.89
  4491.5  504.26  4555.5  503.50  4712.4  503.02  4823.6  502.17  4882.7  500.48
  4923.0  501.34  4953.2  501.26  4977.7  500.75  5000.5  495.28  5003.3  494.78
  5006.5  495.28  5033.7  498.14  5114.3  499.78  5148.9  501.36  5179.9  503.45
  5317.8  505.36  5532.5  511.83  5591.3  512.99  5596.4  512.71  5640.9  514.13
  5646.0  513.85  5798.3  516.16  5828.8  517.37  5833.9  516.91  5879.6  518.17
#Mann=3,-1,0
  3727.1    0.05       0  5000.5    0.03       0  5006.5    0.05       0
Bank Sta=5000.5,5006.5
Exp/Cntr=0.3,0.1

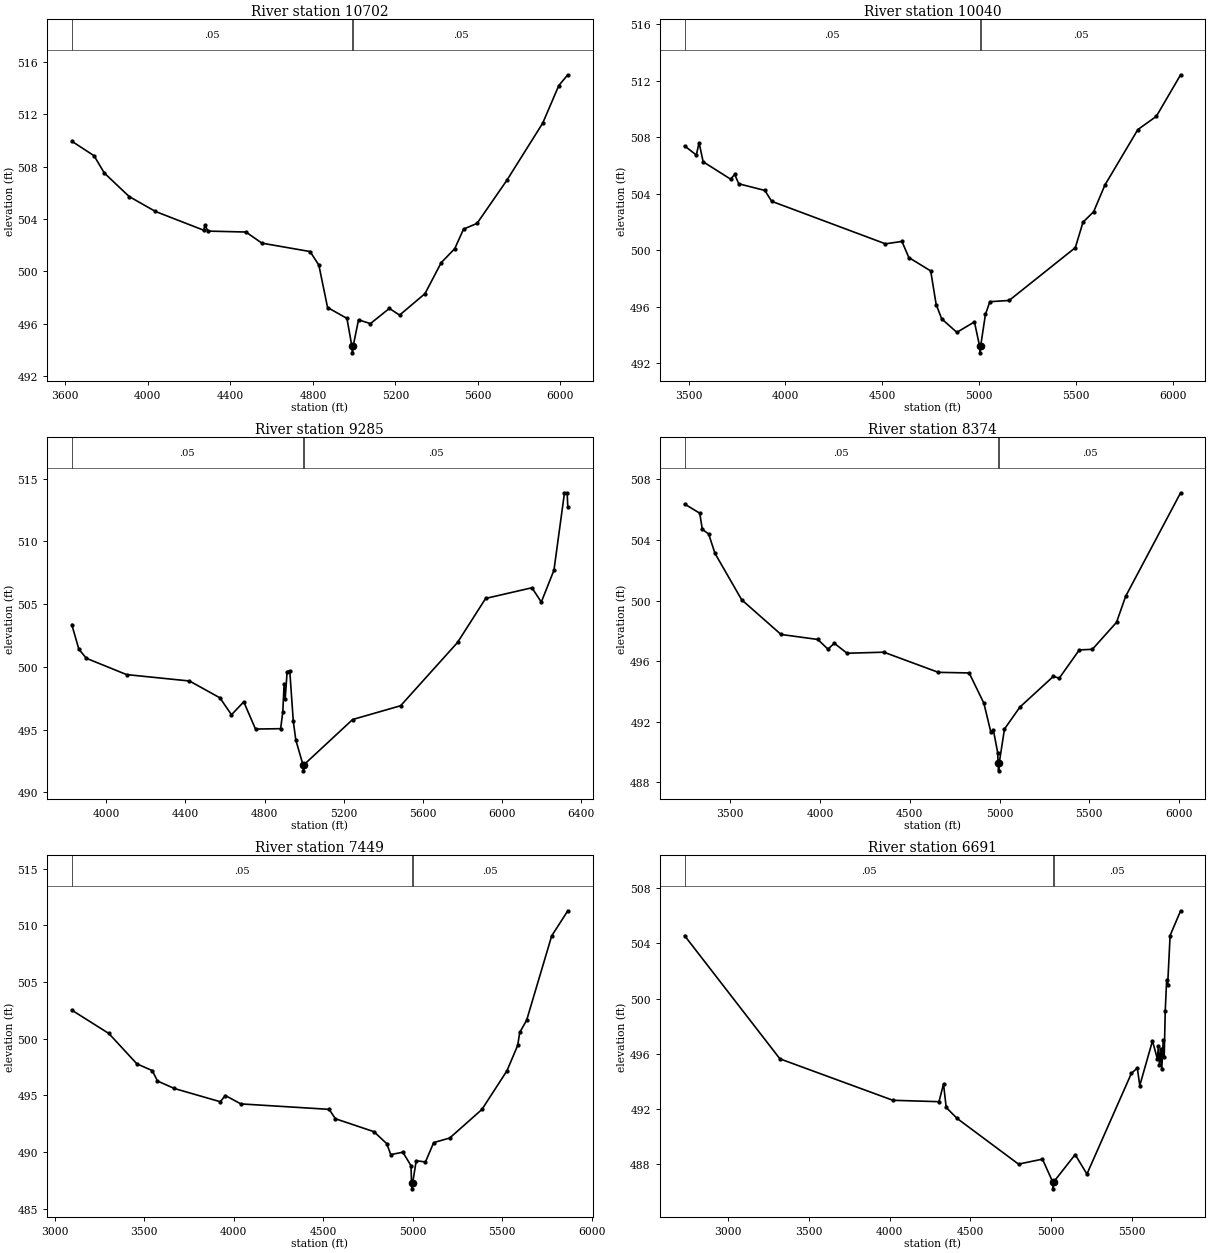
Type RM Length L Ch R = 1,10702,662,662,662
BEGIN DESCRIPTION:
UNT0095 IN SAND CR 19.0
END DESCRIPTION:
XS GIS Cut Line= 4
      3457323.80     10537946.35      3458226.58     10537095.66
      3458434.91     10536824.83      3458892.12     10536141.63
#Sta/Elev= 30
  3631.3  509.93  3739.4  508.82  3789.1  507.50  3909.3  505.71  4036.7  504.57
  4270.2  503.14  4277.0  503.52  4291.2  503.07  4475.3  503.00  4553.0  502.15
  4786.4  501.51  4828.9  500.47  4871.0  497.24  4964.9  496.41  4989.0  494.28
  4991.8  493.78  4995.0  494.28  5021.1  496.30  5078.7  496.01  5170.6  497.17
  5220.3  496.66  5343.4  498.30  5421.8  500.66  5487.5  501.73  5530.1  503.22
  5595.6  503.66  5739.7  506.94  5913.9  511.31  5991.9  514.18  6035.5  515.00
#Mann=3,-1,0
  3631.3    0.05       0  4989.0    0.03       0  4995.0    0.05       0
Bank Sta=4989,4995
Exp/Cntr=0.3,0.1

Type RM Length L Ch R = 1,10040,755,755,755
BEGIN DESCRIPTION:
UNT0095 IN SAND CR 17.0
END DESCRIPTION:
XS GIS Cut Line= 4
      3457743.94     10538178.99      3458671.02     10537185.94
      3458942.11     10537040.11      3459181.43     10536179.01
#Sta/Elev= 30
  3479.6  507.39  3540.2  506.75  3554.4  507.62  3575.4  506.27  3717.0  505.04
  3738.1  505.37  3759.5  504.71  3893.9  504.24  3929.1  503.47  4516.3  500.46
  4601.3  500.63  4636.9  499.49  4749.8  498.54  4778.1  496.16  4806.5  495.15
  4884.8  494.19  4975.6  494.93  5001.8  493.24  5004.5  492.74  5007.8  493.24
  5032.4  495.46  5055.1  496.36  5154.7  496.45  5496.4  500.19  5535.8  501.99
  5590.7  502.73  5648.9  504.62  5819.0  508.55  5914.6  509.49  6039.7  512.43
#Mann=3,-1,0
  3479.6    0.05       0  5001.8    0.03       0  5007.8    0.05       0
Bank Sta=5001.8,5007.8
Exp/Cntr=0.3,0.1

Type RM Length L Ch R = 1,9285,911,911,911
BEGIN DESCRIPTION:
UNT0095 IN SAND CR 15.0
END DESCRIPTION:
XS GIS Cut Line= 3
      3458907.12     10538474.15      3459598.10     10536935.94
      3459879.07     10536165.88
#Sta/Elev= 30
  3825.6  503.38  3861.2  501.42  3899.2  500.69  4102.4  499.39  4420.3  498.88
  4573.8  497.54  4632.5  496.19  4694.4  497.22  4753.8  495.05  4880.8  495.08
  4891.7  496.42  4898.3  498.64  4903.8  497.47  4913.6  499.62  4926.9  499.69
  4944.6  495.69  4957.5  494.17  4993.4  492.22  4996.2  491.72  4999.4  492.22
  5244.5  495.81  5487.1  496.91  5774.4  501.95  5916.5  505.46  6150.3  506.31
  6197.7  505.17  6261.6  507.71  6314.8  513.88  6328.3  513.88  6331.6  512.74
#Mann=3,-1,0
  3825.6    0.05       0  4993.4    0.03       0  4999.4    0.05       0
Bank Sta=4993.4,4999.4
Exp/Cntr=0.3,0.1

Type RM Length L Ch R = 1,8374,925,925,925
BEGIN DESCRIPTION:
UNT0095 IN SAND CR 14.0
END DESCRIPTION:
XS GIS Cut Line= 4
      3459023.45     10538742.61      3460087.69     10537703.30
      3460283.57     10537237.42      3460625.88     10536547.05
#Sta/Elev= 30
  3245.4  506.37  3329.9  505.76  3344.1  504.70  3379.5  504.39  3414.8  503.11
  3563.4  500.05  3782.6  497.76  3987.6  497.43  4044.2  496.79  4079.6  497.18
  4150.4  496.52  4355.4  496.59  4659.4  495.26  4830.8  495.22  4912.9  493.22
  4951.7  491.31  4965.8  491.45  4989.6  489.97  4992.1  489.26  4994.8  488.76
  4998.1  489.26  5027.6  491.52  5113.7  492.97  5300.6  495.00  5332.4  494.87
  5444.5  496.74  5517.3  496.78  5651.8  498.56  5702.4  500.27  6008.9  507.11
#Mann=3,-1,0
  3245.4    0.05       0  4992.1   0.035       0  4998.1    0.05       0
Bank Sta=4992.1,4998.1
Exp/Cntr=0.3,0.1

Type RM Length L Ch R = 1,7449,758,758,758
BEGIN DESCRIPTION:
UNT0095 IN SAND CR 12.0
END DESCRIPTION:
XS GIS Cut Line= 4
      3459570.36     10538859.53      3461007.83     10537804.00
      3461129.35     10537536.63      3461142.11     10536841.62
#Sta/Elev= 30
  3095.2  502.52  3302.4  500.46  3459.1  497.78  3544.8  497.19  3574.1  496.27
  3668.1  495.61  3925.2  494.44  3953.4  494.99  4040.1  494.25  4533.3  493.77
  4568.8  492.94  4784.0  491.80  4855.0  490.75  4878.1  489.78  4945.5  489.99
  4991.0  488.80  4994.1  487.26  4996.8  486.76  5000.1  487.26  5020.2  489.24
  5071.8  489.13  5117.9  490.84  5207.3  491.24  5387.3  493.76  5527.3  497.17
  5587.3  499.41  5598.6  500.55  5637.3  501.63  5777.4  509.07  5867.4  511.28
#Mann=3,-1,0
  3095.2    0.05       0  4994.1    0.03       0  5000.1    0.05       0
Bank Sta=4994.1,5000.1
Exp/Cntr=0.3,0.1

Type RM Length L Ch R = 1,6691,532,532,532
BEGIN DESCRIPTION:
UNT0095 IN SAND CR 10.0
END DESCRIPTION:
XS GIS Cut Line= 3
      3459692.13     10539041.63      3461692.11     10538041.64
      3462392.10     10537591.65
#Sta/Elev= 30
  2731.8  504.56  3321.5  495.64  4020.3  492.64  4305.4  492.54  4333.4  493.82
  4350.1  492.12  4417.2  491.33  4797.3  488.02  4945.5  488.38  5008.8  486.73
  5011.5  486.23  5014.8  486.73  5147.8  488.71  5220.5  487.30  5495.9  494.60
  5532.2  494.97  5547.4  493.71  5626.0  496.94  5656.4  495.63  5662.3  496.56
  5669.2  495.18  5677.5  496.35  5683.4  494.91  5692.7  497.03  5698.6  495.80
  5704.9  499.10  5713.8  501.38  5719.8  500.97  5735.0  504.57  5800.0  506.36
#Mann=3,-1,0
  2731.8    0.05       0  5008.8   0.035       0  5014.8    0.05       0
Bank Sta=5008.8,5014.8
Exp/Cntr=0.3,0.1

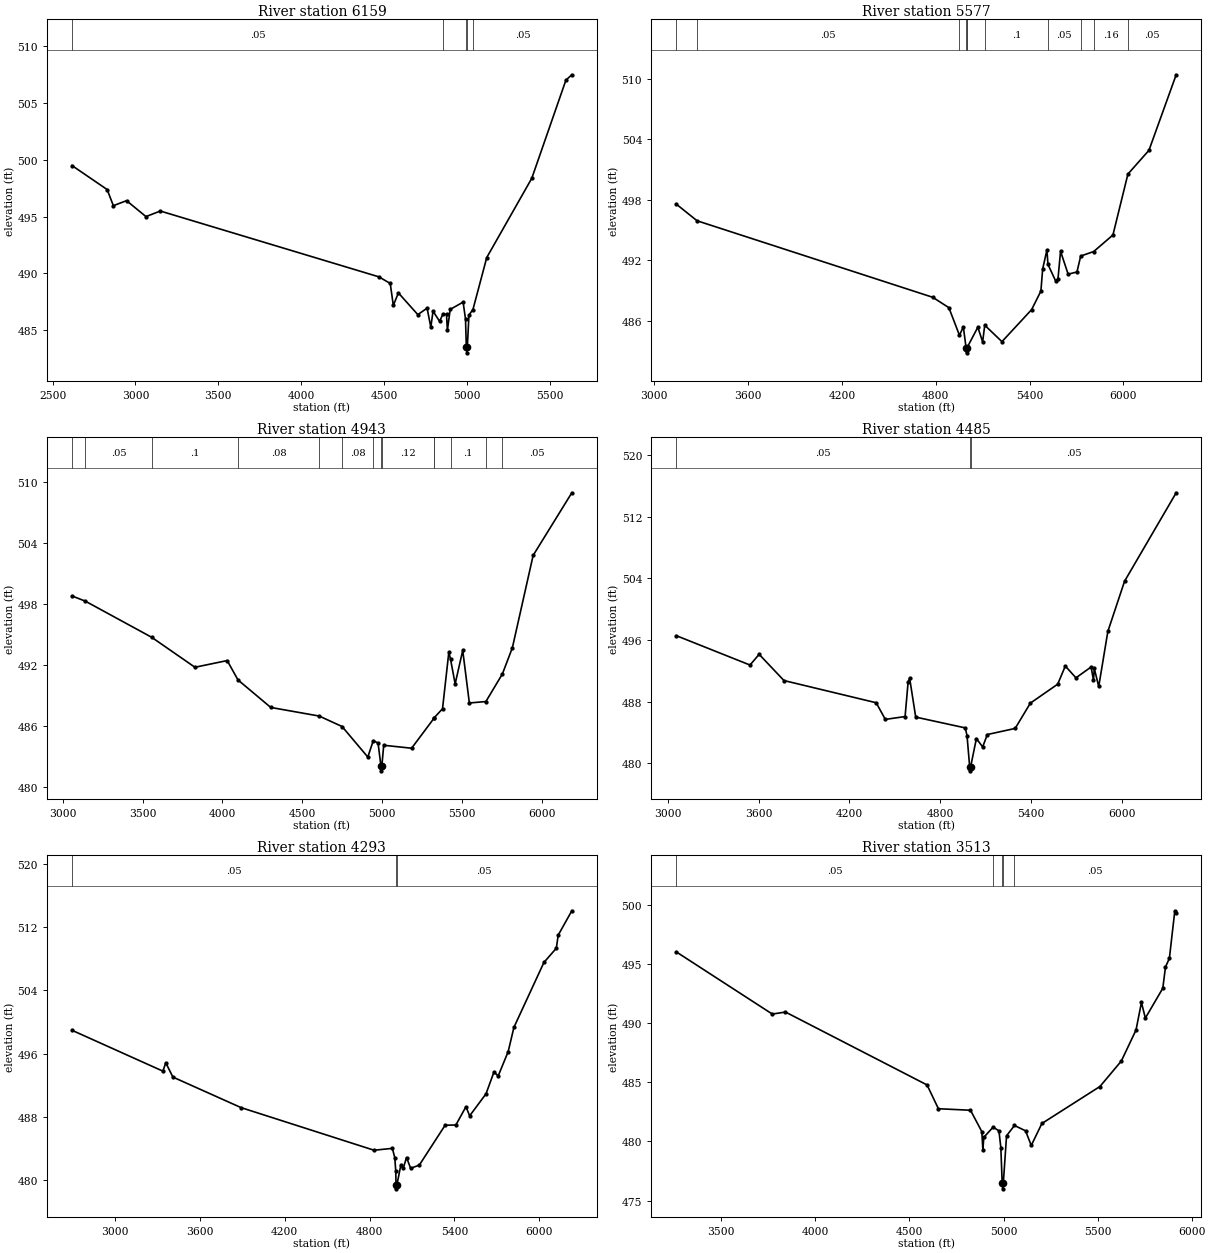
Type RM Length L Ch R = 1,6159,582,582,582
BEGIN DESCRIPTION:
UNT0095 IN SAND CR 9.0
END DESCRIPTION:
XS GIS Cut Line= 4
      3459997.39     10539008.86      3462150.19     10538227.61
      3462382.83     10538043.58      3462723.11     10537783.16
#Sta/Elev= 30
  2617.0  499.49  2829.1  497.38  2866.7  495.96  2946.2  496.40  3063.4  495.00
  3149.9  495.49  4469.0  489.70  4536.9  489.12  4555.5  487.19  4586.1  488.29
  4703.3  486.38  4759.2  486.95  4781.6  485.28  4795.1  486.68  4834.7  485.79
  4855.5  486.45  4876.3  486.40  4881.6  485.00  4898.6  486.84  4976.5  487.48
  4990.9  486.00  4995.9  483.52  4998.6  483.02  5001.9  483.52  5011.7  486.34
  5035.8  486.83  5119.1  491.40  5390.8  498.37  5596.6  507.00  5632.3  507.47
#Mann=5,-1,0
  2617.0    0.05       0  4855.5    0.12       0  4995.9    0.07       0
  5001.9    0.12       0  5035.8    0.05       0
Bank Sta=4995.9,5001.9
Exp/Cntr=0.3,0.1

Type RM Length L Ch R = 1,5577,634,634,634
BEGIN DESCRIPTION:
UNT0095 IN SAND CR 7.0
END DESCRIPTION:
XS GIS Cut Line= 4
      3460386.30     10539099.13      3462018.24     10538668.58
      3462518.24     10538547.05      3463468.33     10538252.32
#Sta/Elev= 30
  3140.4  497.58  3273.1  495.93  4780.5  488.34  4883.7  487.31  4951.5  484.57
  4976.2  485.41  4993.8  483.33  4996.6  482.83  4999.8  483.33  5000.1  483.34
  5068.9  485.37  5099.7  483.92  5113.2  485.57  5223.2  483.94  5413.2  487.12
  5472.4  488.96  5483.6  491.15  5511.0  493.04  5517.4  491.60  5566.7  489.96
  5581.4  490.15  5598.1  492.90  5646.5  490.63  5702.8  490.85  5727.0  492.43
  5810.4  492.88  5933.1  494.52  6028.8  500.56  6163.5  502.92  6337.5  510.41
#Mann=11,-1,0
  3140.4    0.08       0  3273.1    0.05       0  4951.5     0.1       0
  4993.8    0.07       0  4999.8     0.1       0  5000.1    0.12       0
  5113.2     0.1       0  5517.4    0.05       0  5727.0     0.1       0
  5810.4    0.16       0  6028.8    0.05       0
Bank Sta=4993.8,4999.8
Exp/Cntr=0.3,0.1

Type RM Length L Ch R = 1,4943,458,458,458
BEGIN DESCRIPTION:
UNT0095 IN SAND CR 6.0
END DESCRIPTION:
XS GIS Cut Line= 4
      3460499.96     10539157.90      3462292.55     10538890.80
      3462539.35     10538699.92      3463511.34     10538432.46
#Sta/Elev= 30
  3057.5  498.80  3140.8  498.29  3556.5  494.73  3828.1  491.77  4030.3  492.43
  4097.9  490.52  4303.2  487.81  4607.0  486.96  4750.1  485.93  4911.5  482.92
  4946.0  484.55  4975.8  484.29  4993.6  482.06  4996.3  481.56  4999.6  482.06
  5011.1  484.08  5185.9  483.79  5326.1  486.74  5328.4  486.81  5379.7  487.68
  5419.2  493.26  5429.8  492.57  5458.8  490.13  5506.3  493.43  5547.8  488.25
  5651.4  488.39  5754.8  491.11  5817.4  493.69  5947.6  502.80  6190.0  508.97
#Mann=14,-1,0
  3057.5    0.08       0  3140.8    0.05       0  3556.5     0.1       0
  4097.9    0.08       0  4607.0    0.05       0  4750.1    0.08       0
  4946.0    0.12       0  4993.6    0.07       0  4999.6    0.12       0
  5326.1     0.1       0  5328.4    0.05       0  5429.8     0.1       0
  5651.4    0.16       0  5754.8    0.05       0
Bank Sta=4993.6,4999.6
Exp/Cntr=0.3,0.1

Type RM Length L Ch R = 1,4485,192,192,192
BEGIN DESCRIPTION:
UNT0095 IN SAND CR 5.0
END DESCRIPTION:
XS GIS Cut Line= 4
      3460747.36     10539317.89      3462400.19     10539151.22
      3462886.30     10539022.75      3464021.70     10538915.11
#Sta/Elev= 30
  3055.4  496.56  3542.6  492.75  3602.9  494.14  3767.1  490.74  4376.8  487.86
  4437.1  485.70  4567.8  486.07  4587.9  490.56  4597.9  491.05  4638.1  486.00
  4965.5  484.60  4977.2  483.61  4994.9  479.53  4997.6  479.03  5000.9  479.53
  5039.2  483.22  5080.6  482.13  5111.6  483.74  5295.6  484.53  5396.0  487.81
  5576.8  490.27  5627.0  492.62  5697.3  491.09  5797.8  492.50  5813.4  490.75
  5818.4  492.31  5848.0  489.97  5908.3  497.11  6018.8  503.62  6359.9  515.09
#Mann=3,-1,0
  3055.4    0.05       0  4994.9   0.035       0  5000.9    0.05       0
Bank Sta=4994.9,5000.9
Exp/Cntr=0.3,0.1

Type RM Length L Ch R = 1,4293,780,780,780
BEGIN DESCRIPTION:
UNT0095 IN SAND CR 4.0
END DESCRIPTION:
XS GIS Cut Line= 4
      3460532.11     10539498.44      3462650.19     10539279.69
      3462986.99     10539137.33      3464017.64     10538991.58
#Sta/Elev= 30
  2695.2  498.96  3338.6  493.78  3358.7  494.85  3409.0  493.03  3891.5  489.16
  4832.2  483.76  4961.6  484.00  4978.6  482.83  4985.3  481.18  4987.7  479.37
  4990.4  478.87  4993.7  479.37  5022.0  481.92  5038.1  481.45  5061.8  482.84
  5090.9  481.47  5152.3  481.88  5334.8  486.93  5410.9  486.96  5482.0  489.27
  5508.4  488.12  5624.1  490.91  5680.1  493.66  5710.4  493.18  5781.1  496.27
  5821.5  499.33  6033.6  507.55  6121.5  509.36  6134.6  511.01  6231.1  514.10
#Mann=3,-1,0
  2695.2    0.05       0  4987.7   0.035       0  4993.7    0.05       0
Bank Sta=4987.7,4993.7
Exp/Cntr=0.3,0.1

Type RM Length L Ch R = 1,3513,763,763,763
BEGIN DESCRIPTION:
UNT0095 IN SAND CR 3.0
END DESCRIPTION:
XS GIS Cut Line= 4
      3461153.64     10539922.05      3462754.35     10539790.11
      3463088.77     10539741.23      3463642.13     10539291.62
#Sta/Elev= 30
  3260.6  496.04  3770.8  490.78  3841.0  490.95  4593.6  484.78  4653.8  482.77
  4824.4  482.64  4884.7  480.83  4890.2  479.30  4895.3  480.35  4944.7  481.21
  4975.6  480.90  4985.7  479.48  4992.9  476.49  4995.6  475.99  4998.9  476.49
  5016.1  480.48  5058.2  481.35  5117.1  480.90  5147.4  479.66  5203.9  481.52
  5512.5  484.65  5626.0  486.80  5704.3  489.43  5733.1  491.76  5753.9  490.44
  5846.6  492.96  5860.9  494.76  5881.7  495.50  5910.5  499.52  5917.7  499.35
#Mann=5,-1,0
  3260.6    0.05       0  4944.7    0.16       0  4992.9    0.07       0
  4998.9    0.16       0  5058.2    0.05       0
Bank Sta=4992.9,4998.9
Exp/Cntr=0.3,0.1

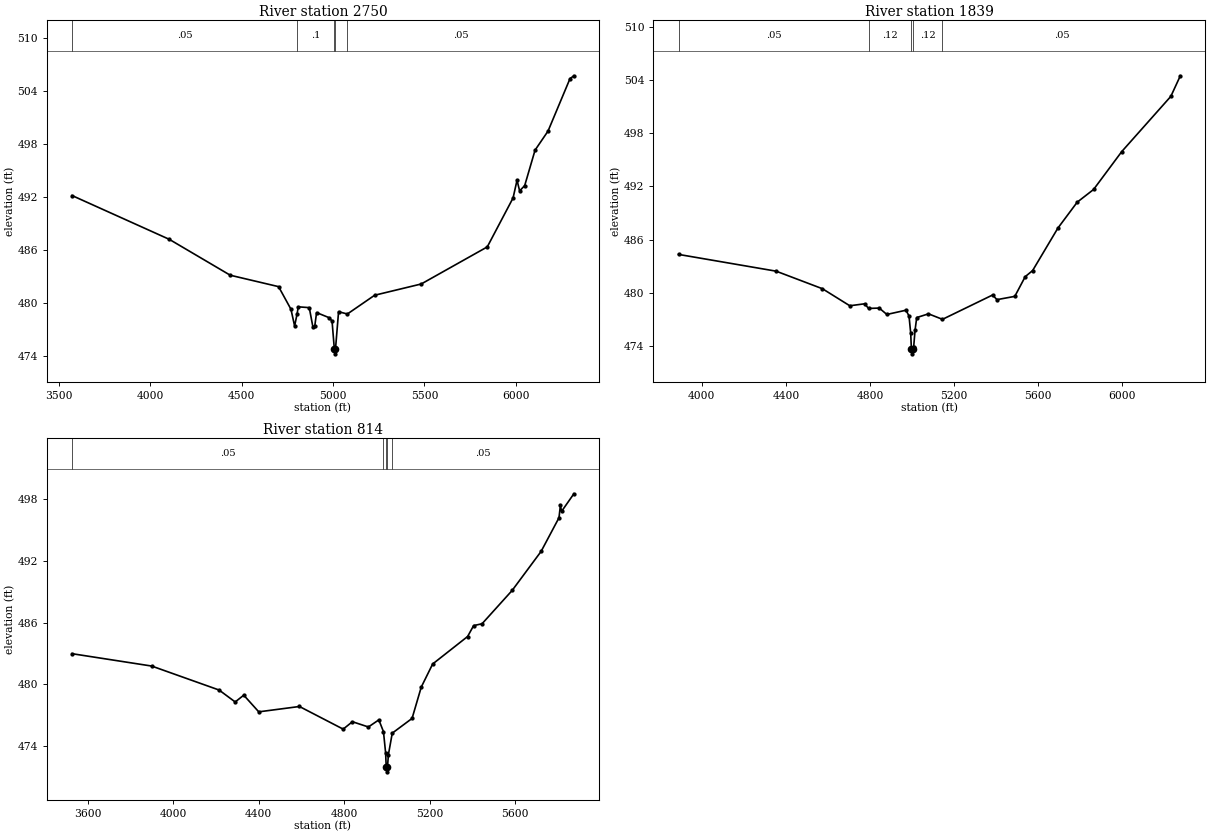
Type RM Length L Ch R = 1,2750,911,911,911
BEGIN DESCRIPTION:
UNT0095 IN SAND CR 2.0
END DESCRIPTION:
XS GIS Cut Line= 4
      3461684.89     10540185.94      3462726.58     10540331.77
      3463236.99     10540297.05      3464032.16     10539422.02
#Sta/Elev= 30
  3571.9  492.15  4104.3  487.20  4437.5  483.15  4701.9  481.86  4769.6  479.31
  4789.7  477.41  4803.0  478.76  4809.7  479.58  4869.8  479.49  4889.9  477.29
  4899.9  477.40  4909.9  478.93  4980.1  478.34  4994.6  477.96  5007.2  474.77
  5009.9  474.27  5013.2  474.77  5030.2  479.03  5078.3  478.77  5227.6  480.89
  5482.4  482.16  5843.9  486.35  5985.1  491.88  6006.7  493.88  6020.9  492.68
  6048.6  493.27  6105.4  497.28  6176.3  499.43  6296.6  505.36  6317.7  505.68
#Mann=5,-1,0
  3571.9    0.05       0  4803.0     0.1       0  5007.2    0.07       0
  5013.2     0.1       0  5078.3    0.05       0
Bank Sta=5007.2,5013.2
Exp/Cntr=0.3,0.1

Type RM Length L Ch R = 1,1839,1025,1025,1025
BEGIN DESCRIPTION:
UNT0095 IN SAND CR 2.1
END DESCRIPTION:
XS GIS Cut Line= 4
      3462388.28     10540597.88      3463351.58     10540647.75
      3463587.69     10540453.30      3464382.82     10539668.59
#Sta/Elev= 30
  3889.4  484.32  4353.8  482.43  4574.1  480.45  4704.3  478.53  4774.4  478.75
  4793.7  478.23  4844.5  478.27  4880.6  477.55  4971.8  478.03  4986.1  477.37
  4994.0  475.46  4997.5  473.61  5000.2  473.11  5003.5  473.61  5008.3  473.91
  5014.8  475.77  5022.7  477.20  5078.7  477.62  5145.3  477.00  5383.4  479.74
  5404.6  479.22  5489.4  479.59  5538.9  481.81  5574.2  482.50  5694.5  487.29
  5786.4  490.21  5864.2  491.64  5998.5  495.92  6231.9  502.14  6277.0  504.46
#Mann=5,-1,0
  3889.4    0.05       0  4793.7    0.12       0  4997.5    0.07       0
  5003.5    0.12       0  5145.3    0.05       0
Bank Sta=4997.5,5003.5
Exp/Cntr=0.3,0.1

Type RM Length L Ch R = 1,814,0,0,0
BEGIN DESCRIPTION:
UNT0095 IN SAND CR 1.0
END DESCRIPTION:
XS GIS Cut Line= 4
      3462690.37     10540730.69      3463817.95     10540806.21
      3464289.08     10540536.63      3464584.20     10539929.02
#Sta/Elev= 30
  3526.3  482.97  3898.9  481.77  4214.3  479.44  4289.7  478.28  4329.8  478.94
  4400.0  477.32  4590.4  477.84  4795.1  475.64  4838.3  476.36  4913.1  475.85
  4962.0  476.54  4983.6  475.40  4993.7  473.34  4996.5  471.99  4999.2  471.49
  5002.5  471.99  5006.8  473.16  5024.8  475.25  5117.5  476.68  5160.6  479.73
  5213.9  481.97  5377.4  484.64  5405.6  485.70  5445.1  485.88  5586.0  489.12
  5721.4  492.91  5805.1  496.18  5811.7  497.38  5817.2  496.80  5874.7  498.51
#Mann=5,-1,0
  3526.3    0.05       0  4983.6    0.16       0  4996.5    0.07       0
  5002.5    0.16       0  5024.8    0.05       0
Bank Sta=4996.5,5002.5
Exp/Cntr=0.3,0.1

Chan Stop Cuts=-1