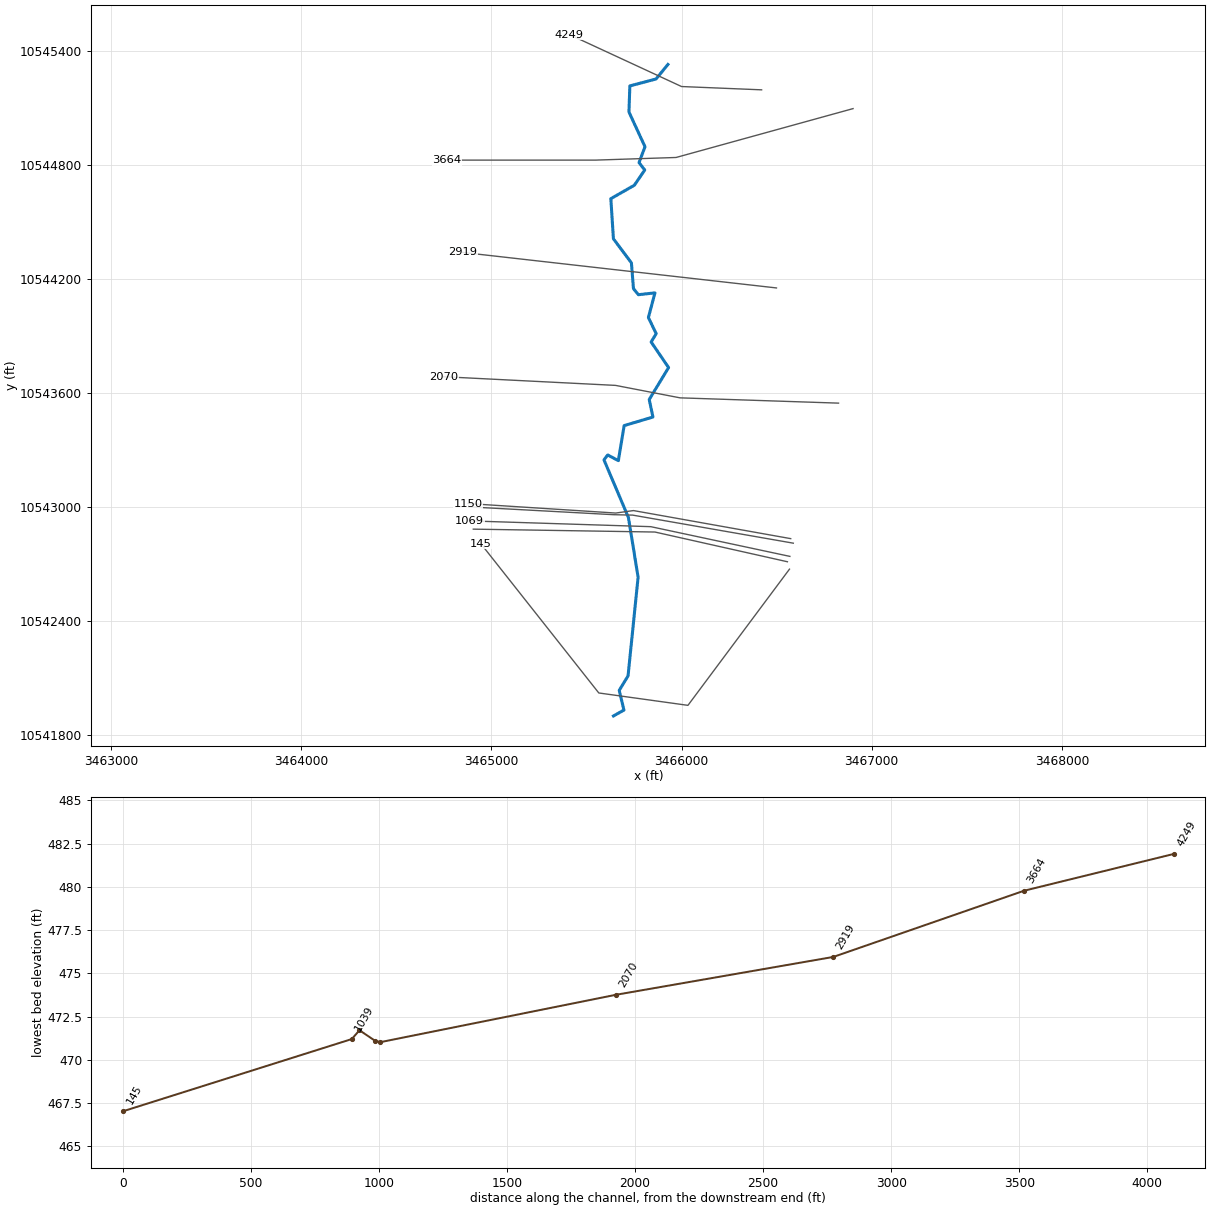
--- UNT0096 IN SAND CR.prj (project) ---

Proj Title=UNT0096 IN SAND CR Base Level Engineering
Current Plan=p01
Default Exp/Contr=0.3,0.1
English Units
Geom File=g01
Flow File=f01
Plan File=p01
BEGIN DESCRIPTION:
UNT0096 IN SAND CR
END DESCRIPTION:

--- UNT0096 IN SAND CR.p01 (plan) ---

Plan Title=Multiple Run
Short Identifier=Multiple
Geom File=g01
Flow File=f01
Subcritical Flow
K Sum by GR= 0
Std Step Tol= 0.01
Critical Tol= 0.01
Num of Std Step Trials= 20
Max Error Tol= 0.3
Flow Tol Ratio= 0.001
Split Flow NTrial= 30
Split Flow Tol= 0.02
Split Flow Ratio= 0.02
Log Output Level= 0
Friction Slope Method= 1
Unsteady Friction Slope Method= 2
Unsteady Bridges Friction Slope Method= 1
Parabolic Critical Depth
Global Vel Dist=  1 , 1 , 1
Global Log Level= 0
CheckData=True
Encroach Param= -1, 0, 0, 0
BEGIN DESCRIPTION:
Multiple Run
END DESCRIPTION:

--- UNT0096 IN SAND CR.f01 (steady flow) ---

Flow Title=Multiple
Number of Profiles=7
Profile Names=10-year,25-year,50-year,1pct_min,100-year,1pct_plu,500-year
River Rch & RM= UNT0096 IN SAND ,Reach-1,4249
     825    1110    1341    1181    1598    2161    2261
Boundary for River Rch & Prof#=UNT0096 IN SAND ,Reach-1,1
Up Type=0
Dn Type=3
Dn Slope=0.005
Boundary for River Rch & Prof#=UNT0096 IN SAND ,Reach-1,2
Up Type=0
Dn Type=3
Dn Slope=0.005
Boundary for River Rch & Prof#=UNT0096 IN SAND ,Reach-1,3
Up Type=0
Dn Type=3
Dn Slope=0.005
Boundary for River Rch & Prof#=UNT0096 IN SAND ,Reach-1,4
Up Type=0
Dn Type=3
Dn Slope=0.005
Boundary for River Rch & Prof#=UNT0096 IN SAND ,Reach-1,5
Up Type=0
Dn Type=3
Dn Slope=0.005
Boundary for River Rch & Prof#=UNT0096 IN SAND ,Reach-1,6
Up Type=0
Dn Type=3
Dn Slope=0.005
Boundary for River Rch & Prof#=UNT0096 IN SAND ,Reach-1,7
Up Type=0
Dn Type=3
Dn Slope=0.005

--- UNT0096 IN SAND CR.g01 (geometry) ---

Geom Title=Existing Conditions

River Reach=UNT0096 IN SAND ,Reach-1
Reach XY= 30
      3465928.49     10545327.29      3465866.08     10545251.08
      3465728.40     10545214.47      3465723.60     10545077.47
      3465807.99     10544894.58      3465776.68     10544811.22
      3465806.76     10544772.41      3465751.93     10544692.28
      3465628.40     10544621.70      3465641.99     10544410.64
      3465736.58     10544284.16      3465747.41     10544148.47
      3465773.48     10544116.80      3465860.35     10544126.39
      3465825.84     10543996.60      3465866.90     10543911.92
      3465840.30     10543868.20      3465932.01     10543733.62
      3465830.22     10543565.58      3465849.78     10543473.53
      3465698.39     10543428.52      3465667.94     10543244.24
      3465611.82     10543274.17      3465592.37     10543248.22
      3465720.88     10542945.31      3465771.76     10542631.41
      3465718.92     10542112.52      3465672.47     10542036.34
      3465697.28     10541932.74      3465642.11     10541901.64

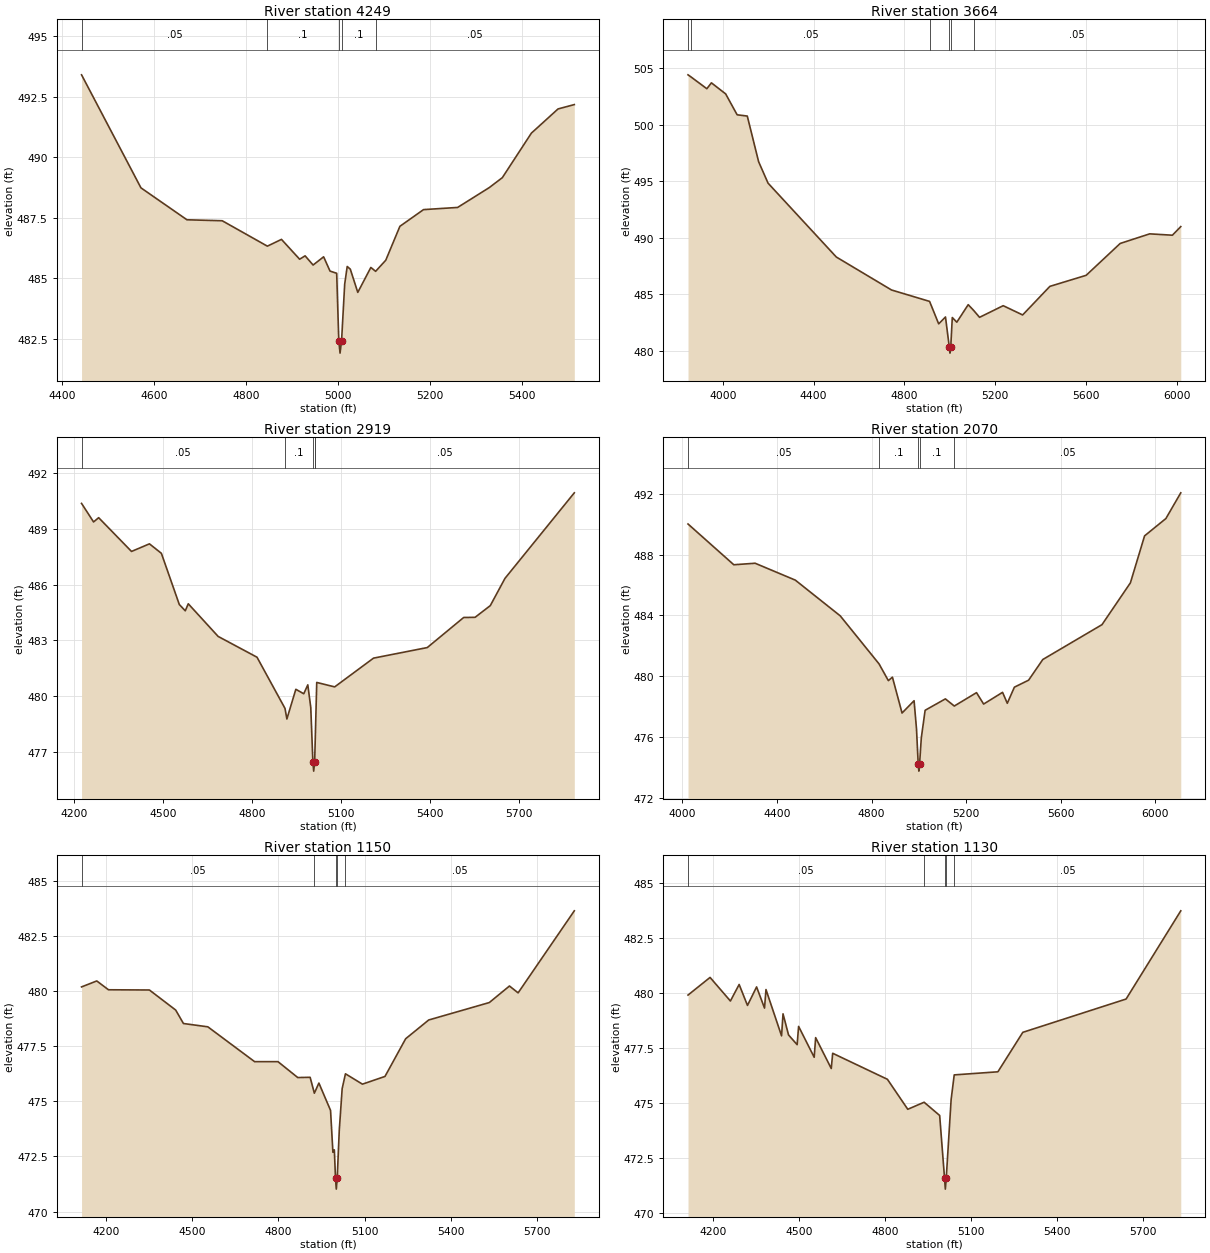
Type RM Length L Ch R = 1,4249,585,585,585
BEGIN DESCRIPTION:
UNT0096 IN SAND CR 5.1
END DESCRIPTION:
XS GIS Cut Line= 3
      3466421.24     10545193.97      3466000.20     10545211.33
      3465409.95     10545484.75
#Sta/Elev= 30
  4442.9  493.41  4572.1  488.74  4672.2  487.42  4748.9  487.38  4847.1  486.33
  4877.8  486.61  4917.3  485.79  4929.2  485.93  4946.6  485.55  4969.5  485.89
  4983.4  485.30  4997.9  485.21  5002.5  482.41  5005.2  481.91  5008.5  482.41
  5015.3  484.76  5020.8  485.49  5027.5  485.38  5043.8  484.42  5072.2  485.45
  5082.6  485.29  5104.7  485.75  5135.4  487.15  5186.8  487.84  5261.0  487.93
  5329.8  488.75  5358.2  489.16  5421.4  491.00  5479.4  492.00  5514.8  492.18
#Mann=5,-1,0
  4442.9    0.05       0  4847.1     0.1       0  5002.5    0.07       0
  5008.5     0.1       0  5082.6    0.05       0
Bank Sta=5002.5,5008.5
Exp/Cntr=0.3,0.1

Type RM Length L Ch R = 1,3664,745,745,745
BEGIN DESCRIPTION:
UNT0096 IN SAND CR 5.0
END DESCRIPTION:
XS GIS Cut Line= 4
      3466902.09     10545095.27      3465971.50     10544838.32
      3465547.88     10544824.43      3464765.15     10544824.43
#Sta/Elev= 30
  3846.1  504.42  3860.1  504.22  3929.1  503.19  3949.2  503.71  4012.1  502.73
  4062.6  500.88  4107.3  500.77  4157.3  496.73  4198.8  494.83  4499.7  488.29
  4743.1  485.37  4910.9  484.36  4951.0  482.37  4981.0  482.98  4998.0  480.28
  5000.8  479.78  5004.0  480.28  5011.0  482.93  5031.0  482.52  5081.1  484.07
  5104.7  483.57  5131.1  482.95  5235.4  483.98  5321.1  483.16  5441.1  485.69
  5601.1  486.67  5751.1  489.49  5881.1  490.34  5981.1  490.22  6018.1  490.98
#Mann=6,-1,0
  3846.1     0.1       0  3860.1    0.05       0  4910.9     0.1       0
  4998.0    0.07       0  5004.0     0.1       0  5104.7    0.05       0
Bank Sta=4998,5004
Exp/Cntr=0.3,0.1

Type RM Length L Ch R = 1,2919,849,849,849
BEGIN DESCRIPTION:
UNT0096 IN SAND CR 3.0
END DESCRIPTION:
XS GIS Cut Line= 2
      3466499.33     10544152.30      3464850.05     10544338.93
#Sta/Elev= 30
  4225.6  490.38  4266.1  489.38  4283.2  489.61  4393.9  487.79  4454.3  488.20
  4494.5  487.69  4554.9  484.93  4575.0  484.59  4585.1  484.97  4685.7  483.21
  4816.6  482.09  4910.9  479.33  4917.2  478.76  4947.4  480.36  4974.1  480.12
  4987.7  480.60  4997.7  479.38  5004.8  476.45  5007.5  475.95  5010.8  476.45
  5010.9  476.51  5017.8  480.73  5078.2  480.49  5209.1  482.04  5390.2  482.61
  5512.7  484.23  5551.2  484.24  5602.4  484.87  5651.9  486.34  5885.4  490.95
#Mann=5,-1,0
  4225.6    0.05       0  4910.9     0.1       0  5004.8    0.07       0
  5010.8     0.1       0  5010.9    0.05       0
Bank Sta=5004.8,5010.8
Exp/Cntr=0.3,0.1

Type RM Length L Ch R = 1,2070,920,920,920
BEGIN DESCRIPTION:
UNT0096 IN SAND CR 2.0
END DESCRIPTION:
XS GIS Cut Line= 4
      3466825.66     10543546.65      3465992.33     10543574.43
      3465653.32     10543639.90      3464749.24     10543685.54
#Sta/Elev= 30
  4023.5  490.01  4217.2  487.33  4307.2  487.43  4477.3  486.32  4667.4  483.97
  4831.6  480.81  4870.9  479.71  4888.1  479.94  4928.8  477.58  4979.7  478.39
  4989.9  476.55  4997.1  474.26  4999.9  473.76  5003.1  474.26  5010.3  475.95
  5026.4  477.76  5112.1  478.51  5149.8  478.04  5243.8  478.92  5273.9  478.17
  5354.0  478.94  5374.0  478.22  5404.0  479.28  5464.1  479.74  5524.2  481.10
  5774.5  483.39  5894.7  486.14  5954.7  489.23  6044.9  490.37  6107.8  492.06
#Mann=5,-1,0
  4023.5    0.05       0  4831.6     0.1       0  4997.1    0.07       0
  5003.1     0.1       0  5149.8    0.05       0
Bank Sta=4997.1,5003.1
Exp/Cntr=0.3,0.1

Type RM Length L Ch R = 1,1150,20,20,20
BEGIN DESCRIPTION:
UNT0096 IN SAND CR 1.3
END DESCRIPTION:
XS GIS Cut Line= 4
      3466574.21     10542834.16      3465747.38     10542981.73
      3465654.06     10542968.71      3464877.18     10543018.62
#Sta/Elev= 30
  4115.6  480.19  4168.5  480.46  4209.2  480.06  4351.4  480.05  4442.8  479.14
  4469.7  478.53  4554.5  478.38  4717.1  476.80  4798.3  476.80  4867.0  476.08
  4910.1  476.09  4924.7  475.37  4940.5  475.83  4981.0  474.59  4989.2  472.69
  4994.2  472.80  4998.2  471.52  5001.0  471.02  5004.2  471.52  5011.3  473.68
  5021.4  475.58  5032.8  476.25  5091.8  475.78  5170.2  476.13  5242.1  477.84
  5322.2  478.69  5532.7  479.48  5602.8  480.23  5632.9  479.92  5828.2  483.64
#Mann=5,-1,0
  4115.6    0.05       0  4924.7     0.1       0  4998.2    0.07       0
  5004.2     0.1       0  5032.8    0.05       0
Bank Sta=4998.2,5004.2
Exp/Cntr=0.3,0.1

Type RM Length L Ch R = 1,1130,61,61,61
BEGIN DESCRIPTION:
UNT0096 IN SAND CR 1.0
END DESCRIPTION:
XS GIS Cut Line= 4
      3466587.92     10542810.29      3465743.04     10542957.86
      3465643.21     10542960.03      3464881.44     10543001.26
#Sta/Elev= 30
  4112.5  479.90  4189.5  480.70  4260.5  479.63  4291.0  480.38  4320.1  479.43
  4351.9  480.27  4379.6  479.31  4384.7  480.15  4439.1  478.05  4444.2  479.05
  4463.5  478.09  4493.5  477.65  4498.6  478.48  4553.0  477.08  4558.1  477.97
  4612.6  476.57  4617.6  477.26  4808.7  476.08  4879.8  474.72  4936.8  475.04
  4991.1  474.44  5008.1  471.60  5010.9  471.10  5014.1  471.60  5031.1  475.16
  5041.9  476.28  5194.4  476.42  5281.4  478.21  5642.0  479.72  5832.9  483.72
#Mann=5,-1,0
  4112.5    0.05       0  4936.8     0.1       0  5008.1    0.07       0
  5014.1     0.1       0  5041.9    0.05       0
Bank Sta=5008.1,5014.1
Exp/Cntr=0.3,0.1

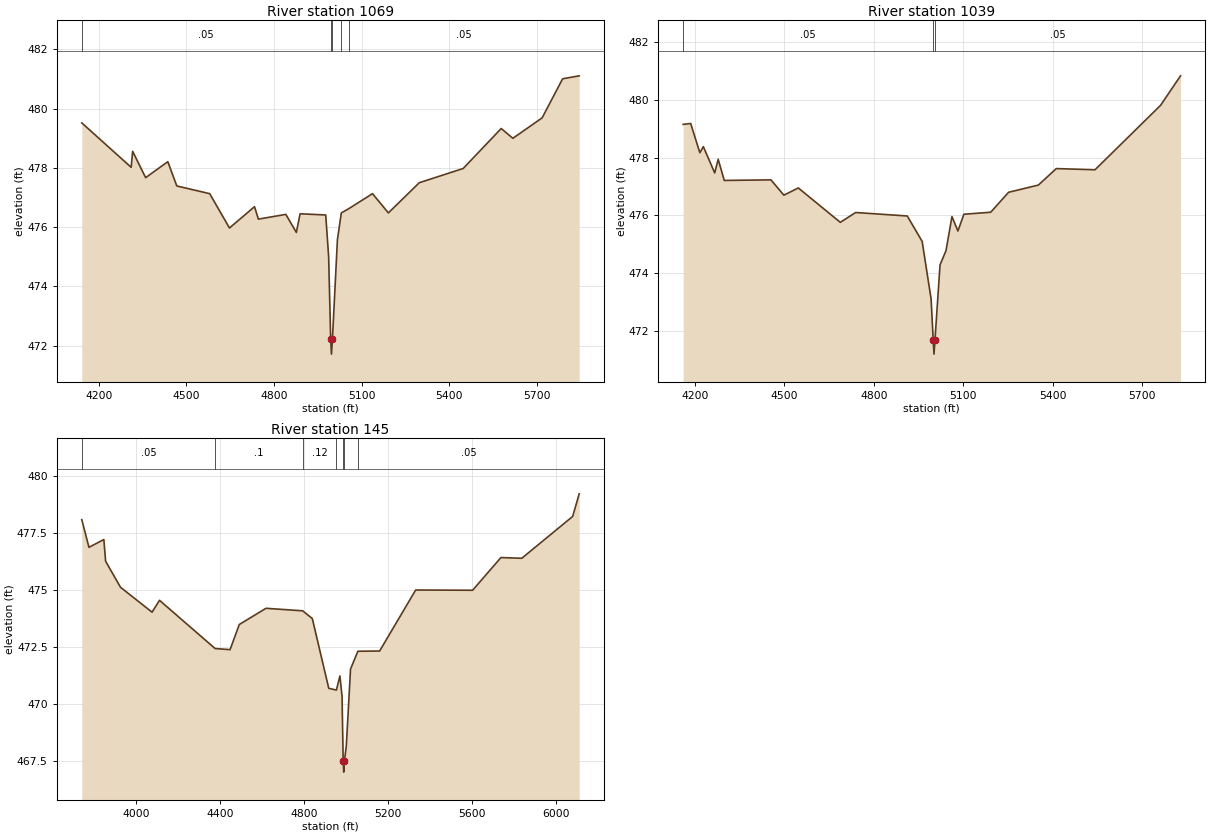
Type RM Length L Ch R = 1,1069,30,30,30
BEGIN DESCRIPTION:
UNT0096 IN SAND CR 1.1
END DESCRIPTION:
XS GIS Cut Line= 3
      3466569.91     10542740.83      3465838.52     10542897.09
      3464885.40     10542927.42
#Sta/Elev= 30
  4142.4  479.52  4311.3  478.02  4316.4  478.56  4360.8  477.67  4436.7  478.21
  4467.4  477.39  4579.9  477.13  4647.6  475.97  4733.2  476.69  4746.6  476.27
  4840.4  476.43  4876.4  475.82  4889.2  476.45  4976.8  476.41  4986.8  475.01
  4993.8  472.21  4996.5  471.71  4999.8  472.21  5016.8  475.57  5030.2  476.48
  5055.3  476.62  5136.8  477.13  5191.2  476.48  5296.9  477.50  5447.0  477.98
  5577.1  479.33  5617.1  479.00  5717.1  479.69  5787.2  481.01  5843.9  481.11
#Mann=5,-1,0
  4142.4    0.05       0  4993.8    0.04       0  4999.8    0.05       0
  5030.2     0.1       0  5055.3    0.05       0
Bank Sta=4993.8,4999.8
Exp/Cntr=0.3,0.1

Type RM Length L Ch R = 1,1039,894,894,894
BEGIN DESCRIPTION:
UNT0096 IN SAND CR 1.2
END DESCRIPTION:
XS GIS Cut Line= 3
      3466556.85     10542712.63      3465860.22     10542868.88
      3464905.18     10542884.04
#Sta/Elev= 30
  4160.0  479.15  4185.4  479.18  4216.1  478.17  4227.8  478.38  4266.0  477.47
  4277.6  477.94  4298.1  477.21  4454.7  477.23  4498.1  476.70  4546.5  476.95
  4687.5  475.76  4738.8  476.10  4912.1  475.98  4962.1  475.10  4992.1  473.11
  4999.1  471.70  5001.8  471.20  5005.1  471.70  5022.1  474.29  5042.1  474.78
  5062.1  475.96  5082.1  475.46  5102.1  476.04  5192.1  476.11  5252.1  476.80
  5352.1  477.05  5412.1  477.62  5542.1  477.58  5762.2  479.81  5829.1  480.83
#Mann=3,-1,0
  4160.0    0.05       0  4999.1    0.04       0  5005.1    0.05       0
Bank Sta=4999.1,5005.1
Exp/Cntr=0.3,0.1

Type RM Length L Ch R = 1,145,0,0,0
BEGIN DESCRIPTION:
UNT0096 IN SAND CR 3.1
END DESCRIPTION:
XS GIS Cut Line= 4
      3466567.71     10542673.74      3466033.84     10541957.57
      3465565.09     10542022.67      3464945.04     10542807.48
#Sta/Elev= 30
  3742.7  478.07  3776.8  476.86  3847.7  477.20  3856.1  476.25  3927.0  475.11
  4077.1  474.02  4112.5  474.54  4376.9  472.43  4448.2  472.38  4492.0  473.48
  4619.2  474.19  4793.6  474.08  4839.6  473.74  4917.7  470.69  4954.2  470.61
  4970.9  471.23  4981.0  470.34  4986.4  467.52  4989.1  467.02  4992.4  467.52
  5001.2  468.15  5021.4  471.53  5056.3  472.31  5159.8  472.32  5331.4  474.99
  5602.3  474.98  5736.9  476.41  5836.3  476.38  6078.3  478.21  6109.4  479.20
#Mann=7,-1,0
  3742.7    0.05       0  4376.9     0.1       0  4793.6    0.12       0
  4954.2    0.16       0  4986.4    0.07       0  4992.4    0.16       0
  5056.3    0.05       0
Bank Sta=4986.4,4992.4
Exp/Cntr=0.3,0.1

Chan Stop Cuts=-1