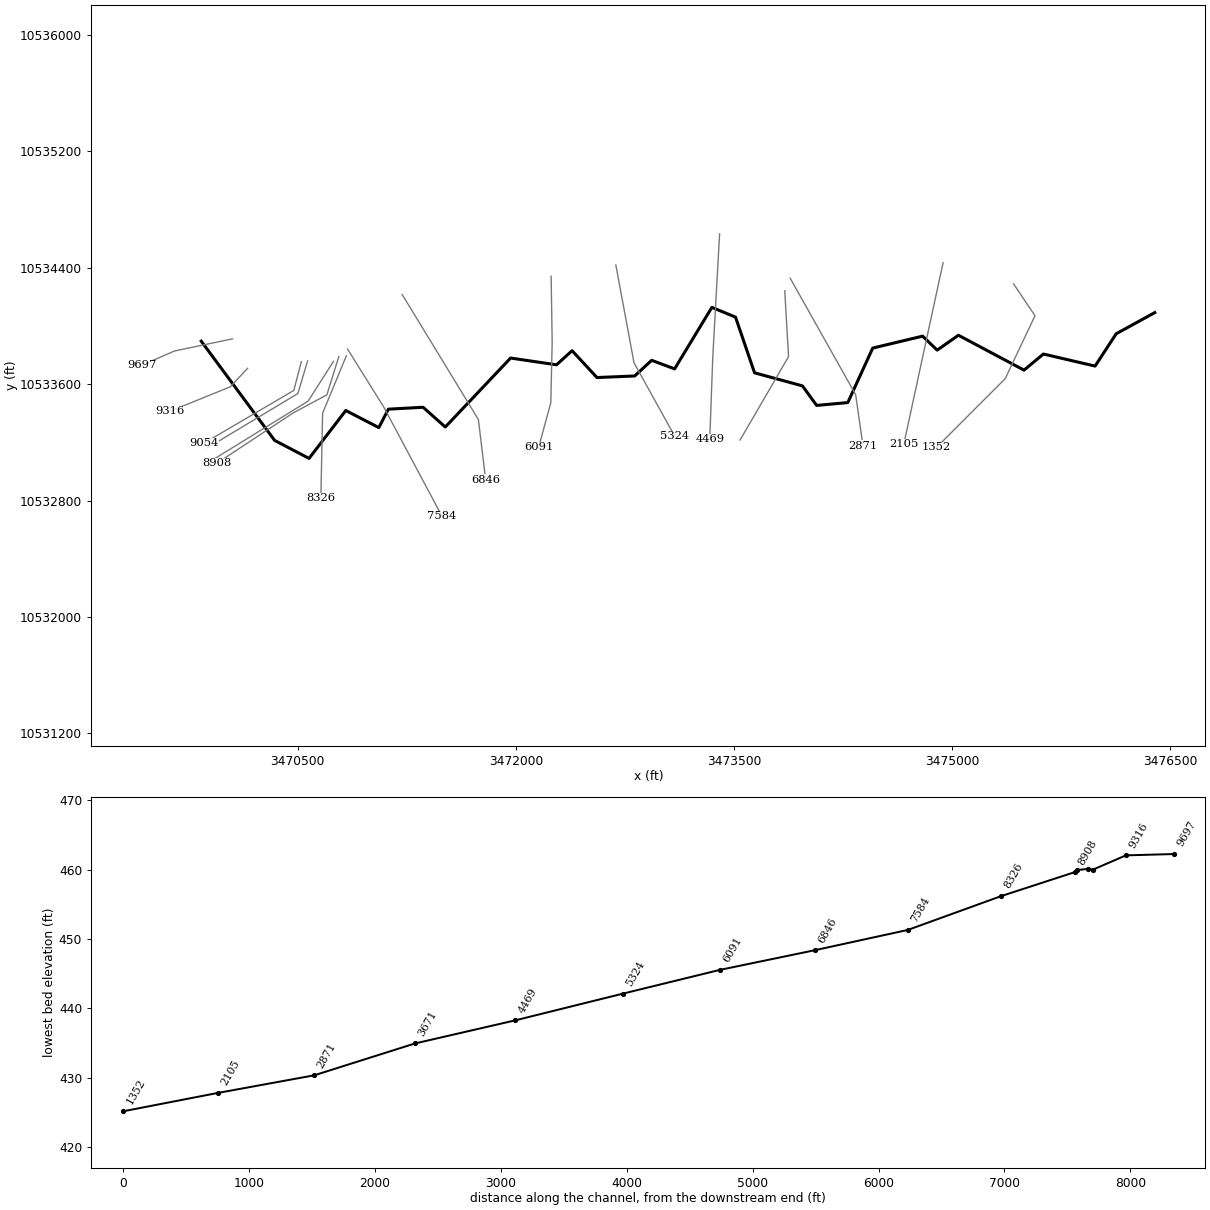
--- UNT0097 IN SAND CR.prj (project) ---

Proj Title=UNT0097 IN SAND CR Base Level Engineering
Current Plan=p01
Default Exp/Contr=0.3,0.1
English Units
Geom File=g01
Flow File=f01
Plan File=p01
Y Axis Title=Elevation
X Axis Title(PF)=Main Channel Distance
X Axis Title(XS)=Station
BEGIN DESCRIPTION:
UNT0097 IN SAND CR
END DESCRIPTION:
DSS Export Rating Curves= 0
DSS Export Rating Curve Sorted= 0
DSS Export Volume Flow Curves= 0
DXF OffsetX= 0
DXF OffsetY= 0
DXF ScaleX= 1
DXF ScaleY= 10

--- UNT0097 IN SAND CR.p01 (plan) ---

Plan Title=Multiple Run
Short Identifier=Multiple
Geom File=g01
Flow File=f01
Subcritical Flow
K Sum by GR= 0
Std Step Tol= 0.01
Critical Tol= 0.01
Num of Std Step Trials= 20
Max Error Tol= 0.3
Flow Tol Ratio= 0.001
Split Flow NTrial= 30
Split Flow Tol= 0.02
Split Flow Ratio= 0.02
Log Output Level= 0
Friction Slope Method= 1
Unsteady Friction Slope Method= 2
Unsteady Bridges Friction Slope Method= 1
Parabolic Critical Depth
Global Vel Dist=  1 , 1 , 1
Global Log Level= 0
CheckData=True
Encroach Param= -1, 0, 0, 0
BEGIN DESCRIPTION:
Multiple Run
END DESCRIPTION:

--- UNT0097 IN SAND CR.f01 (steady flow) ---

Flow Title=Multiple
Number of Profiles=7
Profile Names=10-year,25-year,50-year,1pct_min,100-year,1pct_plu,500-year
River Rch & RM= UNT0097 IN SAND ,Reach-1,9697
     940    1281    1559    1386    1874    2534    2696
River Rch & RM= UNT0097 IN SAND ,Reach-1,7584
    1401    1950    2408    2167    2930    3963    4327
Boundary for River Rch & Prof#=UNT0097 IN SAND ,Reach-1,1
Up Type=0
Dn Type=3
Dn Slope=0.005
Boundary for River Rch & Prof#=UNT0097 IN SAND ,Reach-1,2
Up Type=0
Dn Type=3
Dn Slope=0.005
Boundary for River Rch & Prof#=UNT0097 IN SAND ,Reach-1,3
Up Type=0
Dn Type=3
Dn Slope=0.005
Boundary for River Rch & Prof#=UNT0097 IN SAND ,Reach-1,4
Up Type=0
Dn Type=3
Dn Slope=0.005
Boundary for River Rch & Prof#=UNT0097 IN SAND ,Reach-1,5
Up Type=0
Dn Type=3
Dn Slope=0.005
Boundary for River Rch & Prof#=UNT0097 IN SAND ,Reach-1,6
Up Type=0
Dn Type=3
Dn Slope=0.005
Boundary for River Rch & Prof#=UNT0097 IN SAND ,Reach-1,7
Up Type=0
Dn Type=3
Dn Slope=0.005

--- UNT0097 IN SAND CR.g01 (geometry) ---

Geom Title=Existing Conditions
Program Version=4.10

River Reach=UNT0097 IN SAND ,Reach-1
Reach XY= 30
      3469836.59     10533895.13      3470340.85      10533213.7
      3470577.77     10533089.74      3470830.31     10533418.92
      3471057.49     10533301.47      3471123.23     10533428.16
      3471361.91     10533441.05      3471514.51     10533305.54
      3471963.37     10533779.37      3472279.16     10533732.89
      3472386.13     10533829.94      3472557.18     10533645.39
      3472816.77     10533656.16      3472933.14     10533763.75
      3473090.96     10533704.88      3473347.24     10534127.57
      3473509.69     10534060.56       3473640.7     10533677.77
      3473969.72      10533588.2      3474067.41     10533453.87
      3474281.69     10533473.45      3474453.16     10533847.86
      3474796.04      10533929.8      3474896.19     10533833.73
      3475042.16       10533936.      3475493.07     10533696.38
       3475626.5     10533806.88      3475981.87     10533724.15
      3476126.87     10533946.26      3476392.11     10534091.64

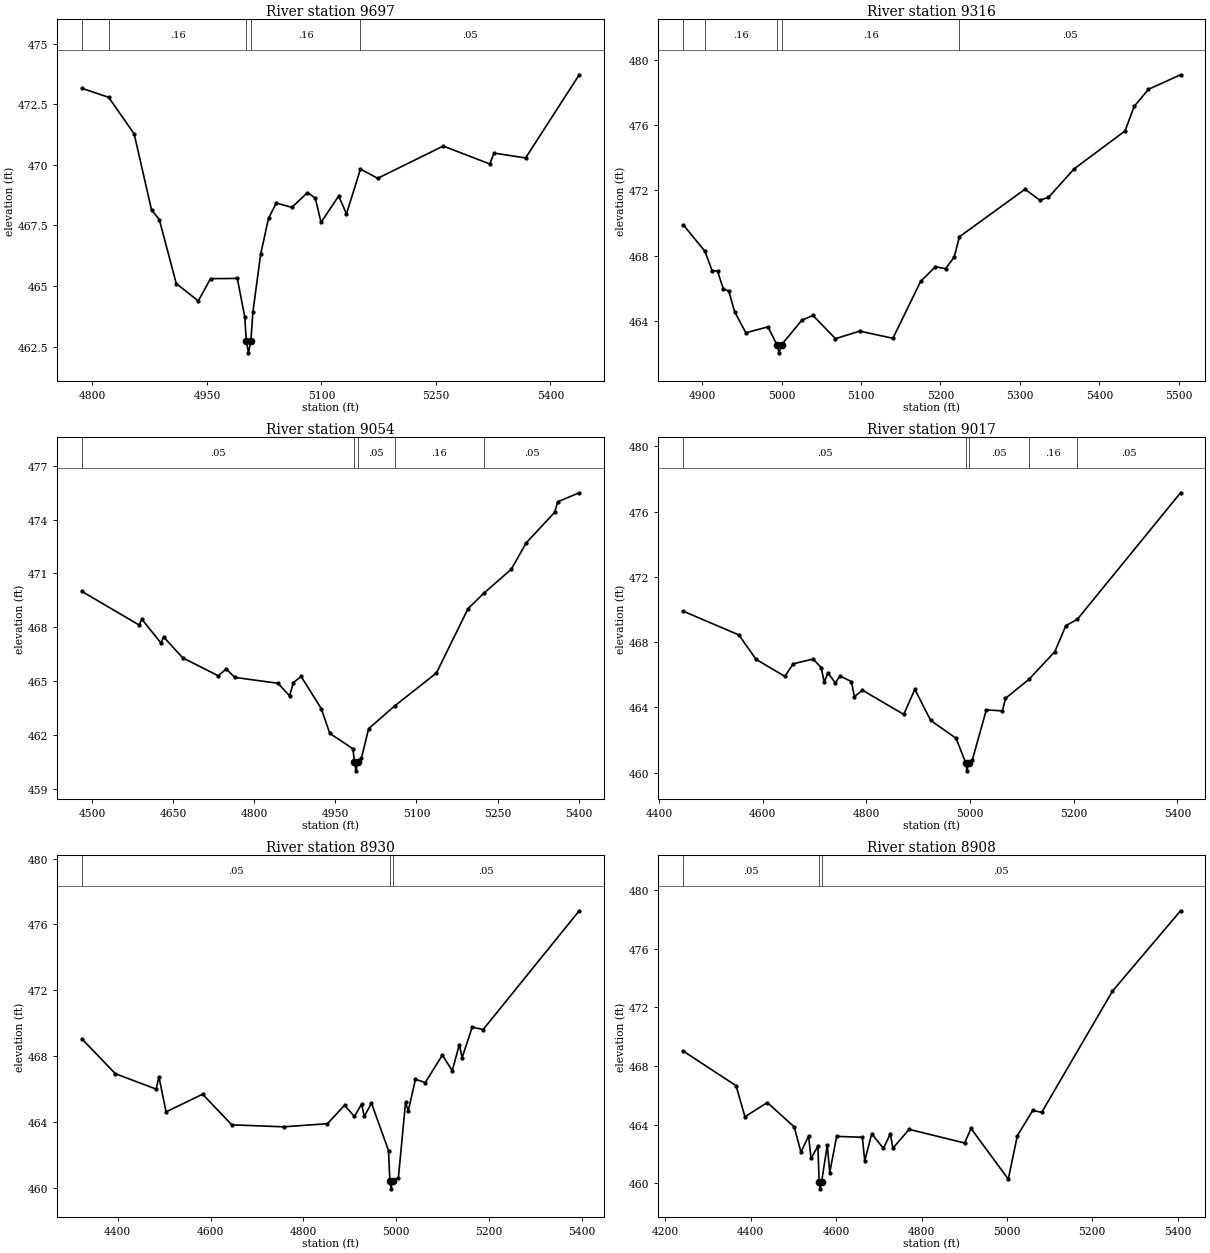
Type RM Length L Ch R = 1 ,9697    ,381,381,381
BEGIN DESCRIPTION:
UNT0097 IN SAND CR 15.0
END DESCRIPTION:
XS GIS Cut Line= 3
       3470051.3     10533911.24      3469652.84     10533827.91
      3469428.88     10533730.25
#Sta/Elev= 30
  4786.3  473.15  4821.3  472.78  4854.7  471.27  4877.4  468.14  4887.6  467.74
  4909.8   465.1  4938.7  464.38  4954.7   465.3  4989.8  465.31  4999.5  463.73
  5001.6  462.74  5004.4  462.24  5007.6  462.74  5010.2  463.92  5020.4  466.31
  5030.7  467.79  5040.9  468.42  5061.3  468.24  5081.7  468.85    5092  468.62
  5099.5  467.62  5122.6  468.71  5132.8  467.97  5151.1  469.82  5173.7  469.44
  5259.6  470.77  5320.6  470.03  5326.1  470.48  5367.5  470.28  5437.7  473.71
#Mann= 5 ,-1 , 0
  4786.3     .05       0  4821.3     .16       0  5001.6     .07       0
  5007.6     .16       0  5151.1     .05       0
Bank Sta=5001.6,5007.6
XS Rating Curve= 0 ,0
Exp/Cntr=0.3,0.1

Type RM Length L Ch R = 1 ,9316    ,262,262,262
BEGIN DESCRIPTION:
UNT0097 IN SAND CR 15.1
END DESCRIPTION:
XS GIS Cut Line= 3
      3470155.68     10533708.99      3470035.92     10533581.42
      3469617.97     10533412.16
#Sta/Elev= 30
  4876.3  469.89  4903.5  468.27  4912.5  467.09  4919.4  467.05  4926.7  465.97
  4933.5  465.84  4940.8  464.58    4955  463.28  4982.9  463.64    4994  462.55
  4996.8  462.05    5000  462.55  5025.4  464.04  5039.5  464.34  5067.8  462.92
  5098.5  463.38  5140.1  462.94    5175  466.42  5193.7  467.33  5206.4   467.2
  5217.2  467.91  5223.9  469.16  5306.4  472.07  5325.1   471.4  5335.9  471.57
  5368.3  473.32  5432.3  475.64  5443.8  477.14  5461.8  478.19  5502.2  479.08
#Mann= 5 ,-1 , 0
  4876.3     .05       0  4903.5     .16       0    4994     .07       0
    5000     .16       0  5223.9     .05       0
Bank Sta=4994,5000
XS Rating Curve= 0 ,0
Exp/Cntr=0.3,0.1

Type RM Length L Ch R = 1 ,9054    ,37,37,37
BEGIN DESCRIPTION:
UNT0097 IN SAND CR 13.2
END DESCRIPTION:
XS GIS Cut Line= 3
      3470525.09      10533754.8        3470473.     10533556.86
      3469856.04     10533194.66
#Sta/Elev= 30
    4481  469.99  4586.7  468.12  4591.9  468.44  4627.1  467.12  4632.2  467.45
  4667.4  466.29  4733.1  465.29  4747.9  465.67  4763.6   465.2  4843.7  464.87
  4865.2  464.17  4872.2  464.91  4886.6  465.25  4923.8  463.46  4939.5  462.08
  4982.4  461.22  4985.2  460.49    4988  459.99  4991.2  460.49  4998.1  460.69
  5011.4  462.34  5059.7  463.61  5136.8  465.44  5195.4  469.03  5224.2  469.88
  5275.5  471.23  5302.8  472.69  5355.6   474.4  5361.4  474.99  5401.1  475.49
#Mann= 5 ,-1 , 0
    4481     .05       0  4985.2     .03       0  4991.2     .05       0
  5059.7     .16       0  5224.2     .05       0
Bank Sta=4985.2,4991.2
XS Rating Curve= 0 ,0
Exp/Cntr=0.3,0.1

Type RM Length L Ch R = 1 ,9017    ,87,87,87
BEGIN DESCRIPTION:
UNT0097 IN SAND CR 13.0
END DESCRIPTION:
XS GIS Cut Line= 3
      3470567.54     10533759.59      3470501.13      10533535.6
      3469878.73      10533161.9
#Sta/Elev= 30
  4446.6  469.89  4553.8  468.44  4587.1  466.94  4642.6   465.9  4658.7  466.67
  4697.1  466.96  4712.7  466.44  4718.5  465.55  4725.7  466.11  4739.9   465.5
  4749.1  465.92    4771  465.58  4776.8  464.66  4792.3  465.05    4872  463.57
  4893.4   465.1    4924   463.2  4973.1   462.1  4991.4  460.61  4994.2  460.11
  4997.4  460.61  5004.2  460.76  5031.4  463.85  5062.5  463.78  5068.3  464.55
  5113.4  465.71  5163.5  467.41  5184.9  469.01  5207.1   469.4  5406.2  477.15
#Mann= 5 ,-1 , 0
  4446.6     .05       0  4991.4     .03       0  4997.4     .05       0
  5113.4     .16       0  5207.1     .05       0
Bank Sta=4991.4,4997.4
XS Rating Curve= 0 ,0
Exp/Cntr=0.3,0.1

Type RM Length L Ch R = 1 ,8930    ,22,22,22
BEGIN DESCRIPTION:
UNT0097 IN SAND CR 13.1
END DESCRIPTION:
XS GIS Cut Line= 3
       3470745.9     10533756.93      3470571.44     10533483.51
      3469935.92     10533092.32
#Sta/Elev= 30
  4323.1  469.04  4394.9  466.93  4482.9  465.99  4488.8  466.74  4504.1  464.61
  4582.8  465.68  4645.6  463.82  4757.1   463.7  4851.7  463.89  4888.4  465.01
  4909.7  464.33  4925.1  465.08    4931  464.33  4946.4  465.14  4983.1  462.26
    4986  460.43  4988.7  459.93    4992  460.43  5004.4  460.61  5019.8  465.18
  5025.6  464.66  5041.1  466.59  5062.3  466.39    5099  468.06  5120.3  467.11
  5135.7   468.7  5141.6   467.9  5163.3  469.76  5186.8  469.61  5393.7  476.83
#Mann= 3 ,-1 , 0
  4323.1     .05       0    4986     .03       0    4992     .05       0
Bank Sta=4986,4992
XS Rating Curve= 0 ,0
Exp/Cntr=0.3,0.1

Type RM Length L Ch R = 1 ,8908    ,582,582,582
BEGIN DESCRIPTION:
UNT0097 IN SAND CR 13.3
END DESCRIPTION:
XS GIS Cut Line= 4
      3470782.39     10533789.53      3470700.35     10533526.48
      3470467.27     10533401.48      3469945.64     10533057.62
#Sta/Elev= 30
    4242  469.02  4365.6  466.66  4386.4  464.54  4438.8  465.51  4501.7  463.85
  4517.5  462.13  4535.5  463.22  4541.1   461.7  4557.4  462.53  4560.1  460.12
  4562.8  459.62  4566.1  460.12  4579.3  462.61    4585  460.73  4601.2   463.2
  4661.4  463.14    4667  461.53  4683.3  463.37  4710.9  462.38  4727.1  463.39
  4732.8  462.39    4771  463.68  4900.9  462.75    4916  463.74  5003.3  460.28
  5024.4  463.24  5060.5  464.97  5081.6  464.84  5247.2  473.11  5406.8   478.6
#Mann= 3 ,-1 , 0
    4242     .05       0  4560.1     .03       0  4566.1     .05       0
Bank Sta=4560.1,4566.1
XS Rating Curve= 0 ,0
Exp/Cntr=0.3,0.1

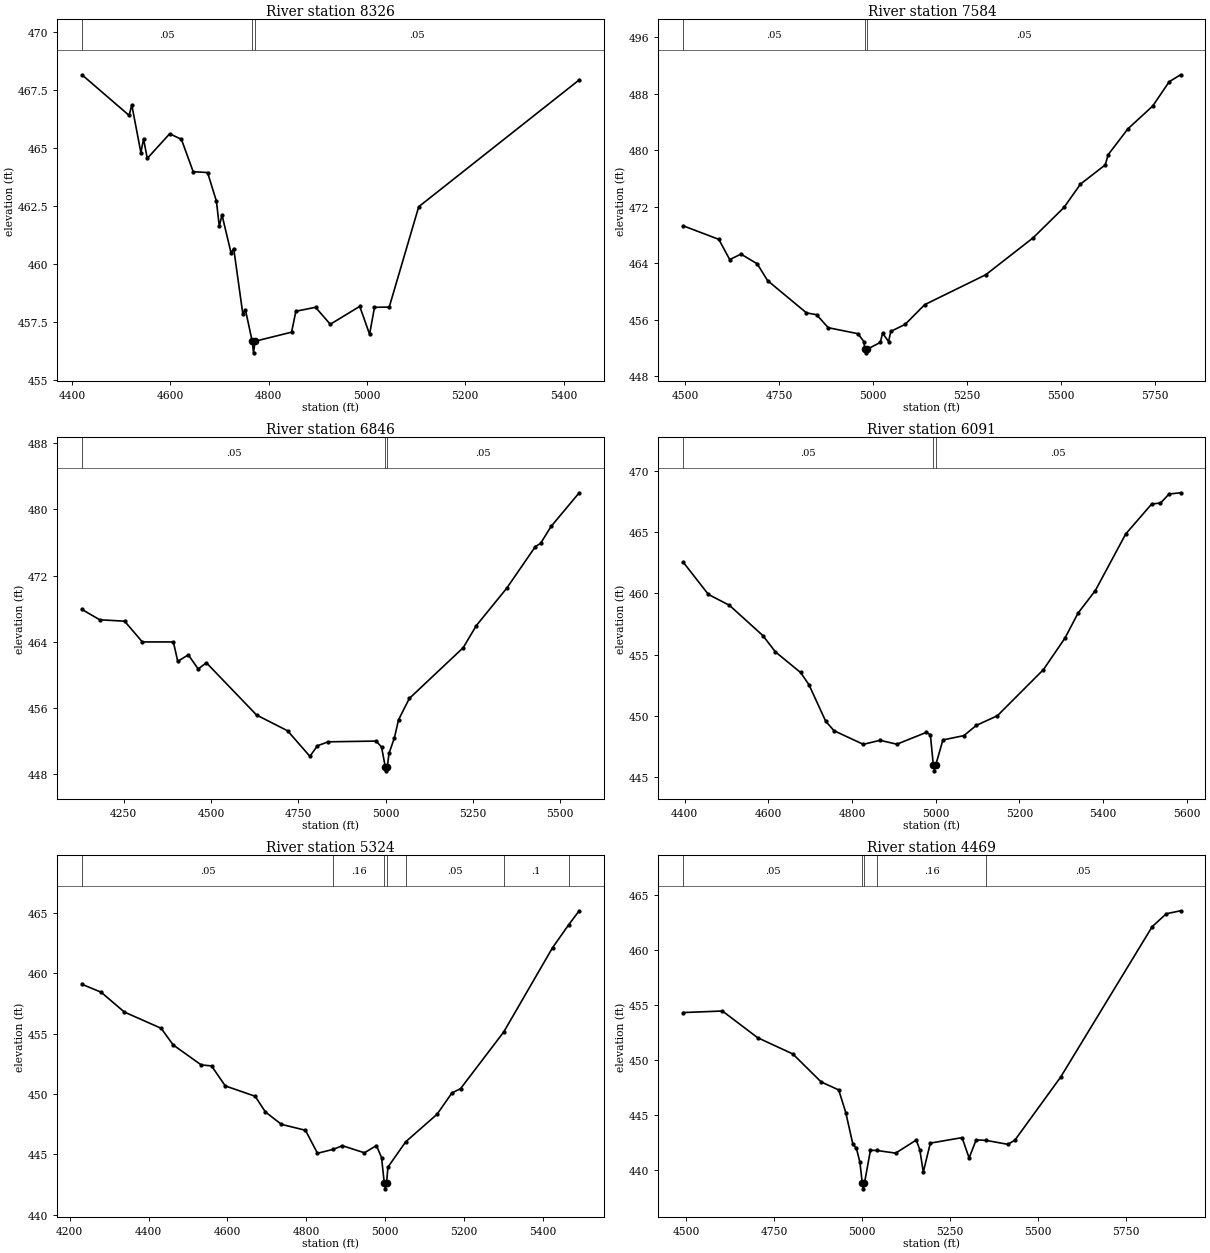
Type RM Length L Ch R = 1 ,8326    ,742,742,742
BEGIN DESCRIPTION:
UNT0097 IN SAND CR 11.1
END DESCRIPTION:
XS GIS Cut Line= 3
      3470834.19     10533794.45      3470670.99     10533400.34
      3470658.87     10532815.13
#Sta/Elev= 30
    4420  468.15    4516   466.4  4521.4  466.85  4539.9   464.8  4545.3  465.39
  4552.9  464.55  4598.5  465.61  4622.4  465.37  4646.3  463.98  4675.6  463.94
  4693.6  462.71  4699.5  461.62  4704.9  462.12  4723.4  460.48  4728.8  460.67
  4747.3  457.86  4752.7  458.03  4766.4  456.68  4769.1  456.18  4772.4  456.68
  4846.6  457.07  4855.3  457.97  4895.3  458.14  4925.3  457.41  4985.3  458.18
  5005.3  456.98  5015.3  458.14  5045.3  458.15  5105.3  462.47  5431.9  467.93
#Mann= 3 ,-1 , 0
    4420     .05       0  4766.4     .03       0  4772.4     .05       0
Bank Sta=4766.4,4772.4
XS Rating Curve= 0 ,0
Exp/Cntr=0.3,0.1

Type RM Length L Ch R = 1 ,7584    ,738,738,738
BEGIN DESCRIPTION:
UNT0097 IN SAND CR 11.0
END DESCRIPTION:
XS GIS Cut Line= 3
      3470842.09     10533841.67      3471092.11     10533441.64
      3471492.09     10532691.67
#Sta/Elev= 30
  4495.4  469.27  4589.8  467.36  4618.7   464.5  4648.7  465.27  4691.8   463.9
  4719.5  461.52  4822.7  456.96  4849.8  456.69  4880.5  454.86  4959.5  454.01
  4975.3  452.89  4977.9   451.8  4980.7   451.3  4983.9   451.8  5019.2  452.78
  5024.9  454.08  5041.1   452.9  5046.8  454.33  5085.1  455.33  5137.1  458.12
    5299  462.34  5425.1  467.57  5507.2  471.87  5551.1  475.18    5617   477.9
  5624.5  479.33  5677.2     483  5743.1  486.23    5787  489.67  5817.1  490.65
#Mann= 3 ,-1 , 0
  4495.4     .05       0  4977.9    .035       0  4983.9     .05       0
Bank Sta=4977.9,4983.9
XS Rating Curve= 0 ,0
Exp/Cntr=0.3,0.1

Type RM Length L Ch R = 1 ,6846    ,755,755,755
BEGIN DESCRIPTION:
UNT0097 IN SAND CR 9.0
END DESCRIPTION:
XS GIS Cut Line= 3
       3471218.1     10534215.96      3471742.11      10533356.6
      3471792.11     10532941.62
#Sta/Elev= 30
  4130.4   467.9  4181.3  466.65  4252.6  466.48  4303.3  463.97  4392.3  463.97
  4404.8  461.62    4435  462.41  4463.4   460.7  4486.8  461.45  4630.6  455.13
  4719.6  453.22  4783.5  450.13  4804.8  451.41  4835.8  451.89  4973.3  451.98
  4988.7  451.25  4999.2  448.88  5001.9  448.38  5005.2  448.88    5010  450.49
  5025.5  452.37  5037.3  454.55  5068.1  457.13  5222.5  463.27    5260  465.94
  5347.1  470.46  5429.2   475.5  5444.1  475.88  5474.3  477.94  5554.9  482.01
#Mann= 3 ,-1 , 0
  4130.4     .05       0  4999.2     .03       0  5005.2     .05       0
Bank Sta=4999.2,5005.2
XS Rating Curve= 0 ,0
Exp/Cntr=0.3,0.1

Type RM Length L Ch R = 1 ,6091    ,767,767,767
BEGIN DESCRIPTION:
UNT0097 IN SAND CR 7.0
END DESCRIPTION:
XS GIS Cut Line= 4
      3472242.11      10534341.6      3472249.34     10533887.85
      3472239.77     10533471.86      3472155.98     10533165.31
#Sta/Elev= 30
  4397.1  462.54  4457.1  459.92  4507.1  459.04  4587.1  456.57  4617.1  455.24
  4677.1  453.56  4697.1  452.57  4737.1  449.59  4757.1  448.81  4827.1   447.7
  4867.1  448.03  4907.1  447.71  4977.2  448.67  4987.2  448.49  4994.2  446.04
  4996.9  445.54  5000.2  446.04  5017.2  448.06  5067.2  448.41  5097.2  449.25
  5147.2  450.03  5257.2  453.79  5308.7  456.36  5339.8  458.39  5381.3  460.24
  5453.8  464.85    5516   467.3  5536.8  467.37  5557.5  468.11  5584.8  468.21
#Mann= 3 ,-1 , 0
  4397.1     .05       0  4994.2    .035       0  5000.2     .05       0
Bank Sta=4994.2,5000.2
XS Rating Curve= 0 ,0
Exp/Cntr=0.3,0.1

Type RM Length L Ch R = 1 ,5324    ,855,855,855
BEGIN DESCRIPTION:
UNT0097 IN SAND CR 6.0
END DESCRIPTION:
XS GIS Cut Line= 3
      3472686.84     10534419.11      3472811.84     10533747.22
      3473092.12     10533241.62
#Sta/Elev= 30
  4231.2   459.1  4279.5  458.45  4338.7   456.8  4432.1  455.45  4462.6  454.07
  4533.8  452.41  4559.9  452.33  4594.8  450.67  4670.6  449.81  4696.5  448.51
  4737.2  447.48  4798.2  446.99  4828.7  445.08    4869  445.41  4891.8  445.71
  4947.8  445.12  4978.2  445.72  4991.3  444.72    4998  442.63  5000.8  442.13
    5004  442.63  5007.4  443.93  5052.4  446.03  5132.1  448.32  5169.9  450.09
  5191.6  450.44  5301.3  455.15  5425.1  462.14    5466  464.04  5492.7   465.2
#Mann= 7 ,-1 , 0
  4231.2     .05       0    4869     .16       0    4998     .07       0
    5004     .16       0  5052.4     .05       0  5301.3      .1       0
    5466     .05       0
Bank Sta=4998,5004
XS Rating Curve= 0 ,0
Exp/Cntr=0.3,0.1

Type RM Length L Ch R = 1 ,4469    ,798,798,798
BEGIN DESCRIPTION:
UNT0097 IN SAND CR 5.0
END DESCRIPTION:
XS GIS Cut Line= 3
      3473400.38      10534632.6      3473353.51     10533788.89
      3473332.68     10533221.18
#Sta/Elev= 30
  4491.3  454.32  4602.4  454.46  4702.6  452.03  4802.7  450.55  4882.9  448.01
  4932.9  447.28    4953  445.22    4973  442.36    4983  441.98    4993  440.74
    5000  438.78  5002.8  438.28    5006  438.78  5023.1  441.79  5041.5  441.77
  5094.7  441.53  5153.3  442.72  5163.3  441.85  5173.3  439.81  5193.3  442.44
  5283.5  442.94  5303.5  441.09  5323.5  442.73  5351.6  442.69  5413.6  442.33
  5433.6  442.71  5563.7  448.45  5823.9  462.14  5863.9  463.31  5904.4  463.58
#Mann= 5 ,-1 , 0
  4491.3     .05       0    5000    .035       0    5006     .05       0
  5041.5     .16       0  5351.6     .05       0
Bank Sta=5000,5006
XS Rating Curve= 0 ,0
Exp/Cntr=0.3,0.1

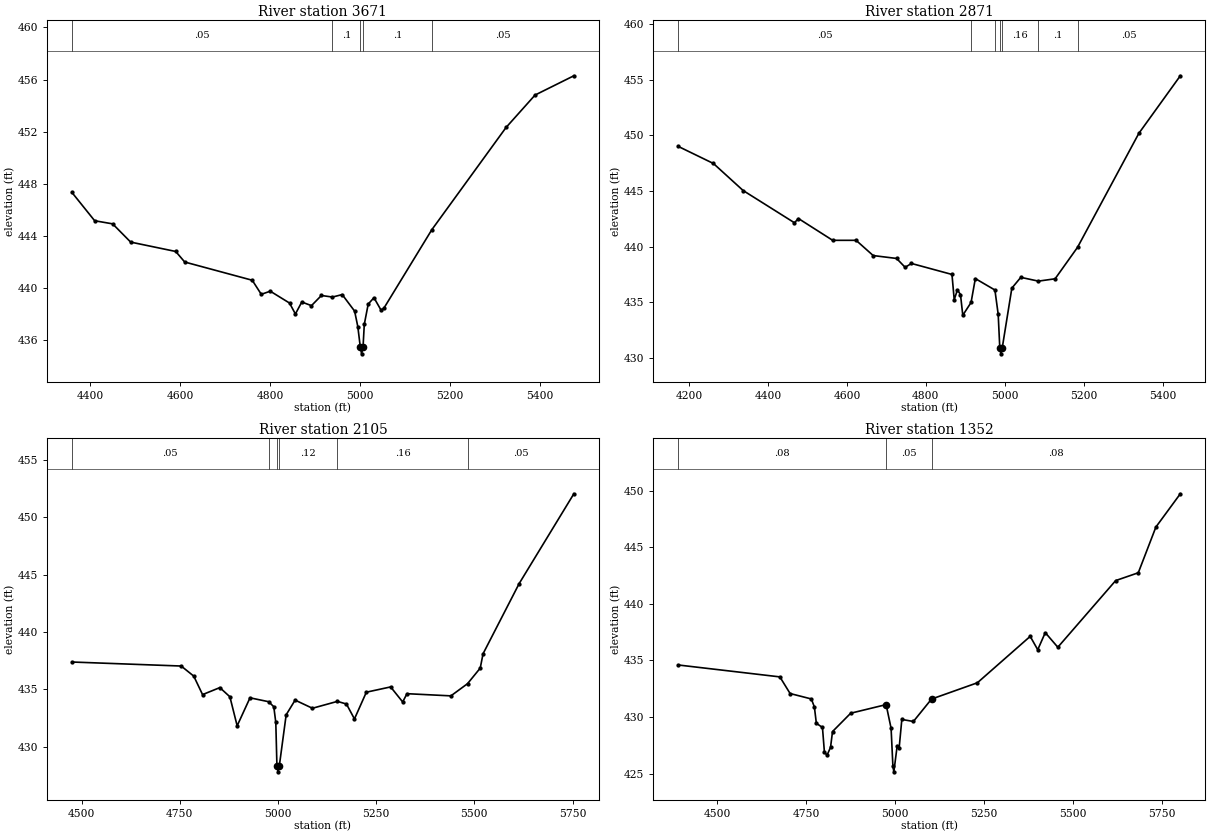
Type RM Length L Ch R = 1 ,3671    ,800,800,800
BEGIN DESCRIPTION:
UNT0097 IN SAND CR 4.0
END DESCRIPTION:
XS GIS Cut Line= 3
       3473848.3     10534242.02      3473874.34     10533788.89
      3473541.22     10533216.33
#Sta/Elev= 30
  4359.3  447.33  4409.8  445.16  4449.8  444.92  4489.9  443.52  4590.1   442.8
  4610.1  441.99  4760.3  440.59  4780.4  439.51  4800.4  439.75  4843.2  438.84
  4856.3     438  4870.5  438.92    4892  438.64  4914.1  439.42  4938.7   439.3
  4960.4  439.49    4988  438.22  4995.1  437.03  5000.7  435.44  5003.5  434.94
  5006.7  435.44  5009.5   437.2  5018.2  438.76    5031  439.25  5046.7   438.3
    5053  438.44  5159.7  444.47  5324.8  452.32  5389.3  454.81  5475.6  456.29
#Mann= 5 ,-1 , 0
  4359.3     .05       0  4938.7      .1       0  5000.7     .07       0
  5006.7      .1       0  5159.7     .05       0
Bank Sta=5000.7,5006.7
XS Rating Curve= 0 ,0
Exp/Cntr=0.3,0.1

Type RM Length L Ch R = 1 ,2871    ,766,766,766
BEGIN DESCRIPTION:
UNT0097 IN SAND CR 3.0
END DESCRIPTION:
XS GIS Cut Line= 3
      3473885.74     10534327.69      3474335.76     10533527.65
      3474385.76     10533177.62
#Sta/Elev= 30
  4173.2     449  4261.9  447.47  4337.1  445.04  4467.1  442.14  4477.3  442.52
    4564  440.56  4623.3  440.56  4666.6  439.19  4725.9  438.93  4747.6  438.13
  4763.5  438.48  4866.2  437.49  4871.9  435.22    4880   436.1  4887.8  435.68
  4893.6  433.82  4914.6  434.97  4925.4  437.12    4975  436.09  4983.3  433.91
  4987.4  430.85  4990.2  430.35  4993.4  430.85  5017.9  436.26  5040.6  437.23
  5085.1  436.89  5127.5   437.1  5184.3  439.93  5339.6  450.18  5444.7  455.36
#Mann= 7 ,-1 , 0
  4173.2     .05       0  4914.6      .1       0    4975     .16       0
  4987.4     .07       0  4993.4     .16       0  5085.1      .1       0
  5184.3     .05       0
Bank Sta=4987.4,4993.4
XS Rating Curve= 0 ,0
Exp/Cntr=0.3,0.1

Type RM Length L Ch R = 1 ,2105    ,753,753,753
BEGIN DESCRIPTION:
UNT0097 IN SAND CR 2.0
END DESCRIPTION:
XS GIS Cut Line= 2
      3474936.85     10534434.76      3474666.21     10533185.65
#Sta/Elev= 30
  4475.3  437.38  4753.5  437.03  4785.5  436.15  4807.9  434.54  4851.9  435.15
  4877.5  434.35    4896  431.82  4928.7  434.26  4976.3  433.92  4989.3  433.48
  4994.4  432.11  4997.3  428.31  5000.1  427.81  5003.3  428.31  5020.8  432.78
  5043.6  434.06  5087.7  433.35  5151.3  433.95  5174.3  433.72  5194.7  432.42
    5225  434.75  5286.8  435.21  5317.5   433.9  5328.5  434.62  5440.3  434.43
  5482.6  435.49    5515  436.85  5522.2   438.1  5614.2  444.22  5753.4  452.04
#Mann= 6 ,-1 , 0
  4475.3     .05       0  4976.3     .12       0  4997.3     .07       0
  5003.3     .12       0  5151.3     .16       0  5482.6     .05       0
Bank Sta=4997.3,5003.3
XS Rating Curve= 0 ,0
Exp/Cntr=0.3,0.1

Type RM Length L Ch R = 1 ,1352    ,0,0,0
BEGIN DESCRIPTION:
UNT0097 IN SAND CR 1.0
END DESCRIPTION:
XS GIS Cut Line= 4
      3475420.74     10534289.84      3475568.66     10534070.07
      3475363.93     10533637.85      3474891.35     10533165.27
#Sta/Elev= 30
    4391   434.6  4676.3  433.55  4705.1  432.08  4764.8   431.6  4773.4  430.89
  4778.9  429.45  4796.1  429.08  4801.6  426.89  4809.1  426.64  4818.8  427.32
  4824.4  428.72  4875.5  430.34  4975.1   431.1  4989.1  429.01  4994.2  425.66
  4996.9  425.16  5006.3  427.48  5011.9  427.31  5019.3  429.79  5051.8  429.61
  5102.8  431.59  5231.8  433.03  5380.3  437.13  5401.5  435.95  5422.7  437.46
    5458  436.17  5620.7  442.06  5684.3  442.75  5733.8  446.79  5802.5  449.73
#Mann= 3 , 0 , 0
    4391     .08       0  4975.1     .05       0  5102.8     .08       0
Bank Sta=4975.1,5102.8
XS Rating Curve= 0 ,0
Exp/Cntr=0.3,0.1

Chan Stop Cuts=-1
Use User Specified Reach Order=0
Composite Channel Slope=5