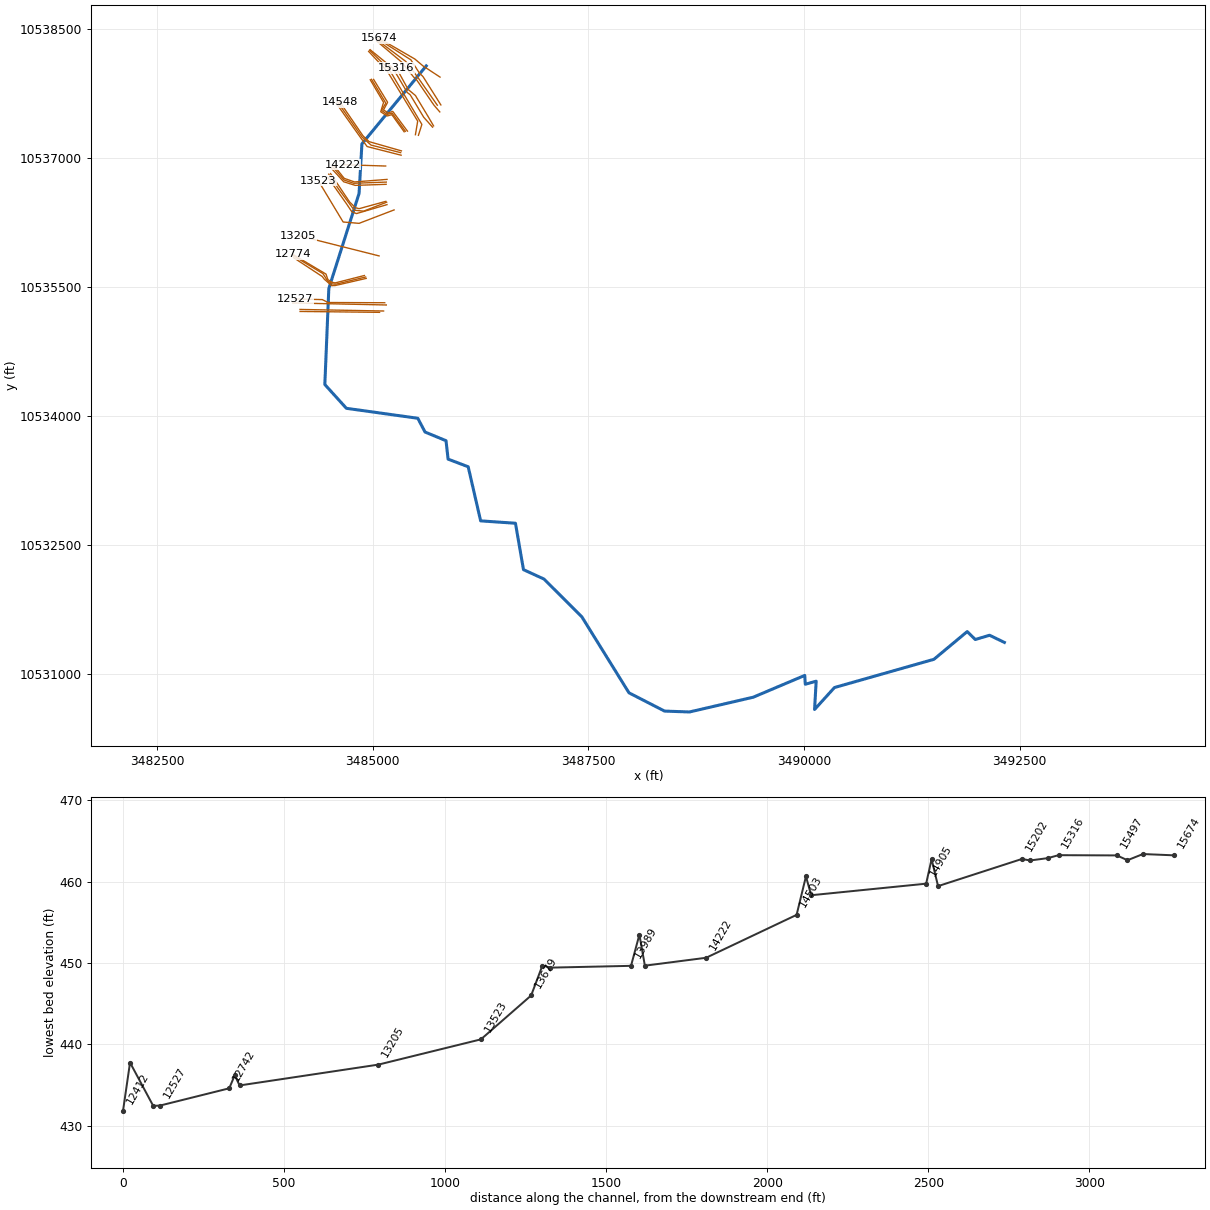
--- UNT0098 IN SAND CR.prj (project) ---

Proj Title=UNT0098 IN SAND CR Base Level Engineering
Current Plan=p01
Default Exp/Contr=0.3,0.1
English Units
Geom File=g01
Flow File=f01
Plan File=p01
Y Axis Title=Elevation
X Axis Title(PF)=Main Channel Distance
X Axis Title(XS)=Station
BEGIN DESCRIPTION:
UNT0098 IN SAND CR
END DESCRIPTION:
DSS Export Rating Curves= 0
DSS Export Rating Curve Sorted= 0
DSS Export Volume Flow Curves= 0
DXF OffsetX= 0
DXF OffsetY= 0
DXF ScaleX= 1
DXF ScaleY= 10

--- UNT0098 IN SAND CR.p01 (plan) ---

Plan Title=Multiple Run
Short Identifier=Multiple
Geom File=g01
Flow File=f01
Subcritical Flow
K Sum by GR= 0
Std Step Tol= 0.01
Critical Tol= 0.01
Num of Std Step Trials= 20
Max Error Tol= 0.3
Flow Tol Ratio= 0.001
Split Flow NTrial= 30
Split Flow Tol= 0.02
Split Flow Ratio= 0.02
Log Output Level= 0
Friction Slope Method= 1
Unsteady Friction Slope Method= 2
Unsteady Bridges Friction Slope Method= 1
Parabolic Critical Depth
Global Vel Dist=  1 , 1 , 1
Global Log Level= 0
CheckData=True
Encroach Param= -1, 0, 0, 0
BEGIN DESCRIPTION:
Multiple Run
END DESCRIPTION:

--- UNT0098 IN SAND CR.f01 (steady flow) ---

Flow Title=Multiple
Number of Profiles=7
Profile Names=10-year,25-year,50-year,1pct_min,100-year,1pct_plu,500-year
River Rch & RM= UNT0098 IN SAND ,Reach-1,15674
     294     372     432     367     497     672     652
River Rch & RM= UNT0098 IN SAND ,Reach-1,11977
     668     892    1073     943    1275    1725    1793
River Rch & RM= UNT0098 IN SAND ,Reach-1,7023
    1007    1370    1665    1476    1996    2700    2859
Boundary for River Rch & Prof#=UNT0098 IN SAND ,Reach-1,1
Up Type=0
Dn Type=3
Dn Slope=0.005
Boundary for River Rch & Prof#=UNT0098 IN SAND ,Reach-1,2
Up Type=0
Dn Type=3
Dn Slope=0.005
Boundary for River Rch & Prof#=UNT0098 IN SAND ,Reach-1,3
Up Type=0
Dn Type=3
Dn Slope=0.005
Boundary for River Rch & Prof#=UNT0098 IN SAND ,Reach-1,4
Up Type=0
Dn Type=3
Dn Slope=0.005
Boundary for River Rch & Prof#=UNT0098 IN SAND ,Reach-1,5
Up Type=0
Dn Type=3
Dn Slope=0.005
Boundary for River Rch & Prof#=UNT0098 IN SAND ,Reach-1,6
Up Type=0
Dn Type=3
Dn Slope=0.005
Boundary for River Rch & Prof#=UNT0098 IN SAND ,Reach-1,7
Up Type=0
Dn Type=3
Dn Slope=0.005

--- UNT0098 IN SAND CR.g01 (geometry) ---

Geom Title=Existing Conditions
Program Version=4.10

River Reach=UNT0098 IN SAND ,Reach-1
Reach XY= 30
      3485619.08     10538067.28      3484873.33      10537160.4
      3484840.35     10536584.01      3484489.65     10535478.11
      3484443.34     10534361.41      3484693.37     10534084.71
      3485521.17     10533968.88      3485605.38     10533808.91
       3485848.7     10533707.98      3485872.62      10533493.8
      3486105.65     10533404.77      3486250.08     10532775.54
      3486653.74     10532747.98       3486746.8     10532208.19
      3486985.42     10532098.26      3487424.34     10531658.15
      3487969.93     10530775.73      3488382.76     10530563.01
      3488671.56     10530552.91      3489410.91     10530724.54
      3490008.07     10530977.84      3490014.68     10530875.37
      3490140.64     10530910.85      3490122.11     10530581.64
      3490352.61     10530836.86      3491506.08     10531165.33
      3491891.99     10531487.84      3491985.74     10531395.65
      3492151.36     10531445.13      3492323.23     10531361.69

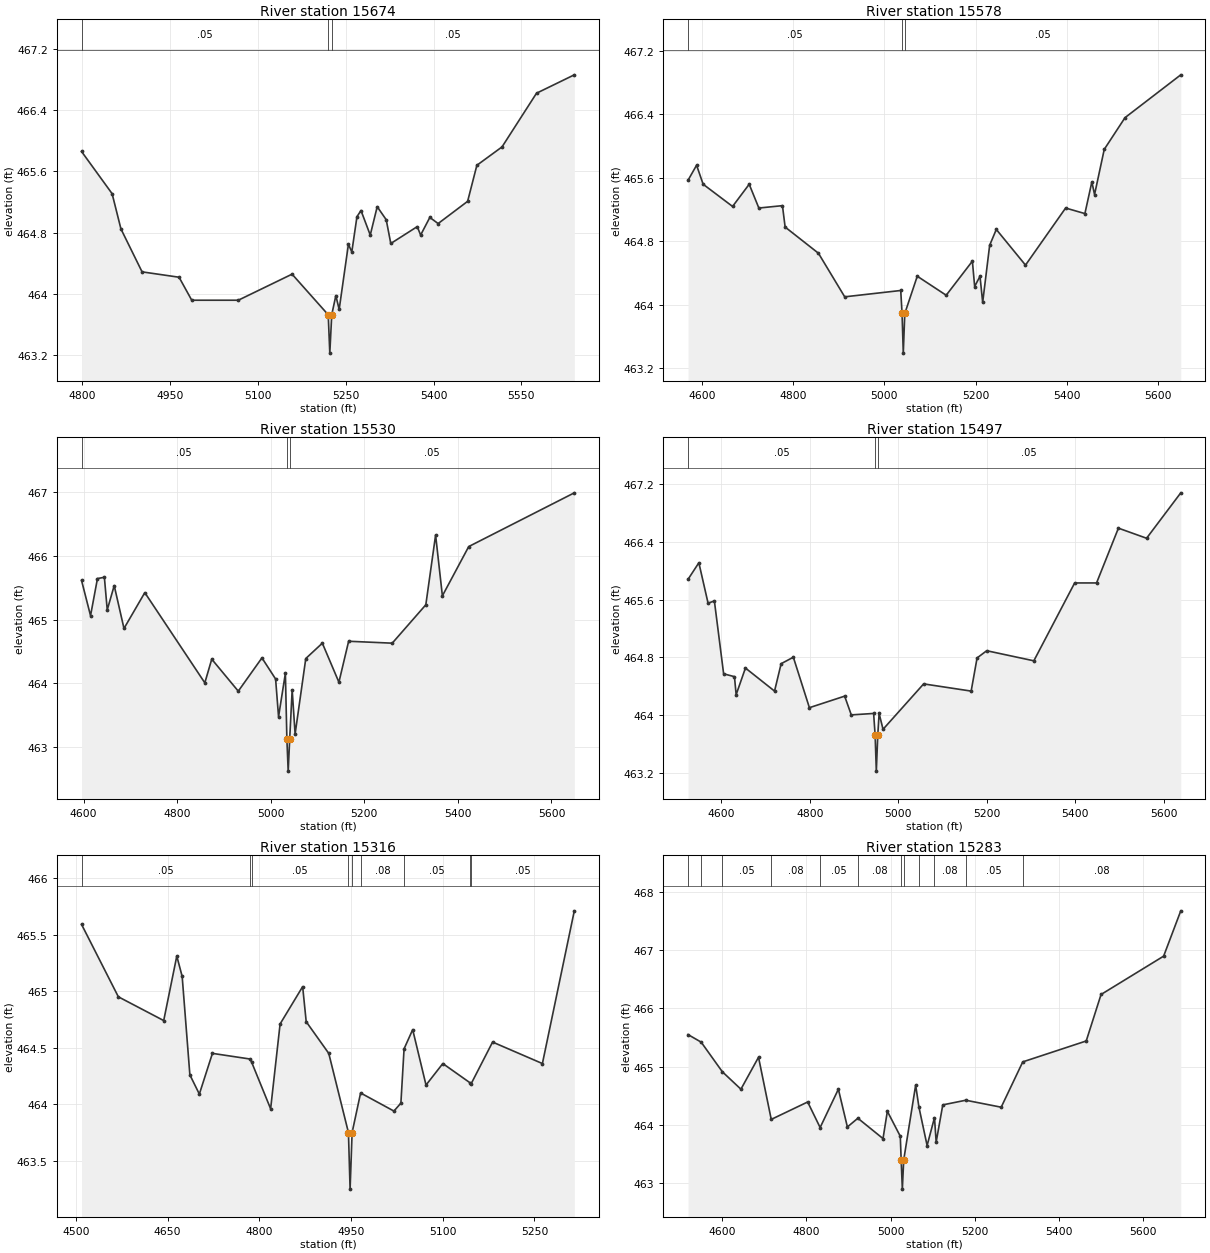
Type RM Length L Ch R = 1 ,15674   ,96,96,96
BEGIN DESCRIPTION:
UNT01215 IN SAND CR 7.8
END DESCRIPTION:
XS GIS Cut Line= 4
      3485779.38     10537937.08      3485581.43     10538067.31
      3485487.68     10538147.17      3485070.74      10538388.8
#Sta/Elev= 30
  4798.6  465.86  4850.8  465.31  4865.9  464.85    4902  464.29  4965.2  464.22
  4986.9  463.92  5066.4  463.92  5158.3  464.26  5220.1  463.73  5222.8  463.23
  5226.1  463.73  5233.1  463.98  5238.8   463.8  5254.6  464.65  5260.4  464.55
  5269.2  465.01  5276.1  465.09  5291.9  464.77  5303.8  465.14  5319.2  464.97
    5327  464.66  5372.2  464.88    5378  464.77  5393.7     465  5407.9  464.92
  5458.3  465.21  5474.1  465.68  5517.1  465.92    5576  466.62  5640.6  466.86
#Mann= 3 ,-1 , 0
  4798.6     .05       0  5220.1     .03       0  5226.1     .05       0
Bank Sta=5220.1,5226.1
XS Rating Curve= 0 ,0
Exp/Cntr=0.3,0.1

Type RM Length L Ch R = 1 ,15578   ,48,48,48
BEGIN DESCRIPTION:
UNT01215 IN SAND CR 7.7
END DESCRIPTION:
XS GIS Cut Line= 5
       3485788.9     10537613.53      3485583.82     10537940.14
      3485536.07     10537990.05      3485441.67     10538137.62
      3485060.35     10538380.11
#Sta/Elev= 30
  4568.8  465.57  4587.6  465.76    4602  465.52  4666.6  465.24  4703.1  465.52
  4724.3  465.22  4776.1  465.25    4782  464.98  4855.1  464.65  4912.8   464.1
  5035.8  464.18  5038.7  463.89  5041.4  463.39  5044.7  463.89  5072.1  464.36
  5135.6  464.12  5193.1  464.55  5198.1  464.23  5209.8  464.36  5215.7  464.03
    5231  464.75  5245.6  464.95  5309.7   464.5  5397.8  465.22  5440.1  465.15
  5455.4  465.55  5461.3  465.39  5482.6  465.96  5528.2  466.36  5650.6   466.9
#Mann= 3 ,-1 , 0
  4568.8     .05       0  5038.7     .03       0  5044.7     .05       0
Bank Sta=5038.7,5044.7
XS Rating Curve= 0 ,0
Exp/Cntr=0.3,0.1

Type RM Length L Ch R = 1 ,15530   ,33,33,33
BEGIN DESCRIPTION:
UNT01215 IN SAND CR 7.5
END DESCRIPTION:
XS GIS Cut Line= 4
      3485747.64     10537610.31      3485523.05     10537932.54
      3485381.99     10538119.18      3485041.23     10538375.78
#Sta/Elev= 30
  4595.5  465.61  4614.7  465.06  4629.5  465.64  4644.3  465.66  4650.4  465.15
  4665.3  465.53  4686.2  464.86  4730.7  465.42    4859  464.01  4873.8  464.38
  4930.5  463.88  4981.1   464.4  5010.3  464.07  5016.6  463.48  5031.2  464.16
  5034.4  463.13  5037.2  462.63  5040.4  463.13  5045.7   463.9    5052  463.21
  5074.8  464.39  5110.2  464.63  5145.6  464.02  5166.4  464.66  5259.6  464.63
  5331.4  465.23  5352.3  466.32  5366.8  465.37  5423.1  466.14  5648.8  466.98
#Mann= 3 ,-1 , 0
  4595.5     .05       0  5034.4     .03       0  5040.4     .05       0
Bank Sta=5034.4,5040.4
XS Rating Curve= 0 ,0
Exp/Cntr=0.3,0.1

Type RM Length L Ch R = 1 ,15497   ,181,181,181
BEGIN DESCRIPTION:
UNT01215 IN SAND CR 7.6
END DESCRIPTION:
XS GIS Cut Line= 6
      3485776.53     10537532.08      3485707.98     10537611.64
      3485510.03     10537902.16      3485470.97     10537940.14
      3485336.42     10538109.41      3485041.25     10538359.27
#Sta/Elev= 30
  4524.6  465.88  4549.1  466.11  4569.9  465.55  4584.2  465.58  4605.1  464.57
  4629.6  464.53  4633.4  464.28  4654.4  464.65  4720.2  464.33  4735.1  464.71
  4762.7   464.8    4799   464.1  4878.7  464.26  4893.7     464  4944.2  464.02
  4947.6  463.72  4950.3  463.22  4953.6  463.72  4956.6  464.02  4965.5   463.8
  5057.3  464.43  5164.7  464.33  5178.1  464.79  5199.9  464.89  5306.4  464.75
  5398.7  465.83  5448.2  465.83  5497.6  466.59  5561.3  466.45  5638.6  467.08
#Mann= 3 ,-1 , 0
  4524.6     .05       0  4947.6     .03       0  4953.6     .05       0
Bank Sta=4947.6,4953.6
XS Rating Curve= 0 ,0
Exp/Cntr=0.3,0.1

Type RM Length L Ch R = 1 ,15316   ,33,33,33
BEGIN DESCRIPTION:
UNT01215 IN SAND CR 7.4
END DESCRIPTION:
XS GIS Cut Line= 5
      3485704.27     10537369.64      3485631.88      10537493.8
      3485493.76     10537723.13      3485410.21     10537792.57
      3485272.41     10538043.21
#Sta/Elev= 30
  4509.1  465.59  4569.3  464.95  4643.5  464.74  4664.9  465.31  4673.7  465.13
  4686.3  464.26  4701.8  464.09  4723.2  464.45  4784.8   464.4  4787.5  464.37
  4818.4  463.96  4833.9  464.71  4870.8  465.04  4876.6  464.73  4913.5  464.45
  4945.7  463.75  4948.4  463.25  4951.7  463.75  4965.6   464.1  5020.1  463.94
  5031.5  464.01  5036.7  464.49  5050.8  464.66  5072.6  464.17  5100.1  464.36
  5144.6  464.19  5146.3  464.18  5181.5  464.55    5263  464.36  5315.2  465.71
#Mann= 9 ,-1 , 0
  4509.1     .05       0  4784.8     .08       0  4787.5     .05       0
  4945.7     .07       0  4951.7     .05       0  4965.6     .08       0
  5036.7     .05       0  5144.6     .08       0  5146.3     .05       0
Bank Sta=4945.7,4951.7
XS Rating Curve= 0 ,0
Exp/Cntr=0.3,0.1

Type RM Length L Ch R = 1 ,15283   ,55,55,55
BEGIN DESCRIPTION:
UNT01215 IN SAND CR 7.3
END DESCRIPTION:
XS GIS Cut Line= 6
      3485692.48     10537355.02      3485590.17     10537470.16
      3485432.99     10537731.81      3485399.36     10537757.85
      3485234.43     10538038.88      3484969.25      10538255.4
#Sta/Elev= 30
  4519.1  465.55  4550.3  465.42  4600.6  464.91  4644.7  464.61  4686.5  465.16
  4716.7  464.09  4803.2  464.39  4832.8  463.95  4876.1  464.61  4897.5  463.96
  4922.4  464.11  4982.1  463.76  4992.4  464.23  5023.1   463.8  5025.2  463.39
    5028  462.89  5031.2  463.39  5059.6  464.68  5067.4   464.3  5086.8  463.64
  5104.3  464.12  5108.3   463.7    5124  464.34  5178.6  464.42  5262.7   464.3
  5313.9  465.08  5464.6  465.44  5499.8  466.24  5648.4   466.9  5689.1  467.68
#Mann= 12 ,-1 , 0
  4519.1     .05       0  4550.3     .08       0  4600.6     .05       0
  4716.7     .08       0  4832.8     .05       0  4922.4     .08       0
  5025.2     .07       0  5031.2     .08       0  5067.4     .05       0
  5104.3     .08       0  5178.6     .05       0  5313.9     .08       0
Bank Sta=5025.2,5031.2
XS Rating Curve= 0 ,0
Exp/Cntr=0.3,0.1

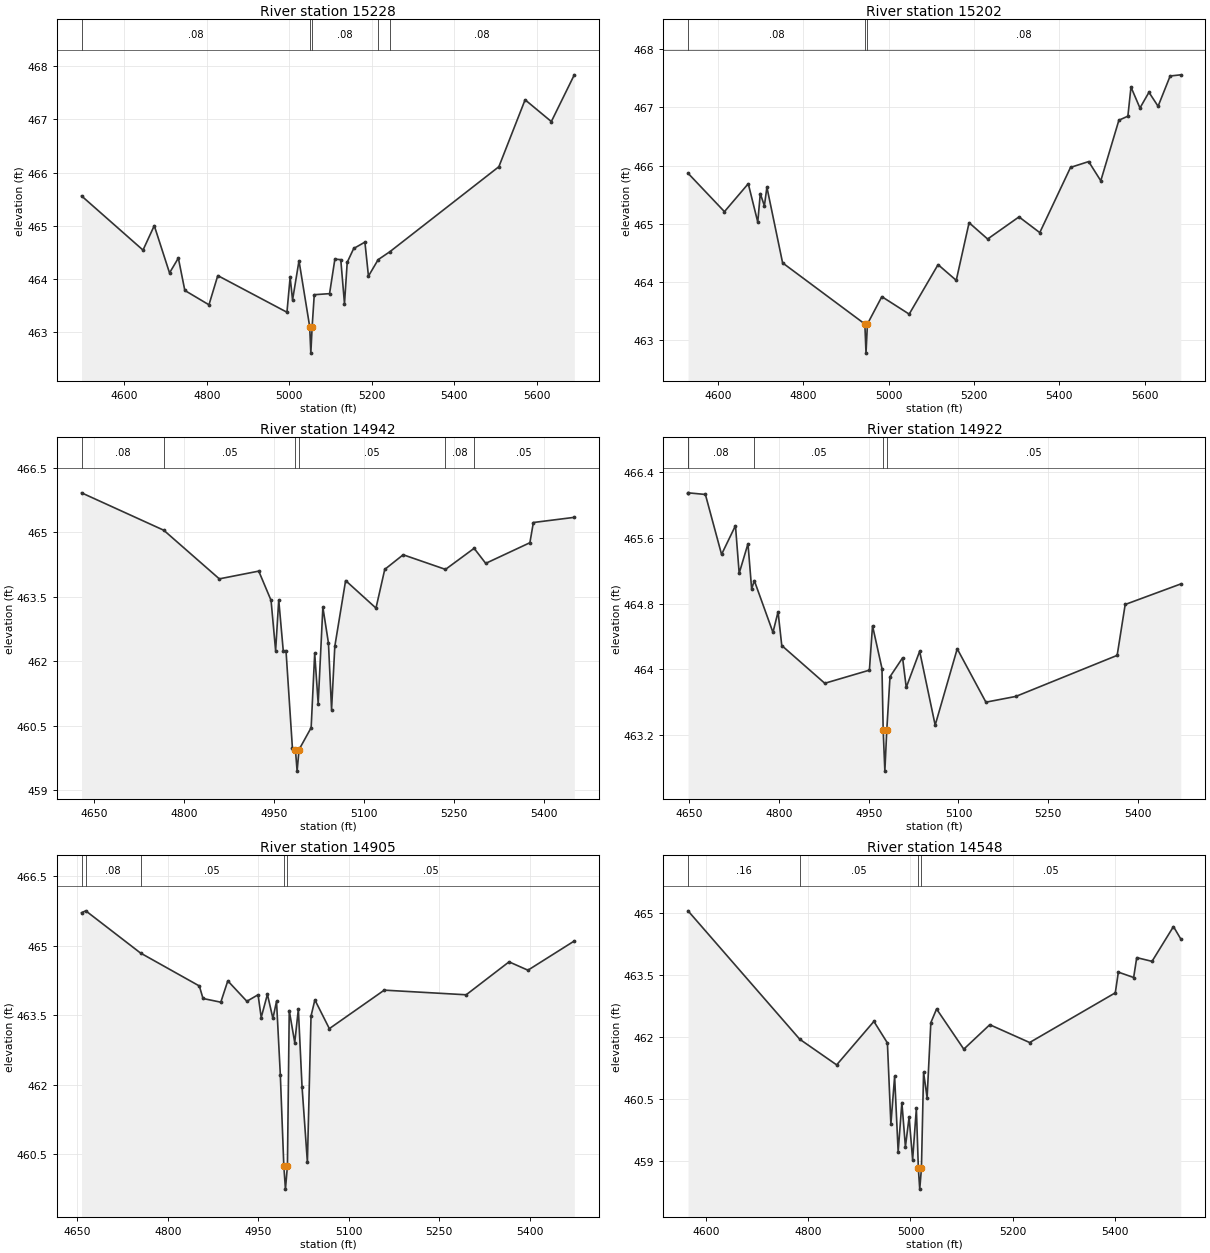
Type RM Length L Ch R = 1 ,15228   ,26,26,26
BEGIN DESCRIPTION:
UNT01215 IN SAND CR 7.1
END DESCRIPTION:
XS GIS Cut Line= 4
     3485528.474    10537259.748      3485568.61     10537386.78
      3485189.94     10538025.86       3484961.6     10538249.85
#Sta/Elev= 30
  4496.6  465.56  4645.6  464.54  4672.9     465  4709.9  464.11  4731.3  464.39
    4747  463.78  4805.5  463.51  4826.9  464.06  4994.6  463.37  5002.3  464.03
  5008.2   463.6  5023.8  464.34  5049.7   463.1  5052.5   462.6  5055.7   463.1
  5060.8   463.7  5097.9  463.72  5110.8  464.37  5125.1  464.36  5134.1  463.53
  5140.7  464.31  5156.4  464.57  5183.6  464.69  5192.2  464.05  5215.7  464.36
  5244.2  464.51  5508.4  466.11    5572  467.37  5635.6  466.96  5691.3  467.84
#Mann= 5 ,-1 , 0
  4496.6     .08       0  5049.7     .07       0  5055.7     .08       0
  5215.7     .05       0  5244.2     .08       0
Bank Sta=5049.7,5055.7
XS Rating Curve= 0 ,0
Exp/Cntr=0.3,0.1

Type RM Length L Ch R = 1 ,15202   ,260,260,260
BEGIN DESCRIPTION:
UNT01215 IN SAND CR 7.2
END DESCRIPTION:
XS GIS Cut Line= 4
      3485493.87     10537267.53      3485520.13     10537425.08
      3485167.15     10538006.33      3484951.17     10538235.97
#Sta/Elev= 30
  4529.7  465.87  4615.1  465.21  4670.9  465.69  4693.2  465.03  4699.1  465.52
  4708.7  465.31  4714.6  465.63  4751.4  464.33  4944.2  463.28  4946.9  462.78
  4950.2  463.28    4984  463.75  5048.1  463.45  5115.8   464.3  5158.4  464.03
  5188.5  465.02    5232  464.74  5305.5  465.12  5354.2  464.85  5426.3  465.97
  5468.8  466.07  5497.2  465.74  5539.6  466.78  5560.7  466.85    5568  467.35
    5589  466.99  5610.1  467.26  5631.5  467.02  5659.8  467.54  5684.7  467.56
#Mann= 3 ,-1 , 0
  4529.7     .08       0  4944.2     .07       0  4950.2     .08       0
Bank Sta=4944.2,4950.2
XS Rating Curve= 0 ,0
Exp/Cntr=0.3,0.1

Type RM Length L Ch R = 1 ,14942   ,20,20,20
BEGIN DESCRIPTION:
UNT01215 IN SAND CR 7.10
END DESCRIPTION:
XS GIS Cut Line= 6
      3485401.33     10537308.85       3485231.2     10537538.01
      3485178.24     10537522.39      3485123.56     10537554.51
       3485171.3     10537643.92      3485008.96     10537910.44
#Sta/Elev= 30
  4629.3  465.92  4766.3  465.05  4858.8  463.92  4924.5   464.1    4945  463.42
  4952.6  462.25  4957.8  463.43  4965.3  462.25  4969.9  462.25  4980.6  459.98
  4985.6  459.95  4988.4  459.45  4991.6  459.95  5011.8  460.46  5017.7  462.19
  5023.5  461.02  5031.3  463.26  5040.6  462.43  5045.8  460.88  5051.2  462.35
  5069.2  463.88  5119.8  463.24  5134.4  464.14  5165.1  464.48  5235.6  464.14
  5283.3  464.63  5302.6  464.28  5376.2  464.76    5382  465.23  5450.2  465.35
#Mann= 6 ,-1 , 0
  4629.3     .08       0  4766.3     .05       0  4985.6    .035       0
  4991.6     .05       0  5235.6     .08       0  5283.3     .05       0
Bank Sta=4985.6,4991.6
XS Rating Curve= 0 ,0
Exp/Cntr=0.3,0.1

Type RM Length L Ch R = 1 ,14922   ,17,17,17
BEGIN DESCRIPTION:
UNT01215 IN SAND CR 7.0
END DESCRIPTION:
XS GIS Cut Line= 6
      3485377.01     10537307.13      3485223.38     10537518.05
      3485165.22     10537503.29      3485100.99     10537550.17
      3485150.47     10537634.37      3484984.68     10537911.25
#Sta/Elev= 30
  4648.5  466.15  4648.9  466.15  4677.5  466.13  4704.5   465.4  4727.7  465.75
  4733.9  465.17  4748.6  465.53  4754.7  464.98  4759.2  465.08  4790.3  464.45
  4798.8   464.7    4805  464.29  4876.8  463.83  4951.3  463.99  4956.5  464.53
  4972.3  464.01  4974.3  463.26  4977.1  462.76  4980.3  463.26  4985.7  463.91
  5006.7  464.14  5012.8  463.78  5035.2  464.22  5061.1  463.32  5097.9  464.25
  5145.8   463.6  5195.8  463.67  5364.9  464.17  5378.3  464.79  5471.1  465.04
#Mann= 5 ,-1 , 0
  4648.5     .16       0  4648.9     .08       0  4759.2     .05       0
  4974.3    .035       0  4980.3     .05       0
Bank Sta=4974.3,4980.3
XS Rating Curve= 0 ,0
Exp/Cntr=0.3,0.1

Type RM Length L Ch R = 1 ,14905   ,357,357,357
BEGIN DESCRIPTION:
UNT01215 IN SAND CR 7.9
END DESCRIPTION:
XS GIS Cut Line= 6
      3485363.11     10537301.07      3485220.78     10537499.82
      3485165.22     10537485.06      3485091.44     10537533.67
      3485124.42     10537643.92       3484969.9     10537906.08
#Sta/Elev= 30
  4656.8  465.71  4663.8  465.75  4754.6  464.84  4852.1  464.13  4858.2  463.86
  4887.7  463.78  4899.3  464.24  4930.9   463.8  4949.5  463.94  4954.7  463.45
    4965  463.95  4974.1  463.43  4980.1   463.8  4986.4  462.22  4992.2  460.25
  4994.9  459.75  4998.2  460.25  5001.2   463.6  5010.3  462.91  5016.3  463.63
  5022.4  461.96  5031.3  460.33  5037.3  463.48  5043.7  463.83  5067.7  463.21
  5158.7  464.04  5294.6  463.94  5365.7  464.65    5397  464.47  5473.9   465.1
#Mann= 5 ,-1 , 0
  4656.8     .16       0  4663.8     .08       0  4754.6     .05       0
  4992.2    .035       0  4998.2     .05       0
Bank Sta=4992.2,4998.2
XS Rating Curve= 0 ,0
Exp/Cntr=0.3,0.1

Type RM Length L Ch R = 1 ,14548   ,16,16,16
BEGIN DESCRIPTION:
UNT01215 IN SAND CR 6.2
END DESCRIPTION:
XS GIS Cut Line= 4
      3485331.35     10537078.97      3484956.36     10537186.61
      3484886.91     10537252.58      3484617.83     10537646.66
#Sta/Elev= 30
  4565.2  465.05  4783.5  461.95  4855.7  461.33  4928.5  462.38  4954.9  461.86
  4961.7   459.9    4969  461.05  4975.9  459.23  4983.2  460.42  4990.1  459.35
  4997.3  460.07  5004.2  459.04  5011.5  460.28  5015.4  458.83  5018.1  458.33
  5021.4  458.83  5025.6  461.15  5032.5  460.54  5039.8  462.35    5051  462.68
  5104.2  461.71    5155   462.3  5232.9  461.87  5400.3  463.07  5406.3  463.57
  5436.2  463.44  5442.2  463.92  5472.1  463.83    5514  464.67  5528.3  464.37
#Mann= 4 ,-1 , 0
  4565.2     .16       0  4783.5     .05       0  5015.4    .035       0
  5021.4     .05       0
Bank Sta=5015.4,5021.4
XS Rating Curve= 0 ,0
Exp/Cntr=0.3,0.1

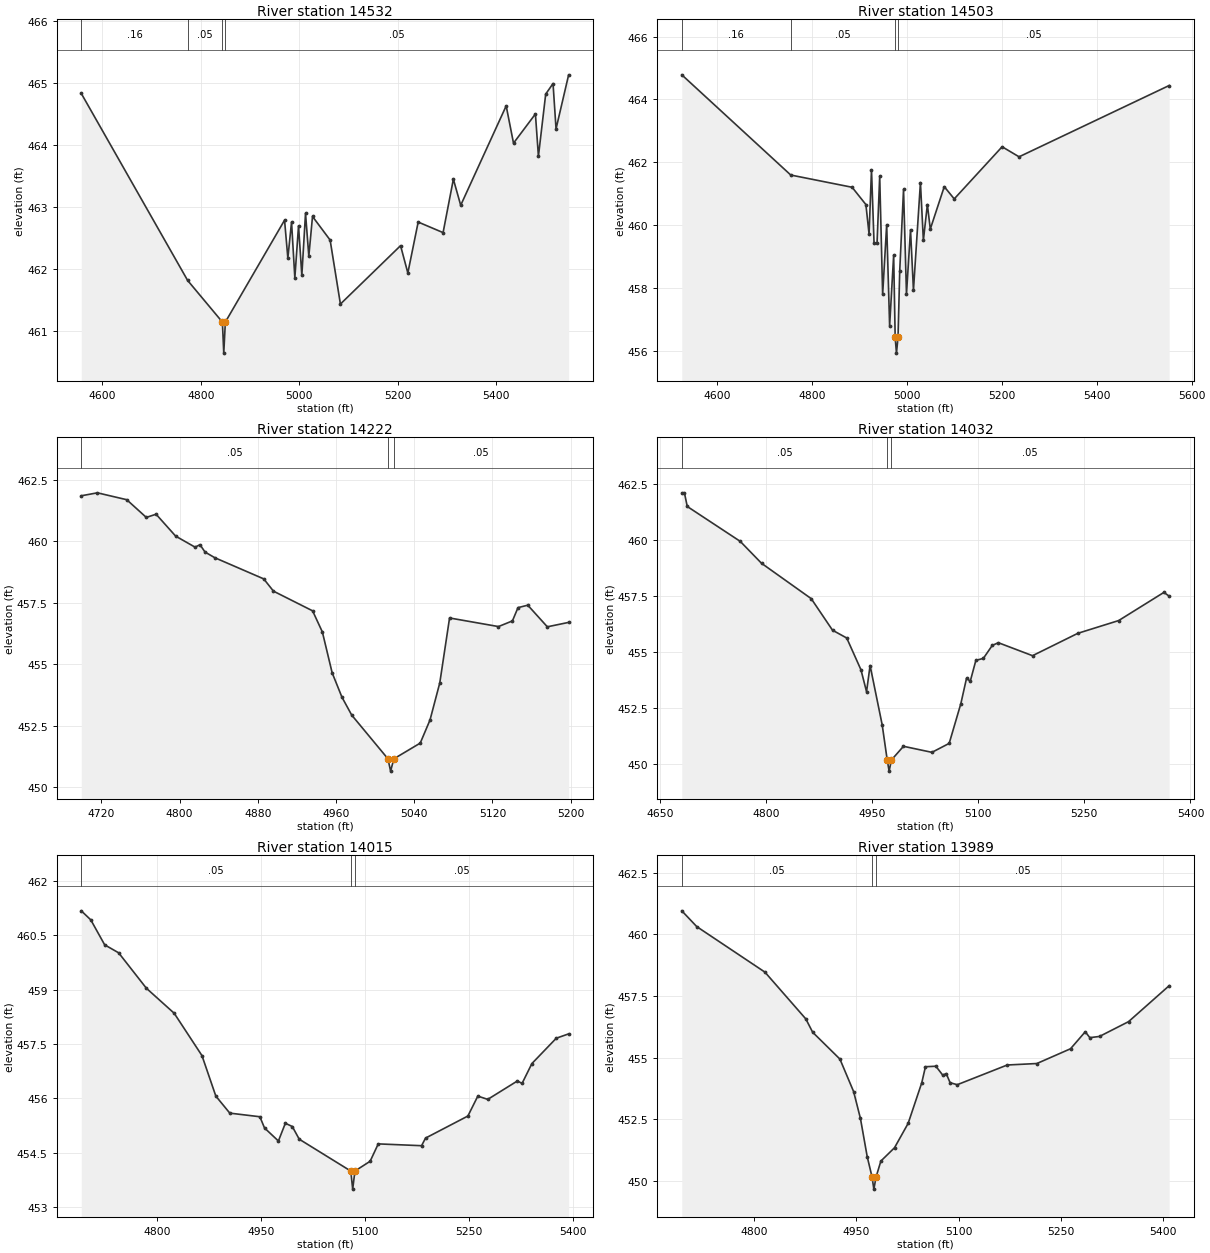
Type RM Length L Ch R = 1 ,14532   ,29,29,29
BEGIN DESCRIPTION:
UNT01215 IN SAND CR 6.0
END DESCRIPTION:
XS GIS Cut Line= 4
      3485322.67     10537058.14      3484978.93     10537146.68
      3484874.76     10537240.43      3484591.77     10537646.68
#Sta/Elev= 30
    4557  464.83  4773.1  461.82  4843.7  461.15  4846.5  460.65  4849.7  461.15
    4970  462.79  4976.7  462.18  4984.2  462.76  4990.9  461.86  4998.4   462.7
  5005.1   461.9  5012.6   462.9  5019.3  462.21  5026.8  462.85  5062.6  462.47
  5083.5  461.44  5205.7  462.38  5220.5  461.94  5241.5  462.76  5292.1  462.59
    5313  463.45  5327.9  463.03  5420.3  464.63  5435.2  464.03  5479.7   464.5
  5485.8  463.82  5500.6  464.82  5515.5  464.99  5521.6  464.26  5547.2  465.13
#Mann= 4 ,-1 , 0
    4557     .16       0  4773.1     .05       0  4843.7    .035       0
  4849.7     .05       0
Bank Sta=4843.7,4849.7
XS Rating Curve= 0 ,0
Exp/Cntr=0.3,0.1

Type RM Length L Ch R = 1 ,14503   ,281,281,281
BEGIN DESCRIPTION:
UNT01215 IN SAND CR 6.1
END DESCRIPTION:
XS GIS Cut Line= 4
      3485327.87     10537028.63      3484933.79     10537129.32
      3484853.93     10537238.69      3484574.44     10537634.49
#Sta/Elev= 30
  4525.9  464.78  4755.4  461.59  4884.7   461.2  4913.7  460.65  4920.4  459.71
  4925.5  461.76  4930.9  459.42  4937.2  459.42  4942.8  461.55    4949  457.79
  4957.5  460.01  4963.7  456.79  4972.2  459.04  4975.4  456.42  4978.1  455.92
  4981.4  456.42    4985  458.54    4993  461.13  4999.2   457.8  5007.7  459.85
  5013.9  457.92  5028.6  461.35  5034.8  459.51  5043.2  460.65  5049.4  459.87
  5078.8  461.22  5099.8  460.83  5200.7  462.49  5236.4  462.17  5552.6  464.44
#Mann= 4 ,-1 , 0
  4525.9     .16       0  4755.4     .05       0  4975.4    .035       0
  4981.4     .05       0
Bank Sta=4975.4,4981.4
XS Rating Curve= 0 ,0
Exp/Cntr=0.3,0.1

Type RM Length L Ch R = 1 ,14222   ,190,190,190
BEGIN DESCRIPTION:
UNT01215 IN SAND CR 5.0
END DESCRIPTION:
XS GIS Cut Line= 2
      3485148.61     10536902.84      3484650.35     10536918.46
#Sta/Elev= 30
  4699.4  461.85  4715.9  461.97  4745.9  461.69  4765.9  460.97  4775.9   461.1
  4795.9  460.21  4815.8  459.76  4820.8  459.86    4826  459.56    4836  459.33
    4886  458.47    4896  457.97    4936  457.17    4946  456.31    4956  454.65
    4966  453.66    4976  452.93  5013.1  451.15  5015.8  450.65  5019.1  451.15
  5046.1  451.79  5056.1  452.73  5066.1  454.24  5076.1  456.88  5126.1  456.53
  5140.4  456.76  5146.1   457.3  5156.1   457.4  5176.1  456.52  5197.9   456.7
#Mann= 3 ,-1 , 0
  4699.4     .05       0  5013.1    .035       0  5019.1     .05       0
Bank Sta=5013.1,5019.1
XS Rating Curve= 0 ,0
Exp/Cntr=0.3,0.1

Type RM Length L Ch R = 1 ,14032   ,17,17,17
BEGIN DESCRIPTION:
UNT01215 IN SAND CR 5.2
END DESCRIPTION:
XS GIS Cut Line= 4
      3485164.48     10536747.26      3484787.72     10536717.74
      3484667.93     10536759.41      3484553.38     10536903.47
#Sta/Elev= 30
  4681.1  462.12  4684.8  462.12  4688.8  461.51  4763.7  459.95  4793.8  458.97
    4864  457.39  4894.1  455.98  4914.2  455.63  4934.3  454.21  4942.2  453.23
  4947.2   454.4  4964.3  451.75  4971.4  450.18  4974.1  449.68  4977.4  450.18
  4994.4  450.79  5034.6  450.52    5059  450.92  5075.5   452.7  5083.5  453.83
  5088.8   453.7  5096.7  454.63  5107.3  454.72  5119.9   455.3  5128.5  455.42
  5176.8  454.84  5240.8  455.84  5298.5  456.41  5362.5  457.67  5369.9   457.5
#Mann= 3 ,-1 , 0
  4681.1     .05       0  4971.4    .035       0  4977.4     .05       0
Bank Sta=4971.4,4977.4
XS Rating Curve= 0 ,0
Exp/Cntr=0.3,0.1

Type RM Length L Ch R = 1 ,14015   ,26,26,26
BEGIN DESCRIPTION:
UNT01215 IN SAND CR 5.1
END DESCRIPTION:
XS GIS Cut Line= 4
      3485155.83     10536716.01      3484777.31     10536702.12
       3484666.2     10536740.31      3484532.51     10536896.57
#Sta/Elev= 30
  4691.2  461.18  4704.9  460.93  4724.9  460.24    4745  460.02    4785  459.04
    4825  458.35    4865  457.18    4885  456.06  4905.1  455.59  4948.4  455.49
  4955.1  455.18  4975.1  454.82  4985.1  455.31  4995.1  455.22  5005.1  454.87
  5079.3  453.99  5082.1  453.49  5085.3  453.99  5107.2  454.26  5118.9  454.74
  5181.3  454.69    5187   454.9    5248  455.51  5262.3  456.06  5276.6  455.97
  5319.4  456.48    5326  456.41  5340.2  456.96  5375.3  457.66  5393.1  457.78
#Mann= 3 ,-1 , 0
  4691.2     .05       0  5079.3    .035       0  5085.3     .05       0
Bank Sta=5079.3,5085.3
XS Rating Curve= 0 ,0
Exp/Cntr=0.3,0.1

Type RM Length L Ch R = 1 ,13989   ,250,250,250
BEGIN DESCRIPTION:
UNT01215 IN SAND CR 5.3
END DESCRIPTION:
XS GIS Cut Line= 4
      3485154.02     10536689.97       3484796.4     10536677.81
      3484662.72     10536719.48      3484516.15     10536879.85
#Sta/Elev= 30
    4694  460.96  4715.9  460.32    4816  458.47    4876  456.57    4886  456.03
    4926  454.94  4946.1  453.62  4956.1  452.53  4966.1  450.97  4973.1  450.16
  4975.8  449.66  4979.1  450.16  4986.1   450.8  5006.1  451.34  5026.1  452.33
  5046.1  453.98  5051.5  454.63  5066.8  454.65  5076.8  454.29    5082  454.35
  5087.7  453.98  5098.2   453.9  5171.5   454.7    5215  454.76  5264.4  455.36
    5286  456.05  5292.7  455.81  5306.9  455.86  5349.5  456.46  5409.1  457.92
#Mann= 3 ,-1 , 0
    4694     .05       0  4973.1    .035       0  4979.1     .05       0
Bank Sta=4973.1,4979.1
XS Rating Curve= 0 ,0
Exp/Cntr=0.3,0.1

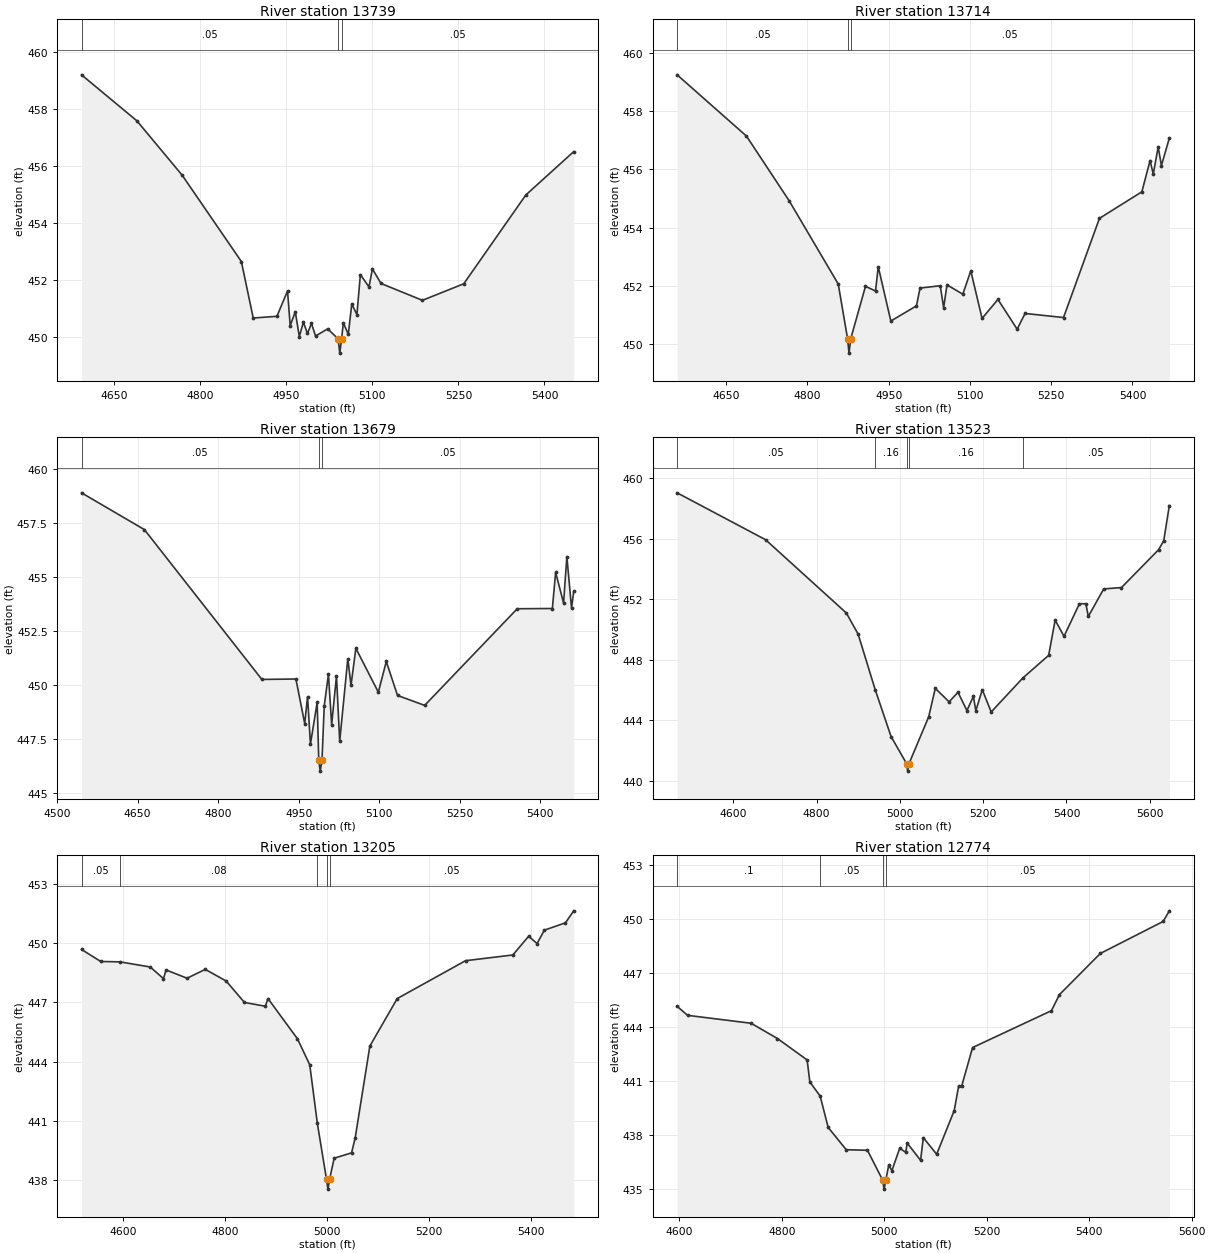
Type RM Length L Ch R = 1 ,13739   ,25,25,25
BEGIN DESCRIPTION:
UNT01215 IN SAND CR 4.0
END DESCRIPTION:
XS GIS Cut Line= 5
      3485150.59     10536492.06      3484841.54     10536406.98
      3484798.14      10536417.4      3484730.43     10536485.11
      3484509.95     10536814.97
#Sta/Elev= 30
  4593.3  459.19  4689.7  457.58  4768.8  455.67  4871.8  452.65  4892.5  450.67
  4933.8  450.73  4952.3  451.62  4956.9   450.4  4965.8  450.89  4972.8  450.02
  4979.9  450.52    4987  450.13    4994  450.48  5001.1  450.04  5022.3  450.29
  5040.5  449.94  5043.3  449.44  5046.5  449.94  5049.5   450.5  5058.2   450.1
  5064.2  451.16  5073.2  450.79  5079.2  452.19  5094.2  451.76  5100.2  452.39
  5115.2  451.88  5187.3  451.29  5259.4  451.87  5367.5  454.98    5451   456.5
#Mann= 3 ,-1 , 0
  4593.3     .05       0  5040.5    .035       0  5046.5     .05       0
Bank Sta=5040.5,5046.5
XS Rating Curve= 0 ,0
Exp/Cntr=0.3,0.1

Type RM Length L Ch R = 1 ,13714   ,35,35,35
BEGIN DESCRIPTION:
UNT01215 IN SAND CR 4.2
END DESCRIPTION:
XS GIS Cut Line= 6
      3485159.87     10536481.82      3484892.97     10536377.67
       3484784.1     10536389.49      3484698.96     10536504.85
      3484600.42     10536638.39      3484488.66     10536808.15
#Sta/Elev= 30
  4559.4  459.24  4687.4  457.14  4766.3  454.92  4856.8  452.07    4874   450.2
  4876.7   449.7    4880   450.2  4907.1  451.99  4925.6  451.83  4930.7  452.66
  4953.9   450.8  5001.2  451.32  5007.8  451.93  5045.1  452.01  5051.4  451.26
  5057.6  452.04  5086.8  451.72  5101.5  452.52  5122.3  450.89  5151.6  451.54
  5187.1  450.52  5201.7  451.06  5272.7  450.92    5339  454.32  5417.3  455.23
  5432.4   456.3  5438.4  455.84  5447.4  456.77  5453.4  456.13    5468  457.07
#Mann= 3 ,-1 , 0
  4559.4     .05       0    4874    .035       0    4880     .05       0
Bank Sta=4874,4880
XS Rating Curve= 0 ,0
Exp/Cntr=0.3,0.1

Type RM Length L Ch R = 1 ,13679   ,156,156,156
BEGIN DESCRIPTION:
UNT01215 IN SAND CR 4.1
END DESCRIPTION:
XS GIS Cut Line= 5
      3485164.42     10536453.85      3484810.29     10536349.69
      3484756.47     10536370.52      3484697.45     10536459.06
      3484477.03     10536773.19
#Sta/Elev= 30
  4545.4  458.89  4662.5  457.19  4881.4  450.26  4944.8  450.28  4961.2  448.22
  4966.5  449.46  4971.9  447.27  4984.4   449.2  4987.4  446.52  4990.1  446.02
  4993.4  446.52  4997.6  449.04  5005.4   450.5  5011.4  448.17  5020.4  450.42
  5026.4   447.4  5041.5  451.22  5047.5  449.99  5056.5   451.7  5098.4  449.67
  5113.2  451.09  5134.1  449.52  5184.7  449.06  5357.2  453.53  5422.6  453.54
  5428.7  455.21  5443.5  453.79  5449.6  455.94  5458.3  453.57  5462.4  454.33
#Mann= 3 ,-1 , 0
  4545.4     .05       0  4987.4    .035       0  4993.4     .05       0
Bank Sta=4987.4,4993.4
XS Rating Curve= 0 ,0
Exp/Cntr=0.3,0.1

Type RM Length L Ch R = 1 ,13523   ,318,318,318
BEGIN DESCRIPTION:
UNT01215 IN SAND CR 4.3
END DESCRIPTION:
XS GIS Cut Line= 4
       3485246.7     10536392.42      3484840.45     10536236.17
      3484655.56      10536251.8      3484366.78     10536733.09
#Sta/Elev= 30
    4465  459.02  4677.5  455.92  4871.4  451.08  4899.6  449.69  4940.7  446.01
  4978.9  442.91    5016  441.13  5018.8  440.63    5022  441.13  5069.2  444.22
    5085   446.1  5118.2  445.21  5139.6  445.84    5161  444.63  5176.5  445.57
  5182.4  444.62  5197.9  446.01  5219.3  444.54  5295.8   446.8  5357.3  448.28
  5372.9  450.61  5394.2  449.54  5431.2  451.69  5446.7  451.69  5452.5  450.85
  5489.5  452.67  5532.2  452.76  5621.6  455.27  5633.7  455.86  5647.1  458.18
#Mann= 5 ,-1 , 0
    4465     .05       0  4940.7     .16       0    5016     .07       0
    5022     .16       0  5295.8     .05       0
Bank Sta=5016,5022
XS Rating Curve= 0 ,0
Exp/Cntr=0.3,0.1

Type RM Length L Ch R = 1 ,13205   ,431,431,431
BEGIN DESCRIPTION:
UNT01215 IN SAND CR 3.0
END DESCRIPTION:
XS GIS Cut Line= 2
      3485073.01     10535857.23      3484136.28     10536094.02
#Sta/Elev= 30
  4518.4  449.69  4556.1  449.08  4593.9  449.06  4653.4   448.8  4679.2  448.21
  4684.4  448.65  4725.6  448.23  4761.3  448.68  4802.3  448.09  4838.2     447
  4879.2  446.81  4884.4   447.2  4942.2  445.16  4966.4  443.84  4981.3  440.87
  4999.3  438.03  5002.1  437.53  5005.3  438.03  5014.4   439.1  5048.5  439.37
  5055.7  440.14  5084.4  444.79  5138.2   447.2  5272.3  449.12  5365.1  449.41
  5396.1  450.36  5412.6  449.99    5427  450.67  5468.3  451.04  5484.6  451.65
#Mann= 5 ,-1 , 0
  4518.4     .05       0  4593.9     .08       0  4981.3     .05       0
  4999.3     .04       0  5005.3     .05       0
Bank Sta=4999.3,5005.3
XS Rating Curve= 0 ,0
Exp/Cntr=0.3,0.1

Type RM Length L Ch R = 1 ,12774   ,15,15,15
BEGIN DESCRIPTION:
UNT01215 IN SAND CR 1.4
END DESCRIPTION:
XS GIS Cut Line= 6
      3484902.02     10535629.38      3484563.46     10535543.44
       3484528.3     10535549.95      3484478.83      10535581.2
      3484456.69      10535646.3       3484071.3     10535875.45
#Sta/Elev= 30
  4595.7  445.13  4616.2  444.63  4740.1  444.19  4791.6  443.34  4849.5  442.15
  4854.7  440.93  4874.9  440.14  4890.5   438.4  4925.8  437.16  4967.2  437.13
  4996.9  435.47  4999.7  434.97  5002.9  435.47  5008.9  436.32  5014.8  435.99
  5030.1  437.24  5041.9  437.02  5044.8  437.53  5070.9  436.57  5076.2  437.83
  5102.3  436.91  5136.6  439.34  5145.1  440.69    5151  440.69  5172.4  442.84
  5326.3  444.89  5341.9  445.78  5421.7  448.07  5544.4  449.85  5556.4  450.44
#Mann= 4 ,-1 , 0
  4595.7      .1       0  4874.9     .05       0  4996.9     .04       0
  5002.9     .05       0
Bank Sta=4996.9,5002.9
XS Rating Curve= 0 ,0
Exp/Cntr=0.3,0.1

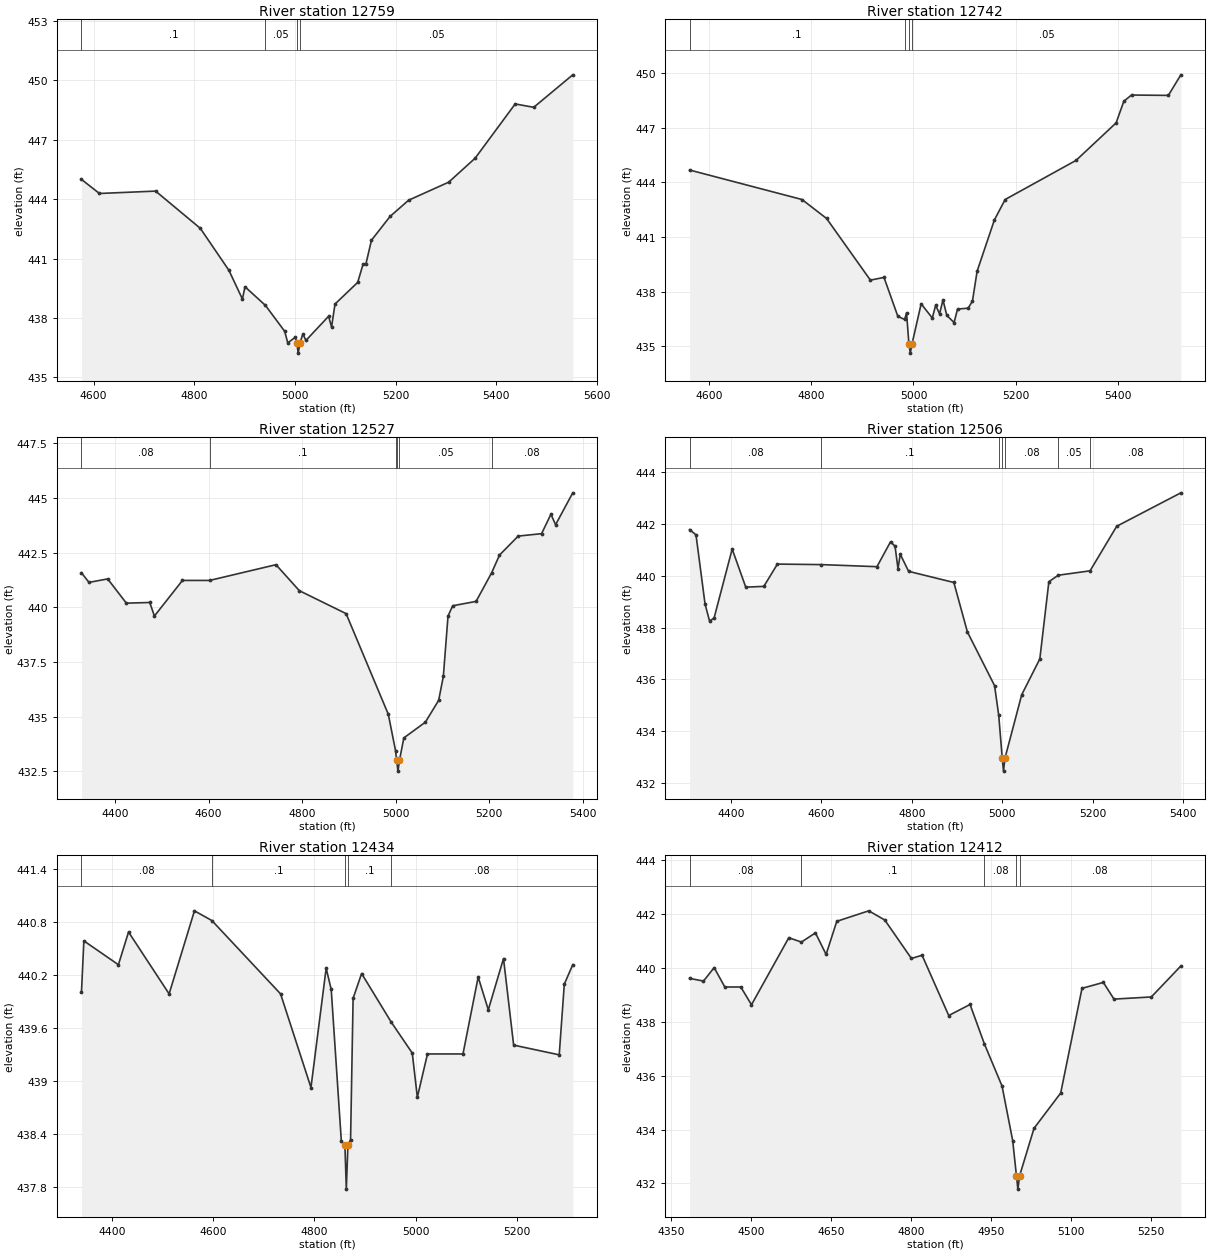
Type RM Length L Ch R = 1 ,12759   ,17,17,17
BEGIN DESCRIPTION:
UNT01215 IN SAND CR 1.2
END DESCRIPTION:
XS GIS Cut Line= 6
      3484916.68     10535612.18      3484572.97     10535528.86
       3484528.7     10535531.46      3484474.01     10535567.92
      3484421.92     10535651.25      3484067.73     10535864.81
#Sta/Elev= 30
  4576.1     445  4611.7  444.29  4723.3  444.41  4812.1  442.53  4868.9  440.41
  4895.7  438.96  4900.8  439.58  4941.4  438.64  4979.7  437.33  4985.7  436.75
  5000.8  437.03  5003.8  436.73  5006.5  436.23  5009.8  436.73  5015.8   437.2
  5021.8  436.87  5066.8  438.09  5072.7  437.55  5079.6  438.71  5124.6   439.8
  5135.4  440.73  5140.9  440.73    5152  441.93  5188.9  443.13  5225.7  443.95
  5305.3  444.86  5357.8  446.07  5437.4  448.81  5474.2  448.64  5551.7  450.28
#Mann= 4 ,-1 , 0
  4576.1      .1       0  4941.4     .05       0  5003.8     .04       0
  5009.8     .05       0
Bank Sta=5003.8,5009.8
XS Rating Curve= 0 ,0
Exp/Cntr=0.3,0.1

Type RM Length L Ch R = 1 ,12742   ,215,215,215
BEGIN DESCRIPTION:
UNT01215 IN SAND CR 1.3
END DESCRIPTION:
XS GIS Cut Line= 6
      3484922.81     10535595.52      3484566.06     10535513.49
       3484523.1     10535510.89      3484435.86     10535587.71
      3484413.72     10535617.66      3484081.69     10535836.41
#Sta/Elev= 30
  4562.4  444.68  4782.1  443.06  4830.1  442.02  4915.8  438.63  4942.4  438.78
  4969.5  436.64  4982.7  436.47  4986.5  436.83  4991.1  435.12  4993.8  434.62
  4997.1  435.12    5015  437.33  5036.8  436.55  5043.4  437.25    5051  436.78
  5057.7  437.54  5065.2  436.69  5079.4   436.3  5086.1  437.04  5106.9  437.09
  5115.3  437.48  5124.4  439.12  5158.2  441.94  5179.2  443.06  5317.8  445.21
  5396.1  447.27  5411.2  448.46  5426.2   448.8  5498.2  448.78  5522.6  449.91
#Mann= 4 ,-1 , 0
  4562.4      .1       0  4982.7     .05       0  4991.1     .04       0
  4997.1     .05       0
Bank Sta=4991.1,4997.1
XS Rating Curve= 0 ,0
Exp/Cntr=0.3,0.1

Type RM Length L Ch R = 1 ,12527   ,21,21,21
BEGIN DESCRIPTION:
UNT01215 IN SAND CR 1.1
END DESCRIPTION:
XS GIS Cut Line= 4
      3485138.11     10535312.71      3484481.82     10535315.31
      3484414.11     10535349.17       3484095.4     10535356.94
#Sta/Elev= 30
  4328.3  441.58  4344.3  441.14  4384.3   441.3  4424.3  440.19  4474.3  440.22
  4484.3   439.6  4544.3  441.23  4602.4  441.23  4744.3  441.95  4794.3  440.76
  4894.3  439.71  4984.6   435.1    5000  433.44  5002.5     433  5005.2   432.5
  5008.5     433  5017.8  434.02  5063.8  434.74  5092.3  435.74  5102.3  436.84
  5112.3   439.6  5122.3  440.07  5172.3  440.27  5205.4  441.57  5222.4  442.39
  5262.4  443.26  5312.4  443.37  5332.4  444.26  5342.4  443.78  5379.1  445.24
#Mann= 6 ,-1 , 0
  4328.3     .08       0  4602.4      .1       0    5000     .05       0
  5002.5    .035       0  5008.5     .05       0  5205.4     .08       0
Bank Sta=5002.5,5008.5
XS Rating Curve= 0 ,0
Exp/Cntr=0.3,0.1

Type RM Length L Ch R = 1 ,12506   ,72,72,72
BEGIN DESCRIPTION:
UNT01215 IN SAND CR 1.0
END DESCRIPTION:
XS GIS Cut Line= 2
      3485156.29     10535286.67      3484070.34     10535310.11
#Sta/Elev= 30
  4308.9  441.78  4323.1  441.58  4343.1  438.91  4353.1  438.25  4363.1  438.37
  4403.1  441.03  4433.1  439.56  4473.1  439.59  4503.1  440.45  4600.5  440.43
  4723.2  440.35  4753.2  441.31  4763.2  441.14  4769.7  440.27  4774.7  440.83
  4793.2  440.17  4893.2  439.74  4923.2  437.83  4983.2  435.76  4992.4  434.62
  5000.2  432.96    5003  432.46  5006.2  432.96  5043.3  435.41  5083.3  436.79
  5103.3  439.77    5124  440.02  5194.4  440.19  5253.3  441.91  5395.1   443.2
#Mann= 7 ,-1 , 0
  4308.9     .08       0  4600.5      .1       0  4992.4     .08       0
  5000.2     .07       0  5006.2     .08       0    5124     .05       0
  5194.4     .08       0
Bank Sta=5000.2,5006.2
XS Rating Curve= 0 ,0
Exp/Cntr=0.3,0.1

Type RM Length L Ch R = 1 ,12434   ,22,22,22
BEGIN DESCRIPTION:
UNT01215 IN SAND CR 3.1
END DESCRIPTION:
XS GIS Cut Line= 2
      3485125.03     10535216.62       3484155.4     10535234.81
#Sta/Elev= 30
  4340.2  440.01  4344.9  440.59  4413.1  440.32  4433.1  440.69  4513.2  439.99
  4563.2  440.93  4597.6  440.82  4733.2  439.99  4793.2  438.93  4823.2  440.28
  4833.2  440.04  4853.2  438.32  4860.2  438.28    4863  437.78  4866.2  438.28
  4871.4  438.34  4876.4  439.94  4893.2  440.22  4951.7  439.67  4993.2  439.32
  5003.2  438.82  5023.2  439.31  5093.3  439.31  5123.3  440.18  5143.3  439.81
  5173.3  440.39  5193.3  439.41  5283.3   439.3  5293.3   440.1    5310  440.32
#Mann= 5 ,-1 , 0
  4340.2     .08       0  4597.6      .1       0  4860.2     .07       0
  4866.2      .1       0  4951.7     .08       0
Bank Sta=4860.2,4866.2
XS Rating Curve= 0 ,0
Exp/Cntr=0.3,0.1

Type RM Length L Ch R = 1 ,12412   ,314,314,314
BEGIN DESCRIPTION:
UNT01215 IN SAND CR 3.2
END DESCRIPTION:
XS GIS Cut Line= 2
      3485078.16     10535200.99      3484156.71      10535211.4
#Sta/Elev= 30
  4385.2  439.62  4411.3  439.52  4431.3  440.02  4451.3   439.3  4481.3   439.3
  4501.3  438.64  4571.3  441.13    4595  440.97  4621.3  441.31  4641.3  440.51
  4661.3  441.74  4721.3  442.13  4751.3  441.79  4801.3  440.36  4821.3  440.48
  4871.3  438.24  4911.3  438.65  4938.1  437.19  4971.3  435.62  4991.3  433.59
  4998.3  432.29    5001  431.79  5004.3  432.29  5031.3  434.05  5081.3  435.36
  5121.3  439.25  5161.3  439.47  5181.3  438.85  5251.3  438.93  5306.7  440.08
#Mann= 5 ,-1 , 0
  4385.2     .08       0    4595      .1       0  4938.1     .08       0
  4998.3     .07       0  5004.3     .08       0
Bank Sta=4998.3,5004.3
XS Rating Curve= 0 ,0
Exp/Cntr=0.3,0.1