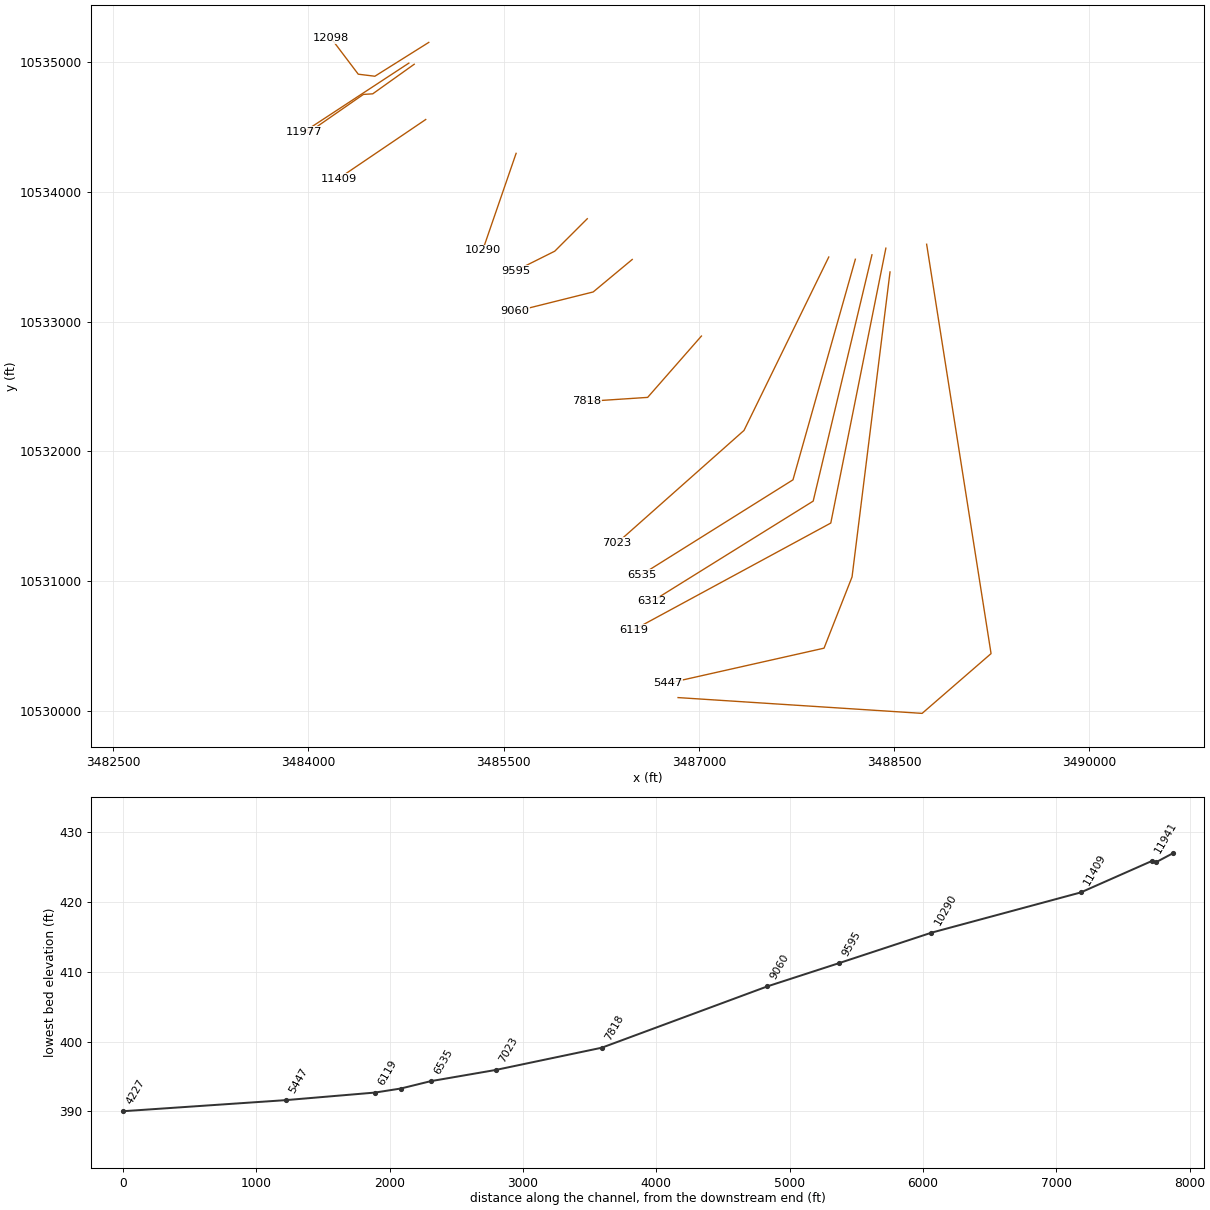
HEC-RAS study UNT0098 IN SAND CR.prj: UNT0098 IN SAND CR Base Level Engineering

--- UNT0098 IN SAND CR.g01 (geometry) --- (continued)

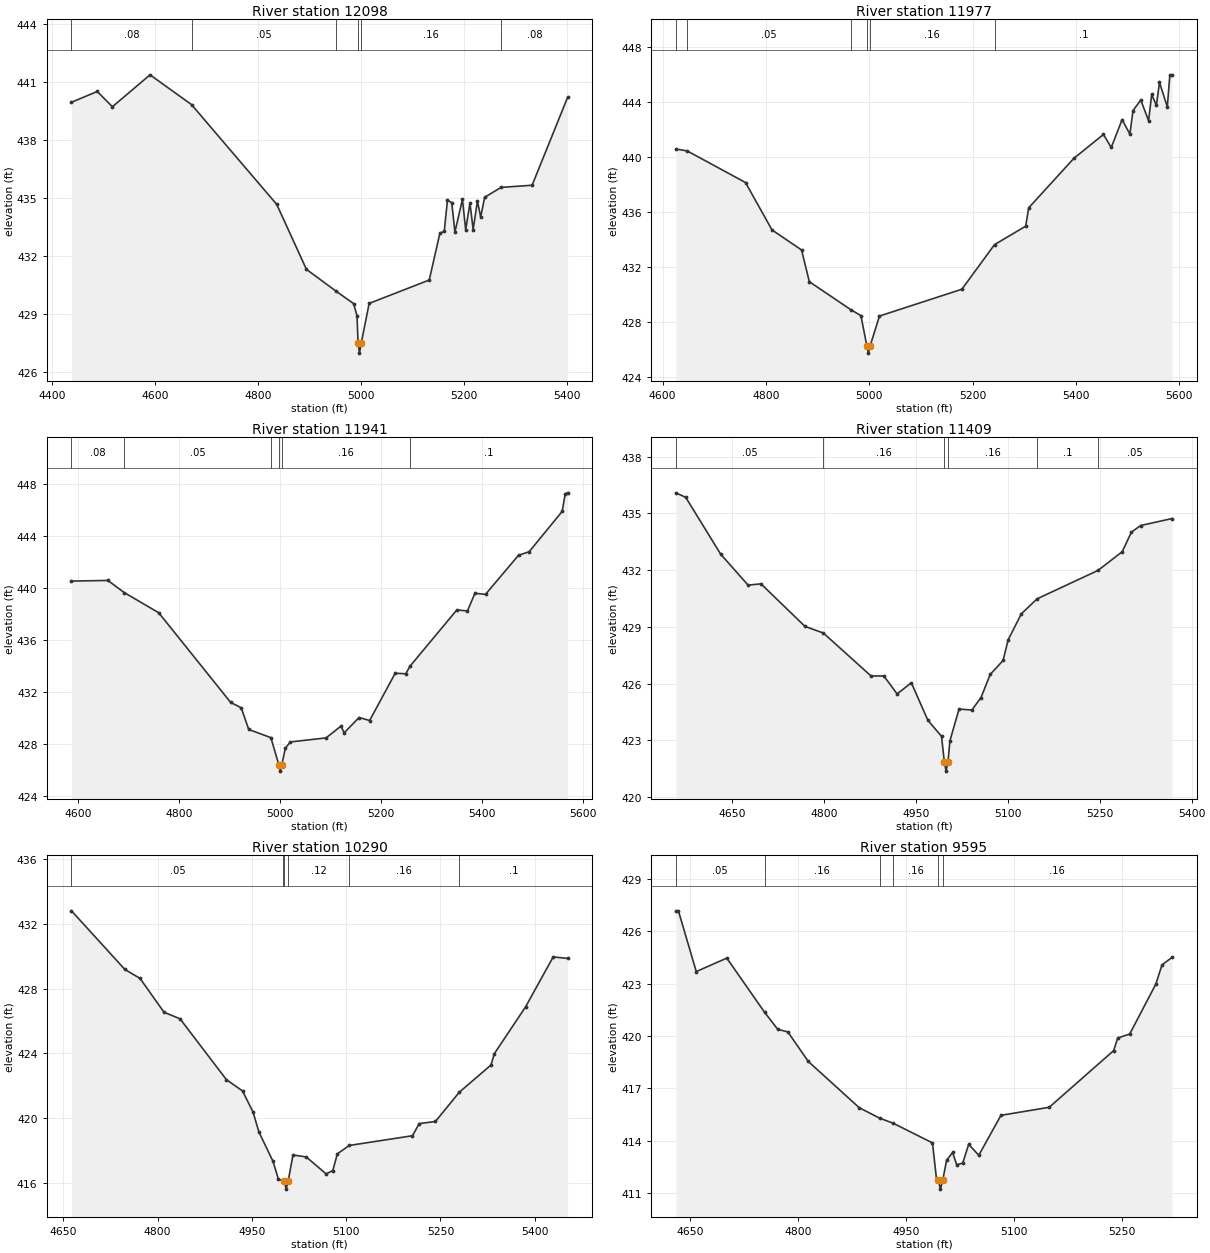
Type RM Length L Ch R = 1 ,12098   ,121,121,121
BEGIN DESCRIPTION:
UNT01215 IN SAND CR 3.3
END DESCRIPTION:
XS GIS Cut Line= 4
      3484924.55     10535148.92      3484510.47     10534888.49
      3484382.86     10534904.12      3484174.51     10535180.18
#Sta/Elev= 30
  4437.7  439.95  4487.8  440.51  4517.2  439.72  4590.3  441.37  4670.9  439.83
  4836.4  434.67  4894.1  431.31  4952.3  430.17  4985.7  429.54  4992.3  428.92
  4994.4  427.48  4997.1  426.98  5000.4  427.48  5015.9  429.55  5132.6  430.76
  5153.4  433.19  5161.7  433.27    5168  434.89  5176.3  434.76  5182.5  433.24
  5197.1  434.93  5203.4  433.35  5211.7  434.74  5217.9  433.37  5226.2  434.84
  5232.5  434.02  5240.3  435.04  5272.2  435.55  5332.4  435.66  5401.3   440.2
#Mann= 6 ,-1 , 0
  4437.7     .08       0  4670.9     .05       0  4952.3     .16       0
  4994.4     .07       0  5000.4     .16       0  5272.2     .08       0
Bank Sta=4994.4,5000.4
XS Rating Curve= 0 ,0
Exp/Cntr=0.3,0.1

Type RM Length L Ch R = 1 ,11977   ,36,36,36
BEGIN DESCRIPTION:
UNT0522 IN SAND CR 9.0
END DESCRIPTION:
XS GIS Cut Line= 2
      3484771.57     10534989.48      3483968.65     10534462.16
#Sta/Elev= 30
  4625.6  440.61  4647.5  440.47  4760.4  438.17  4811.7  434.72  4868.9  433.26
    4884  430.95    4964  428.92  4983.9  428.48  4995.5  426.25  4998.2  425.75
  5001.5  426.25  5019.8  428.45  5179.3   430.4  5242.6  433.65  5302.9  434.99
  5308.8  436.33  5396.2  439.93  5453.5  441.67  5468.6  440.72  5489.6  442.75
  5504.7  441.69  5510.7  443.41  5525.8  444.17  5540.9  442.67  5546.9  444.58
    5556  443.79    5562  445.46  5577.1  443.68  5582.1  446.01  5586.2  446.01
#Mann= 6 ,-1 , 0
  4625.6     .08       0  4647.5     .05       0    4964     .16       0
  4995.5     .07       0  5001.5     .16       0  5242.6      .1       0
Bank Sta=4995.5,5001.5
XS Rating Curve= 0 ,0
Exp/Cntr=0.3,0.1

Type RM Length L Ch R = 1 ,11941   ,532,532,532
BEGIN DESCRIPTION:
UNT0522 IN SAND CR 9.1
END DESCRIPTION:
XS GIS Cut Line= 4
      3484812.81     10534980.81      3484493.83     10534752.96
      3484422.21     10534748.62      3483995.91     10534452.16
#Sta/Elev= 30
  4586.2  440.52  4658.4  440.57  4690.6  439.64  4759.1  438.08  4901.7  431.17
  4922.6  430.76  4937.4  429.09  4981.3  428.46    4997  426.38  4999.7  425.88
    5003  426.38    5010  427.65    5020  428.13  5090.6  428.44  5120.3  429.35
  5126.4  428.83  5156.1  430.01    5177  429.78  5227.6  433.42  5248.6  433.38
  5257.1  433.97  5349.8   438.3  5370.8  438.22  5385.6  439.58  5406.6   439.5
    5472  442.51    5493  442.78  5558.5  445.89  5564.5  447.24  5569.2  447.32
#Mann= 6 ,-1 , 0
  4586.2     .08       0  4690.6     .05       0  4981.3     .16       0
    4997     .07       0    5003     .16       0  5257.1      .1       0
Bank Sta=4997,5003
XS Rating Curve= 0 ,0
Exp/Cntr=0.3,0.1

Type RM Length L Ch R = 1 ,11409   ,1119,1119,1119
BEGIN DESCRIPTION:
UNT0522 IN SAND CR 8.0
END DESCRIPTION:
XS GIS Cut Line= 2
      3484900.98     10534555.35      3484230.78     10534100.45
#Sta/Elev= 30
  4557.9  436.09    4574  435.85    4631  432.85  4675.8  431.21  4696.8  431.28
  4768.7  429.03  4798.7  428.68  4876.5  426.41  4897.5  426.41  4919.1  425.46
  4942.3  426.05  4969.3  424.07  4991.6  423.22  4996.2  421.88    4999  421.38
  5002.2  421.88  5005.3  422.98  5020.2  424.66  5041.2  424.61  5056.1  425.27
  5071.1  426.49  5092.1  427.23  5100.4  428.32    5122   429.7  5147.8  430.49
  5247.2  431.99  5286.7  432.98  5301.6  434.01  5316.6  434.36  5367.9  434.73
#Mann= 6 ,-1 , 0
  4557.9     .05       0  4798.7     .16       0  4996.2     .07       0
  5002.2     .16       0  5147.8      .1       0  5247.2     .05       0
Bank Sta=4996.2,5002.2
XS Rating Curve= 0 ,0
Exp/Cntr=0.3,0.1

Type RM Length L Ch R = 1 ,10290   ,695,695,695
BEGIN DESCRIPTION:
UNT0522 IN SAND CR 6.0
END DESCRIPTION:
XS GIS Cut Line= 2
      3485595.39     10534294.92      3485338.45      10533548.4
#Sta/Elev= 30
  4662.8  432.81  4747.7  429.19    4772  428.63  4810.1  426.54  4835.5  426.14
  4909.5  422.37    4935  421.68  4951.8  420.37    4961  419.15  4983.5  417.33
  4992.2  416.22  4999.8  416.14  5001.7  416.11  5004.4  415.61  5007.7  416.11
  5015.3  417.72  5036.4   417.6  5068.1  416.55  5078.7  416.76  5085.9  417.79
    5105  418.31  5205.5  418.91  5216.2  419.66    5242  419.79    5280   421.6
  5330.4  423.28  5335.7  423.98  5385.4  426.87  5429.4  429.96  5452.3  429.87
#Mann= 6 ,-1 , 0
  4662.8     .05       0  4999.8     .12       0  5001.7     .07       0
  5007.7     .12       0    5105     .16       0    5280      .1       0
Bank Sta=5001.7,5007.7
XS Rating Curve= 0 ,0
Exp/Cntr=0.3,0.1

Type RM Length L Ch R = 1 ,9595    ,535,535,535
BEGIN DESCRIPTION:
UNT0522 IN SAND CR 4.0
END DESCRIPTION:
XS GIS Cut Line= 3
      3486142.09     10533791.63      3485892.11     10533541.64
      3485592.14     10533391.66
#Sta/Elev= 30
  4630.2  427.18  4633.7  427.18  4658.5   423.7  4700.9  424.47  4753.3  421.37
  4771.6  420.39  4785.7  420.24    4814  418.55  4884.7   415.9    4913   415.3
  4932.3     415  4986.5  413.88  4992.1  411.81  4994.7  411.73  4997.5  411.23
  5000.7  411.73  5006.1  412.88  5014.5  413.33  5020.1  412.63  5028.5  412.72
  5036.8   413.8  5050.8  413.17  5081.6  415.46  5148.6  415.92  5238.1  419.17
  5243.7  419.89  5260.4  420.12  5296.8  422.99  5305.2  424.08  5319.1  424.51
#Mann= 6 ,-1 , 0
  4630.2     .05       0  4753.3     .16       0    4913     .12       0
  4932.3     .16       0  4994.7     .07       0  5000.7     .16       0
Bank Sta=4994.7,5000.7
XS Rating Curve= 0 ,0
Exp/Cntr=0.3,0.1

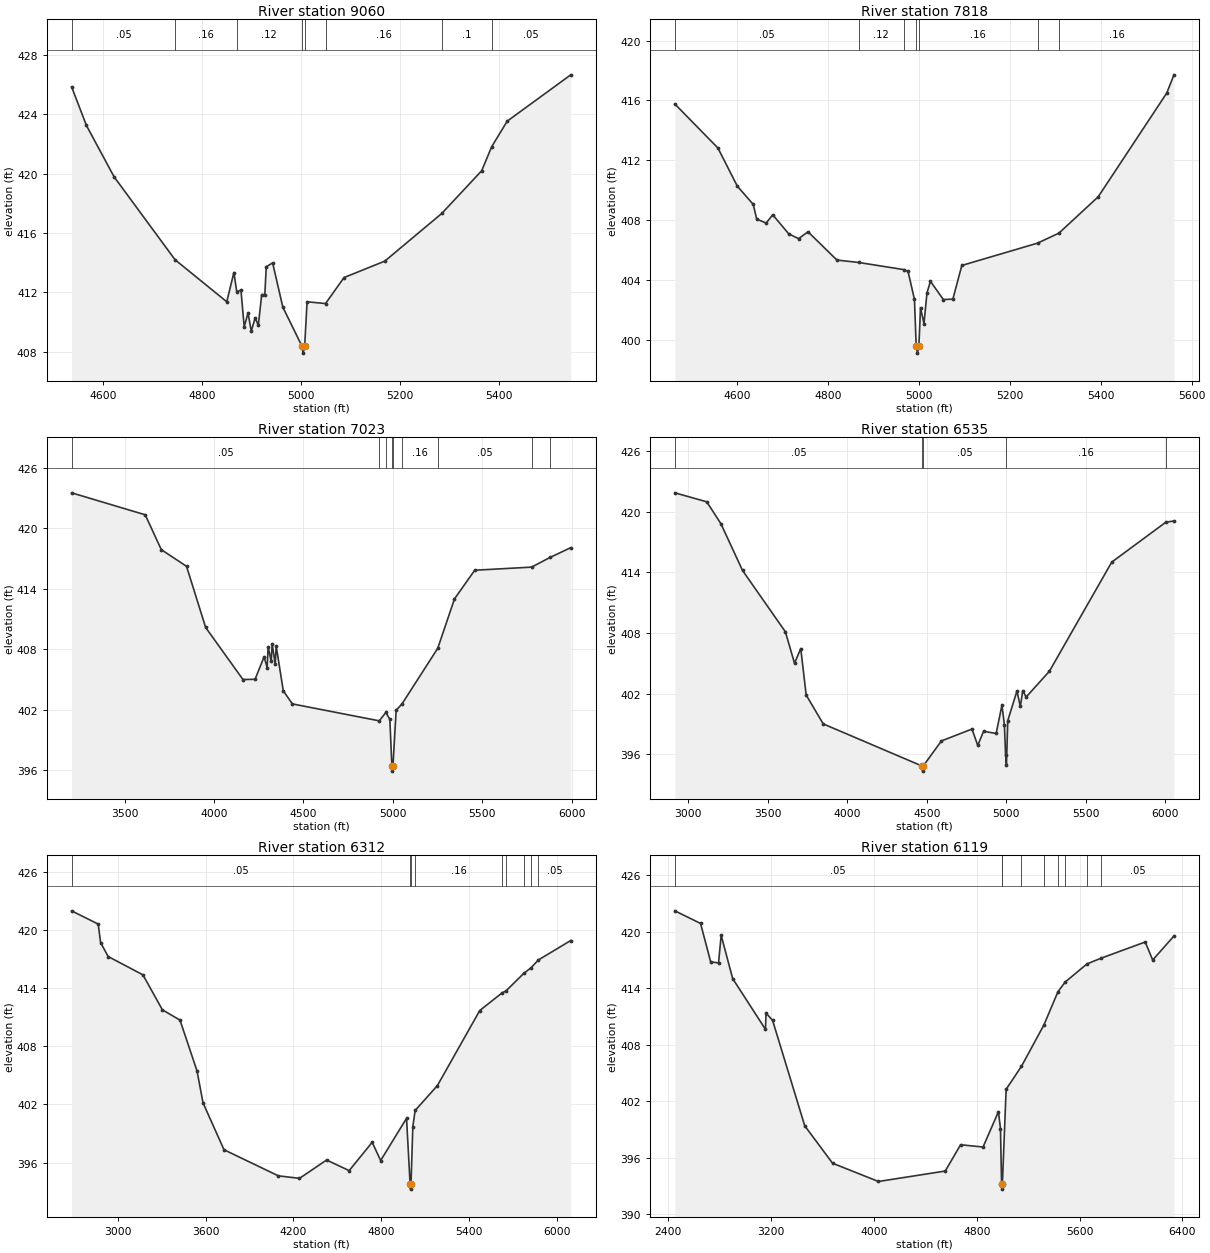
Type RM Length L Ch R = 1 ,9060    ,1242,1242,1242
BEGIN DESCRIPTION:
UNT0522 IN SAND CR 3.0
END DESCRIPTION:
XS GIS Cut Line= 3
      3486487.42     10533477.96      3486187.45     10533227.98
      3485587.49     10533077.99
#Sta/Elev= 30
    4536  425.85  4565.9  423.25  4621.8  419.79  4745.1   414.2  4849.6  411.37
    4864  413.34  4869.7  412.06  4878.3  412.15  4884.8  409.69  4892.6  410.61
  4899.1  409.39  4906.9  410.28  4913.4  409.79  4920.2  411.85  4926.5  411.85
  4929.4  413.73  4942.3  413.99  4962.9  411.01  5001.1  408.41  5003.9  407.91
  5007.1  408.41  5011.9  411.37  5049.2  411.25  5086.6     413  5169.1  414.11
  5284.2  417.32  5364.9   420.2  5385.1  421.82  5416.5  423.54  5544.9  426.66
#Mann= 8 ,-1 , 0
    4536     .05       0  4745.1     .16       0  4869.7     .12       0
  5001.1     .07       0  5007.1     .12       0  5049.2     .16       0
  5284.2      .1       0  5385.1     .05       0
Bank Sta=5001.1,5007.1
XS Rating Curve= 0 ,0
Exp/Cntr=0.3,0.1

Type RM Length L Ch R = 1 ,7818    ,795,795,795
BEGIN DESCRIPTION:
UNT0522 IN SAND CR 1.0
END DESCRIPTION:
XS GIS Cut Line= 3
      3487018.98     10532888.64      3486605.81     10532416.44
      3486135.38     10532385.31
#Sta/Elev= 30
  4462.2  415.76    4557  412.82  4599.7  410.27  4634.8  409.05  4642.4  408.07
  4663.3   407.8  4677.6  408.36  4712.7  407.09  4734.5  406.76  4755.4  407.22
    4819  405.33  4866.7  405.17  4966.7  404.69  4975.6  404.57  4989.7   402.7
  4993.5  399.61  4996.2  399.11  4999.5  399.61  5003.1  402.14  5010.7  401.09
  5017.3  403.14  5024.9  403.91  5053.4  402.69  5074.3  402.72    5094  404.97
  5260.7  406.46  5307.8  407.13  5394.3  409.56  5545.1  416.49  5561.1  417.71
#Mann= 7 ,-1 , 0
  4462.2     .05       0  4866.7     .12       0  4966.7     .16       0
  4993.5     .07       0  4999.5     .16       0  5260.7     .12       0
  5307.8     .16       0
Bank Sta=4993.5,4999.5
XS Rating Curve= 0 ,0
Exp/Cntr=0.3,0.1

Type RM Length L Ch R = 1 ,7023    ,488,488,488
BEGIN DESCRIPTION:
UNT0098 IN SAND CR 1.2
END DESCRIPTION:
XS GIS Cut Line= 3
      3487997.15     10533496.84       3487346.1     10532162.17
      3486370.95     10531295.37
#Sta/Elev= 30
  3204.4  423.53  3615.7  421.35  3705.8  417.89  3846.6  416.24  3953.6  410.17
    4162  405.01  4229.6  405.03  4280.2  407.26  4297.2  406.19  4302.7  408.24
  4319.7  406.83  4325.3  408.53  4342.2  406.54  4347.8  408.33  4387.3   403.9
  4437.9  402.59  4923.5  400.91  4960.8  401.74    4983  401.06  4994.3  396.42
    4997  395.92  5000.3  396.42  5018.2  401.95  5051.3   402.6  5250.8  408.11
  5344.3  413.01  5457.4  415.85  5775.5  416.16  5878.3  417.12  5994.1  418.09
#Mann= 9 ,-1 , 0
  3204.4     .05       0  4923.5     .16       0  4960.8     .12       0
  4994.3     .07       0  5000.3     .12       0  5051.3     .16       0
  5250.8     .05       0  5775.5     .16       0  5878.3     .05       0
Bank Sta=4994.3,5000.3
XS Rating Curve= 0 ,0
Exp/Cntr=0.3,0.1

Type RM Length L Ch R = 1 ,6535    ,223,223,223
BEGIN DESCRIPTION:
UNT0098 IN SAND CR 1.11
END DESCRIPTION:
XS GIS Cut Line= 3
      3488201.42     10533479.83      3487722.24     10531781.87
      3486560.74     10531052.67
#Sta/Elev= 30
  2917.9  421.89  3118.3     421  3206.9  418.84    3343   414.2  3612.2  408.12
  3669.7     405  3708.9  406.46  3742.9  401.85  3850.1  398.99  4471.6  394.81
  4474.3  394.31  4477.6  394.81  4592.4   397.3  4784.4  398.48  4820.9  396.86
  4857.4  398.26  4936.3  398.04  4972.9  400.85  4988.2  398.91  4995.6  395.94
  5001.1  394.93  5009.4  399.32  5067.1  402.25  5088.3  400.72  5103.6  402.29
  5124.8  401.65  5270.9  404.21  5662.4  415.02  6002.4  418.98  6053.6   419.1
#Mann= 5 ,-1 , 0
  2917.9     .05       0  4471.6     .07       0  4477.6     .05       0
  4995.6     .16       0  6002.4     .05       0
Bank Sta=4471.6,4477.6
XS Rating Curve= 0 ,0
Exp/Cntr=0.3,0.1

Type RM Length L Ch R = 1 ,6312    ,193,193,193
BEGIN DESCRIPTION:
UNT0098 IN SAND CR 1.112
END DESCRIPTION:
XS GIS Cut Line= 3
      3488328.91     10533513.92      3487877.52     10531618.07
      3486641.42     10530847.24
#Sta/Elev= 30
  2686.2  421.95  2867.6  420.58  2883.9  418.68  2935.3  417.24  3172.9  415.35
  3305.3  411.75  3425.7  410.68  3541.7  405.45  3582.9  402.15  3725.9  397.32
  4096.8  394.63  4240.8  394.37  4425.9  396.26    4580  395.17  4736.9  398.09
  4794.7  396.21  4971.4  400.56  4995.8  393.76  4998.6  393.26  5001.8  393.76
  5014.2   399.7    5030  401.37  5181.7  403.93  5470.8  411.67    5624   413.5
  5649.7  413.69  5770.7  415.49  5822.1   416.1  5870.4  416.88  6091.8  418.89
#Mann= 9 ,-1 , 0
  2686.2     .05       0  4995.8    .035       0  5001.8     .05       0
    5030     .16       0    5624     .05       0  5649.7      .1       0
  5770.7     .05       0  5822.1      .1       0  5870.4     .05       0
Bank Sta=4995.8,5001.8
XS Rating Curve= 0 ,0
Exp/Cntr=0.3,0.1

Type RM Length L Ch R = 1 ,6119    ,672,672,672
BEGIN DESCRIPTION:
UNT0098 IN SAND CR 1.1
END DESCRIPTION:
XS GIS Cut Line= 3
      3488435.88     10533565.08       3488012.7     10531449.18
      3486495.36     10530625.48
#Sta/Elev= 30
  2450.3  422.22  2650.3  420.88  2729.2   416.8  2790.3  416.69  2810.7  419.62
  2900.2  415.03  3155.1  409.65  3160.2  411.37  3211.2  410.58  3461.1   399.4
  3677.6  395.43  4034.5  393.49  4554.6   394.6  4673.8  397.39  4848.7  397.15
  4968.5   400.9  4984.3  399.11    4993  393.18  4995.8  392.68    4999  393.18
  5028.4  403.28  5147.8  405.72  5322.1   410.1  5431.9  413.64  5488.5  414.67
  5658.1  416.59  5766.8  417.19  6110.7  418.91  6168.9     417  6334.6  419.55
#Mann= 9 ,-1 , 0
  2450.3     .05       0    4993    .035       0    4999     .05       0
  5147.8     .16       0  5322.1     .05       0  5431.9     .16       0
  5488.5     .05       0  5658.1      .1       0  5766.8     .05       0
Bank Sta=4993,4999
XS Rating Curve= 0 ,0
Exp/Cntr=0.3,0.1

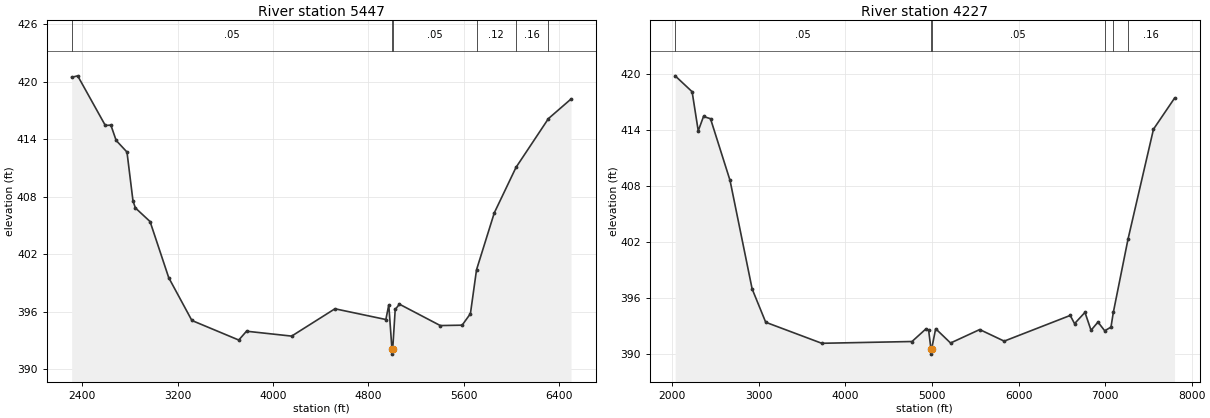
Type RM Length L Ch R = 1 ,5447    ,1220,1220,1220
BEGIN DESCRIPTION:
UNT0098 IN SAND CR 1.111
END DESCRIPTION:
XS GIS Cut Line= 4
       3488467.8     10533381.97      3488176.13     10531034.74
      3487960.85     10530486.12      3486759.43     10530215.28
#Sta/Elev= 30
    2312  420.46  2362.7  420.62  2594.5  415.44  2640.9  415.48  2685.2  413.88
  2775.9  412.67  2826.3  407.57  2846.4  406.84  2969.4  405.42    3126  399.56
    3320   395.1    3713  393.06  3777.9  393.98  4156.4  393.47  4519.2  396.32
  4946.1   395.2  4970.5  396.72  4997.3  392.09  5000.1  391.59  5003.3  392.09
  5024.4  396.25  5059.9   396.8  5402.2  394.57  5585.4  394.61  5654.9  395.81
  5706.1  400.39  5855.1  406.33  6037.1  411.07  6308.9  416.16  6498.2   418.2
#Mann= 6 ,-1 , 0
    2312     .05       0  4997.3     .03       0  5003.3     .05       0
  5706.1     .12       0  6037.1     .16       0  6308.9     .12       0
Bank Sta=4997.3,5003.3
XS Rating Curve= 0 ,0
Exp/Cntr=0.3,0.1

Type RM Length L Ch R = 1 ,4227    ,0,0,0
BEGIN DESCRIPTION:
UNT0098 IN SAND CR 1.0
END DESCRIPTION:
XS GIS Cut Line= 4
      3488749.11     10533595.35      3489243.91     10530444.27
       3488714.4      10529984.2      3486839.38     10530105.73
#Sta/Elev= 30
  2032.1  419.78  2228.2  418.08    2299  413.89  2359.8  415.43  2440.8  415.19
  2666.2  408.59  2921.6  396.98  3078.5  393.41  3726.3  391.16  4768.9  391.35
  4930.9  392.71  4961.3  392.53  4988.6   390.5  4991.4     390  4994.6   390.5
  5042.2  392.72  5214.3  391.19  5551.2  392.63  5834.1  391.39    6597  394.14
  6647.1  393.26  6767.3  394.47  6837.5  392.55  6917.6  393.43  6995.5   392.5
  7067.9  392.89  7094.8  394.46  7264.9  402.31    7559  414.07  7802.2  417.39
#Mann= 6 ,-1 , 0
  2032.1     .05       0  4988.6     .03       0  4994.6     .05       0
  6995.5     .16       0  7094.8     .12       0  7264.9     .16       0
Bank Sta=4988.6,4994.6
XS Rating Curve= 0 ,0
Exp/Cntr=0.3,0.1

Chan Stop Cuts=-1
Use User Specified Reach Order=0
Composite Channel Slope=5