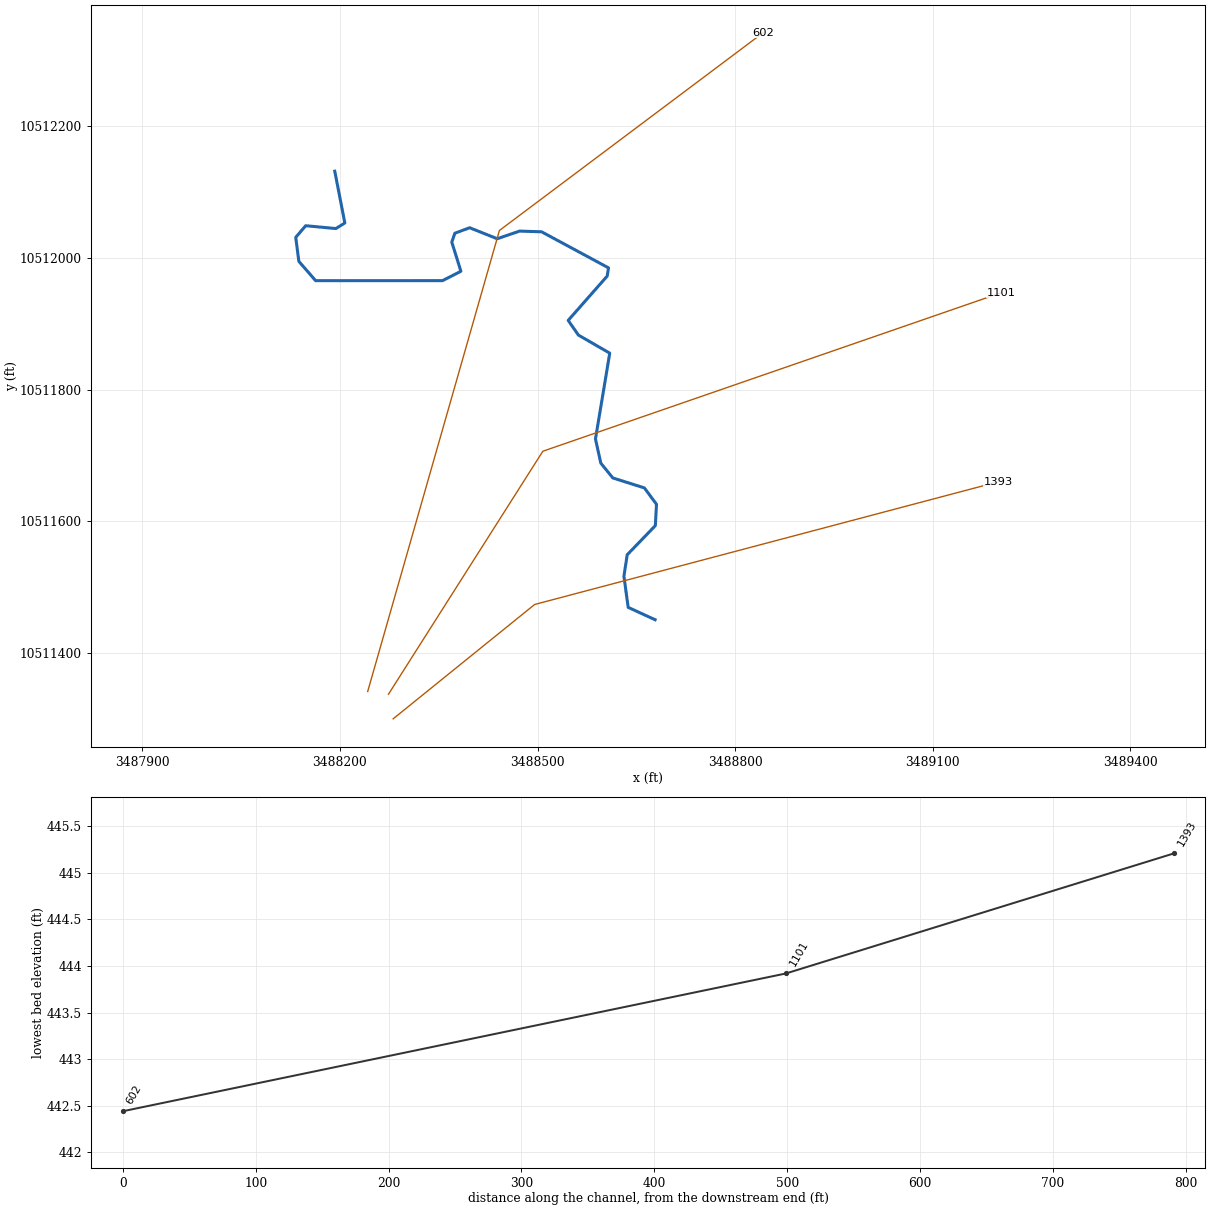
--- UNT0101 IN SAND CR.prj (project) ---

Proj Title=UNT0101 IN SAND CR Base Level Engineering
Current Plan=p01
Default Exp/Contr=0.3,0.1
English Units
Geom File=g01
Flow File=f01
Plan File=p01
BEGIN DESCRIPTION:
UNT0101 IN SAND CR
END DESCRIPTION:

--- UNT0101 IN SAND CR.p01 (plan) ---

Plan Title=Multiple Run
Short Identifier=Multiple
Geom File=g01
Flow File=f01
Subcritical Flow
K Sum by GR= 0
Std Step Tol= 0.01
Critical Tol= 0.01
Num of Std Step Trials= 20
Max Error Tol= 0.3
Flow Tol Ratio= 0.001
Split Flow NTrial= 30
Split Flow Tol= 0.02
Split Flow Ratio= 0.02
Log Output Level= 0
Friction Slope Method= 1
Unsteady Friction Slope Method= 2
Unsteady Bridges Friction Slope Method= 1
Parabolic Critical Depth
Global Vel Dist=  1 , 1 , 1
Global Log Level= 0
CheckData=True
Encroach Param= -1, 0, 0, 0
BEGIN DESCRIPTION:
Multiple Run
END DESCRIPTION:

--- UNT0101 IN SAND CR.f01 (steady flow) ---

Flow Title=Multiple
Number of Profiles=7
Profile Names=10-year,25-year,50-year,1pct_min,100-year,1pct_plu,500-year
River Rch & RM= UNT0101 IN SAND ,Reach-1,1393
     912    1244    1516    1348    1824    2466    2630
Boundary for River Rch & Prof#=UNT0101 IN SAND ,Reach-1,1
Up Type=0
Dn Type=3
Dn Slope=0.005
Boundary for River Rch & Prof#=UNT0101 IN SAND ,Reach-1,2
Up Type=0
Dn Type=3
Dn Slope=0.005
Boundary for River Rch & Prof#=UNT0101 IN SAND ,Reach-1,3
Up Type=0
Dn Type=3
Dn Slope=0.005
Boundary for River Rch & Prof#=UNT0101 IN SAND ,Reach-1,4
Up Type=0
Dn Type=3
Dn Slope=0.005
Boundary for River Rch & Prof#=UNT0101 IN SAND ,Reach-1,5
Up Type=0
Dn Type=3
Dn Slope=0.005
Boundary for River Rch & Prof#=UNT0101 IN SAND ,Reach-1,6
Up Type=0
Dn Type=3
Dn Slope=0.005
Boundary for River Rch & Prof#=UNT0101 IN SAND ,Reach-1,7
Up Type=0
Dn Type=3
Dn Slope=0.005

--- UNT0101 IN SAND CR.g01 (geometry) ---

Geom Title=Existing Conditions

River Reach=UNT0101 IN SAND ,Reach-1
Reach XY= 30
      3488678.47     10511450.61      3488637.62     10511469.39
      3488631.13     10511516.54      3488636.10     10511549.24
      3488678.85     10511593.48      3488680.58     10511625.87
      3488662.22     10511650.74      3488614.23     10511665.92
      3488596.03     10511688.43      3488587.92     10511725.17
      3488609.60     10511855.34      3488562.09     10511882.77
      3488546.50     10511905.10      3488605.71     10511972.35
      3488607.79     10511984.85      3488506.11     10512039.62
      3488472.68     10512040.67      3488438.80     10512029.09
      3488396.85     10512045.78      3488374.46     10512037.45
      3488369.77     10512023.91      3488383.63     10511979.70
      3488355.75     10511965.46      3488163.10     10511965.38
      3488137.59     10511994.71      3488132.84     10512031.15
      3488147.98     10512048.86      3488193.79     10512044.54
      3488207.38     10512053.02      3488192.11     10512131.64

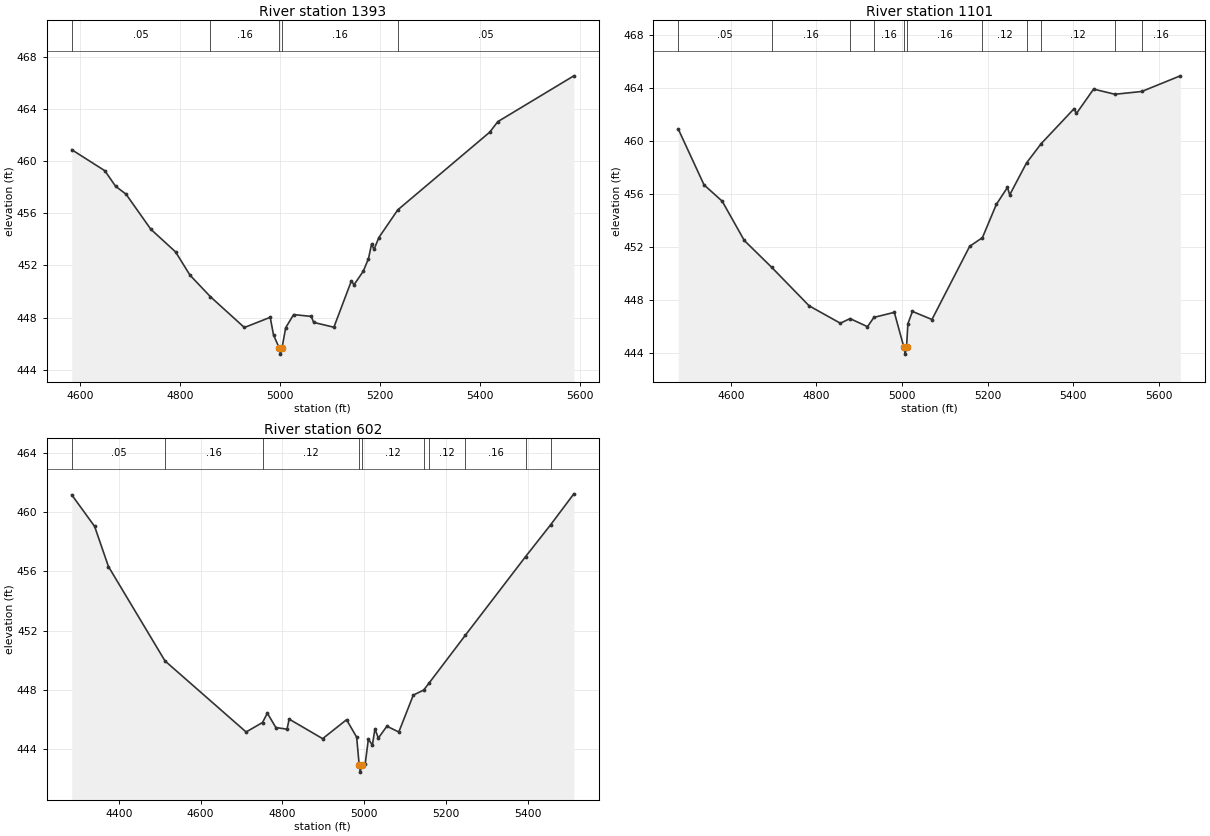
Type RM Length L Ch R = 1,1393,292,292,292
BEGIN DESCRIPTION:
UNT0101 IN SAND CR 1.0
END DESCRIPTION:
XS GIS Cut Line= 3
      3488280.72     10511300.14      3488495.59     10511473.77
      3489199.02     10511659.91
#Sta/Elev= 30
  4583.3  460.87  4649.4  459.26  4670.9  458.07  4691.7  457.47  4741.3  454.78
  4790.9  453.04  4819.7  451.26  4860.5  449.61  4928.4  447.25  4980.1  448.03
  4986.7  446.68  4997.8  445.71  5000.5  445.21  5003.8  445.71  5011.1  447.24
  5026.9  448.24  5062.0  448.10  5067.1  447.64  5107.4  447.27  5142.4  450.82
  5147.6  450.52  5166.3  451.57  5176.6  452.53  5182.7  453.63  5187.8  453.24
  5197.3  454.14  5235.1  456.26  5418.9  462.21  5435.2  463.02  5587.2  466.53
#Mann=5,-1,0
  4583.3    0.05       0  4860.5    0.16       0  4997.8    0.07       0
  5003.8    0.16       0  5235.1    0.05       0
Bank Sta=4997.8,5003.8
Exp/Cntr=0.3,0.1

Type RM Length L Ch R = 1,1101,499,499,499
BEGIN DESCRIPTION:
UNT0101 IN SAND CR 2.0
END DESCRIPTION:
XS GIS Cut Line= 3
      3488273.63     10511337.50      3488508.02     10511706.44
      3489203.61     10511946.97
#Sta/Elev= 30
  4477.4  460.89  4537.7  456.68  4580.1  455.45  4631.7  452.49  4695.9  450.46
  4783.3  447.56  4856.2  446.25  4878.8  446.60  4919.6  445.99  4934.6  446.69
  4982.3  447.07  5004.8  444.42  5007.6  443.92  5010.8  444.42  5014.0  446.21
  5024.6  447.14  5070.2  446.53  5158.4  452.05  5188.1  452.70  5220.7  455.21
  5246.6  456.49  5251.9  455.93  5291.3  458.34  5325.5  459.79  5402.5  462.43
  5407.8  462.06  5447.9  463.90  5497.7  463.51  5560.4  463.72  5650.5  464.90
#Mann=11,-1,0
  4477.4    0.05       0  4695.9    0.16       0  4878.8    0.12       0
  4934.6    0.16       0  5004.8    0.07       0  5010.8    0.16       0
  5188.1    0.12       0  5291.3    0.05       0  5325.5    0.12       0
  5497.7    0.05       0  5560.4    0.16       0
Bank Sta=5004.8,5010.8
Exp/Cntr=0.3,0.1

Type RM Length L Ch R = 1,602,0,0,0
BEGIN DESCRIPTION:
UNT0101 IN SAND CR 3.0
END DESCRIPTION:
XS GIS Cut Line= 3
      3488242.11     10511341.67      3488442.11     10512041.64
      3488842.12     10512341.65
#Sta/Elev= 30
  4285.0  461.16  4340.9  459.03  4374.7  456.32  4513.0  449.95  4711.4  445.15
  4751.5  445.79  4763.4  446.42  4784.2  445.45  4811.5  445.34  4816.7  446.02
  4898.6  444.70  4957.1  445.98  4981.8  444.80  4987.9  442.94  4990.6  442.44
  4993.9  442.94  5002.6  442.99  5010.4  444.66  5020.3  444.27  5026.5  445.36
  5034.9  444.74  5055.7  445.54  5084.9  445.15  5120.3  447.64  5145.7  447.98
  5158.3  448.43  5247.3  451.67  5394.9  456.99  5456.5  459.15  5513.0  461.23
#Mann=10,-1,0
  4285.0    0.05       0  4513.0    0.16       0  4751.5    0.12       0
  4987.9    0.07       0  4993.9    0.12       0  5145.7    0.16       0
  5158.3    0.12       0  5247.3    0.16       0  5394.9    0.12       0
  5456.5    0.05       0
Bank Sta=4987.9,4993.9
Exp/Cntr=0.3,0.1

Chan Stop Cuts=-1