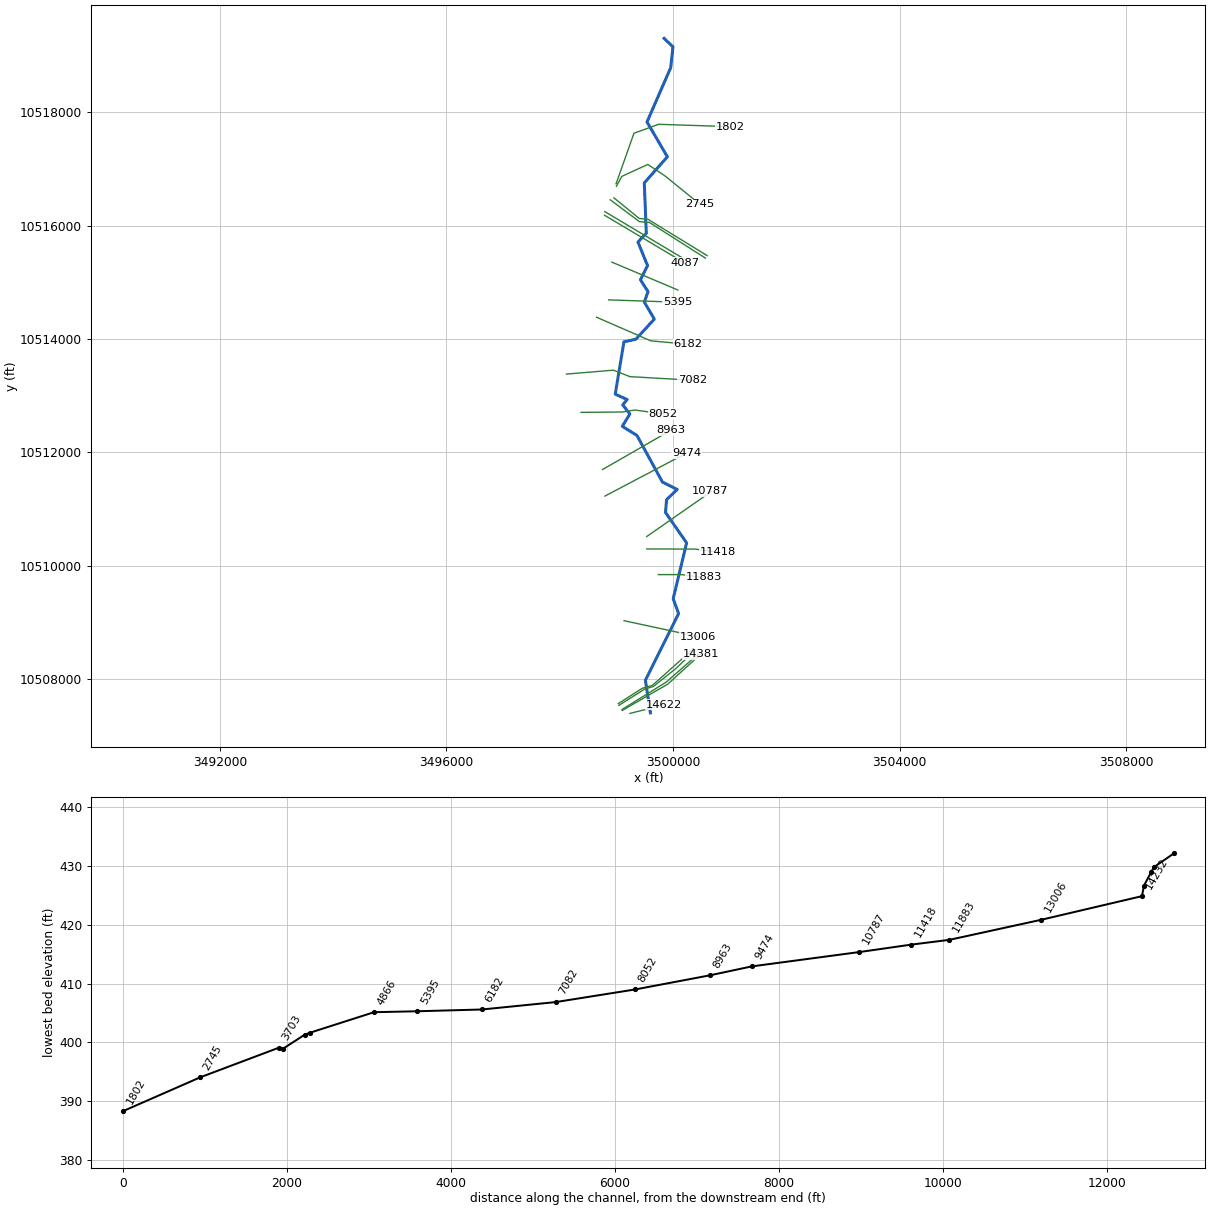
--- UNT0104 IN SAND CR.prj (project) ---

Proj Title=UNT0104 IN SAND CR Base Level Engineering
Current Plan=p01
Default Exp/Contr=0.3,0.1
English Units
Geom File=g01
Flow File=f01
Plan File=p01
Y Axis Title=Elevation
X Axis Title(PF)=Main Channel Distance
X Axis Title(XS)=Station
BEGIN DESCRIPTION:
UNT0104 IN SAND CR
END DESCRIPTION:
DSS Export Rating Curves= 0
DSS Export Rating Curve Sorted= 0
DSS Export Volume Flow Curves= 0
DXF OffsetX= 0
DXF OffsetY= 0
DXF ScaleX= 1
DXF ScaleY= 10

--- UNT0104 IN SAND CR.p01 (plan) ---

Plan Title=Multiple Run
Short Identifier=Multiple
Geom File=g01
Flow File=f01
Subcritical Flow
K Sum by GR= 0
Std Step Tol= 0.01
Critical Tol= 0.01
Num of Std Step Trials= 20
Max Error Tol= 0.3
Flow Tol Ratio= 0.001
Split Flow NTrial= 30
Split Flow Tol= 0.02
Split Flow Ratio= 0.02
Log Output Level= 0
Friction Slope Method= 1
Unsteady Friction Slope Method= 2
Unsteady Bridges Friction Slope Method= 1
Parabolic Critical Depth
Global Vel Dist=  1 , 1 , 1
Global Log Level= 0
CheckData=True
Encroach Param= -1, 0, 0, 0
BEGIN DESCRIPTION:
Multiple Run
END DESCRIPTION:

--- UNT0104 IN SAND CR.f01 (steady flow) ---

Flow Title=Multiple
Number of Profiles=7
Profile Names=10-year,25-year,50-year,1pct_min,100-year,1pct_plu,500-year
River Rch & RM= UNT0104 IN SAND ,Reach-1,14622
    1584    2242    2801    2551    3450    4665    5220
River Rch & RM= UNT0104 IN SAND ,Reach-1,9474
    2005    2854    3577    3263    4413    5968    6703
Boundary for River Rch & Prof#=UNT0104 IN SAND ,Reach-1,1
Up Type=0
Dn Type=3
Dn Slope=0.005
Boundary for River Rch & Prof#=UNT0104 IN SAND ,Reach-1,2
Up Type=0
Dn Type=3
Dn Slope=0.005
Boundary for River Rch & Prof#=UNT0104 IN SAND ,Reach-1,3
Up Type=0
Dn Type=3
Dn Slope=0.005
Boundary for River Rch & Prof#=UNT0104 IN SAND ,Reach-1,4
Up Type=0
Dn Type=3
Dn Slope=0.005
Boundary for River Rch & Prof#=UNT0104 IN SAND ,Reach-1,5
Up Type=0
Dn Type=3
Dn Slope=0.005
Boundary for River Rch & Prof#=UNT0104 IN SAND ,Reach-1,6
Up Type=0
Dn Type=3
Dn Slope=0.005
Boundary for River Rch & Prof#=UNT0104 IN SAND ,Reach-1,7
Up Type=0
Dn Type=3
Dn Slope=0.005

--- UNT0104 IN SAND CR.g01 (geometry) ---

Geom Title=Existing Conditions
Program Version=4.10

River Reach=UNT0104 IN SAND ,Reach-1
Reach XY= 30
      3499602.11     10507401.64      3499513.63     10507976.76
      3500099.68     10509152.85      3500004.55     10509416.02
      3500241.36     10510401.34      3499868.66     10510937.75
      3499887.21     10511164.35      3500076.31     10511344.41
       3499813.7     10511476.15      3499364.78     10512297.91
      3499105.97     10512458.96      3499239.64     10512677.36
      3499113.71     10512837.85      3499192.11     10512931.64
      3498981.15     10513026.55      3499134.96     10513950.71
      3499344.96      10513996.2      3499671.33     10514351.45
       3499494.5     10514652.84      3499560.56      10514835.8
        3499426.     10515046.48      3499552.13     10515296.45
      3499382.04     10515711.72      3499529.79     10515867.02
      3499494.37     10516755.78      3499901.71     10517217.07
      3499542.54     10517831.67      3499960.95     10518791.41
      3500000.54     10519156.24      3499844.46     10519307.86

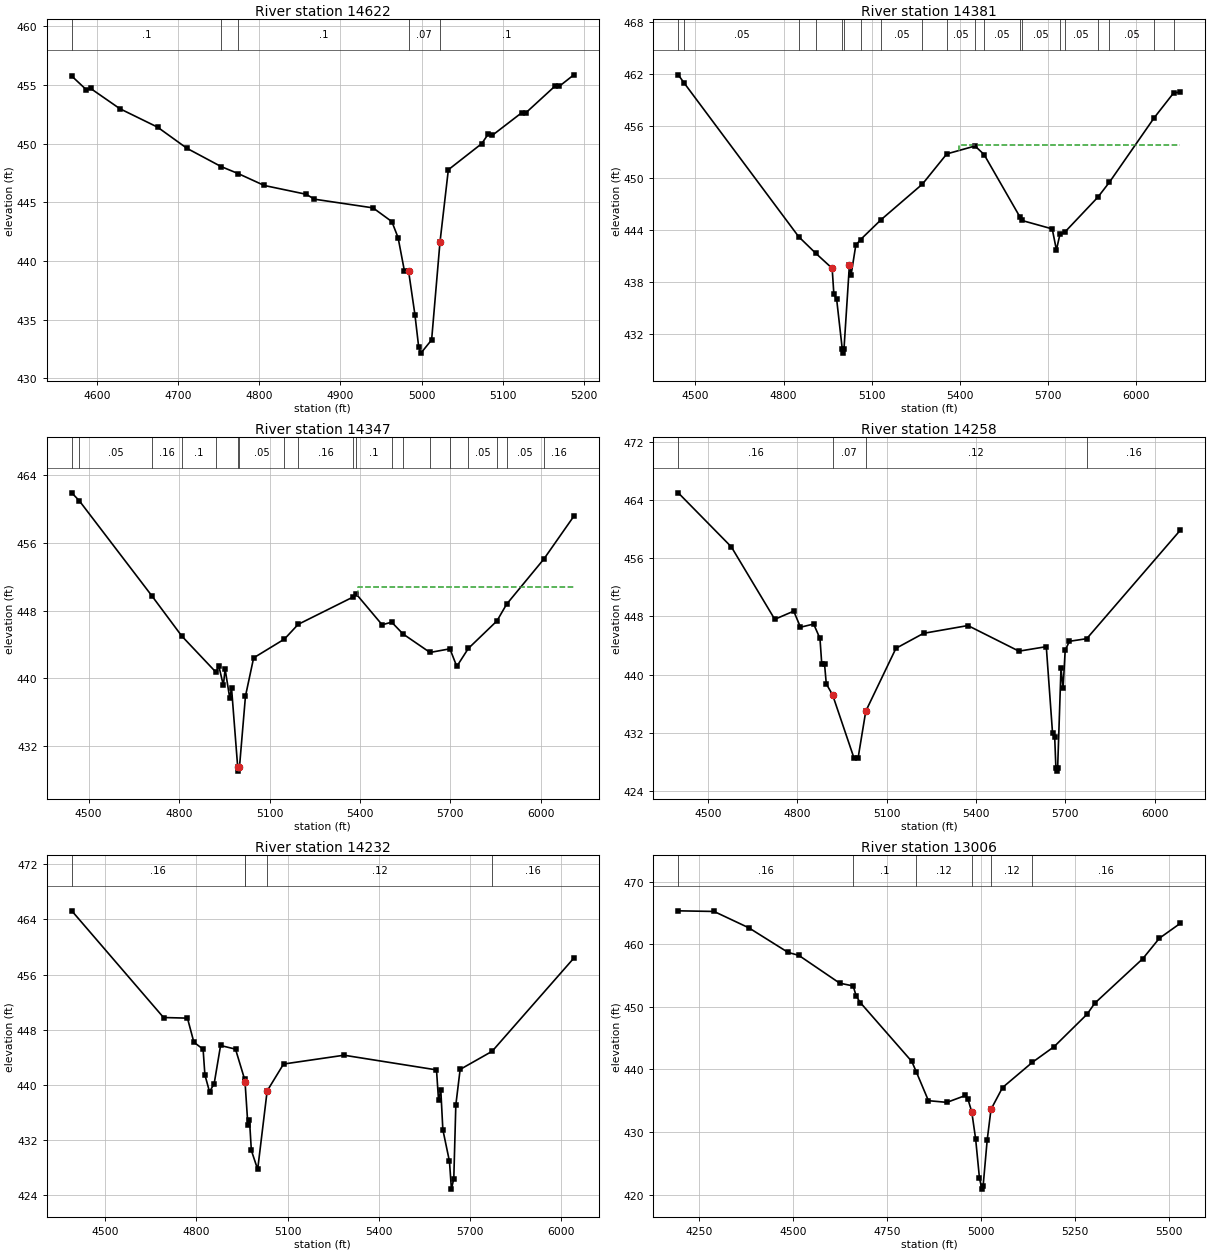
Type RM Length L Ch R = 1 ,14622   ,241,241,241
BEGIN DESCRIPTION:
UNT0104 IN SAND CR 27.0
END DESCRIPTION:
XS GIS Cut Line= 3
      3499242.07     10507391.63      3499642.11     10507491.64
       3499842.1     10507541.64
#Sta/Elev= 30
    4569  455.75  4587.1  454.58  4592.2   454.7  4628.3  452.97  4674.7   451.4
  4710.8   449.6    4753  448.04  4774.1  447.44  4806.1  446.43  4857.7  445.68
    4868  445.26  4940.1  444.52  4963.3  443.35    4971  441.98  4978.8  439.14
  4983.9  439.14  4991.7  435.43  4996.4  432.64  4999.1  432.14  5012.3  433.27
  5022.6   441.6  5032.9  447.77  5074.1     450  5081.8  450.79    5087   450.7
  5123.1  452.62  5128.2  452.61  5164.3   454.9  5169.5  454.88  5187.5  455.86
#Mann= 5 ,-1 , 0
    4569      .1       0    4753     .16       0  4774.1      .1       0
  4983.9     .07       0  5022.6      .1       0
Bank Sta=4983.9,5022.6
XS Rating Curve= 0 ,0
Exp/Cntr=0.3,0.1

Type RM Length L Ch R = 1 ,14381   ,34,34,34
BEGIN DESCRIPTION:
UNT0104 IN SAND CR 26.1
END DESCRIPTION:
XS GIS Cut Line= 3
      3499105.63     10507443.46      3499908.63     10507907.89
      3500485.86     10508433.04
#Sta/Elev= 30
  4441.8  461.89  4462.1  460.94  4851.6  443.24  4908.8  441.36  4965.4   439.6
  4971.2  436.64  4980.7  436.04  4999.7  430.33  5002.5  429.83  5005.7  430.33
  5024.2  440.03    5030  438.87  5045.8  442.26    5062  442.91  5132.1  445.21
  5272.4   449.3  5355.4  452.78  5451.5  453.69  5482.2  452.71    5604  445.53
  5611.2  445.11  5714.1  444.14  5728.3  441.72  5740.2   443.5  5756.4  443.75
  5869.2  447.79  5908.9  449.53  6061.3  456.96  6127.2  459.81  6149.8  459.89
#Mann= 20 ,-1 , 0
  4441.8     .16       0  4462.1     .05       0  4851.6      .1       0
  4908.8     .05       0  4999.7     .04       0  5005.7     .05       0
    5062     .12       0  5132.1     .05       0  5272.4     .16       0
  5355.4     .05       0  5451.5      .1       0  5482.2     .05       0
    5604     .12       0  5611.2     .05       0  5740.2     .12       0
  5756.4     .05       0  5869.2     .16       0  5908.9     .05       0
  6061.3     .16       0  6127.2     .05       0
#XS Ineff= 2 , 0
                         5396.07          453.85
Permanent Ineff=
       F       F
Bank Sta=4965.4,5024.2
XS Rating Curve= 0 ,0
Exp/Cntr=0.3,0.1

Type RM Length L Ch R = 1 ,14347   ,89,89,89
BEGIN DESCRIPTION:
UNT0104 IN SAND CR 26.0
END DESCRIPTION:
XS GIS Cut Line= 3
      3499101.36     10507460.86      3499880.41     10507942.61
      3500444.25     10508437.05
#Sta/Elev= 30
  4443.9  461.91  4468.7  460.98  4709.2  449.76  4809.1  444.98  4922.5  440.71
  4931.5  441.49  4946.9  439.17  4952.7  441.09  4968.1  437.65    4974  438.86
  4994.4  429.53  4997.1  429.03  5000.4  429.53  5020.2  437.88  5047.3  442.41
  5149.5  444.63  5195.1  446.37  5378.4  449.62  5386.9  449.99  5473.7  446.32
  5505.4  446.63  5542.8  445.24  5632.5  443.05  5698.6  443.48  5721.4   441.4
  5759.6  443.52  5854.5  446.77  5886.7  448.75  6010.4  454.09  6109.8  459.15
#Mann= 19 ,-1 , 0
  4443.9     .16       0  4468.7     .05       0  4709.2     .16       0
  4809.1      .1       0  4922.5     .05       0  4994.4     .07       0
  5000.4     .05       0  5149.5     .05       0  5195.1     .16       0
  5378.4     .05       0  5386.9      .1       0  5505.4     .05       0
  5542.8     .12       0  5632.5     .05       0  5698.6     .12       0
  5759.6     .05       0  5854.5     .16       0  5886.7     .05       0
  6010.4     .16       0
#XS Ineff= 2 , 0
                         5393.54          450.79
Permanent Ineff=
       F       F
Bank Sta=4994.4,5000.4
XS Rating Curve= 0 ,0
Exp/Cntr=0.3,0.1

Type RM Length L Ch R = 1 ,14258   ,26,26,26
BEGIN DESCRIPTION:
UNT0104 IN SAND CR 24.0
END DESCRIPTION:
XS GIS Cut Line= 5
      3499044.88     10507532.44      3499509.32     10507825.42
      3499652.55     10507864.49      3500049.68     10508181.33
      3500396.94     10508513.39
#Sta/Elev= 30
  4400.1  465.05  4578.4   457.6  4724.3  447.61  4787.9  448.74  4810.6  446.52
  4854.9  446.96  4876.1  444.97    4882  441.49  4891.4  441.46  4897.3  438.71
  4918.5  437.19  4990.1  428.51  5003.9  428.44  5029.9  434.94  5131.2  443.61
    5224  445.68  5372.9  446.75  5544.3  443.22  5636.1  443.84  5657.2  431.88
  5664.4  431.33  5668.3  427.18  5671.1  426.68  5674.3  427.18  5685.5  440.89
  5692.4  438.08  5699.6  443.35  5713.8  444.58  5771.9  444.94  6086.2   459.9
#Mann= 4 ,-1 , 0
  4400.1     .16       0  4918.5     .07       0  5029.9     .12       0
  5771.9     .16       0
#XS Ineff= 2 , 0
                         5373.31          446.64
Permanent Ineff=
       F       F
Bank Sta=4918.5,5029.9
XS Rating Curve= 0 ,0
Exp/Cntr=0.3,0.1

Type RM Length L Ch R = 1 ,14232   ,1226,1226,1226
BEGIN DESCRIPTION:
UNT0104 IN SAND CR 24.1
END DESCRIPTION:
XS GIS Cut Line= 4
      3499034.08     10507562.85      3499457.24     10507834.11
      3499637.36     10507886.19      3500355.65     10508526.36
#Sta/Elev= 30
  4389.8  465.25  4691.8  449.77  4770.5  449.68  4791.6  446.19    4822  445.17
  4827.9  441.45  4843.2  438.99  4858.4  440.17  4879.5  445.71  4928.7  445.18
  4958.4  440.84    4960  440.43  4969.4  434.16  4974.6  434.96  4980.8  430.49
  5001.6  427.73  5032.8  439.12  5086.8  443.02  5285.8   444.3  5590.1  442.17
  5596.8  437.79  5604.3  439.22    5611   433.5  5632.8  428.89  5639.2  424.87
    5647  426.38  5653.7  437.08  5667.9  442.24  5773.2  444.87  6042.1  458.39
#Mann= 5 ,-1 , 0
  4389.8     .16       0  4958.4     .12       0    4960     .07       0
  5032.8     .12       0  5773.2     .16       0
#XS Ineff= 2 , 0
         4883.99  445.62  5294.1          444.07
Permanent Ineff=
       F       F
Bank Sta=4960,5032.8
XS Rating Curve= 0 ,0
Exp/Cntr=0.3,0.1

Type RM Length L Ch R = 1 ,13006   ,1123,1123,1123
BEGIN DESCRIPTION:
UNT0104 IN SAND CR 22.0
END DESCRIPTION:
XS GIS Cut Line= 2
      3499138.27     10509027.67      3500444.66     10508745.56
#Sta/Elev= 30
  4193.8  465.32  4289.1  465.22  4381.9   462.6  4486.1  458.68  4514.9   458.2
  4623.7  453.76  4659.4  453.32  4667.8  451.66  4678.6  450.65  4815.6  441.25
  4827.9  439.54  4859.8  434.99    4909  434.72  4958.3  435.82    4965  435.24
  4975.2  433.18  4985.5  428.86  4995.7  422.59  5002.2  420.86  5005.4  421.36
  5016.2   428.7  5026.4  433.61  5057.1  437.09  5136.5  441.12  5194.4  443.62
  5282.2  448.81  5302.6  450.56  5430.5  457.68  5474.6  460.94  5530.3  463.32
#Mann= 6 ,-1 , 0
  4193.8     .16       0  4659.4      .1       0  4827.9     .12       0
  4975.2     .07       0  5026.4     .12       0  5136.5     .16       0
Bank Sta=4975.2,5026.4
XS Rating Curve= 0 ,0
Exp/Cntr=0.3,0.1

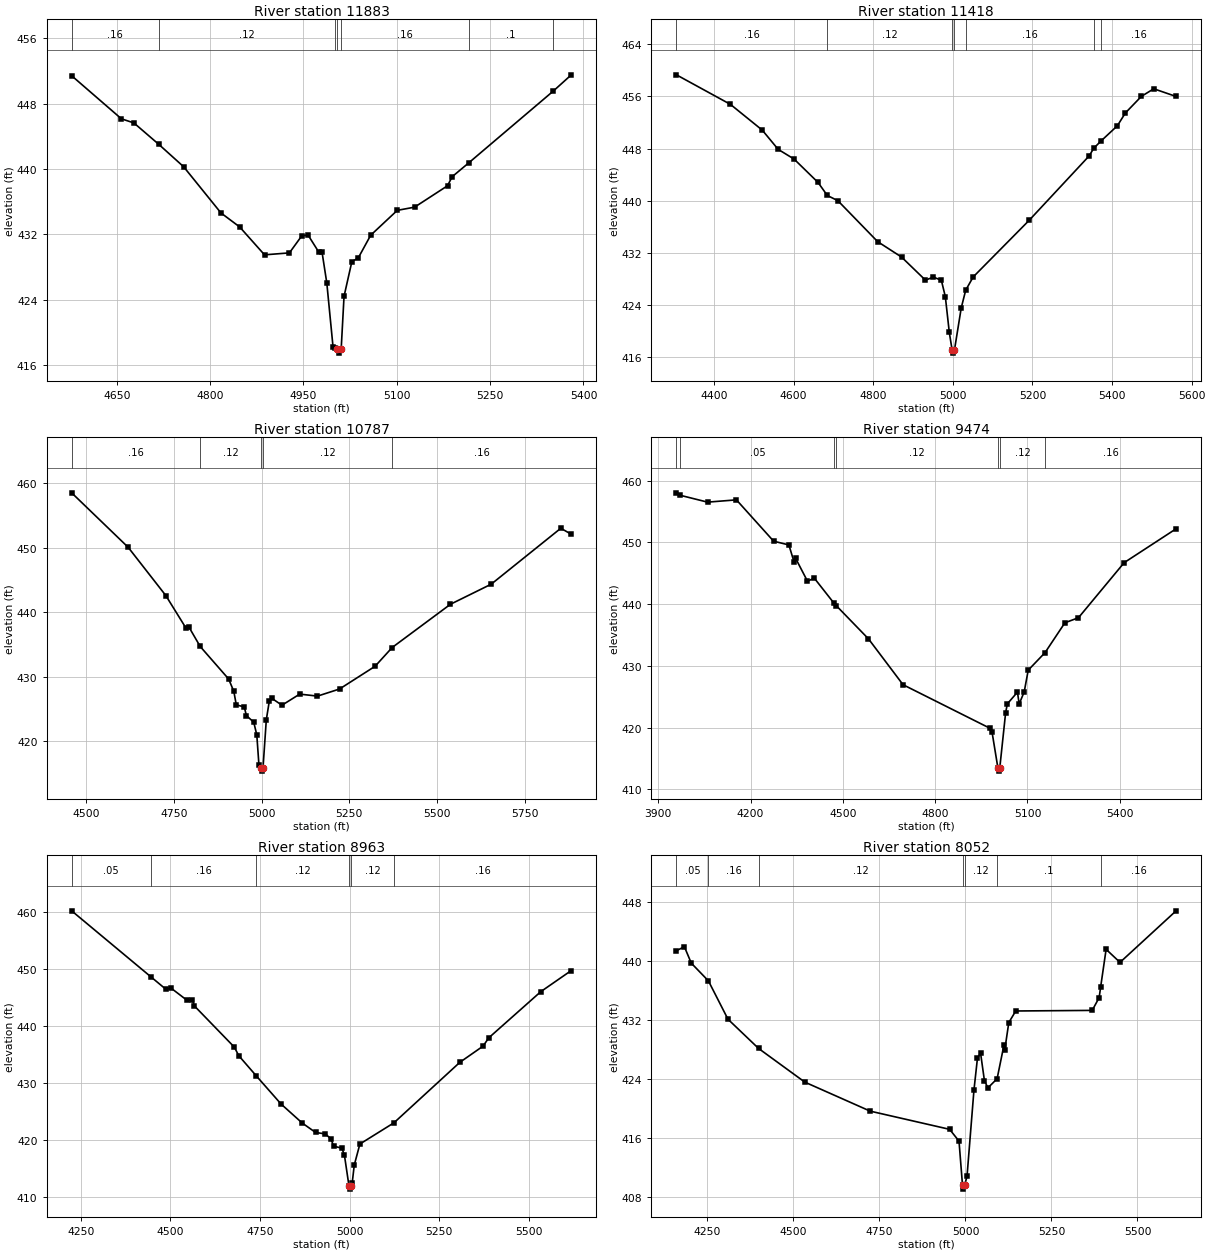
Type RM Length L Ch R = 1 ,11883   ,465,465,465
BEGIN DESCRIPTION:
UNT0104 IN SAND CR 21.0
END DESCRIPTION:
XS GIS Cut Line= 3
      3499742.11     10509841.64      3500142.11     10509841.64
       3500542.1     10509791.64
#Sta/Elev= 30
  4577.4  451.42  4657.4  446.14  4677.4  445.64  4717.2  443.03  4757.4  440.27
  4817.4  434.61  4847.4   432.9  4887.4  429.48  4927.4  429.72  4947.4  431.82
  4957.4   431.9  4974.9  429.78  4979.9  429.78  4987.5  426.03  4997.5  418.21
  5000.6  418.09  5004.6  417.94  5007.4  417.44  5010.6  417.94  5015.2   424.4
  5027.8  428.66  5037.9  429.08    5058  431.88  5100.8  434.93  5128.6  435.32
  5181.5  437.94    5189  439.05  5215.4  440.73  5351.5  449.54  5380.5  451.53
#Mann= 7 ,-1 , 0
  4577.4     .16       0  4717.2     .12       0  5000.6     .16       0
  5004.6     .07       0  5010.6     .16       0  5215.4      .1       0
  5351.5     .05       0
Bank Sta=5004.6,5010.6
XS Rating Curve= 0 ,0
Exp/Cntr=0.3,0.1

Type RM Length L Ch R = 1 ,11418   ,631,631,631
BEGIN DESCRIPTION:
UNT0104 IN SAND CR 20.0
END DESCRIPTION:
XS GIS Cut Line= 3
      3499536.42     10510294.01      3500392.11     10510291.64
      3500788.49     10510238.64
#Sta/Elev= 30
  4305.4   459.3  4441.1  454.77  4521.1  450.82  4561.1  447.87  4601.1  446.38
  4661.1  442.81  4684.6   440.8  4711.1     440  4811.1  433.72  4871.1  431.36
  4931.1  427.82  4951.1  428.29  4971.1   427.8  4981.1  425.29  4991.1   419.8
  4998.1  417.13  5000.8  416.63  5004.1  417.13  5021.1  423.57  5032.3  426.28
  5051.1  428.31  5191.4  436.97  5342.7  446.88    5354  448.04  5372.4  449.16
  5413.3  451.48  5433.5  453.45  5473.8     456  5504.9  457.16    5561  455.98
#Mann= 7 ,-1 , 0
  4305.4     .16       0  4684.6     .12       0  4998.1     .07       0
  5004.1     .12       0  5032.3     .16       0    5354      .1       0
  5372.4     .16       0
Bank Sta=4998.1,5004.1
XS Rating Curve= 0 ,0
Exp/Cntr=0.3,0.1

Type RM Length L Ch R = 1 ,10787   ,1313,1313,1313
BEGIN DESCRIPTION:
UNT0104 IN SAND CR 18.0
END DESCRIPTION:
XS GIS Cut Line= 3
       3499537.5     10510513.12      3500683.37     10511311.75
      3500657.28     10511311.75
#Sta/Elev= 30
  4459.4  458.48  4620.2  450.05  4727.5  442.57  4784.2  437.59  4792.9  437.73
  4825.4  434.68  4906.4  429.64  4921.2  427.72  4928.2  425.63  4950.9  425.32
    4957  423.97  4977.9  422.95  4986.6  420.98  4992.7  416.32  4998.3  415.87
  5001.1  415.37  5004.3  415.87  5013.7  423.34  5022.4  426.27  5028.5  426.68
  5058.2  425.58  5108.8   427.3  5159.4  426.99  5222.2  428.09  5323.4  431.61
  5372.1  434.52  5538.1  441.22  5654.1  444.33  5852.3  452.99  5882.2  452.06
#Mann= 5 ,-1 , 0
  4459.4     .16       0  4825.4     .12       0  4998.3     .07       0
  5004.3     .12       0  5372.1     .16       0
Bank Sta=4998.3,5004.3
XS Rating Curve= 0 ,0
Exp/Cntr=0.3,0.1

Type RM Length L Ch R = 1 ,9474    ,511,511,511
BEGIN DESCRIPTION:
UNT0104 IN SAND CR 16.0
END DESCRIPTION:
XS GIS Cut Line= 2
      3498800.35     10511228.04      3500237.48      10511984.8
#Sta/Elev= 30
  3958.9  458.05  3972.1  457.64  4060.1  456.54  4153.9  456.91  4274.8  450.21
  4324.5   449.6  4340.9  446.89  4346.5  447.41  4384.9  443.72    4407  444.22
  4471.6  440.12  4478.4  439.76  4583.2  434.37  4695.5  426.94    4978  419.88
  4984.9  419.23  5003.9  413.43  5006.7  412.93  5009.9  413.43    5029  422.42
  5034.6  423.84  5067.4  425.74    5073  423.82  5089.4  425.79  5102.4   429.3
  5157.2  432.15  5221.6  436.98  5265.7   437.8  5414.3  446.73  5583.1  452.22
#Mann= 7 ,-1 , 0
  3958.9      .1       0  3972.1     .05       0  4471.6     .16       0
  4478.4     .12       0  5003.9     .07       0  5009.9     .12       0
  5157.2     .16       0
Bank Sta=5003.9,5009.9
XS Rating Curve= 0 ,0
Exp/Cntr=0.3,0.1

Type RM Length L Ch R = 1 ,8963    ,911,911,911
BEGIN DESCRIPTION:
UNT0104 IN SAND CR 15.0
END DESCRIPTION:
XS GIS Cut Line= 2
      3498758.67     10511696.79      3499967.03     10512391.25
#Sta/Elev= 30
  4224.6  460.14  4445.5  448.59  4486.6  446.45  4502.4  446.58  4545.6  444.51
  4561.4  444.51  4567.1  443.48  4678.4  436.27  4690.8  434.77    4740  431.21
  4808.7  426.31  4867.6  422.99    4905  421.33  4932.3  421.08  4948.1  420.19
  4955.2  418.93  4978.3  418.59  4985.5  417.32  4998.3  411.91    5001  411.41
  5004.3  411.91    5007  412.43  5012.9  415.63  5028.6  419.31  5123.5  423.02
  5307.5  433.62  5372.2  436.45    5388   437.9  5533.2  445.99  5618.3  449.69
#Mann= 6 ,-1 , 0
  4224.6     .05       0  4445.5     .16       0    4740     .12       0
  4998.3     .07       0  5004.3     .12       0  5123.5     .16       0
Bank Sta=4998.3,5004.3
XS Rating Curve= 0 ,0
Exp/Cntr=0.3,0.1

Type RM Length L Ch R = 1 ,8052    ,970,970,970
BEGIN DESCRIPTION:
UNT0104 IN SAND CR 13.0
END DESCRIPTION:
XS GIS Cut Line= 4
      3498379.04      10512705.2      3499108.22     10512712.14
      3499330.44     10512746.87      3499823.54     10512677.41
#Sta/Elev= 30
  4160.1  441.38  4183.2  441.93  4203.2   439.7    4253  437.29  4309.9  432.08
  4398.9  428.11  4533.2  423.54  4723.2   419.6    4954  417.13  4981.3  415.53
  4991.5  409.51  4994.2  409.01  4997.5  409.51  5004.6  410.76  5024.8  422.49
  5034.9  426.79    5044  427.47  5055.2  423.73  5065.3  422.76    5092     424
  5111.8  428.54  5114.2   427.9    5126  431.63  5146.2   433.2  5368.4  433.28
  5388.6  435.02  5393.1  436.52  5408.8  441.57  5449.2   439.8  5612.2   446.8
#Mann= 7 ,-1 , 0
  4160.1     .05       0    4253     .16       0  4398.9     .12       0
  4991.5     .07       0  4997.5     .12       0    5092      .1       0
  5393.1     .16       0
Bank Sta=4991.5,4997.5
XS Rating Curve= 0 ,0
Exp/Cntr=0.3,0.1

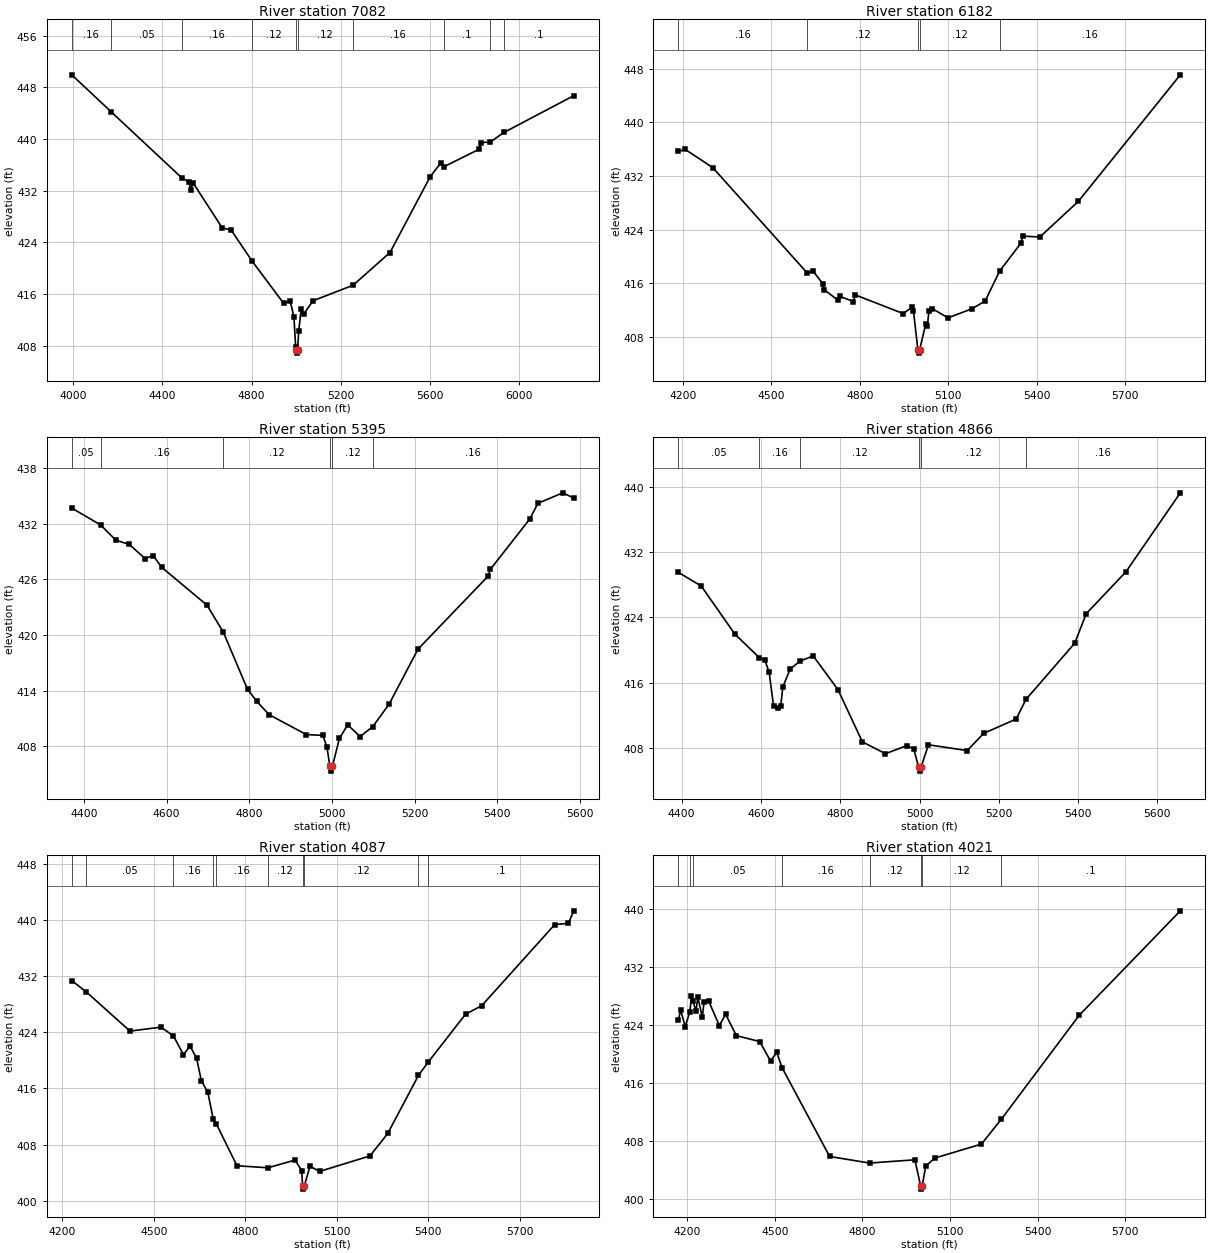
Type RM Length L Ch R = 1 ,7082    ,900,900,900
BEGIN DESCRIPTION:
UNT0104 IN SAND CR 11.0
END DESCRIPTION:
XS GIS Cut Line= 4
      3498119.77     10513380.81      3498949.63     10513450.26
       3499241.3     10513335.67       3500345.5     10513273.17
#Sta/Elev= 30
  3993.2  449.93  4168.8  444.24  4488.2  433.94  4517.4   433.4  4527.4  432.14
  4537.4  433.21  4667.9  426.25    4708  425.91  4801.9  421.11  4943.3  414.58
  4973.1  414.88  4989.8  412.46  4997.5  407.75  4999.9  407.36  5002.7  406.86
  5005.9  407.36  5011.3  410.29    5022  413.63  5032.8  412.88  5075.7  414.97
  5254.8  417.36  5420.6  422.43  5600.9  434.16  5649.5  436.34  5660.7  435.67
  5821.2  438.43  5828.1  439.45  5870.2  439.52  5931.7  441.01  6245.3  446.71
#Mann= 10 ,-1 , 0
  3993.2     .16       0  4168.8     .05       0  4488.2     .16       0
  4801.9     .12       0  4999.9     .07       0  5005.9     .12       0
  5254.8     .16       0  5660.7      .1       0  5870.2     .16       0
  5931.7      .1       0
Bank Sta=4999.9,5005.9
XS Rating Curve= 0 ,0
Exp/Cntr=0.3,0.1

Type RM Length L Ch R = 1 ,6182    ,787,787,787
BEGIN DESCRIPTION:
UNT0104 IN SAND CR 10.0
END DESCRIPTION:
XS GIS Cut Line= 3
       3498652.1     10514384.68      3499606.98       10513968.
      3500266.66     10513907.24
#Sta/Elev= 30
  4183.6  435.68  4207.3  435.98  4300.9  433.26  4620.4   417.6  4641.9   417.8
  4673.9  415.98  4679.4  415.04  4726.2  413.49  4731.7  414.07  4778.5  413.29
    4784  414.29  4947.3   411.5  4976.7  412.43  4982.2  411.81  4997.1   406.1
  4999.9   405.6  5003.1   406.1  5023.5  409.92    5029  409.66  5034.6  411.87
  5045.5  412.25  5099.2  410.86  5180.4  412.21  5225.4  413.36  5274.2  417.81
  5347.7  422.04  5352.7  423.05  5411.3  422.92  5541.9  428.24  5887.9   447.1
#Mann= 5 ,-1 , 0
  4183.6     .16       0  4620.4     .12       0  4997.1     .07       0
  5003.1     .12       0  5274.2     .16       0
Bank Sta=4997.1,5003.1
XS Rating Curve= 0 ,0
Exp/Cntr=0.3,0.1

Type RM Length L Ch R = 1 ,5395    ,529,529,529
BEGIN DESCRIPTION:
UNT0104 IN SAND CR 9.0
END DESCRIPTION:
XS GIS Cut Line= 2
      3498865.12     10514691.31      3500078.81      10514649.7
#Sta/Elev= 30
  4370.8  433.71  4440.3   431.9  4477.8  430.23    4510  429.79  4547.9  428.26
  4567.9  428.58  4587.9  427.33    4698  423.22  4737.5  420.29    4796  414.13
    4818  412.85  4848.1   411.4  4938.1  409.25  4978.1  409.16  4988.1  407.88
  4995.2   405.8  4997.9   405.3  5001.2   405.8  5018.2  408.84  5038.2   410.3
  5068.2  409.03  5099.1  410.12  5138.2  412.52  5208.3  418.48    5378  426.37
    5383  427.08  5478.4  432.52  5498.4  434.23  5558.5  435.36  5585.2  434.79
#Mann= 6 ,-1 , 0
  4370.8     .05       0  4440.3     .16       0  4737.5     .12       0
  4995.2     .07       0  5001.2     .12       0  5099.1     .16       0
Bank Sta=4995.2,5001.2
XS Rating Curve= 0 ,0
Exp/Cntr=0.3,0.1

Type RM Length L Ch R = 1 ,4866    ,779,779,779
BEGIN DESCRIPTION:
UNT0104 IN SAND CR 7.0
END DESCRIPTION:
XS GIS Cut Line= 2
      3498920.68     10515357.99      3500087.28     10514864.97
#Sta/Elev= 30
  4391.4  429.52  4449.5  427.83  4534.1  421.95  4595.7  419.06  4610.1  418.74
  4620.8  417.24  4631.8  413.13  4642.6  412.86  4649.9  413.09  4655.3  415.46
  4673.6  417.65  4698.9  418.64  4731.9  419.26  4794.6  415.11  4855.8  408.73
  4914.1  407.28  4968.3  408.27  4985.2  407.88  4997.9  405.64  5000.7  405.14
  5003.9  405.64  5022.6  408.37  5120.3  407.66  5161.9  409.77  5243.9  411.53
  5268.5  413.93  5391.5  420.82  5420.6  424.44  5520.9  429.59  5657.9  439.26
#Mann= 6 ,-1 , 0
  4391.4     .05       0  4595.7     .16       0  4698.9     .12       0
  4997.9     .07       0  5003.9     .12       0  5268.5     .16       0
Bank Sta=4997.9,5003.9
XS Rating Curve= 0 ,0
Exp/Cntr=0.3,0.1

Type RM Length L Ch R = 1 ,4087    ,66,66,66
BEGIN DESCRIPTION:
UNT0104 IN SAND CR 5.0
END DESCRIPTION:
XS GIS Cut Line= 2
      3498793.13     10516184.36      3500207.61     10515342.61
#Sta/Elev= 30
  4231.4  431.36  4279.5  429.73  4422.3  424.17  4523.6  424.73  4564.8  423.48
  4597.6  420.82    4619  422.02  4640.4  420.35    4656  417.13  4677.5  415.43
    4695  411.66  4705.5  410.94  4772.9  404.99  4874.4   404.7  4963.3   405.8
  4985.2  404.31    4988  402.16  4990.7  401.66    4994  402.16  5012.4  404.92
  5043.6  404.18  5209.1  406.39  5267.5   409.6    5368  417.86  5399.9  419.75
  5522.6  426.59  5575.2  427.78  5814.7  439.34  5859.4  439.52  5877.4   441.3
#Mann= 10 ,-1 , 0
  4231.4      .1       0  4279.5     .05       0  4564.8     .16       0
    4695     .05       0  4705.5     .16       0  4874.4     .12       0
    4988     .07       0    4994     .12       0    5368     .16       0
  5399.9      .1       0
Bank Sta=4988,4994
XS Rating Curve= 0 ,0
Exp/Cntr=0.3,0.1

Type RM Length L Ch R = 1 ,4021    ,262,262,262
BEGIN DESCRIPTION:
UNT0104 IN SAND CR 4.1
END DESCRIPTION:
XS GIS Cut Line= 2
      3498797.42     10516249.49      3500273.11     10515368.42
#Sta/Elev= 30
  4169.6  424.66    4178  426.01  4193.6  423.76  4209.4  425.84    4215  427.99
  4220.7  427.24  4230.6  425.85  4236.4  427.89    4252  425.05  4257.8  427.11
  4273.4  427.33  4310.3  423.89  4331.7  425.48  4368.7  422.51  4448.5   421.7
  4485.5  419.02  4506.9  420.21  4525.1  418.08  4687.8  405.83  4824.7  404.92
  4979.7  405.37    4999  401.82  5001.7  401.32    5005  401.82  5016.7  404.49
  5047.9  405.61  5207.4  407.54    5276  410.99  5542.1  425.32  5888.3  439.75
#Mann= 8 ,-1 , 0
  4169.6     .05       0  4209.4      .1       0  4220.7     .05       0
  4525.1     .16       0  4824.7     .12       0    4999     .07       0
    5005     .12       0    5276      .1       0
Bank Sta=4999,5005
XS Rating Curve= 0 ,0
Exp/Cntr=0.3,0.1

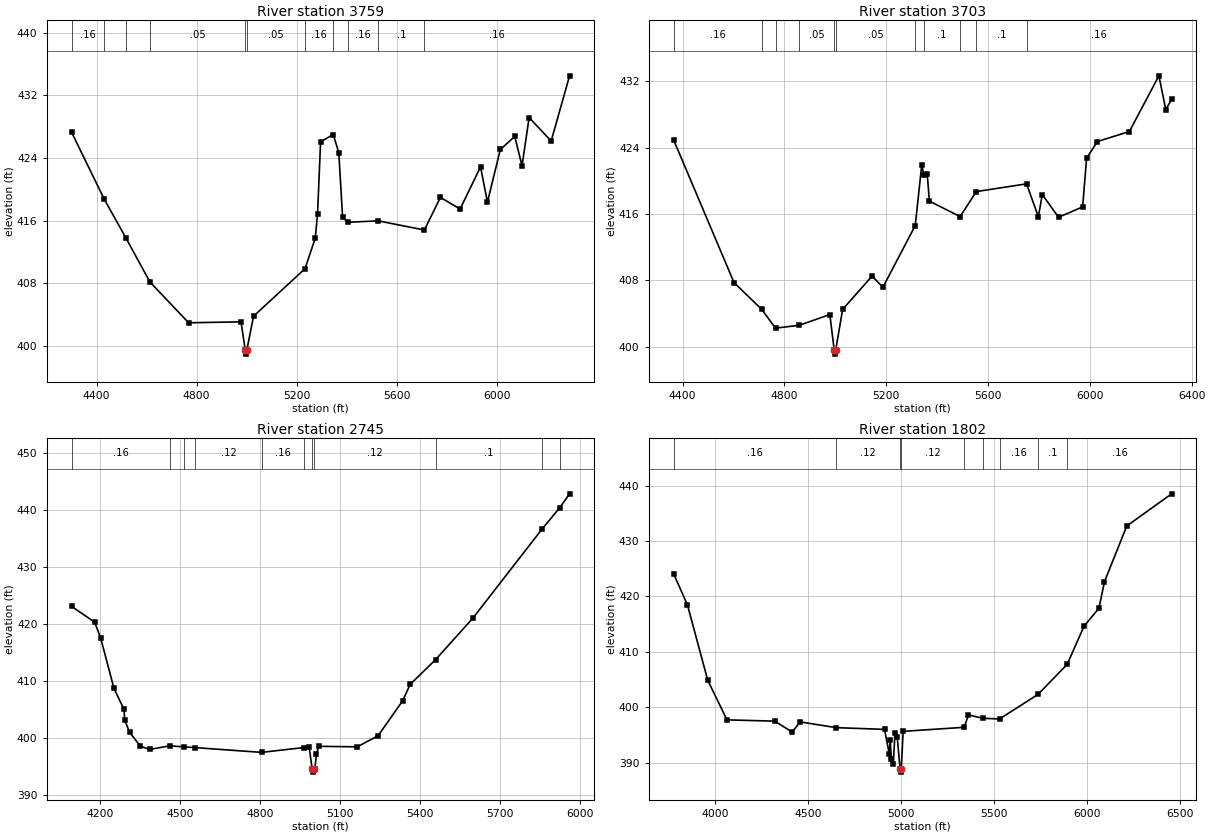
Type RM Length L Ch R = 1 ,3759    ,56,56,56
BEGIN DESCRIPTION:
UNT0104 IN SAND CR 4.0
END DESCRIPTION:
XS GIS Cut Line= 4
      3498892.95      10516457.8      3499409.44     10516071.52
      3499583.05      10516058.5      3500572.62     10515429.16
#Sta/Elev= 30
  4299.7  427.28  4430.1  418.75  4517.3  413.78    4613  408.17    4768  402.96
  4977.4  403.08  4994.5  399.46  4997.2  398.96  5000.5  399.46  5027.6   403.8
  5233.2  409.86  5274.5  413.77  5283.6   416.9  5295.6  426.06  5346.1  426.99
  5368.5  424.68  5383.7  416.41  5405.3  415.79  5526.1  415.97  5710.7   414.8
  5774.9  418.96  5853.6  417.48  5935.4  422.86  5962.9  418.36  6014.5  425.08
  6072.1  426.74  6101.3     423  6129.7  429.15  6217.8  426.16  6291.5  434.48
#Mann= 11 ,-1 , 0
  4299.7     .16       0  4430.1     .05       0  4517.3     .16       0
    4613     .05       0  4994.5     .04       0  5000.5     .05       0
  5233.2     .16       0  5346.1      .1       0  5405.3     .16       0
  5526.1      .1       0  5710.7     .16       0
Bank Sta=4994.5,5000.5
XS Rating Curve= 0 ,0
Exp/Cntr=0.3,0.1

Type RM Length L Ch R = 1 ,3703    ,958,958,958
BEGIN DESCRIPTION:
UNT0104 IN SAND CR 4.2
END DESCRIPTION:
XS GIS Cut Line= 4
      3498958.04     10516492.53       3499405.1     10516127.94
      3499557.01     10516114.92      3500602.98     10515472.58
#Sta/Elev= 30
  4364.4  424.96  4601.9  407.73  4711.1  404.48  4764.9  402.22  4859.1  402.58
  4978.4  403.87  4995.5  399.59  4998.2  399.09  5001.5  399.59  5028.6  404.48
  5144.3  408.51  5186.9  407.16    5314  414.61  5339.6  421.96  5347.3  420.75
  5360.9  420.84  5369.6  417.56  5490.1  415.69  5554.1  418.71  5751.3  419.64
  5797.7  415.67  5813.1  418.35    5877  415.61  5971.7  416.86  5987.2  422.73
  6029.7  424.75  6155.3  425.96  6271.3  432.68  6298.4  428.61  6321.2  429.83
#Mann= 11 ,-1 , 0
  4364.4     .16       0  4711.1     .05       0  4764.9     .16       0
  4859.1     .05       0  4995.5     .04       0  5001.5     .05       0
    5314     .16       0  5347.3      .1       0  5490.1     .16       0
  5554.1      .1       0  5751.3     .16       0
Bank Sta=4995.5,5001.5
XS Rating Curve= 0 ,0
Exp/Cntr=0.3,0.1

Type RM Length L Ch R = 1 ,2745    ,943,943,943
BEGIN DESCRIPTION:
UNT0104 IN SAND CR 3.0
END DESCRIPTION:
XS GIS Cut Line= 5
       3499001.6     10516695.97      3499097.89     10516870.99
      3499557.27      10517082.2       3499866.3     10516873.87
      3500477.28     10516377.44
#Sta/Elev= 30
  4094.4  423.08  4180.8  420.33  4203.6  417.52    4253  408.74  4290.9  405.03
  4293.3  403.18  4311.5  401.07  4351.9   398.6  4386.9  398.04  4462.2  398.66
  4514.6  398.49  4558.3  398.35  4805.8  397.52  4963.5  398.36  4984.5  398.39
  4995.6  394.56  4998.3  394.06  5001.6  394.56  5005.5  394.58  5011.6  397.24
  5020.5  398.58  5164.4  398.49  5242.6  400.44  5334.6  406.56  5362.6  409.43
  5457.8  413.76  5597.5  421.03  5856.1   436.6  5922.7  440.36  5959.7   442.8
#Mann= 11 ,-1 , 0
  4094.4     .16       0  4462.2     .12       0  4514.6     .16       0
  4558.3     .12       0  4805.8     .16       0  4963.5     .12       0
  4995.6     .07       0  5001.6     .12       0  5457.8      .1       0
  5856.1     .16       0  5922.7      .1       0
Bank Sta=4995.6,5001.6
XS Rating Curve= 0 ,0
Exp/Cntr=0.3,0.1

Type RM Length L Ch R = 1 ,1802    ,0,0,0
BEGIN DESCRIPTION:
UNT0104 IN SAND CR 2.0
END DESCRIPTION:
XS GIS Cut Line= 5
      3498996.89     10516741.21      3499312.09     10517633.01
      3499371.53     10517654.08      3499748.24     10517790.53
      3501012.16     10517748.87
#Sta/Elev= 30
  3778.6  424.11  3853.3  418.45    3962  404.88  4065.4  397.73  4322.3   397.5
  4415.4  395.53  4457.9  397.37    4651  396.33  4911.5  396.01  4936.8  391.61
  4942.1  394.08  4947.7  390.59  4958.3  389.74  4967.4  395.33  4979.6  394.62
  4995.1   388.8  4997.8   388.3  5001.1   388.8  5011.5  395.66  5339.2  396.39
  5362.1  398.63  5438.2  398.02  5528.8  397.89  5735.4  402.33  5892.2  407.75
  5982.5  414.63  6062.5  417.87  6092.5  422.68  6212.2  432.72  6452.8  438.52
#Mann= 9 ,-1 , 0
  3778.6     .16       0    4651     .12       0  4995.1     .07       0
  5001.1     .12       0  5339.2     .16       0  5438.2     .12       0
  5528.8     .16       0  5735.4      .1       0  5892.2     .16       0
Bank Sta=4995.1,5001.1
XS Rating Curve= 0 ,0
Exp/Cntr=0.3,0.1

Chan Stop Cuts=-1
Use User Specified Reach Order=0
Composite Channel Slope=5