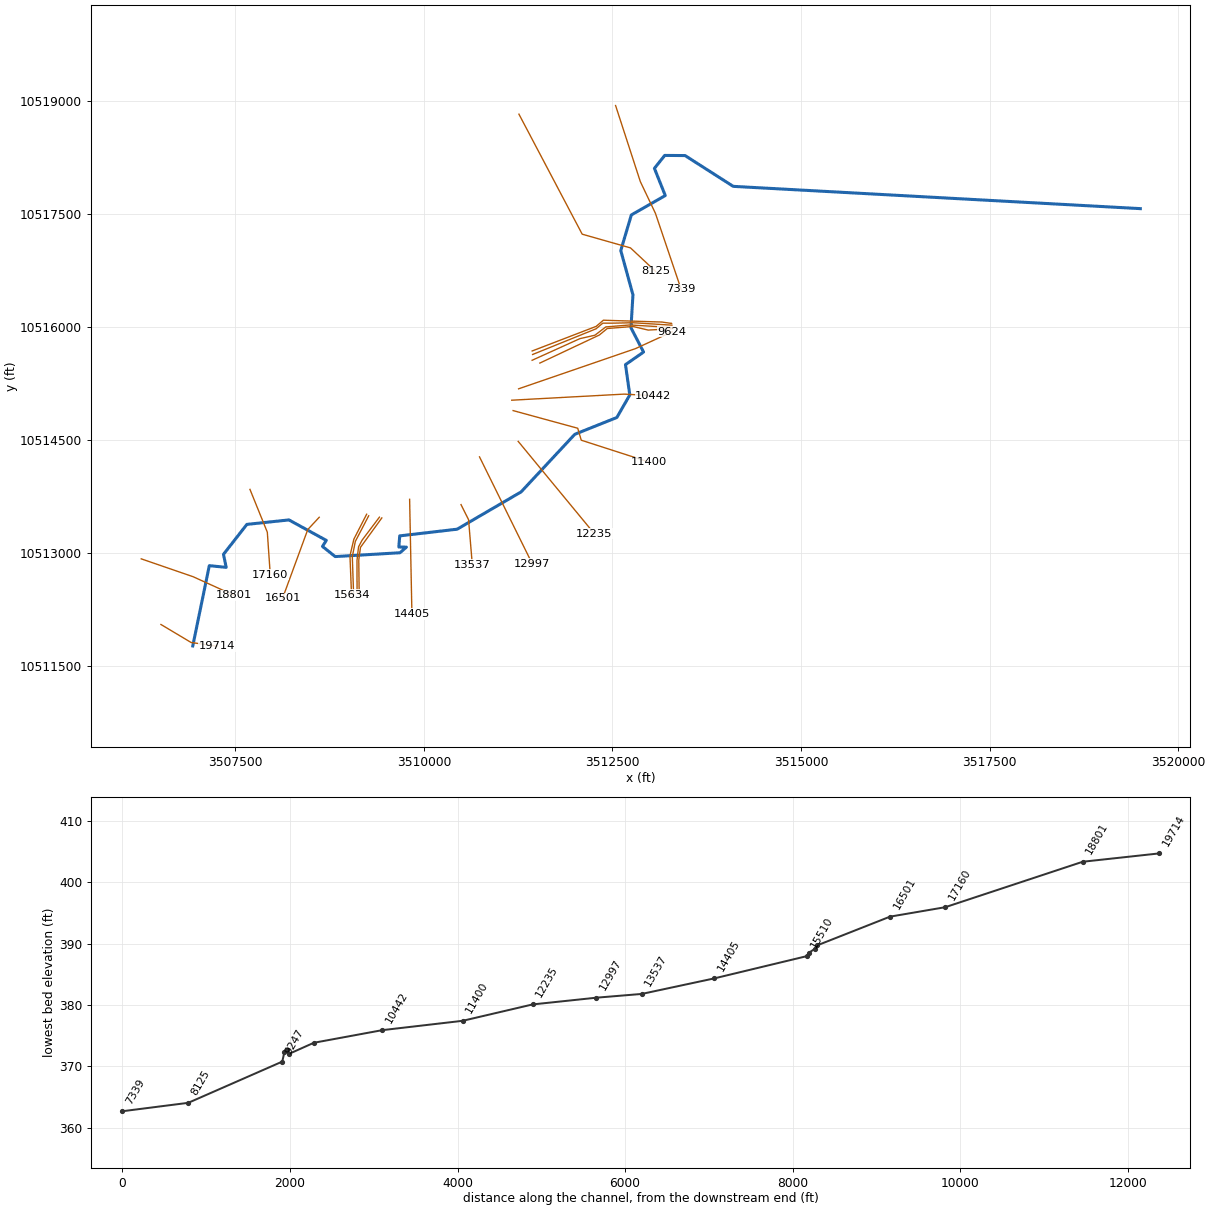
--- UNT0113 IN SAND CR.prj (project) ---

Proj Title=UNT0113 IN SAND CR Base Level Engineering
Current Plan=p01
Default Exp/Contr=0.3,0.1
English Units
Geom File=g01
Flow File=f01
Plan File=p01
BEGIN DESCRIPTION:
UNT0113 IN SAND CR
END DESCRIPTION:

--- UNT0113 IN SAND CR.p01 (plan) ---

Plan Title=Multiple Run
Short Identifier=Multiple
Geom File=g01
Flow File=f01
Subcritical Flow
K Sum by GR= 0
Std Step Tol= 0.01
Critical Tol= 0.01
Num of Std Step Trials= 20
Max Error Tol= 0.3
Flow Tol Ratio= 0.001
Split Flow NTrial= 30
Split Flow Tol= 0.02
Split Flow Ratio= 0.02
Log Output Level= 0
Friction Slope Method= 1
Unsteady Friction Slope Method= 2
Unsteady Bridges Friction Slope Method= 1
Parabolic Critical Depth
Global Vel Dist=  1 , 1 , 1
Global Log Level= 0
CheckData=True
Encroach Param= -1, 0, 0, 0
BEGIN DESCRIPTION:
Multiple Run
END DESCRIPTION:

--- UNT0113 IN SAND CR.f01 (steady flow) ---

Flow Title=Multiple
Number of Profiles=7
Profile Names=10-year,25-year,50-year,1pct_min,100-year,1pct_plu,500-year
River Rch & RM= UNT0113 IN SAND ,Reach-1,19714
     979    1338    1633    1454    1966    2659    2840
River Rch & RM= UNT0113 IN SAND ,Reach-1,17160
    1423    1983    2450    2205    2981    4032    4406
River Rch & RM= UNT0113 IN SAND ,Reach-1,10442
    1842    2590    3219    2910    3936    5323    5873
Boundary for River Rch & Prof#=UNT0113 IN SAND ,Reach-1,1
Up Type=0
Dn Type=3
Dn Slope=0.005
Boundary for River Rch & Prof#=UNT0113 IN SAND ,Reach-1,2
Up Type=0
Dn Type=3
Dn Slope=0.005
Boundary for River Rch & Prof#=UNT0113 IN SAND ,Reach-1,3
Up Type=0
Dn Type=3
Dn Slope=0.005
Boundary for River Rch & Prof#=UNT0113 IN SAND ,Reach-1,4
Up Type=0
Dn Type=3
Dn Slope=0.005
Boundary for River Rch & Prof#=UNT0113 IN SAND ,Reach-1,5
Up Type=0
Dn Type=3
Dn Slope=0.005
Boundary for River Rch & Prof#=UNT0113 IN SAND ,Reach-1,6
Up Type=0
Dn Type=3
Dn Slope=0.005
Boundary for River Rch & Prof#=UNT0113 IN SAND ,Reach-1,7
Up Type=0
Dn Type=3
Dn Slope=0.005

--- UNT0113 IN SAND CR.g01 (geometry) ---

Geom Title=Existing Conditions

River Reach=UNT0113 IN SAND ,Reach-1
Reach XY= 30
      3506935.97     10511764.78      3507155.17     10512830.93
      3507378.97     10512808.27      3507343.16     10512981.16
      3507653.03     10513378.98      3508210.79     10513438.30
      3508706.20     10513166.43      3508655.42     10513086.14
      3508824.25     10512951.59      3509682.61     10513002.40
      3509768.41     10513076.75      3509667.76     10513078.67
      3509679.67     10513226.53      3510440.66     10513315.13
      3511287.92     10513809.52      3512000.64     10514575.35
      3512558.34     10514798.41      3512729.64     10515097.22
      3512672.40     10515500.05      3512912.20     10515667.15
      3512745.10     10515989.41      3512771.56     10516426.89
      3512610.03     10517015.01      3512750.23     10517487.83
      3513200.00     10517745.72      3513056.09     10518106.72
      3513192.81     10518278.16      3513462.36     10518276.26
      3514100.92     10517867.35      3519497.95     10517571.64

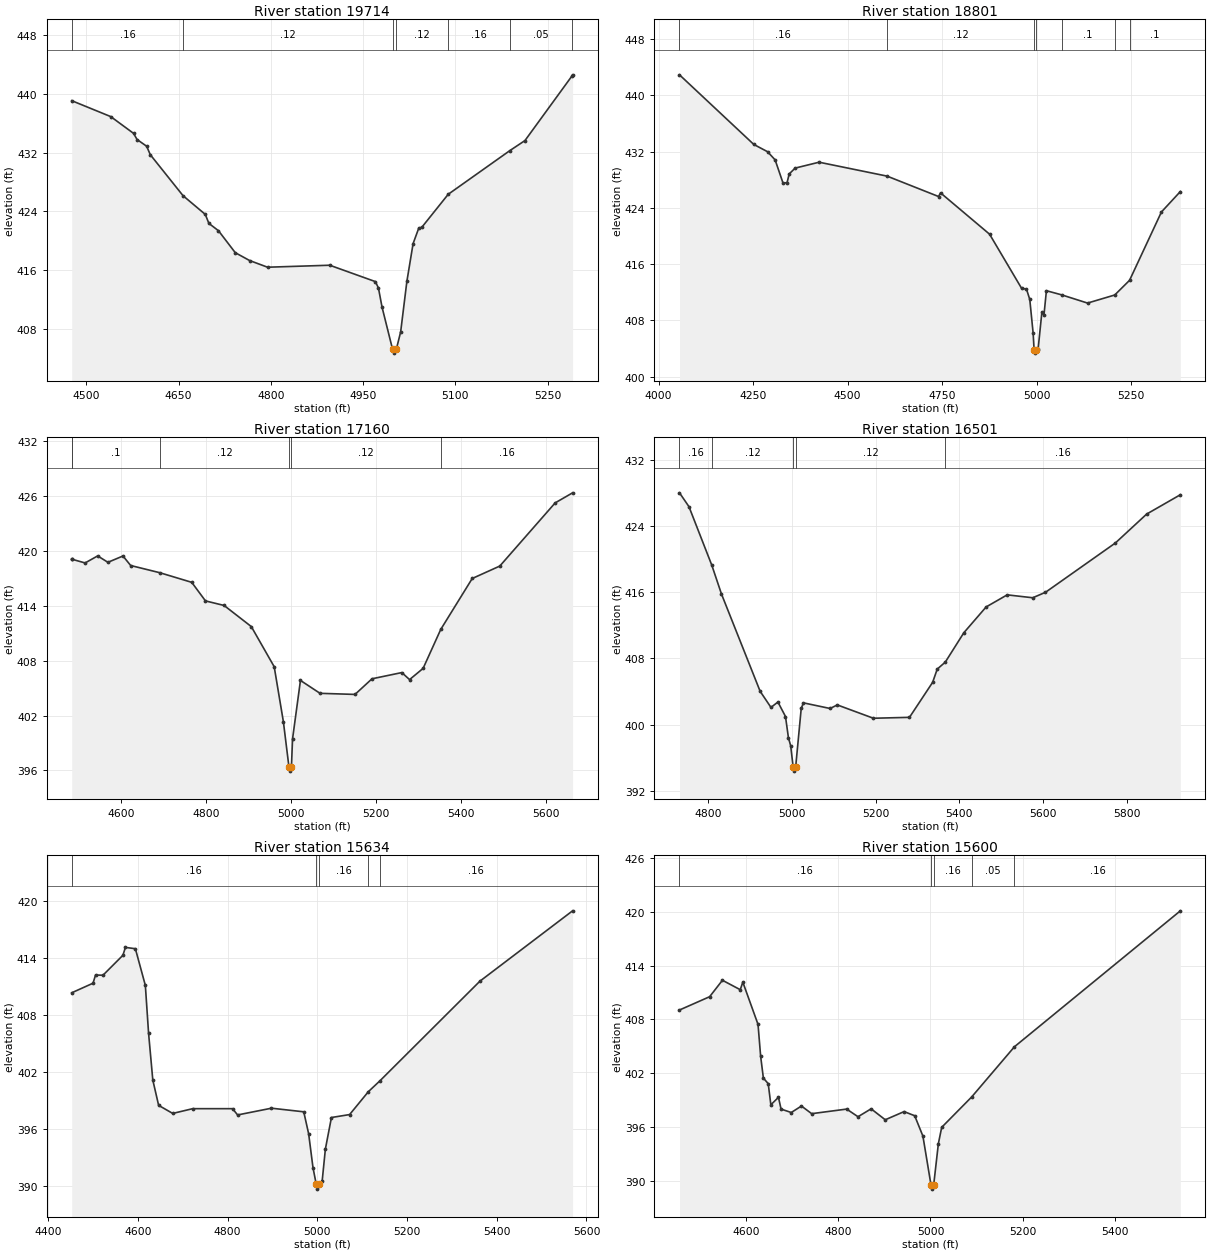
Type RM Length L Ch R = 1,19714,913,913,913
BEGIN DESCRIPTION:
UNT0113 IN SAND CR 27.0
END DESCRIPTION:
XS GIS Cut Line= 3
      3506513.91     10512050.03      3506913.24     10511811.30
      3507258.74     10511761.64
#Sta/Elev= 30
  4476.2  439.07  4539.7  436.90  4576.7  434.62  4582.5  433.78  4598.1  432.86
  4603.9  431.72  4657.2  426.13  4693.4  423.58  4699.2  422.36  4714.8  421.36
  4742.1  418.37  4765.4  417.30  4794.6  416.39  4895.7  416.66  4969.9  414.43
  4974.9  413.55  4980.7  410.96  4997.9  405.19  5000.7  404.69  5003.9  405.19
  5011.0  407.59  5021.1  414.46  5031.2  419.60  5040.4  421.71  5045.4  421.83
  5088.3  426.32  5188.7  432.28  5213.1  433.64  5289.2  442.40  5290.5  442.59
#Mann=7,-1,0
  4476.2    0.16       0  4657.2    0.12       0  4997.9    0.07       0
  5003.9    0.12       0  5088.3    0.16       0  5188.7    0.05       0
  5289.2    0.16       0
Bank Sta=4997.9,5003.9
Exp/Cntr=0.3,0.1

Type RM Length L Ch R = 1,18801,1641,1641,1641
BEGIN DESCRIPTION:
UNT0113 IN SAND CR 25.0
END DESCRIPTION:
XS GIS Cut Line= 3
      3506252.94     10512921.25      3506940.46     10512684.26
      3507484.75     10512436.86
#Sta/Elev= 30
  4055.2  442.92  4251.7  433.02  4288.2  431.98  4308.2  430.82  4329.3  427.49
  4339.9  427.60  4345.4  428.82  4361.1  429.65  4424.5  430.49  4604.4  428.51
  4740.5  425.61  4745.8  426.13  4875.5  420.25  4960.0  412.57  4973.2  412.43
  4981.9  410.96  4990.8  406.16  4993.3  403.83  4996.0  403.33  4999.3  403.83
  5003.9  403.88  5013.9  409.15  5019.4  408.74  5025.9  412.21  5066.2  411.62
  5134.7  410.45  5206.7  411.60  5245.9  413.69  5330.2  423.41  5380.3  426.32
#Mann=7,-1,0
  4055.2    0.16       0  4604.4    0.12       0  4993.3    0.07       0
  4999.3    0.12       0  5066.2     0.1       0  5206.7    0.05       0
  5245.9     0.1       0
Bank Sta=4993.3,4999.3
Exp/Cntr=0.3,0.1

Type RM Length L Ch R = 1,17160,659,659,659
BEGIN DESCRIPTION:
UNT0113 IN SAND CR 24.0
END DESCRIPTION:
XS GIS Cut Line= 3
      3507694.31     10513843.50      3507924.33     10513274.94
      3507963.39     10512710.72
#Sta/Elev= 30
  4484.6  419.10  4484.9  419.10  4516.1  418.69  4545.7  419.46  4569.8  418.76
  4605.3  419.45  4623.4  418.41  4692.1  417.62  4767.1  416.57  4799.4  414.54
  4843.3  414.04  4907.3  411.73  4961.2  407.34  4982.8  401.33  4995.8  396.42
  4998.6  395.92  5001.8  396.42  5004.4  399.45  5023.0  405.84  5069.1  404.43
  5151.4  404.31  5191.4  406.02  5261.6  406.70  5279.8  405.93  5311.7  407.16
  5353.2  411.42  5427.3  416.99  5492.2  418.35  5622.5  425.26  5663.5  426.36
#Mann=6,-1,0
  4484.6    0.05       0  4484.9     0.1       0  4692.1    0.12       0
  4995.8    0.07       0  5001.8    0.12       0  5353.2    0.16       0
Bank Sta=4995.8,5001.8
Exp/Cntr=0.3,0.1

Type RM Length L Ch R = 1,16501,867,867,867
BEGIN DESCRIPTION:
UNT0113 IN SAND CR 22.0
END DESCRIPTION:
XS GIS Cut Line= 3
      3508612.35     10513473.34      3508460.51     10513310.05
      3508125.63     10512395.93
#Sta/Elev= 30
  4731.6  428.01  4754.2  426.34  4808.8  419.26  4831.9  415.78  4924.2  404.03
  4950.1  402.08  4966.7  402.73  4984.8  400.98  4991.8  398.42  4997.2  397.44
  5003.1  394.88  5005.9  394.38  5009.1  394.88  5022.4  401.96  5027.7  402.63
  5091.3  401.95  5108.6  402.38  5194.8  400.77  5281.0  400.88  5336.3  405.11
  5347.3  406.71  5366.5  407.55  5410.8  411.10  5464.1  414.22  5514.4  415.68
  5575.4  415.33  5605.9  415.99  5772.9  421.95  5847.5  425.44  5928.1  427.78
#Mann=5,-1,0
  4731.6    0.16       0  4808.8    0.12       0  5003.1    0.07       0
  5009.1    0.12       0  5366.5    0.16       0
Bank Sta=5003.1,5009.1
Exp/Cntr=0.3,0.1

Type RM Length L Ch R = 1,15634,34,34,34
BEGIN DESCRIPTION:
UNT0113 IN SAND CR 20.1
END DESCRIPTION:
XS GIS Cut Line= 4
      3509241.18     10513514.11      3509071.90     10513183.36
      3509019.82     10512962.01      3509040.60     10512445.18
#Sta/Elev= 30
  4452.8  410.38  4500.3  411.39  4505.9  412.25  4522.5  412.23  4566.9  414.33
  4572.5  415.16  4594.7  415.02  4616.9  411.16  4624.1  406.12  4633.5  401.20
  4646.5  398.53  4677.9  397.68  4722.4  398.18  4811.2  398.18  4822.5  397.52
  4898.0  398.23  4969.9  397.85  4980.8  395.54  4990.5  391.97  4997.8  390.21
  5000.5  389.71  5003.8  390.21  5011.0  390.58  5018.1  393.93  5031.6  397.25
  5072.1  397.56  5113.9  399.97  5139.6  401.11  5362.4  411.60  5569.0  419.01
#Mann=5,-1,0
  4452.8    0.16       0  4997.8    0.07       0  5003.8    0.16       0
  5113.9    0.05       0  5139.6    0.16       0
Bank Sta=4997.8,5003.8
Exp/Cntr=0.3,0.1

Type RM Length L Ch R = 1,15600,64,64,64
BEGIN DESCRIPTION:
UNT0113 IN SAND CR 20.0
END DESCRIPTION:
XS GIS Cut Line= 4
      3509268.10     10513492.86      3509091.00     10513152.55
      3509051.07     10512950.29      3509067.96     10512455.38
#Sta/Elev= 30
  4456.3  409.05  4521.6  410.53  4549.3  412.36  4587.9  411.31  4593.5  412.15
  4626.4  407.45  4632.1  403.89  4638.0  401.47  4648.5  400.85  4654.2  398.50
  4670.7  399.33  4676.3  398.02  4698.4  397.64  4720.5  398.36  4742.6  397.51
  4818.4  398.02  4843.0  397.17  4871.4  398.05  4902.0  396.83  4942.8  397.74
  4965.8  397.28  4983.6  395.01  5001.0  389.61  5003.7  389.11  5007.0  389.61
  5017.1  394.18  5024.3  395.99  5089.2  399.37  5181.9  404.96  5541.3  420.09
#Mann=5,-1,0
  4456.3    0.16       0  5001.0    0.07       0  5007.0    0.16       0
  5089.2    0.05       0  5181.9    0.16       0
Bank Sta=5001,5007
Exp/Cntr=0.3,0.1

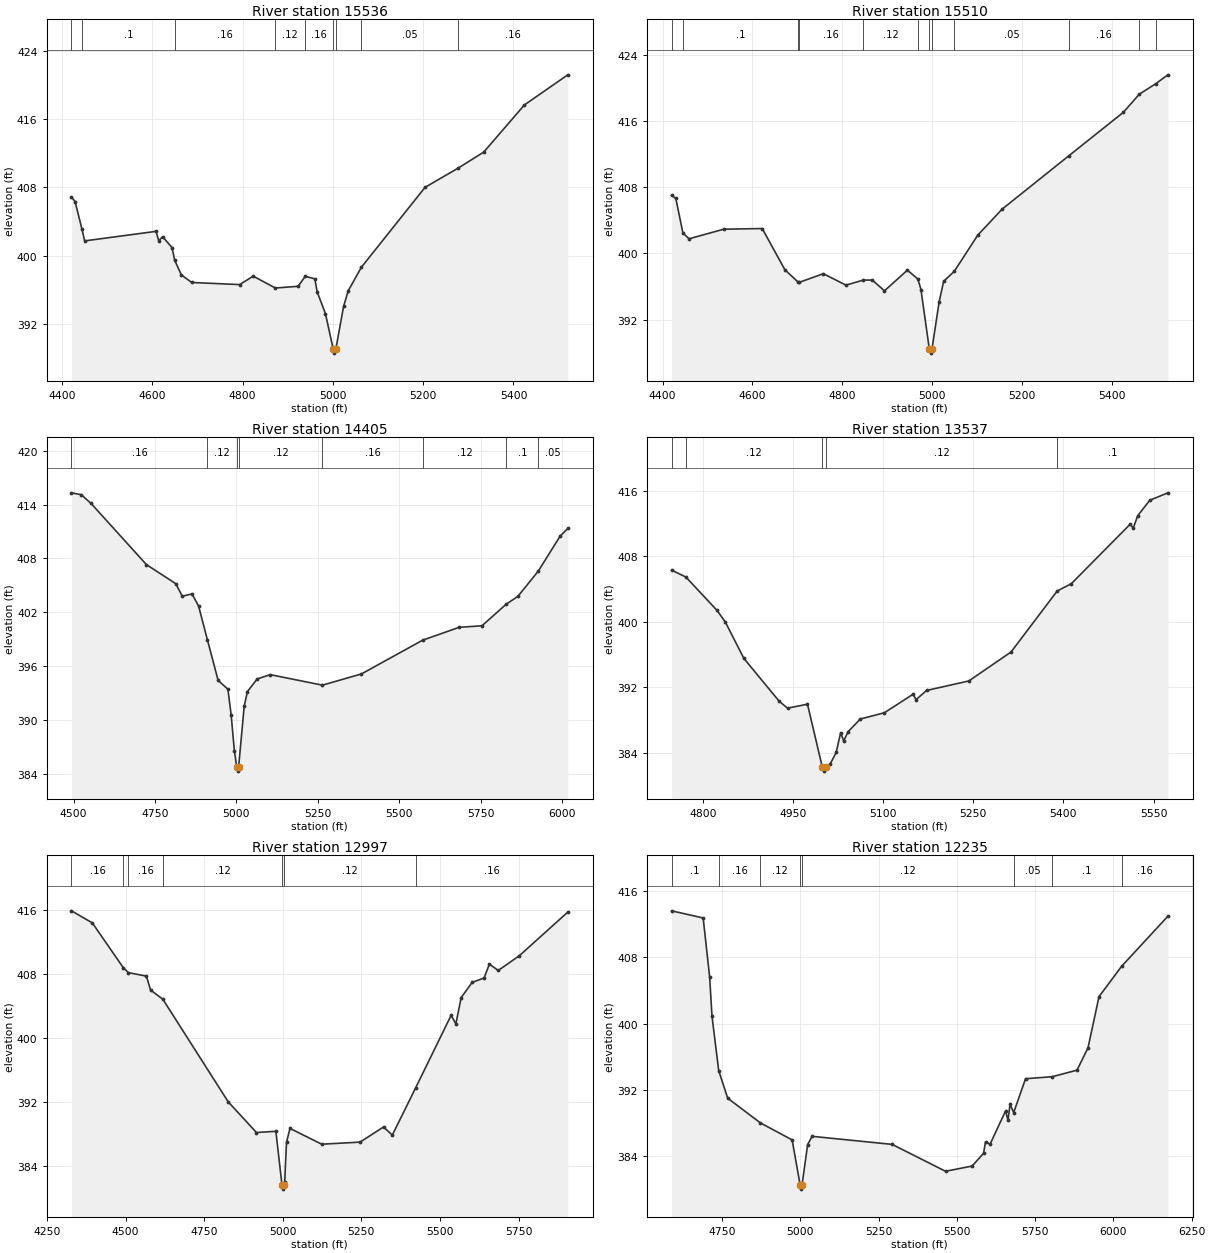
Type RM Length L Ch R = 1,15536,26,26,26
BEGIN DESCRIPTION:
UNT0113 IN SAND CR 20.2
END DESCRIPTION:
XS GIS Cut Line= 5
      3509410.43     10513475.01      3509181.28     10513170.34
      3509133.53     10513079.96      3509112.92     10512897.67
      3509114.00     10512465.67
#Sta/Elev= 30
  4421.3  406.87  4429.3  406.34  4444.7  403.06  4450.5  401.72  4608.4  402.84
  4614.6  401.73  4623.0  402.22  4643.8  400.94  4649.8  399.45  4664.6  397.72
  4687.5  396.83  4793.7  396.58  4823.7  397.57  4872.7  396.18  4923.2  396.38
  4938.9  397.55  4960.2  397.26  4965.2  395.74  4983.6  393.17  5000.7  389.02
  5003.4  388.52  5006.7  389.02  5023.8  394.01  5033.9  395.83  5063.2  398.62
  5204.2  408.02  5277.6  410.28  5334.2  412.17  5424.2  417.71  5520.2  421.25
#Mann=9,-1,0
  4421.3    0.16       0  4444.7     0.1       0  4649.8    0.16       0
  4872.7    0.12       0  4938.9    0.16       0  5000.7    0.07       0
  5006.7    0.16       0  5063.2    0.05       0  5277.6    0.16       0
Bank Sta=5000.7,5006.7
Exp/Cntr=0.3,0.1

Type RM Length L Ch R = 1,15510,1105,1105,1105
BEGIN DESCRIPTION:
UNT0113 IN SAND CR 20.3
END DESCRIPTION:
XS GIS Cut Line= 4
      3509442.28     10513464.68      3509159.30     10513074.06
      3509136.74     10512907.39      3509141.94     10512452.56
#Sta/Elev= 30
  4420.2  407.03  4429.6  406.65  4445.4  402.48  4459.0  401.77  4536.3  402.93
  4622.1  403.01  4672.4  398.04  4701.5  396.56  4704.7  396.51  4758.2  397.55
  4808.5  396.17  4847.4  396.78  4867.3  396.78  4894.3  395.48  4945.4  397.98
  4968.7  396.91  4975.6  395.64  4994.2  388.45  4996.9  387.95  5000.2  388.45
  5016.0  394.11  5026.1  396.63  5049.7  397.83  5102.3  402.22  5156.5  405.36
  5304.6  411.79  5426.5  417.06  5461.7  419.24  5498.6  420.52  5525.6  421.59
#Mann=12,-1,0
  4420.2    0.16       0  4445.4     0.1       0  4701.5    0.05       0
  4704.7    0.16       0  4847.4    0.12       0  4968.7    0.16       0
  4994.2    0.07       0  5000.2    0.16       0  5049.7    0.05       0
  5304.6    0.16       0  5461.7    0.05       0  5498.6    0.16       0
Bank Sta=4994.2,5000.2
Exp/Cntr=0.3,0.1

Type RM Length L Ch R = 1,14405,868,868,868
BEGIN DESCRIPTION:
UNT0113 IN SAND CR 19.0
END DESCRIPTION:
XS GIS Cut Line= 2
      3509810.87     10513711.72      3509841.25     10512188.33
#Sta/Elev= 30
  4493.8  415.30  4523.9  415.09  4553.9  414.12  4723.9  407.31  4813.9  405.19
  4833.9  403.80  4864.0  404.04  4884.0  402.70  4910.9  398.97  4944.0  394.42
  4974.0  393.44  4984.0  390.60  4994.0  386.54  5001.0  384.82  5003.7  384.32
  5007.0  384.82  5024.0  391.52  5034.0  393.18  5064.0  394.58  5104.0  395.06
  5264.2  393.89  5384.1  395.14  5571.5  398.89  5684.1  400.33  5754.1  400.50
  5828.7  402.91  5864.2  403.77  5926.8  406.58  5994.2  410.49  6017.5  411.33
#Mann=8,-1,0
  4493.8    0.16       0  4910.9    0.12       0  5001.0    0.07       0
  5007.0    0.12       0  5264.2    0.16       0  5571.5    0.12       0
  5828.7     0.1       0  5926.8    0.05       0
Bank Sta=5001,5007
Exp/Cntr=0.3,0.1

Type RM Length L Ch R = 1,13537,540,540,540
BEGIN DESCRIPTION:
UNT0113 IN SAND CR 16.0
END DESCRIPTION:
XS GIS Cut Line= 3
      3510492.11     10513641.64      3510592.11     10513441.64
      3510642.11     10512841.63
#Sta/Elev= 30
  4748.2  406.33  4772.1  405.47  4823.7  401.41  4837.6  399.99  4868.4  395.55
  4927.1  390.32  4941.1  389.47  4974.3  389.95  4998.9  382.28  5001.7  381.78
  5004.9  382.28  5011.9  382.63  5022.0  384.06  5029.5  386.48  5034.5  385.47
  5042.0  386.61  5062.1  388.14  5102.3  388.91  5149.9  391.17  5154.9  390.51
  5172.5  391.63  5242.7  392.79  5313.0  396.33  5389.7  403.77  5413.3  404.67
  5511.2  411.93  5516.2  411.44  5523.7  412.97  5543.8  414.85  5573.9  415.76
#Mann=5,-1,0
  4748.2    0.16       0  4772.1    0.12       0  4998.9    0.07       0
  5004.9    0.12       0  5389.7     0.1       0
Bank Sta=4998.9,5004.9
Exp/Cntr=0.3,0.1

Type RM Length L Ch R = 1,12997,762,762,762
BEGIN DESCRIPTION:
UNT0113 IN SAND CR 14.0
END DESCRIPTION:
XS GIS Cut Line= 2
      3510737.36     10514275.37      3511435.25     10512858.75
#Sta/Elev= 30
  4327.6  415.92  4394.0  414.41  4492.8  408.80  4508.9  408.20  4565.9  407.77
  4579.3  406.03  4618.3  404.88  4826.3  392.07  4916.2  388.24  4978.0  388.39
  4997.5  381.67  5000.2  381.17  5003.5  381.67  5006.0  382.05  5011.8  387.02
  5022.9  388.75  5123.9  386.78  5245.9  387.04  5320.5  388.93  5348.5  387.92
  5422.4  393.79  5535.7  402.88  5550.7  401.80  5567.6  405.09  5602.6  406.99
  5640.5  407.53  5657.4  409.27  5685.5  408.47  5752.8  410.32  5906.8  415.76
#Mann=7,-1,0
  4327.6    0.16       0  4492.8    0.12       0  4508.9    0.16       0
  4618.3    0.12       0  4997.5    0.07       0  5003.5    0.12       0
  5422.4    0.16       0
Bank Sta=4997.5,5003.5
Exp/Cntr=0.3,0.1

Type RM Length L Ch R = 1,12235,835,835,835
BEGIN DESCRIPTION:
UNT0113 IN SAND CR 12.0
END DESCRIPTION:
XS GIS Cut Line= 2
      3511250.35     10514481.16      3512257.66     10513257.80
#Sta/Elev= 30
  4589.2  413.59  4690.0  412.73  4710.8  405.59  4718.1  400.93  4739.6  394.35
  4768.2  391.03  4873.0  388.04  4974.1  386.00  4999.7  380.57  5002.5  380.07
  5005.7  380.57  5023.6  385.44  5037.9  386.43  5293.3  385.46  5464.0  382.22
  5548.7  382.85  5585.2  384.38  5591.7  385.77  5606.1  385.48  5655.6  389.49
  5663.4  388.38  5669.9  390.30  5681.5  389.29  5719.4  393.37  5804.6  393.61
  5883.7  394.40  5918.8  397.09  5954.0  403.26  6026.8  406.94  6173.9  412.94
#Mann=8,-1,0
  4589.2     0.1       0  4739.6    0.16       0  4873.0    0.12       0
  4999.7    0.07       0  5005.7    0.12       0  5681.5    0.05       0
  5804.6     0.1       0  6026.8    0.16       0
Bank Sta=4999.7,5005.7
Exp/Cntr=0.3,0.1

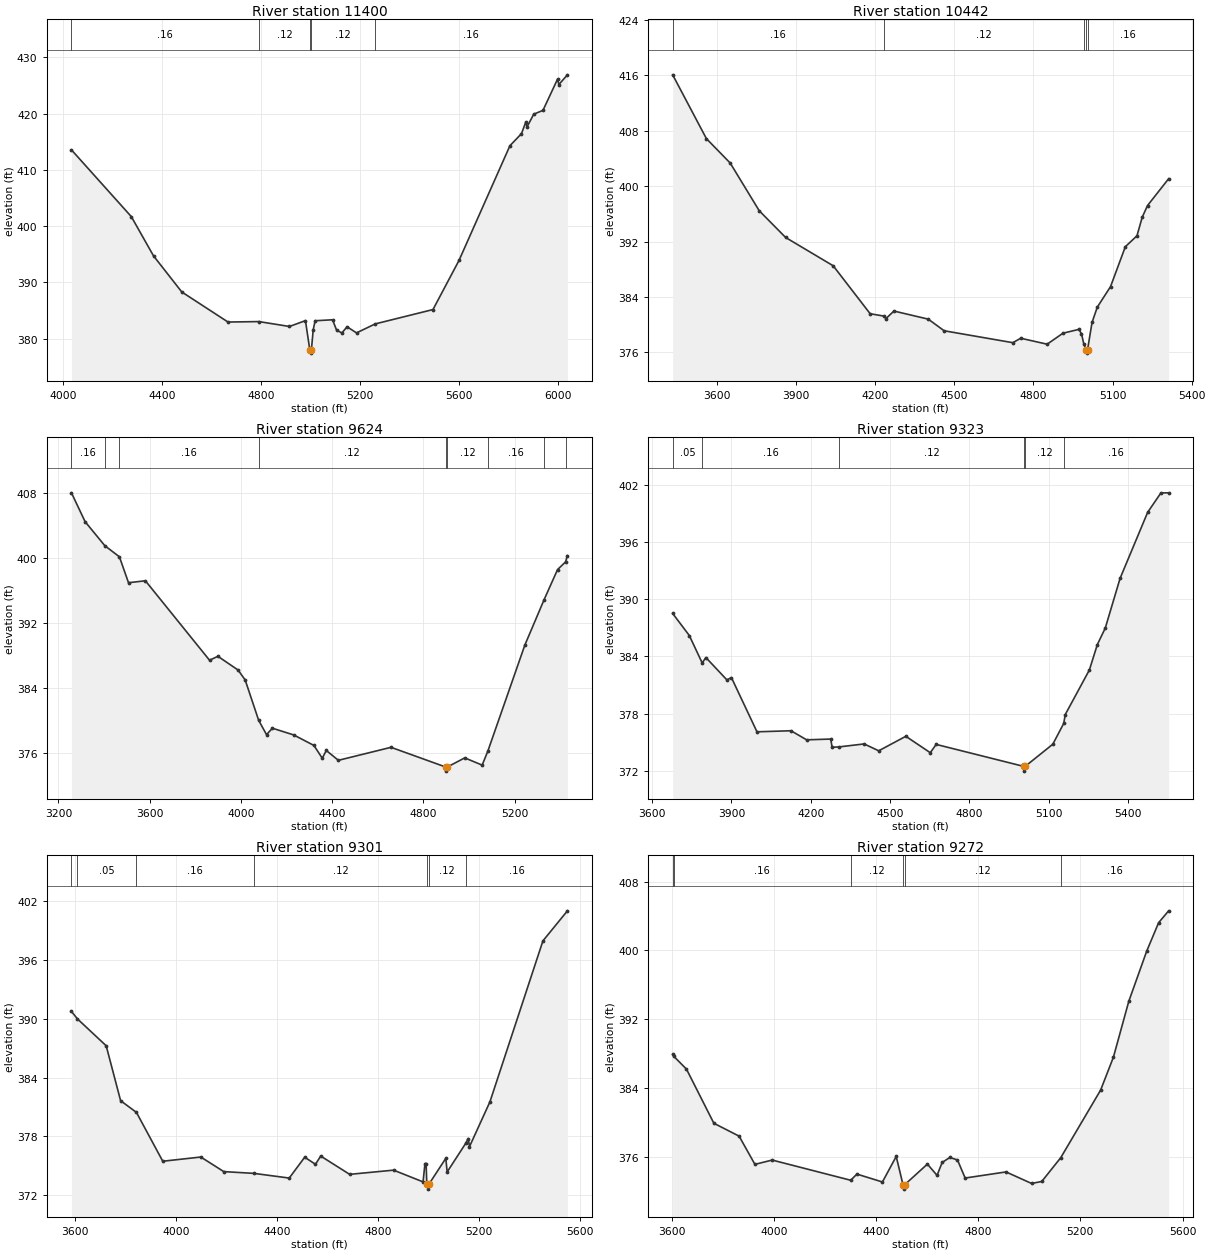
Type RM Length L Ch R = 1,11400,958,958,958
BEGIN DESCRIPTION:
UNT0113 IN SAND CR 10.0
END DESCRIPTION:
XS GIS Cut Line= 4
      3511182.63     10514890.00      3512039.42     10514655.62
      3512086.30     10514496.76      3512988.57     10514205.54
#Sta/Elev= 30
  4034.3  413.55  4275.9  401.68  4365.5  394.70  4479.6  388.28  4666.2  382.93
  4790.9  383.01  4914.2  382.14  4978.8  383.18  4996.7  377.90  4999.4  377.40
  5002.7  377.90  5010.1  381.54  5017.9  383.16  5088.2  383.33  5104.8  381.46
  5126.1  381.00  5146.8  382.09  5184.9  381.00  5260.6  382.60  5493.6  385.15
  5598.7  393.89  5804.2  414.29  5850.9  416.44  5868.3  418.50  5873.5  417.65
  5900.3  419.90  5937.6  420.58  5996.4  426.13  6001.7  425.17  6036.3  426.90
#Mann=5,-1,0
  4034.3    0.16       0  4790.9    0.12       0  4996.7    0.07       0
  5002.7    0.12       0  5260.6    0.16       0
Bank Sta=4996.7,5002.7
Exp/Cntr=0.3,0.1

Type RM Length L Ch R = 1,10442,818,818,818
BEGIN DESCRIPTION:
UNT0113 IN SAND CR 9.0
END DESCRIPTION:
XS GIS Cut Line= 3
      3511164.42     10515028.01      3512654.00     10515108.74
      3513042.07     10515087.91
#Sta/Elev= 30
  3432.3  416.09  3560.2  406.87  3650.3  403.35  3760.5  396.45  3860.6  392.59
  4040.9  388.50  4181.1  381.57  4233.4  381.23  4241.2  380.88  4271.2  381.96
  4401.4  380.79  4461.5  379.11  4721.9  377.39  4751.9  378.03  4852.1  377.17
  4912.2  378.76  4972.2  379.31  4982.3  378.69  4990.8  377.25  4999.3  376.38
  5002.0  375.88  5005.3  376.38  5022.3  380.31  5042.3  382.53  5092.4  385.49
  5148.6  391.26  5192.6  392.83  5212.6  395.52  5232.6  397.20  5312.7  401.08
#Mann=5,-1,0
  3432.3    0.16       0  4233.4    0.12       0  4990.8    0.16       0
  4999.3    0.07       0  5005.3    0.16       0
Bank Sta=4999.3,5005.3
Exp/Cntr=0.3,0.1

Type RM Length L Ch R = 1,9624,301,301,301
BEGIN DESCRIPTION:
UNT0113 IN SAND CR 8.0
END DESCRIPTION:
XS GIS Cut Line= 3
      3511255.60     10515179.07      3512805.05     10515712.91
      3513291.81     10515936.77
#Sta/Elev= 30
  3256.9  408.06  3316.7  404.51  3403.4  401.55  3467.1  400.19  3507.0  397.00
  3581.1  397.24  3862.4  387.46  3898.9  387.95  3987.3  386.26  4018.5  385.04
  4077.6  380.08  4112.1  378.31  4138.0  379.10  4231.7  378.27  4320.0  376.98
  4356.5  375.41  4374.3  376.36  4427.2  375.15  4658.1  376.75  4898.3  374.32
  4901.1  373.82  4904.3  374.32  4981.3  375.45  5057.6  374.56  5082.3  376.26
  5245.0  389.34  5329.2  394.91  5388.3  398.62  5423.3  399.56  5431.5  400.34
#Mann=9,-1,0
  3256.9    0.16       0  3403.4     0.1       0  3467.1    0.16       0
  4077.6    0.12       0  4898.3    0.07       0  4904.3    0.12       0
  5082.3    0.16       0  5329.2    0.05       0  5423.3    0.16       0
Bank Sta=4898.3,4904.3
Exp/Cntr=0.3,0.1

Type RM Length L Ch R = 1,9323,22,22,22
BEGIN DESCRIPTION:
UNT0113 IN SAND CR 7.1
END DESCRIPTION:
XS GIS Cut Line= 6
      3511537.57     10515521.03      3512326.47     10515893.78
      3512430.63     10515979.72      3512771.78     10516007.06
      3512973.60     10515958.89      3513291.28     10515977.11
#Sta/Elev= 30
  3677.7  388.50  3740.6  386.19  3789.2  383.32  3803.4  383.88  3882.7  381.54
  3899.9  381.78  3996.5  376.10  4125.1  376.21  4184.2  375.26  4275.2  375.34
  4280.8  374.48  4307.8  374.52  4401.6  374.83  4456.9  374.11  4559.4  375.63
  4651.9  373.91  4674.1  374.78  5004.8  372.48  5007.5  371.98  5010.8  372.48
  5115.2  374.80  5156.5  376.98  5162.3  377.91  5253.5  382.58  5283.6  385.24
  5313.6  386.97  5369.6  392.18  5473.9  399.10  5524.0  401.13  5553.2  401.14
#Mann=6,-1,0
  3677.7    0.05       0  3789.2    0.16       0  4307.8    0.12       0
  5004.8    0.07       0  5010.8    0.12       0  5156.5    0.16       0
Bank Sta=5004.8,5010.8
Exp/Cntr=0.3,0.1

Type RM Length L Ch R = 1,9301,29,29,29
BEGIN DESCRIPTION:
UNT0113 IN SAND CR 7.0
END DESCRIPTION:
XS GIS Cut Line= 6
      3511435.15     10515558.29      3512067.72     10515845.06
      3512267.87     10515891.18      3512411.71     10516001.00
      3512732.02     10516027.04      3513289.10     10515993.77
#Sta/Elev= 30
  3584.6  390.76  3608.5  389.99  3722.2  387.25  3779.4  381.64  3842.2  380.44
  3946.5  375.45  4097.3  375.88  4188.4  374.39  4307.8  374.21  4447.8  373.73
  4509.1  375.86  4551.8  375.14  4572.6  375.98  4687.3  374.11  4861.4  374.54
  4978.3  373.34  4985.8  375.21  4990.4  375.21  4993.0  373.17  4995.4  373.10
  4998.1  372.60  5001.4  373.10  5068.5  375.75  5073.7  374.35  5147.1  377.27
  5157.2  377.77  5162.3  376.94  5243.3  381.52  5453.4  397.97  5550.5  401.04
#Mann=7,-1,0
  3584.6    0.08       0  3608.5    0.05       0  3842.2    0.16       0
  4307.8    0.12       0  4995.4    0.07       0  5001.4    0.12       0
  5147.1    0.16       0
Bank Sta=4995.4,5001.4
Exp/Cntr=0.3,0.1

Type RM Length L Ch R = 1,9272,25,25,25
BEGIN DESCRIPTION:
UNT0113 IN SAND CR 7.2
END DESCRIPTION:
XS GIS Cut Line= 6
      3511441.07     10515634.67      3512282.20     10515975.81
      3512371.78     10516051.16      3512507.20     10516051.16
      3512776.29     10516056.37      3513287.79     10516024.29
#Sta/Elev= 30
  3603.9  387.91  3608.0  387.70  3658.0  386.20  3765.1  379.91  3864.0  378.41
  3925.9  375.13  3993.5  375.63  4301.0  373.28  4325.1  374.00  4425.1  373.08
  4479.1  376.05  4505.8  372.75  4508.6  372.25  4511.8  372.75  4601.2  375.16
  4639.0  373.85  4659.0  375.35  4689.0  375.93  4719.0  375.64  4749.0  373.54
  4909.0  374.25  5009.0  372.91  5049.0  373.14  5123.6  375.92  5279.5  383.77
  5329.6  387.60  5389.7  394.09  5459.8  399.92  5506.5  403.23  5545.7  404.61
#Mann=6,-1,0
  3603.9    0.05       0  3608.0    0.16       0  4301.0    0.12       0
  4505.8    0.07       0  4511.8    0.12       0  5123.6    0.16       0
Bank Sta=4505.8,4511.8
Exp/Cntr=0.3,0.1

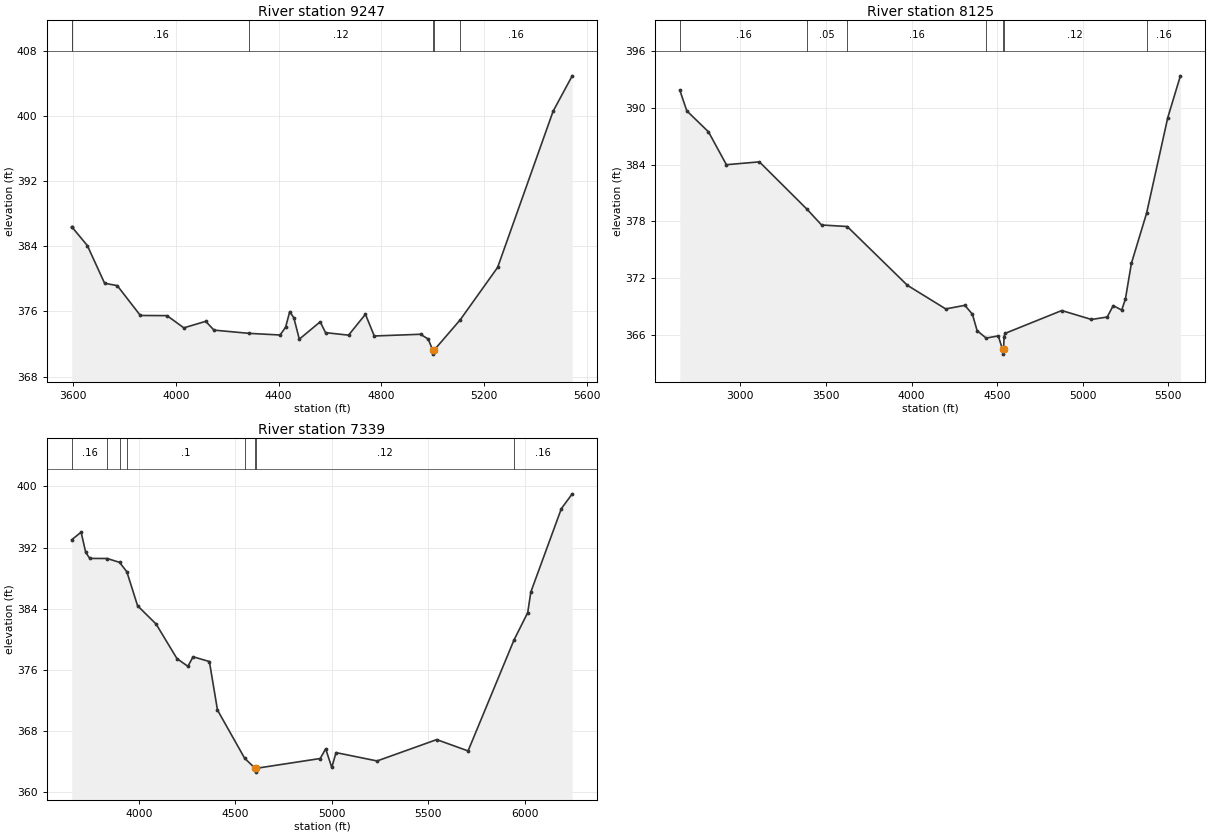
Type RM Length L Ch R = 1,9247,1122,1122,1122
BEGIN DESCRIPTION:
UNT0113 IN SAND CR 7.3
END DESCRIPTION:
XS GIS Cut Line= 6
      3511435.18     10515681.50      3512284.11     10516008.45
      3512379.59     10516090.05      3513155.63     10516065.74
      3513285.84     10516046.65      3513280.68     10516046.65
#Sta/Elev= 30
  3594.5  386.40  3594.8  386.40  3655.5  384.09  3722.6  379.46  3771.9  379.17
  3861.8  375.50  3965.7  375.48  4031.0  373.98  4116.3  374.78  4148.4  373.70
  4286.3  373.30  4405.6  373.10  4427.1  374.05  4443.3  375.97  4459.2  375.22
  4480.6  372.59  4561.9  374.72  4582.7  373.39  4672.3  373.08  4738.0  375.65
  4772.4  372.98  4952.5  373.19  4982.5  372.60  4999.5  371.25  5002.3  370.75
  5005.5  371.25  5106.8  374.96  5252.6  381.41  5468.7  400.61  5543.0  404.95
#Mann=6,-1,0
  3594.5    0.05       0  3594.8    0.16       0  4286.3    0.12       0
  4999.5    0.07       0  5005.5    0.12       0  5106.8    0.16       0
Bank Sta=4999.5,5005.5
Exp/Cntr=0.3,0.1

Type RM Length L Ch R = 1,8125,786,786,786
BEGIN DESCRIPTION:
UNT0113 IN SAND CR 5.0
END DESCRIPTION:
XS GIS Cut Line= 4
      3511259.98     10518826.21      3512098.54     10517232.44
      3512739.16     10517050.15      3513072.51     10516737.63
#Sta/Elev= 30
  2646.5  391.82  2687.2  389.65  2813.8  387.44  2918.4  383.98  3111.1  384.28
  3389.3  379.29  3474.4  377.63  3624.2  377.47  3975.6  371.28  4199.7  368.79
  4311.3  369.17  4355.4  368.24  4383.0  366.50  4435.8  365.72  4506.7  365.95
  4531.3  364.53  4534.0  364.03  4537.3  364.53  4540.6  365.88  4545.8  366.21
  4877.4  368.62  5051.1  367.68  5143.0  367.94  5178.1  369.14  5227.5  368.67
  5249.0  369.81  5284.1  373.58  5372.9  378.87  5496.6  388.93  5570.4  393.34
#Mann=7,-1,0
  2646.5    0.16       0  3389.3    0.05       0  3624.2    0.16       0
  4435.8    0.12       0  4531.3    0.07       0  4537.3    0.12       0
  5372.9    0.16       0
Bank Sta=4531.3,4537.3
Exp/Cntr=0.3,0.1

Type RM Length L Ch R = 1,7339,0,0,0
BEGIN DESCRIPTION:
UNT0113 IN SAND CR 1.0
END DESCRIPTION:
XS GIS Cut Line= 4
      3512541.24     10518940.79      3512869.37     10517930.36
      3513069.57     10517509.25      3513411.03     10516498.09
#Sta/Elev= 30
  3650.9  393.02  3699.8  394.01  3723.6  391.37  3744.6  390.58  3835.1  390.57
  3898.9  390.07  3936.9  388.84  3992.7  384.39  4088.6  382.01  4196.7  377.50
  4253.6  376.48  4280.3  377.73  4365.0  377.11  4407.0  370.77  4548.0  364.47
  4602.2  363.16  4604.9  362.66  4608.2  363.16  4939.9  364.44  4968.1  365.71
  4999.7  363.27  5021.9  365.21  5234.7  364.12  5544.0  366.91  5706.6  365.43
  5944.9  379.93  6015.9  383.49  6032.0  386.18  6190.3  397.08  6246.8  399.02
#Mann=8,-1,0
  3650.9    0.16       0  3835.1    0.08       0  3898.9    0.16       0
  3936.9     0.1       0  4548.0    0.12       0  4602.2    0.07       0
  4608.2    0.12       0  5944.9    0.16       0
Bank Sta=4602.2,4608.2
Exp/Cntr=0.3,0.1

Chan Stop Cuts=-1