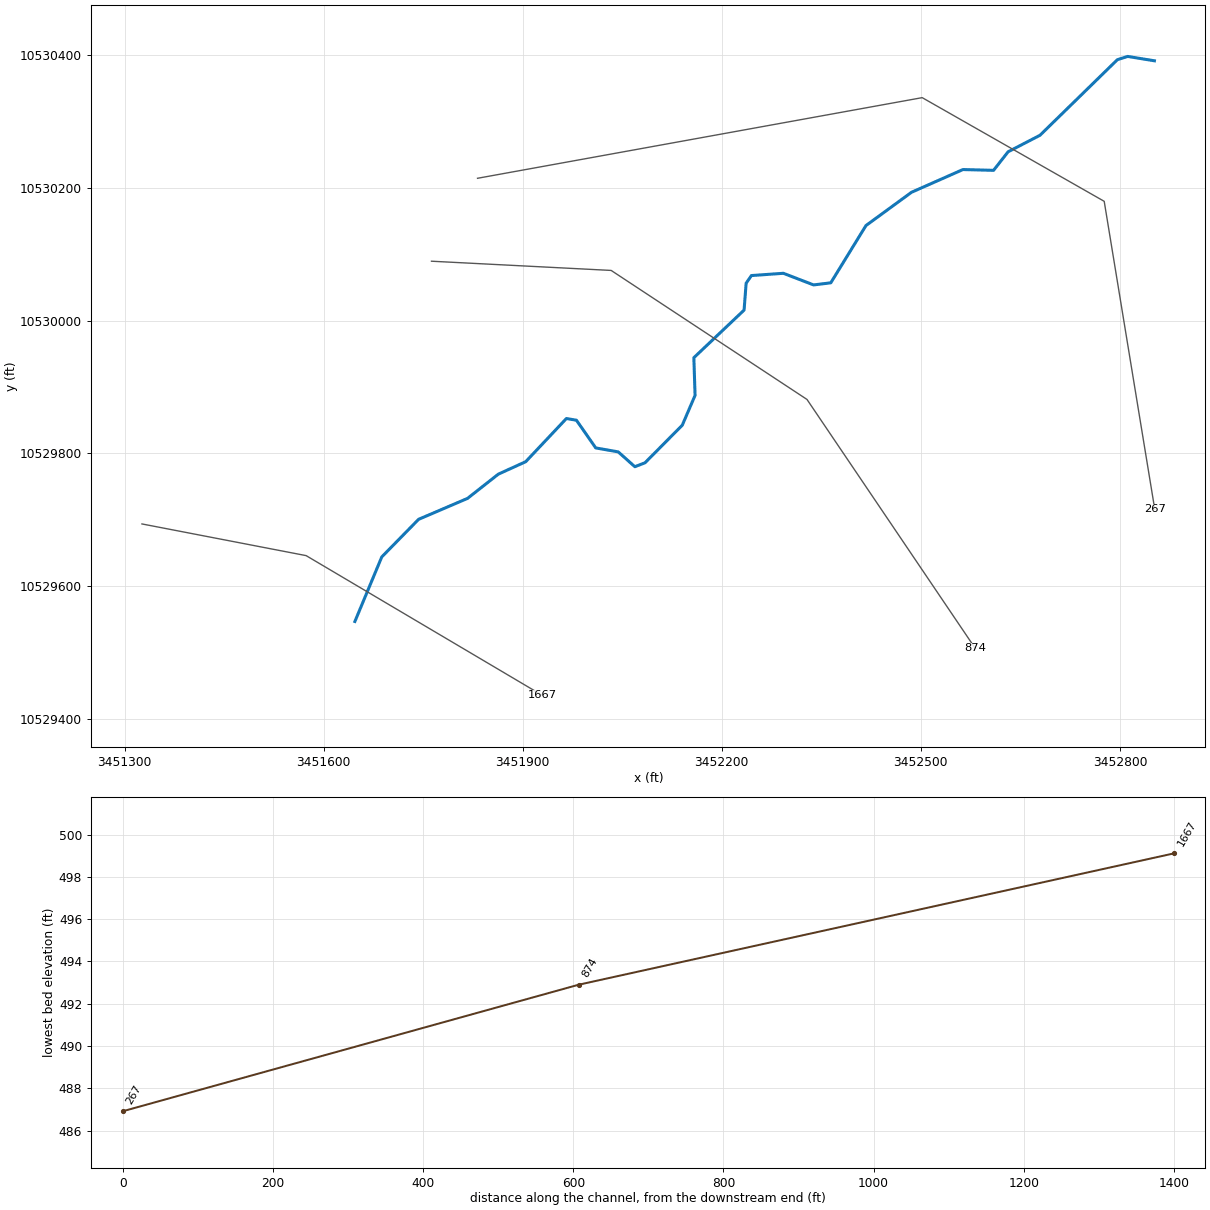
--- UNT01133 IN SAND CR.prj (project) ---

Proj Title=UNT01133 IN SAND CR Base Level Engineering
Current Plan=p01
Default Exp/Contr=0.3,0.1
English Units
Geom File=g01
Flow File=f01
Plan File=p01
BEGIN DESCRIPTION:
UNT01133 IN SAND CR
END DESCRIPTION:

--- UNT01133 IN SAND CR.p01 (plan) ---

Plan Title=Multiple Run
Short Identifier=Multiple
Geom File=g01
Flow File=f01
Subcritical Flow
K Sum by GR= 0
Std Step Tol= 0.01
Critical Tol= 0.01
Num of Std Step Trials= 20
Max Error Tol= 0.3
Flow Tol Ratio= 0.001
Split Flow NTrial= 30
Split Flow Tol= 0.02
Split Flow Ratio= 0.02
Log Output Level= 0
Friction Slope Method= 1
Unsteady Friction Slope Method= 2
Unsteady Bridges Friction Slope Method= 1
Parabolic Critical Depth
Global Vel Dist=  1 , 1 , 1
Global Log Level= 0
CheckData=True
Encroach Param= -1, 0, 0, 0
BEGIN DESCRIPTION:
Multiple Run
END DESCRIPTION:

--- UNT01133 IN SAND CR.f01 (steady flow) ---

Flow Title=Multiple
Number of Profiles=7
Profile Names=10-year,25-year,50-year,1pct_min,100-year,1pct_plu,500-year
River Rch & RM= UNT01133 IN SAND,Reach-1,1667
     287     364     423     361     488     659     644
Boundary for River Rch & Prof#=UNT01133 IN SAND,Reach-1,1
Up Type=0
Dn Type=3
Dn Slope=0.005
Boundary for River Rch & Prof#=UNT01133 IN SAND,Reach-1,2
Up Type=0
Dn Type=3
Dn Slope=0.005
Boundary for River Rch & Prof#=UNT01133 IN SAND,Reach-1,3
Up Type=0
Dn Type=3
Dn Slope=0.005
Boundary for River Rch & Prof#=UNT01133 IN SAND,Reach-1,4
Up Type=0
Dn Type=3
Dn Slope=0.005
Boundary for River Rch & Prof#=UNT01133 IN SAND,Reach-1,5
Up Type=0
Dn Type=3
Dn Slope=0.005
Boundary for River Rch & Prof#=UNT01133 IN SAND,Reach-1,6
Up Type=0
Dn Type=3
Dn Slope=0.005
Boundary for River Rch & Prof#=UNT01133 IN SAND,Reach-1,7
Up Type=0
Dn Type=3
Dn Slope=0.005

--- UNT01133 IN SAND CR.g01 (geometry) ---

Geom Title=Existing Conditions

River Reach=UNT01133 IN SAND,Reach-1
Reach XY= 30
      3451647.11     10529546.64      3451687.63     10529643.94
      3451743.09     10529700.56      3451816.88     10529732.15
      3451863.37     10529768.72      3451904.56     10529787.44
      3451965.88     10529852.51      3451981.01     10529849.93
      3452010.10     10529808.20      3452043.98     10529802.23
      3452069.04     10529779.89      3452084.33     10529785.79
      3452140.49     10529842.39      3452159.79     10529887.36
      3452157.97     10529944.18      3452233.66     10530015.90
      3452236.77     10530056.44      3452244.74     10530067.98
      3452292.85     10530071.40      3452338.47     10530053.85
      3452364.32     10530057.02      3452417.34     10530143.32
      3452486.04     10530193.49      3452563.47     10530227.73
      3452609.64     10530226.56      3452631.56     10530254.50
      3452679.66     10530279.41      3452796.22     10530393.28
      3452811.72     10530398.24      3452852.11     10530391.64

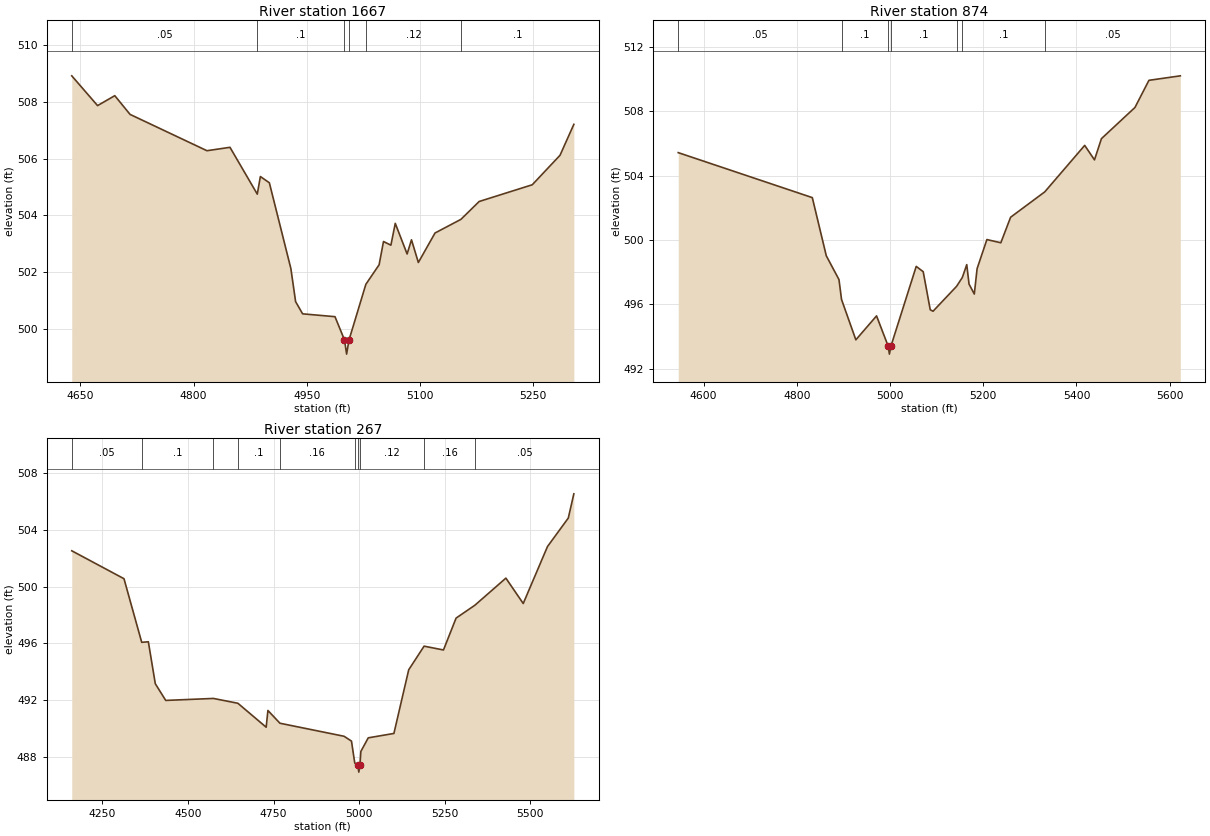
Type RM Length L Ch R = 1,1667,793,793,793
BEGIN DESCRIPTION:
UNT01133 IN SAND CR 3.0
END DESCRIPTION:
XS GIS Cut Line= 3
      3451326.16     10529693.65      3451573.61     10529645.89
      3451929.51     10529435.39
#Sta/Elev= 30
  4638.6  508.92  4672.8  507.87  4695.6  508.22  4715.9  507.56  4817.8  506.28
  4848.3  506.40  4884.5  504.75  4888.6  505.37  4900.5  505.15  4929.0  502.13
  4935.3  500.96  4944.6  500.53  4987.5  500.43  5000.1  499.61  5002.9  499.11
  5006.1  499.61  5028.4  501.57  5046.0  502.26  5051.8  503.08  5061.6  502.95
  5067.4  503.72  5083.1  502.64  5088.9  503.14  5098.0  502.34  5120.1  503.38
  5154.4  503.86  5178.6  504.49  5249.0  505.08  5285.8  506.12  5304.1  507.21
#Mann=6,-1,0
  4638.6    0.05       0  4884.5     0.1       0  5000.1    0.07       0
  5006.1     0.1       0  5028.4    0.12       0  5154.4     0.1       0
Bank Sta=5000.1,5006.1
Exp/Cntr=0.3,0.1

Type RM Length L Ch R = 1,874,607,607,607
BEGIN DESCRIPTION:
UNT01133 IN SAND CR 2.0
END DESCRIPTION:
XS GIS Cut Line= 4
      3451762.53     10530089.59      3452033.35     10530075.70
      3452328.49     10529881.25      3452581.83     10529506.45
#Sta/Elev= 30
  4545.8  505.44  4833.4  502.64  4863.4  499.02  4890.6  497.54  4896.1  496.30
  4926.8  493.79  4971.2  495.28  4996.1  493.40  4998.8  492.90  5002.1  493.40
  5056.3  498.36  5071.3  498.03  5086.4  495.66  5092.4  495.57  5142.9  497.12
  5155.2  497.67  5164.7  498.47  5169.6  497.26  5180.9  496.64  5186.9  498.22
  5207.9  500.03  5237.8  499.83  5258.8  501.42  5332.1  503.00  5417.7  505.89
  5438.7  504.99  5453.6  506.31  5525.5  508.25  5555.5  509.94  5622.8  510.22
#Mann=7,-1,0
  4545.8    0.05       0  4896.1     0.1       0  4996.1    0.07       0
  5002.1     0.1       0  5142.9    0.16       0  5155.2     0.1       0
  5332.1    0.05       0
Bank Sta=4996.1,5002.1
Exp/Cntr=0.3,0.1

Type RM Length L Ch R = 1,267,0,0,0
BEGIN DESCRIPTION:
UNT01133 IN SAND CR 1.0
END DESCRIPTION:
XS GIS Cut Line= 4
      3451831.94     10530214.58      3452502.10     10530336.11
      3452776.41     10530179.86      3452852.62     10529715.65
#Sta/Elev= 30
  4160.4  502.54  4313.0  500.57  4364.8  496.08  4384.2  496.12  4404.5  493.16
  4435.0  491.98  4574.3  492.12  4645.8  491.78  4728.5  490.09  4733.6  491.27
  4768.8  490.37  4956.2  489.45  4977.8  489.11  4987.4  487.56  4996.5  487.42
  4999.2  486.92  5002.5  487.42  5005.2  488.38  5026.8  489.34  5101.8  489.65
  5145.0  494.14  5190.0  495.81  5246.6  495.54  5283.5  497.79  5338.5  498.70
  5429.0  500.61  5479.7  498.82  5550.6  502.84  5611.4  504.85  5627.6  506.56
#Mann=10,-1,0
  4160.4    0.05       0  4364.8     0.1       0  4574.3    0.16       0
  4645.8     0.1       0  4768.8    0.16       0  4987.4    0.12       0
  4996.5    0.07       0  5002.5    0.12       0  5190.0    0.16       0
  5338.5    0.05       0
Bank Sta=4996.5,5002.5
Exp/Cntr=0.3,0.1

Chan Stop Cuts=-1