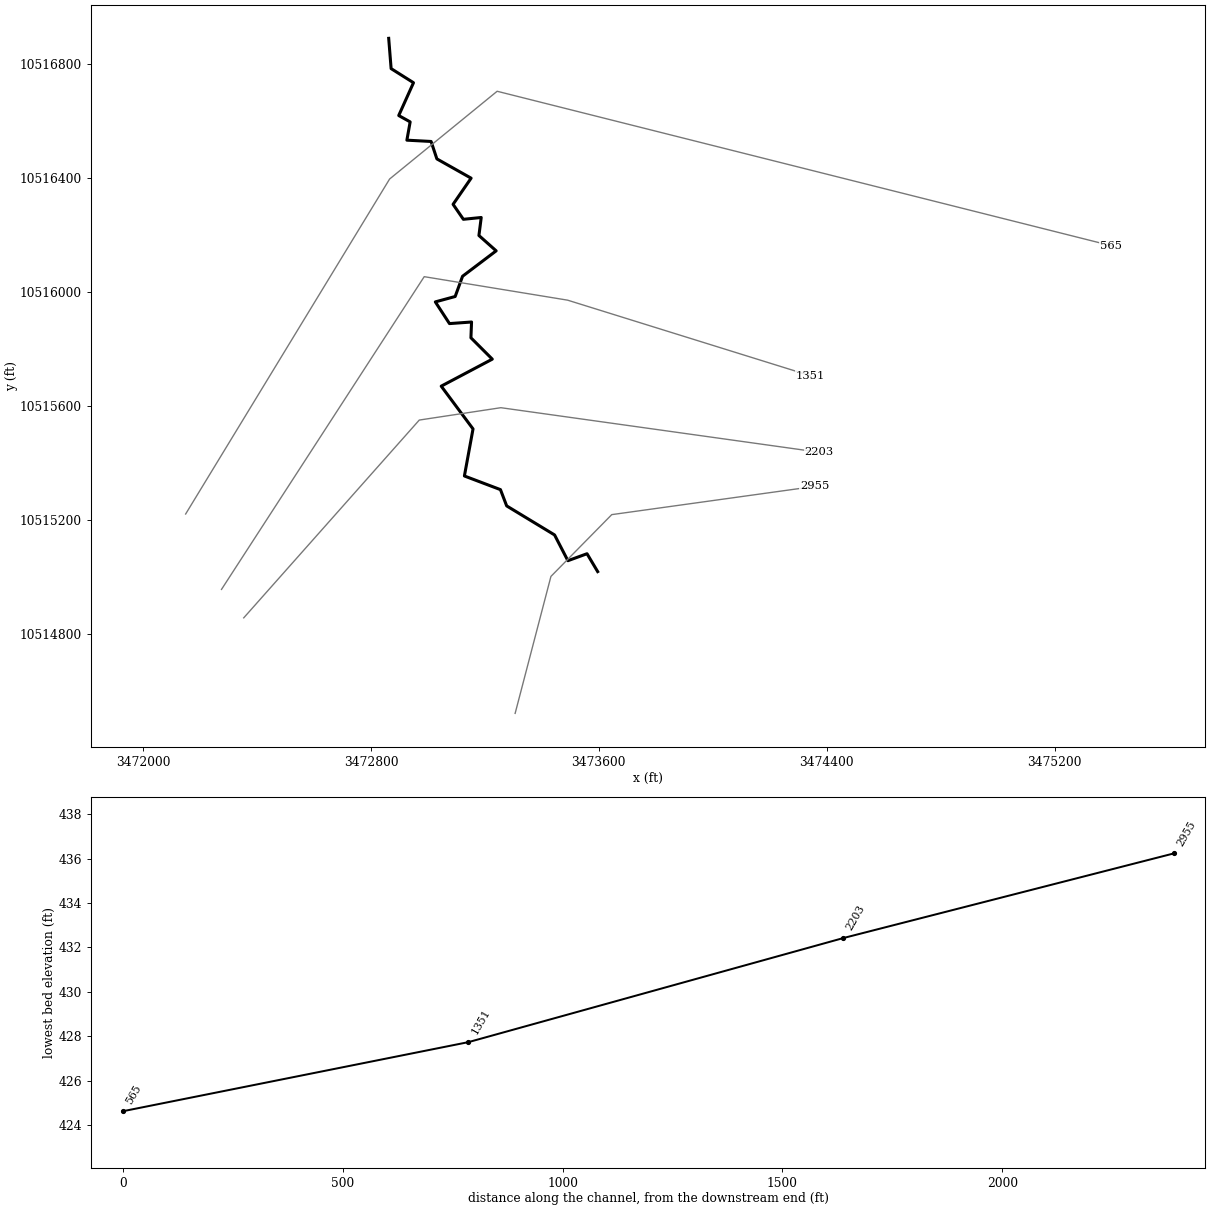
--- UNT01153 IN SAND CR.prj (project) ---

Proj Title=UNT01153 IN SAND CR Base Level Engineering
Current Plan=p01
Default Exp/Contr=0.3,0.1
English Units
Geom File=g01
Flow File=f01
Plan File=p01
BEGIN DESCRIPTION:
UNT01153 IN SAND CR
END DESCRIPTION:

--- UNT01153 IN SAND CR.p01 (plan) ---

Plan Title=Multiple Run
Short Identifier=Multiple
Geom File=g01
Flow File=f01
Subcritical Flow
K Sum by GR= 0
Std Step Tol= 0.01
Critical Tol= 0.01
Num of Std Step Trials= 20
Max Error Tol= 0.3
Flow Tol Ratio= 0.001
Split Flow NTrial= 30
Split Flow Tol= 0.02
Split Flow Ratio= 0.02
Log Output Level= 0
Friction Slope Method= 1
Unsteady Friction Slope Method= 2
Unsteady Bridges Friction Slope Method= 1
Parabolic Critical Depth
Global Vel Dist=  1 , 1 , 1
Global Log Level= 0
CheckData=True
Encroach Param= -1, 0, 0, 0
BEGIN DESCRIPTION:
Multiple Run
END DESCRIPTION:

--- UNT01153 IN SAND CR.f01 (steady flow) ---

Flow Title=Multiple
Number of Profiles=7
Profile Names=10-year,25-year,50-year,1pct_min,100-year,1pct_plu,500-year
River Rch & RM= UNT01153 IN SAND,Reach-1,2955
     504     667     797     697     943    1275    1314
Boundary for River Rch & Prof#=UNT01153 IN SAND,Reach-1,1
Up Type=0
Dn Type=3
Dn Slope=0.005
Boundary for River Rch & Prof#=UNT01153 IN SAND,Reach-1,2
Up Type=0
Dn Type=3
Dn Slope=0.005
Boundary for River Rch & Prof#=UNT01153 IN SAND,Reach-1,3
Up Type=0
Dn Type=3
Dn Slope=0.005
Boundary for River Rch & Prof#=UNT01153 IN SAND,Reach-1,4
Up Type=0
Dn Type=3
Dn Slope=0.005
Boundary for River Rch & Prof#=UNT01153 IN SAND,Reach-1,5
Up Type=0
Dn Type=3
Dn Slope=0.005
Boundary for River Rch & Prof#=UNT01153 IN SAND,Reach-1,6
Up Type=0
Dn Type=3
Dn Slope=0.005
Boundary for River Rch & Prof#=UNT01153 IN SAND,Reach-1,7
Up Type=0
Dn Type=3
Dn Slope=0.005

--- UNT01153 IN SAND CR.g01 (geometry) ---

Geom Title=Existing Conditions

River Reach=UNT01153 IN SAND,Reach-1
Reach XY= 30
      3473595.88     10515019.15      3473558.47     10515081.93
      3473491.34     10515057.41      3473444.56     10515147.90
      3473276.37     10515249.84      3473254.56     10515307.00
      3473127.93     10515354.91      3473158.21     10515520.14
      3473046.54     10515670.30      3473225.86     10515765.15
      3473150.85     10515840.15      3473153.00     10515895.56
      3473075.53     10515890.01      3473025.85     10515966.20
      3473095.55     10515985.15      3473121.47     10516056.23
      3473239.44     10516145.46      3473178.93     10516199.30
      3473186.98     10516262.56      3473124.31     10516256.21
      3473088.18     10516308.81      3473151.48     10516400.64
      3473031.31     10516468.30      3473010.99     10516529.51
      3472925.98     10516534.06      3472937.44     10516598.26
      3472897.31     10516620.58      3472949.19     10516735.80
      3472870.63     10516785.31      3472862.11     10516891.64

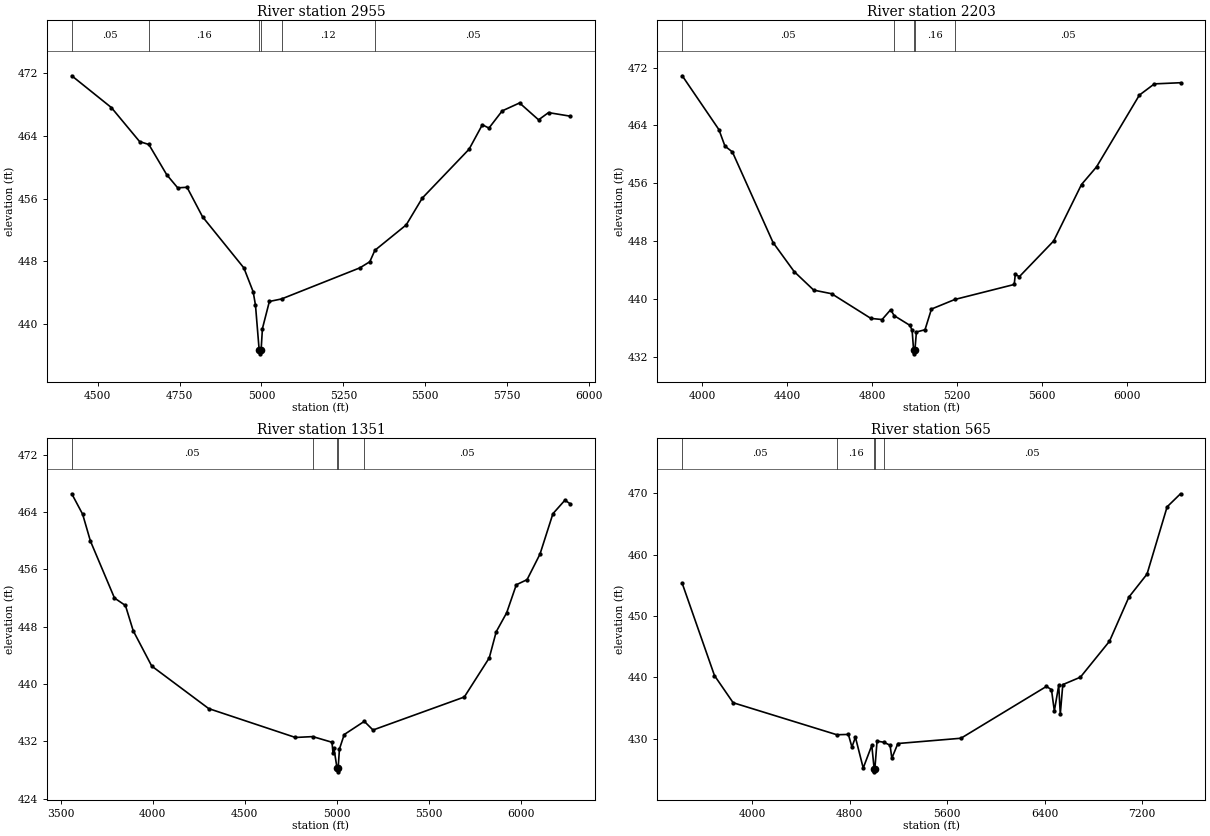
Type RM Length L Ch R = 1,2955,752,752,752
BEGIN DESCRIPTION:
UNT01153 IN SAND CR 3.0
END DESCRIPTION:
XS GIS Cut Line= 4
      3473306.08     10514521.35      3473431.76     10515002.22
      3473645.31     10515219.23      3474357.08     10515318.19
#Sta/Elev= 30
  4421.3  471.64  4542.2  467.59  4628.3  463.26  4656.5  462.89  4711.0  459.04
  4744.5  457.37  4773.0  457.44  4820.2  453.69  4946.4  447.17  4974.7  444.14
  4981.8  442.43  4993.0  436.73  4995.7  436.23  4999.0  436.73  5003.0  439.45
  5024.2  442.90  5061.3  443.22  5300.3  447.18  5330.6  447.96  5346.0  449.41
  5441.7  452.65  5490.8  456.07  5633.5  462.29  5673.9  465.40  5694.1  464.98
  5734.5  467.17  5787.5  468.18  5845.5  466.03  5875.8  466.95  5941.4  466.50
#Mann=6,-1,0
  4421.3    0.05       0  4656.5    0.16       0  4993.0    0.07       0
  4999.0    0.16       0  5061.3    0.12       0  5346.0    0.05       0
Bank Sta=4993,4999
Exp/Cntr=0.3,0.1

Type RM Length L Ch R = 1,2203,852,852,852
BEGIN DESCRIPTION:
UNT01153 IN SAND CR 2.1
END DESCRIPTION:
XS GIS Cut Line= 4
      3472353.13     10514856.82      3472969.47     10515551.28
      3473255.93     10515594.69      3474373.99     10515438.27
#Sta/Elev= 30
  3905.0  470.86  4077.6  463.42  4106.1  461.14  4141.2  460.33  4332.7  447.81
  4432.2  443.79  4524.2  441.23  4608.7  440.73  4793.5  437.32  4846.3  437.16
  4886.8  438.52  4903.3  437.70  4977.8  436.35  4987.9  435.66  4994.9  432.92
  4997.6  432.42  5000.9  432.92  5008.1  435.44  5048.6  435.75  5078.9  438.61
  5189.5  439.94  5468.9  442.01  5473.9  443.41  5493.0  443.09  5654.6  448.02
  5785.8  455.83  5856.5  458.26  6058.5  468.19  6129.1  469.74  6252.2  469.90
#Mann=5,-1,0
  3905.0    0.05       0  4903.3    0.16       0  4994.9    0.07       0
  5000.9    0.16       0  5189.5    0.05       0
Bank Sta=4994.9,5000.9
Exp/Cntr=0.3,0.1

Type RM Length L Ch R = 1,1351,786,786,786
BEGIN DESCRIPTION:
UNT01153 IN SAND CR 2.0
END DESCRIPTION:
XS GIS Cut Line= 4
      3472275.05     10514956.70      3472986.83     10516054.76
      3473490.30     10515972.29      3474341.00     10515707.53
#Sta/Elev= 30
  3559.4  466.57  3618.6  463.71  3660.8  459.97  3791.7  452.01  3851.3  450.97
  3893.6  447.44  3994.3  442.51  4304.3  436.57  4775.7  432.54  4870.1  432.66
  4974.7  431.87  4979.9  430.41  4984.9  431.08  5002.1  428.24  5004.8  427.74
  5008.1  428.24  5015.2  430.93  5041.2  432.95  5150.4  434.79  5197.6  433.58
  5694.2  438.19  5829.9  443.65  5867.7  447.30  5924.6  449.95  5977.0  453.86
  6035.6  454.58  6105.9  458.15  6176.2  463.79  6241.3  465.67  6269.1  465.19
#Mann=5,-1,0
  3559.4    0.05       0  4870.1    0.16       0  5002.1    0.07       0
  5008.1    0.16       0  5150.4    0.05       0
Bank Sta=5002.1,5008.1
Exp/Cntr=0.3,0.1

Type RM Length L Ch R = 1,565,0,0,0
BEGIN DESCRIPTION:
UNT01153 IN SAND CR 1.0
END DESCRIPTION:
XS GIS Cut Line= 4
      3472149.17     10515221.45      3472865.30     10516397.64
      3473242.91     10516705.80      3475398.53     10516163.64
#Sta/Elev= 30
  3426.3  455.30  3690.7  440.30  3843.8  435.88  4694.4  430.67  4789.0  430.72
  4818.1  428.67  4846.8  430.26  4910.7  425.25  4981.1  428.93  5000.3  425.13
  5003.1  424.63  5006.3  425.13  5024.2  429.64  5080.5  429.44  5131.1  428.96
  5145.5  426.85  5195.0  429.24  5712.7  430.10  6413.9  438.54  6455.1  438.00
  6478.6  434.54  6514.5  438.70  6527.3  434.02  6547.9  438.83  6692.3  440.04
  6930.9  445.89  7090.2  453.08  7238.8  456.82  7403.8  467.78  7513.5  469.90
#Mann=5,-1,0
  3426.3    0.05       0  4694.4    0.16       0  5000.3    0.07       0
  5006.3    0.16       0  5080.5    0.05       0
Bank Sta=5000.3,5006.3
Exp/Cntr=0.3,0.1

Chan Stop Cuts=-1