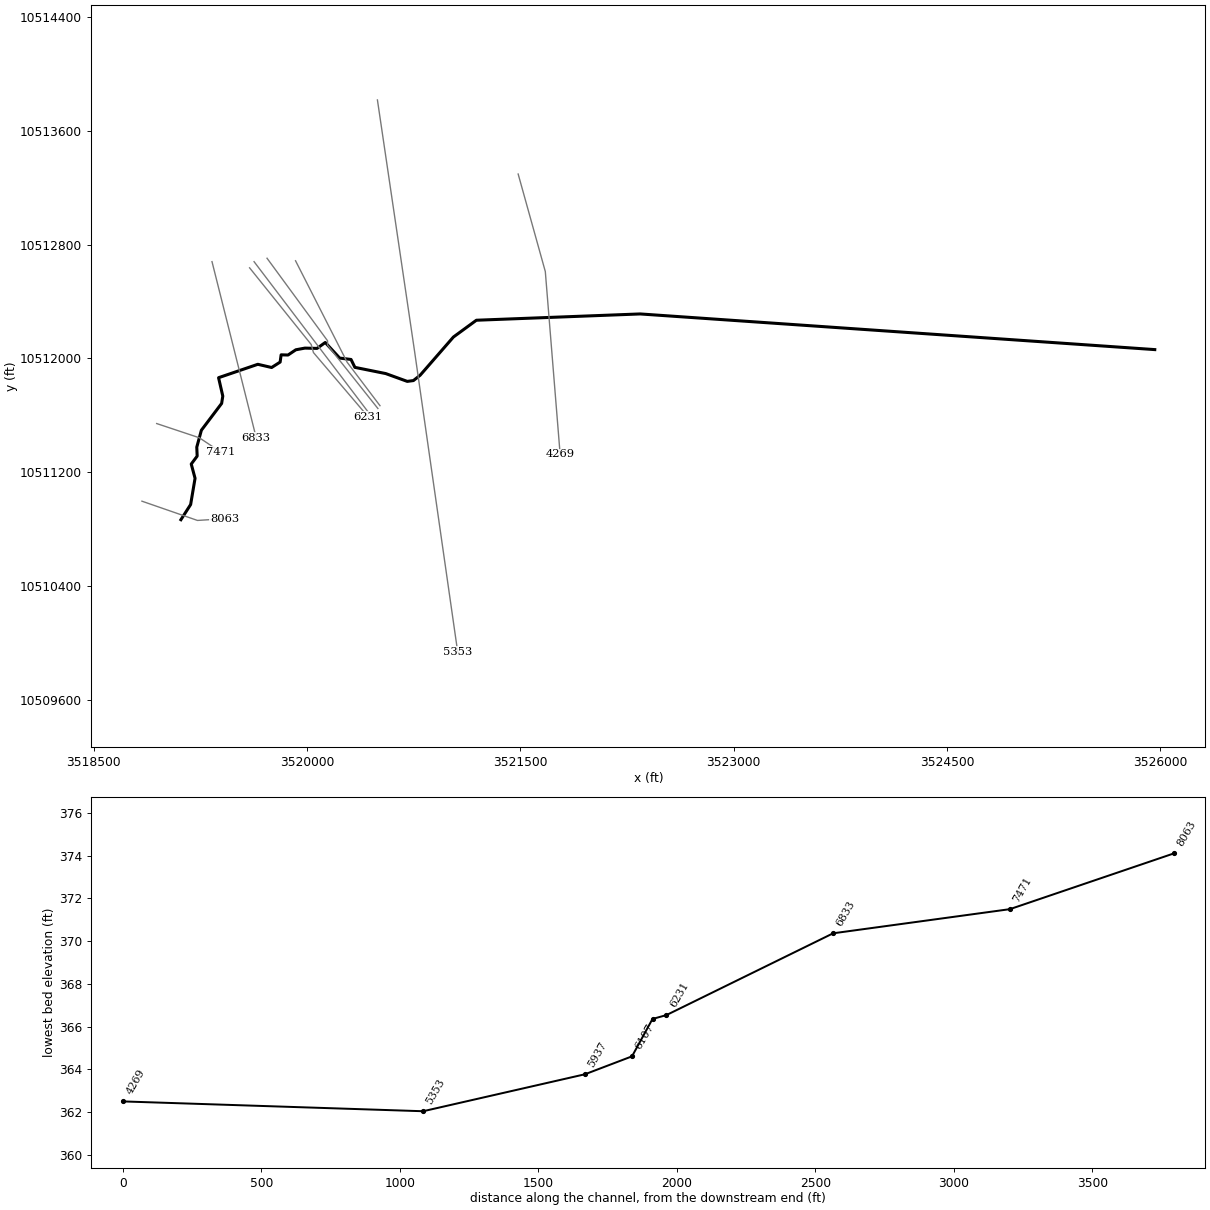
--- UNT0116 IN SAND CR.prj (project) ---

Proj Title=UNT0116 IN SAND CR Base Level Engineering
Current Plan=p01
Default Exp/Contr=0.3,0.1
English Units
Geom File=g01
Flow File=f01
Plan File=p01
BEGIN DESCRIPTION:
UNT0116 IN SAND CR
END DESCRIPTION:

--- UNT0116 IN SAND CR.p01 (plan) ---

Plan Title=Multiple Run
Short Identifier=Multiple
Geom File=g01
Flow File=f01
Subcritical Flow
K Sum by GR= 0
Std Step Tol= 0.01
Critical Tol= 0.01
Num of Std Step Trials= 20
Max Error Tol= 0.3
Flow Tol Ratio= 0.001
Split Flow NTrial= 30
Split Flow Tol= 0.02
Split Flow Ratio= 0.02
Log Output Level= 0
Friction Slope Method= 1
Unsteady Friction Slope Method= 2
Unsteady Bridges Friction Slope Method= 1
Parabolic Critical Depth
Global Vel Dist=  1 , 1 , 1
Global Log Level= 0
CheckData=True
Encroach Param= -1, 0, 0, 0
BEGIN DESCRIPTION:
Multiple Run
END DESCRIPTION:

--- UNT0116 IN SAND CR.f01 (steady flow) ---

Flow Title=Multiple
Number of Profiles=7
Profile Names=10-year,25-year,50-year,1pct_min,100-year,1pct_plu,500-year
River Rch & RM= UNT0116 IN SAND ,Reach-1,8063
    1176    1651    2052    1863    2519    3406    3784
River Rch & RM= UNT0116 IN SAND ,Reach-1,6107
    1562    2211    2762    2515    3401    4599    5145
Boundary for River Rch & Prof#=UNT0116 IN SAND ,Reach-1,1
Up Type=0
Dn Type=3
Dn Slope=0.005
Boundary for River Rch & Prof#=UNT0116 IN SAND ,Reach-1,2
Up Type=0
Dn Type=3
Dn Slope=0.005
Boundary for River Rch & Prof#=UNT0116 IN SAND ,Reach-1,3
Up Type=0
Dn Type=3
Dn Slope=0.005
Boundary for River Rch & Prof#=UNT0116 IN SAND ,Reach-1,4
Up Type=0
Dn Type=3
Dn Slope=0.005
Boundary for River Rch & Prof#=UNT0116 IN SAND ,Reach-1,5
Up Type=0
Dn Type=3
Dn Slope=0.005
Boundary for River Rch & Prof#=UNT0116 IN SAND ,Reach-1,6
Up Type=0
Dn Type=3
Dn Slope=0.005
Boundary for River Rch & Prof#=UNT0116 IN SAND ,Reach-1,7
Up Type=0
Dn Type=3
Dn Slope=0.005

--- UNT0116 IN SAND CR.g01 (geometry) ---

Geom Title=Existing Conditions

River Reach=UNT0116 IN SAND ,Reach-1
Reach XY= 30
      3519112.50     10510865.47      3519180.87     10510972.11
      3519212.01     10511156.67      3519185.22     10511256.84
      3519226.83     10511312.68      3519224.06     10511375.72
      3519256.42     10511494.57      3519398.91     10511683.17
      3519406.98     10511734.67      3519377.30     10511864.08
      3519653.36     10511958.28      3519750.53     10511935.74
      3519810.26     10511973.88      3519817.12     10512024.92
      3519865.73     10512023.54      3519920.59     10512060.34
      3519984.48     10512072.15      3520069.89     10512070.06
      3520127.53     10512111.73      3520228.92     10512002.01
      3520308.78     10511992.29      3520335.87     10511936.73
      3520552.71     10511893.09      3520704.14     10511838.15
      3520747.37     10511843.88      3520794.76     10511881.38
      3521028.68     10512150.07      3521190.14     10512268.13
      3522342.19     10512312.40      3525960.58     10512061.64

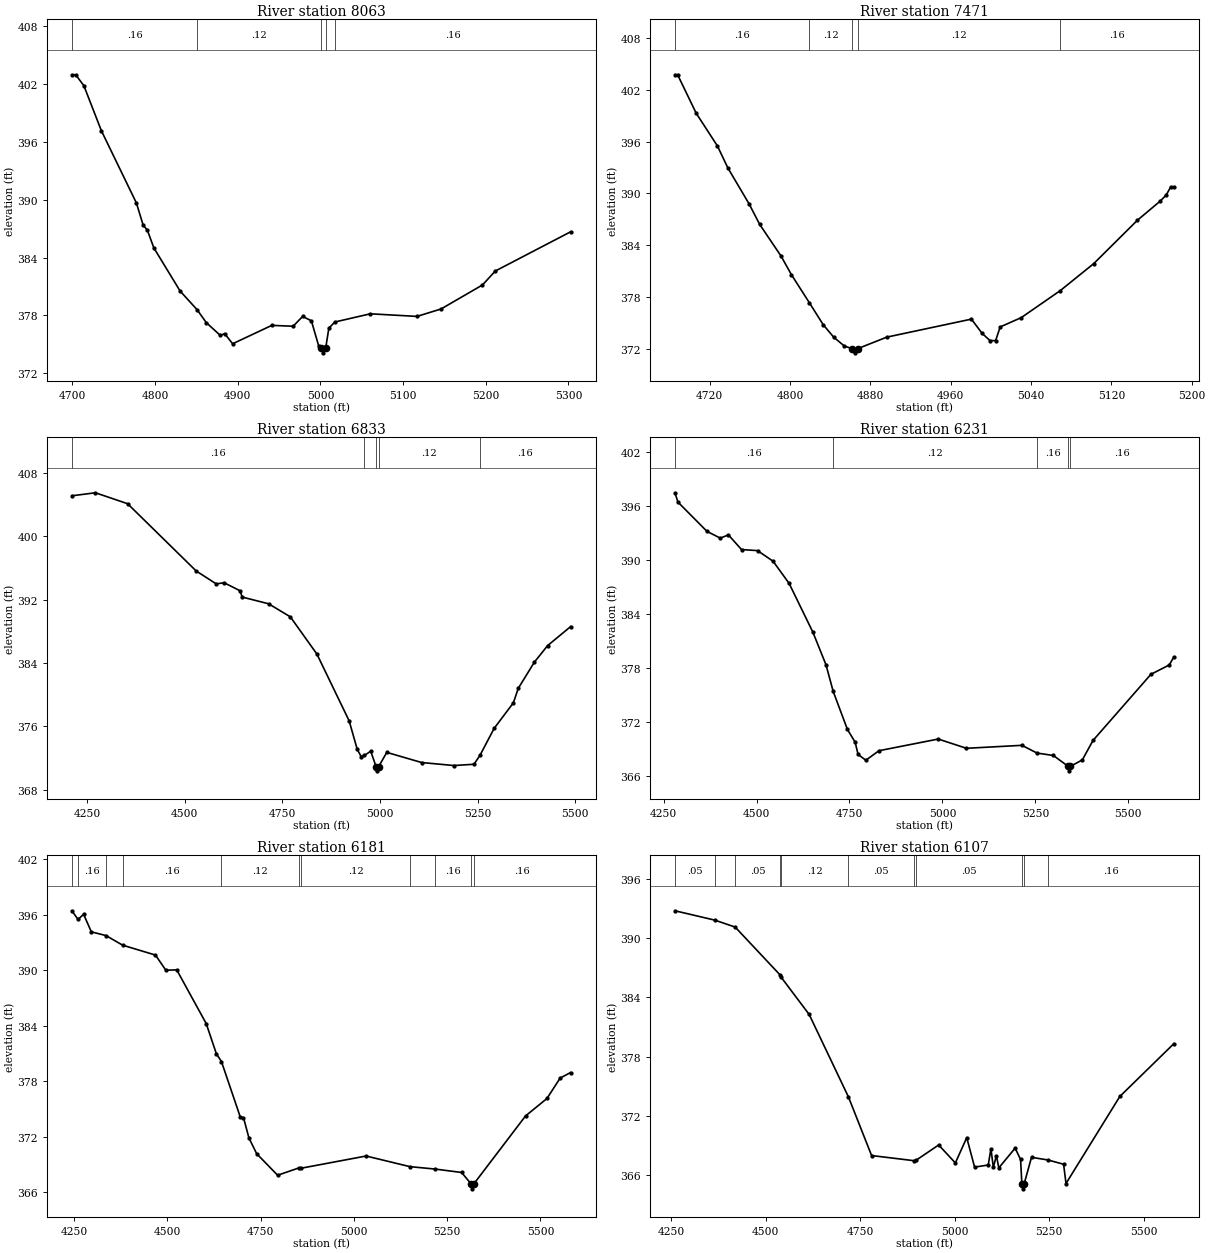
Type RM Length L Ch R = 1,8063,592,592,592
BEGIN DESCRIPTION:
UNT0116 IN SAND CR 9.0
END DESCRIPTION:
XS GIS Cut Line= 3
      3518838.43     10510995.74      3519229.02     10510860.34
      3519418.54     10510872.40
#Sta/Elev= 30
  4699.3  402.96  4703.9  402.96  4713.8  401.82  4734.9  397.16  4777.3  389.66
  4785.4  387.38  4790.6  386.83  4798.4  385.00  4830.2  380.52  4850.7  378.59
  4861.9  377.24  4878.8  375.92  4884.1  376.10  4893.7  375.05  4941.1  376.96
  4966.9  376.87  4978.4  377.89  4989.0  377.43  4998.0  374.77  5000.3  374.61
  5003.1  374.11  5006.3  374.61  5010.1  376.67  5017.4  377.31  5060.3  378.16
  5116.7  377.89  5145.8  378.66  5195.9  381.15  5211.5  382.60  5302.6  386.67
#Mann=5,-1,0
  4699.3    0.16       0  4850.7    0.12       0  5000.3    0.07       0
  5006.3    0.12       0  5017.4    0.16       0
Bank Sta=5000.3,5006.3
Exp/Cntr=0.3,0.1

Type RM Length L Ch R = 1,7471,638,638,638
BEGIN DESCRIPTION:
UNT0116 IN SAND CR 8.0
END DESCRIPTION:
XS GIS Cut Line= 3
      3518942.11     10511541.64      3519242.11     10511441.64
      3519392.10     10511341.64
#Sta/Elev= 30
  4685.6  403.74  4688.2  403.74  4706.7  399.28  4727.8  395.49  4738.3  392.92
  4759.4  388.76  4769.9  386.39  4791.0  382.75  4801.5  380.56  4819.4  377.30
  4833.2  374.75  4843.7  373.30  4854.3  372.28  4861.8  372.00  4864.5  371.50
  4867.8  372.00  4896.4  373.32  4980.7  375.41  4991.3  373.76  4999.2  372.92
  5004.8  372.92  5009.3  374.50  5030.4  375.59  5069.2  378.72  5102.5  381.85
  5146.0  386.88  5168.6  389.09  5174.6  389.80  5179.1  390.74  5182.1  390.74
#Mann=5,-1,0
  4685.6    0.16       0  4819.4    0.12       0  4861.8    0.07       0
  4867.8    0.12       0  5069.2    0.16       0
Bank Sta=4861.8,4867.8
Exp/Cntr=0.3,0.1

Type RM Length L Ch R = 1,6833,602,602,602
BEGIN DESCRIPTION:
UNT0116 IN SAND CR 6.0
END DESCRIPTION:
XS GIS Cut Line= 2
      3519331.17     10512680.03      3519642.10     10511441.67
#Sta/Elev= 30
  4211.1  405.11  4271.3  405.49  4353.6  404.11  4529.1  395.62  4580.6  393.98
  4600.6  394.13  4641.7  393.11  4646.9  392.32  4714.6  391.47  4770.3  389.82
  4838.4  385.11  4920.9  376.68  4941.5  373.09  4951.8  372.15  4959.7  372.31
  4976.1  372.85  4990.0  370.87  4992.8  370.37  4996.0  370.87  5017.2  372.70
  5106.4  371.42  5188.9  371.04  5240.5  371.20  5256.0  372.35  5292.0  375.73
  5341.3  378.96  5353.9  380.80  5395.1  384.10  5428.8  386.18  5487.9  388.59
#Mann=5,-1,0
  4211.1    0.16       0  4959.7    0.12       0  4990.0    0.07       0
  4996.0    0.12       0  5256.0    0.16       0
Bank Sta=4990,4996
Exp/Cntr=0.3,0.1

Type RM Length L Ch R = 1,6231,50,50,50
BEGIN DESCRIPTION:
UNT0116 IN SAND CR 5.1
END DESCRIPTION:
XS GIS Cut Line= 4
      3519595.52     10512636.61      3520028.83     10512097.23
      3520044.45     10512040.81      3520427.63     10511590.87
#Sta/Elev= 30
  4280.8  397.50  4288.5  396.47  4366.9  393.20  4402.6  392.45  4424.4  392.81
  4459.7  391.18  4502.8  391.06  4544.5  389.88  4587.7  387.41  4651.7  381.97
  4686.9  378.35  4706.2  375.39  4744.5  371.15  4765.3  369.73  4773.2  368.36
  4794.1  367.72  4829.3  368.78  4988.8  370.08  5064.6  369.05  5213.9  369.38
  5254.4  368.52  5298.4  368.25  5338.3  367.04  5341.0  366.54  5344.3  367.04
  5376.4  367.76  5405.0  369.92  5560.9  377.29  5610.3  378.33  5622.2  379.20
#Mann=5,-1,0
  4280.8    0.16       0  4706.2    0.12       0  5254.4    0.16       0
  5338.3    0.07       0  5344.3    0.16       0
Bank Sta=5338.3,5344.3
Exp/Cntr=0.3,0.1

Type RM Length L Ch R = 1,6181,74,74,74
BEGIN DESCRIPTION:
UNT0116 IN SAND CR 5.0
END DESCRIPTION:
XS GIS Cut Line= 2
      3519626.94     10512679.97      3520434.93     10511615.37
#Sta/Elev= 30
  4244.3  396.43  4260.7  395.49  4275.6  396.05  4296.4  394.15  4335.5  393.75
  4380.2  392.71  4468.2  391.64  4496.1  390.00  4525.2  390.04  4604.2  384.23
  4631.4  380.97  4645.0  380.13  4695.8  374.09  4704.1  374.06  4718.6  371.87
  4739.4  370.16  4795.6  367.83  4853.2  368.63  4858.6  368.59  5032.7  369.91
  5150.1  368.76  5217.3  368.50  5288.6  368.13  5314.7  366.86  5317.4  366.36
  5320.7  366.86  5459.9  374.24  5517.3  376.13  5552.7  378.34  5580.8  378.94
#Mann=11,-1,0
  4244.3     0.1       0  4260.7    0.16       0  4335.5    0.05       0
  4380.2    0.16       0  4645.0    0.12       0  4853.2    0.05       0
  4858.6    0.12       0  5150.1    0.05       0  5217.3    0.16       0
  5314.7    0.07       0  5320.7    0.16       0
Bank Sta=5314.7,5320.7
Exp/Cntr=0.3,0.1

Type RM Length L Ch R = 1,6107,170,170,170
BEGIN DESCRIPTION:
UNT0116 IN SAND CR 5.2
END DESCRIPTION:
XS GIS Cut Line= 4
      3519718.07     10512704.17      3520143.84     10512123.45
      3520143.41     10512093.06      3520497.68     10511647.38
#Sta/Elev= 30
  4260.1  392.75  4365.7  391.80  4419.3  391.10  4537.6  386.28  4541.5  386.00
  4615.1  382.26  4719.2  373.90  4780.3  367.98  4892.2  367.46  4897.6  367.49
  4957.8  369.05  5002.0  367.23  5032.1  369.79  5052.9  366.81  5089.0  367.02
  5096.1  368.66  5102.5  366.79  5110.6  367.97  5117.0  366.73  5160.2  368.73
  5174.6  367.58  5178.0  365.11  5180.8  364.61  5184.0  365.11  5203.5  367.80
  5247.1  367.53  5288.4  367.10  5294.8  365.15  5437.3  373.96  5579.9  379.29
#Mann=11,-1,0
  4260.1    0.05       0  4365.7     0.1       0  4419.3    0.05       0
  4537.6    0.16       0  4541.5    0.12       0  4719.2    0.05       0
  4892.2    0.12       0  4897.6    0.05       0  5178.0    0.03       0
  5184.0    0.05       0  5247.1    0.16       0
Bank Sta=5178,5184
Exp/Cntr=0.3,0.1

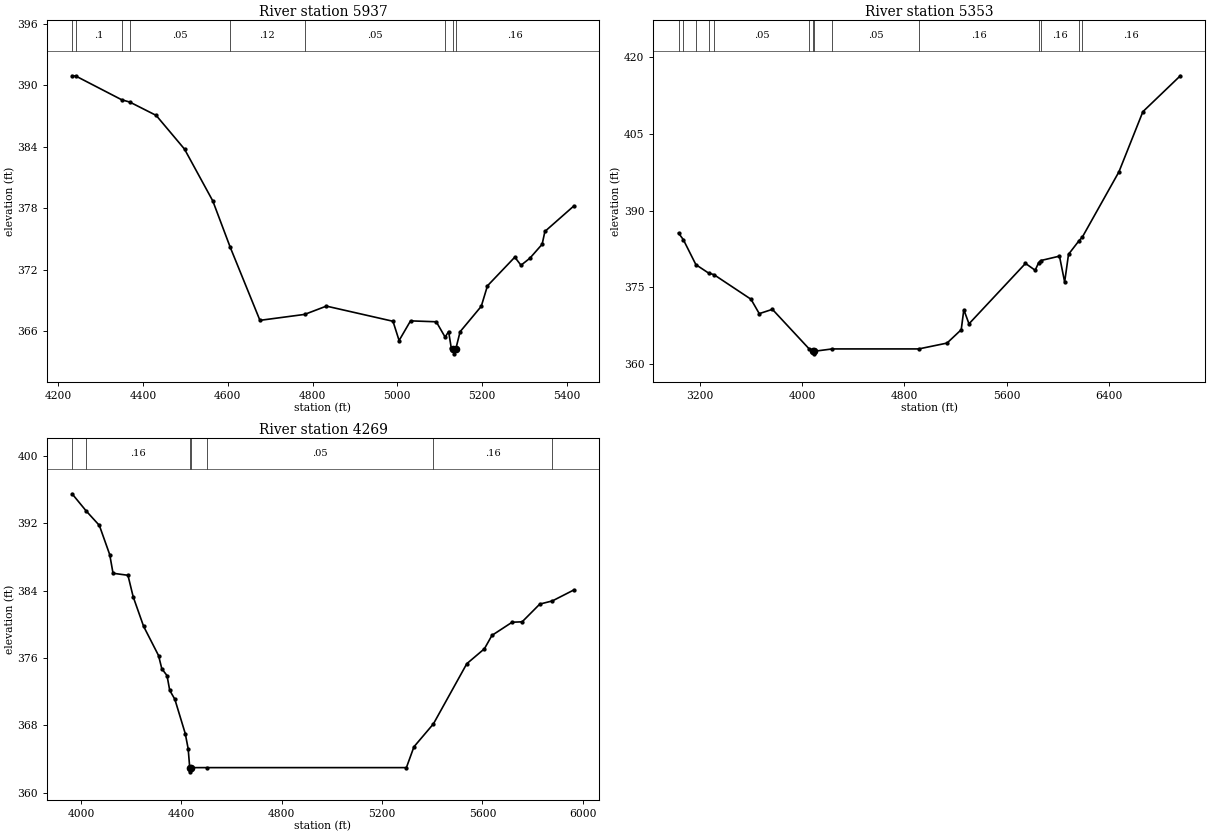
Type RM Length L Ch R = 1,5937,584,584,584
BEGIN DESCRIPTION:
UNT0116 IN SAND CR 5.3
END DESCRIPTION:
XS GIS Cut Line= 3
      3519918.60     10512686.29      3520281.46     10511972.72
      3520512.35     10511667.18
#Sta/Elev= 30
  4232.8  390.92  4241.8  390.89  4349.7  388.58  4369.1  388.35  4431.2  387.05
  4498.0  383.76  4564.7  378.70  4605.7  374.19  4675.9  367.04  4781.3  367.62
  4832.6  368.43  4989.7  366.95  5004.1  365.07  5031.1  366.99  5091.8  366.90
  5112.7  365.40  5120.9  365.95  5127.2  364.32  5132.0  364.27  5134.7  363.77
  5138.0  364.27  5148.0  365.93  5197.9  368.41  5212.5  370.41  5277.0  373.21
  5291.6  372.42  5312.4  373.10  5341.5  374.47  5348.0  375.72  5416.3  378.21
#Mann=9,-1,0
  4232.8    0.05       0  4241.8     0.1       0  4349.7    0.12       0
  4369.1    0.05       0  4605.7    0.12       0  4781.3    0.05       0
  5112.7    0.16       0  5132.0    0.03       0  5138.0    0.16       0
Bank Sta=5132,5138
Exp/Cntr=0.3,0.1

Type RM Length L Ch R = 1,5353,1084,1084,1084
BEGIN DESCRIPTION:
UNT0116 IN SAND CR 3.0
END DESCRIPTION:
XS GIS Cut Line= 3
      3520494.38     10513817.12      3520754.79     10512055.01
      3521058.61     10509936.94
#Sta/Elev= 30
  3034.4  385.62  3071.6  384.35  3170.2  379.45  3268.8  377.82  3311.3  377.50
  3600.6  372.70  3665.2  369.89  3767.8  370.73  4057.6  362.94  4088.2  362.54
  4091.0  362.04  4094.2  362.54  4235.4  363.00  4911.4  363.00  5132.2  364.14
  5243.4  366.75  5263.6  370.66  5304.0  367.90  5745.5  379.70  5821.1  378.36
  5848.0  379.83  5864.0  380.25  6011.1  381.12  6051.5  376.07  6081.8  381.48
  6165.0  384.17  6190.0  384.85  6475.8  397.59  6662.9  409.33  6955.4  416.34
#Mann=14,-1,0
  3034.4     0.1       0  3071.6    0.05       0  3170.2     0.1       0
  3268.8    0.16       0  3311.3    0.05       0  4057.6    0.16       0
  4088.2    0.07       0  4094.2    0.16       0  4235.4    0.05       0
  4911.4    0.16       0  5848.0    0.05       0  5864.0    0.16       0
  6165.0     0.1       0  6190.0    0.16       0
Bank Sta=4088.2,4094.2
Exp/Cntr=0.3,0.1

Type RM Length L Ch R = 1,4269,0,0,0
BEGIN DESCRIPTION:
UNT0116 IN SAND CR 1.0
END DESCRIPTION:
XS GIS Cut Line= 3
      3521483.96     10513296.31      3521674.92     10512610.57
      3521779.06     10511326.22
#Sta/Elev= 30
  3964.3  395.49  4020.9  393.44  4073.0  391.74  4114.5  388.26  4127.6  386.06
  4187.1  385.82  4207.9  383.27  4249.4  379.77  4309.0  376.30  4322.1  374.73
  4342.8  373.92  4353.6  372.17  4374.0  371.11  4415.5  367.04  4427.2  365.23
  4433.3  363.00  4436.0  362.50  4439.3  363.00  4502.7  363.00  5297.1  363.00
  5327.2  365.47  5404.8  368.19  5537.9  375.33  5608.1  377.10  5638.2  378.69
  5718.5  380.25  5758.6  380.30  5828.8  382.40  5879.1  382.78  5964.7  384.08
#Mann=7,-1,0
  3964.3    0.05       0  4020.9    0.16       0  4433.3   0.033       0
  4439.3    0.16       0  4502.7    0.05       0  5404.8    0.16       0
  5879.1     0.1       0
Bank Sta=4433.3,4439.3
Exp/Cntr=0.3,0.1

Chan Stop Cuts=-1