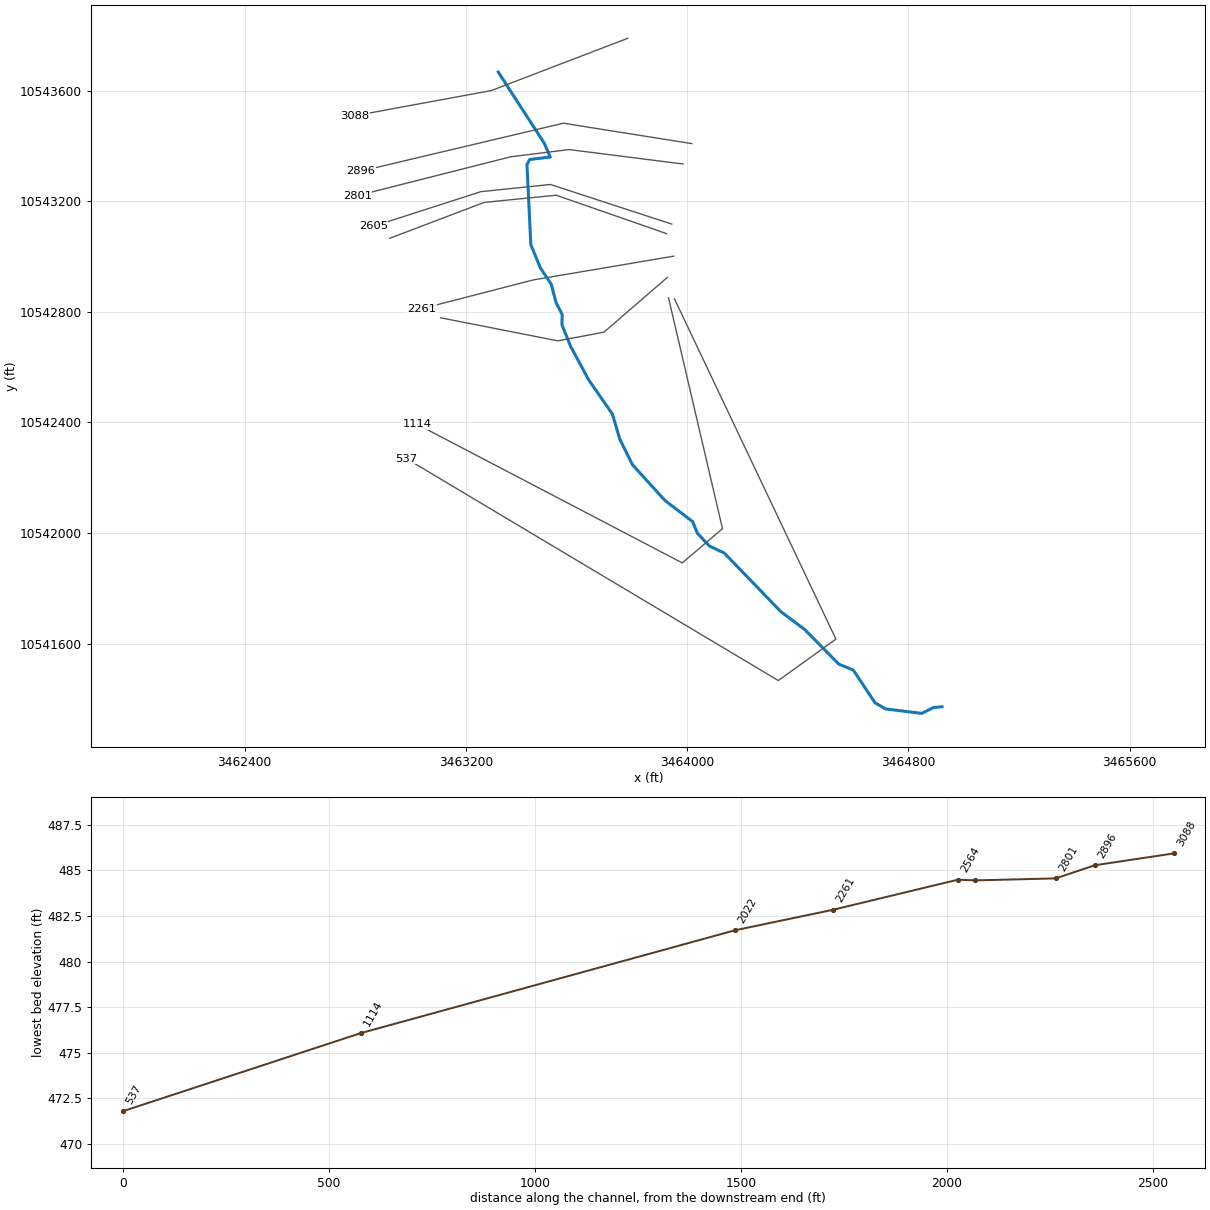
--- UNT01180 IN SAND CR.prj (project) ---

Proj Title=UNT01180 IN SAND CR Base Level Engineering
Current Plan=p01
Default Exp/Contr=0.3,0.1
English Units
Geom File=g01
Flow File=f01
Plan File=p01
BEGIN DESCRIPTION:
UNT01180 IN SAND CR
END DESCRIPTION:

--- UNT01180 IN SAND CR.p01 (plan) ---

Plan Title=Multiple Run
Short Identifier=Multiple
Geom File=g01
Flow File=f01
Subcritical Flow
K Sum by GR= 0
Std Step Tol= 0.01
Critical Tol= 0.01
Num of Std Step Trials= 20
Max Error Tol= 0.3
Flow Tol Ratio= 0.001
Split Flow NTrial= 30
Split Flow Tol= 0.02
Split Flow Ratio= 0.02
Log Output Level= 0
Friction Slope Method= 1
Unsteady Friction Slope Method= 2
Unsteady Bridges Friction Slope Method= 1
Parabolic Critical Depth
Global Vel Dist=  1 , 1 , 1
Global Log Level= 0
CheckData=True
Encroach Param= -1, 0, 0, 0
BEGIN DESCRIPTION:
Multiple Run
END DESCRIPTION:

--- UNT01180 IN SAND CR.f01 (steady flow) ---

Flow Title=Multiple
Number of Profiles=7
Profile Names=10-year,25-year,50-year,1pct_min,100-year,1pct_plu,500-year
River Rch & RM= UNT01180 IN SAND,Reach-1,3088
     400     513     601     514     696     941     928
Boundary for River Rch & Prof#=UNT01180 IN SAND,Reach-1,1
Up Type=0
Dn Type=3
Dn Slope=0.005
Boundary for River Rch & Prof#=UNT01180 IN SAND,Reach-1,2
Up Type=0
Dn Type=3
Dn Slope=0.005
Boundary for River Rch & Prof#=UNT01180 IN SAND,Reach-1,3
Up Type=0
Dn Type=3
Dn Slope=0.005
Boundary for River Rch & Prof#=UNT01180 IN SAND,Reach-1,4
Up Type=0
Dn Type=3
Dn Slope=0.005
Boundary for River Rch & Prof#=UNT01180 IN SAND,Reach-1,5
Up Type=0
Dn Type=3
Dn Slope=0.005
Boundary for River Rch & Prof#=UNT01180 IN SAND,Reach-1,6
Up Type=0
Dn Type=3
Dn Slope=0.005
Boundary for River Rch & Prof#=UNT01180 IN SAND,Reach-1,7
Up Type=0
Dn Type=3
Dn Slope=0.005

--- UNT01180 IN SAND CR.g01 (geometry) ---

Geom Title=Existing Conditions

River Reach=UNT01180 IN SAND,Reach-1
Reach XY= 30
      3463317.16     10543666.82      3463483.44     10543409.58
      3463505.32     10543359.58      3463430.84     10543350.73
      3463420.94     10543331.98      3463434.90     10543042.75
      3463469.65     10542958.32      3463508.39     10542900.16
      3463526.11     10542833.22      3463548.20     10542790.39
      3463547.46     10542752.77      3463578.71     10542674.98
      3463644.77     10542552.74      3463729.71     10542430.65
      3463756.82     10542338.88      3463802.47     10542246.79
      3463920.61     10542117.10      3464020.15     10542040.98
      3464037.47     10541998.83      3464080.95     10541952.64
      3464134.34     10541927.67      3464339.18     10541715.44
      3464425.47     10541650.94      3464548.36     10541526.07
      3464601.18     10541504.16      3464679.37     10541386.25
      3464717.63     10541363.76      3464848.35     10541347.74
      3464890.73     10541368.95      3464922.11     10541371.64

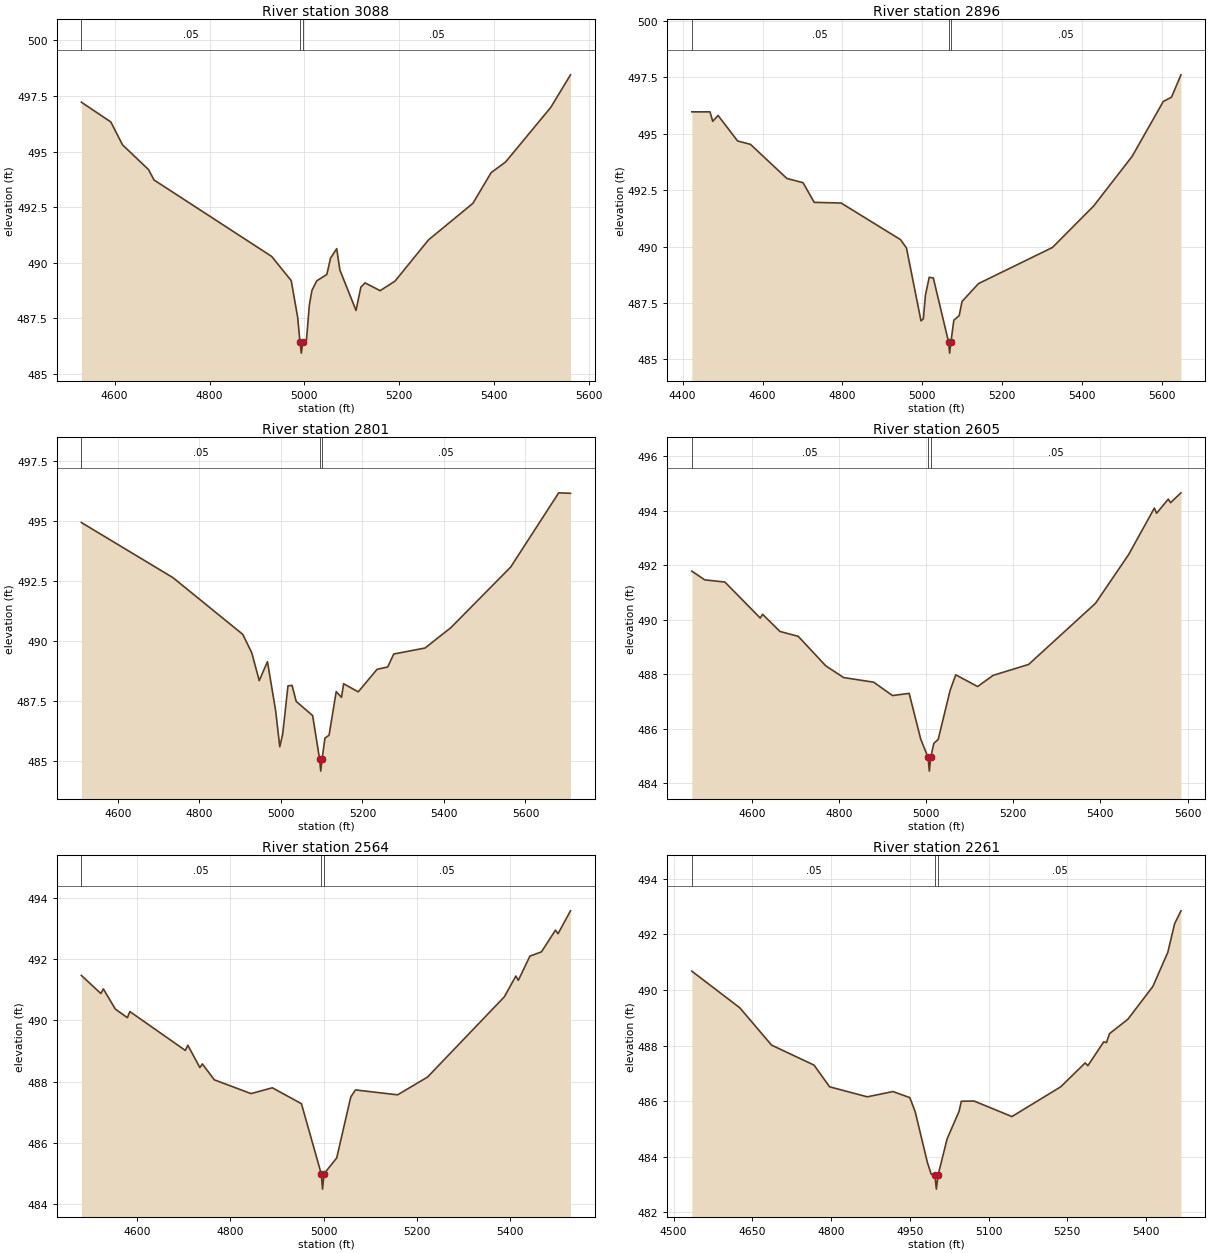
Type RM Length L Ch R = 1,3088,192,192,192
BEGIN DESCRIPTION:
UNT01180 IN SAND CR 3.2
END DESCRIPTION:
XS GIS Cut Line= 3
      3463785.03     10543788.83      3463292.44     10543600.04
      3462797.69     10543508.90
#Sta/Elev= 30
  4530.0  497.22  4592.0  496.33  4616.7  495.30  4671.4  494.19  4683.1  493.72
  4931.0  490.28  4972.2  489.19  4985.7  487.55  4990.6  486.43  4993.4  485.93
  4996.6  486.43  5004.3  486.52  5010.4  488.10  5015.8  488.75  5025.8  489.18
  5047.2  489.47  5055.0  490.20  5068.0  490.63  5074.7  489.67  5108.7  487.85
  5118.9  488.90  5127.7  489.09  5159.5  488.74  5190.9  489.17  5261.2  491.02
  5355.0  492.67  5393.4  494.05  5423.9  494.53  5519.2  496.99  5560.6  498.45
#Mann=3,-1,0
  4530.0    0.05       0  4990.6    0.03       0  4996.6    0.05       0
Bank Sta=4990.6,4996.6
Exp/Cntr=0.3,0.1

Type RM Length L Ch R = 1,2896,95,95,95
BEGIN DESCRIPTION:
UNT01180 IN SAND CR 3.1
END DESCRIPTION:
XS GIS Cut Line= 3
      3464016.96     10543408.16      3463552.55     10543481.94
      3462819.05     10543308.33
#Sta/Elev= 30
  4423.0  495.97  4468.4  495.97  4475.3  495.55  4488.7  495.81  4537.5  494.68
  4569.7  494.53  4660.8  493.02  4701.3  492.83  4729.3  491.96  4796.6  491.93
  4945.1  490.31  4960.1  489.94  4996.5  486.71  5002.3  486.80  5007.5  487.84
  5017.0  488.64  5027.3  488.61  5065.4  485.78  5068.1  485.28  5071.4  485.78
  5078.7  486.74  5092.0  486.94  5099.2  487.57  5140.3  488.36  5325.3  489.96
  5428.1  491.79  5524.9  494.00  5602.8  496.43  5623.3  496.62  5647.0  497.61
#Mann=3,-1,0
  4423.0    0.05       0  5065.4    0.03       0  5071.4    0.05       0
Bank Sta=5065.4,5071.4
Exp/Cntr=0.3,0.1

Type RM Length L Ch R = 1,2801,196,196,196
BEGIN DESCRIPTION:
UNT01180 IN SAND CR 3.0
END DESCRIPTION:
XS GIS Cut Line= 4
      3463984.86     10543334.49      3463573.36     10543386.58
      3463362.42     10543360.54      3462807.70     10543219.90
#Sta/Elev= 30
  4510.8  494.94  4735.3  492.64  4906.7  490.27  4928.7  489.50  4947.0  488.34
  4967.2  489.13  4987.3  487.08  4997.4  485.58  5004.6  486.11  5017.5  488.12
  5027.6  488.14  5037.7  487.47  5078.0  486.88  5095.1  485.06  5097.9  484.56
  5101.1  485.06  5108.2  485.94  5118.3  486.06  5135.8  487.88  5148.8  487.64
  5154.0  488.21  5189.8  487.87  5235.9  488.81  5262.2  488.91  5276.9  489.45
  5353.7  489.70  5417.0  490.55  5563.7  493.08  5681.5  496.18  5710.4  496.16
#Mann=3,-1,0
  4510.8    0.05       0  5095.1    0.03       0  5101.1    0.05       0
Bank Sta=5095.1,5101.1
Exp/Cntr=0.3,0.1

Type RM Length L Ch R = 1,2605,41,41,41
BEGIN DESCRIPTION:
UNT01180 IN SAND CR 2.0
END DESCRIPTION:
XS GIS Cut Line= 4
      3463944.29     10543117.16      3463505.92     10543260.39
      3463254.18     10543234.35      3462865.33     10543109.05
#Sta/Elev= 30
  4462.1  491.78  4491.7  491.46  4538.0  491.38  4619.2  490.06  4624.4  490.20
  4664.3  489.57  4706.4  489.39  4769.5  488.31  4810.5  487.88  4879.5  487.71
  4922.7  487.22  4961.0  487.30  4987.4  485.63  5004.5  484.95  5007.3  484.45
  5010.5  484.95  5017.6  485.47  5027.6  485.61  5054.8  487.40  5067.9  487.98
  5118.1  487.55  5153.7  487.96  5235.2  488.36  5388.7  490.60  5464.9  492.39
  5523.8  494.09  5529.0  493.90  5555.8  494.42  5561.1  494.29  5584.9  494.65
#Mann=3,-1,0
  4462.1    0.05       0  5004.5    0.04       0  5010.5    0.05       0
Bank Sta=5004.5,5010.5
Exp/Cntr=0.3,0.1

Type RM Length L Ch R = 1,2564,303,303,303
BEGIN DESCRIPTION:
UNT01180 IN SAND CR 2.1
END DESCRIPTION:
XS GIS Cut Line= 4
      3463925.81     10543082.64      3463526.51     10543221.53
      3463266.09     10543195.49      3462925.04     10543065.97
#Sta/Elev= 30
  4480.5  491.47  4522.3  490.88  4527.6  491.03  4553.4  490.37  4579.2  490.09
  4584.5  490.29  4703.6  489.02  4708.9  489.19  4734.7  488.46  4740.0  488.58
  4765.8  488.06  4844.4  487.61  4890.2  487.80  4952.6  487.28  4995.1  484.99
  4997.9  484.49  5001.1  484.99  5028.3  485.51  5058.4  487.50  5068.5  487.73
  5158.9  487.57  5223.1  488.15  5387.8  490.77  5412.6  491.45  5417.9  491.31
  5442.7  492.10  5467.5  492.24  5497.6  492.95  5503.0  492.83  5529.8  493.58
#Mann=3,-1,0
  4480.5    0.05       0  4995.1    0.04       0  5001.1    0.05       0
Bank Sta=4995.1,5001.1
Exp/Cntr=0.3,0.1

Type RM Length L Ch R = 1,2261,239,239,239
BEGIN DESCRIPTION:
UNT01180 IN SAND CR 4.0
END DESCRIPTION:
XS GIS Cut Line= 3
      3463951.72     10543001.16      3463443.93     10542915.23
      3463040.26     10542811.05
#Sta/Elev= 30
  4534.6  490.68  4626.1  489.36  4686.5  488.02  4767.5  487.30  4797.1  486.52
  4868.9  486.16  4917.9  486.35  4950.0  486.13  4960.2  485.62  4983.4  483.80
  4990.6  483.38  4997.7  483.34  5000.5  482.84  5003.7  483.34  5021.0  484.65
  5043.8  485.64  5048.0  486.00  5072.1  486.01  5144.4  485.45  5237.4  486.52
  5284.0  487.38  5289.1  487.28  5319.5  488.14  5324.6  488.11  5330.3  488.43
  5365.3  488.95  5413.0  490.13  5441.5  491.36  5454.3  492.38  5466.5  492.85
#Mann=3,-1,0
  4534.6    0.05       0  4997.7    0.03       0  5003.7    0.05       0
Bank Sta=4997.7,5003.7
Exp/Cntr=0.3,0.1

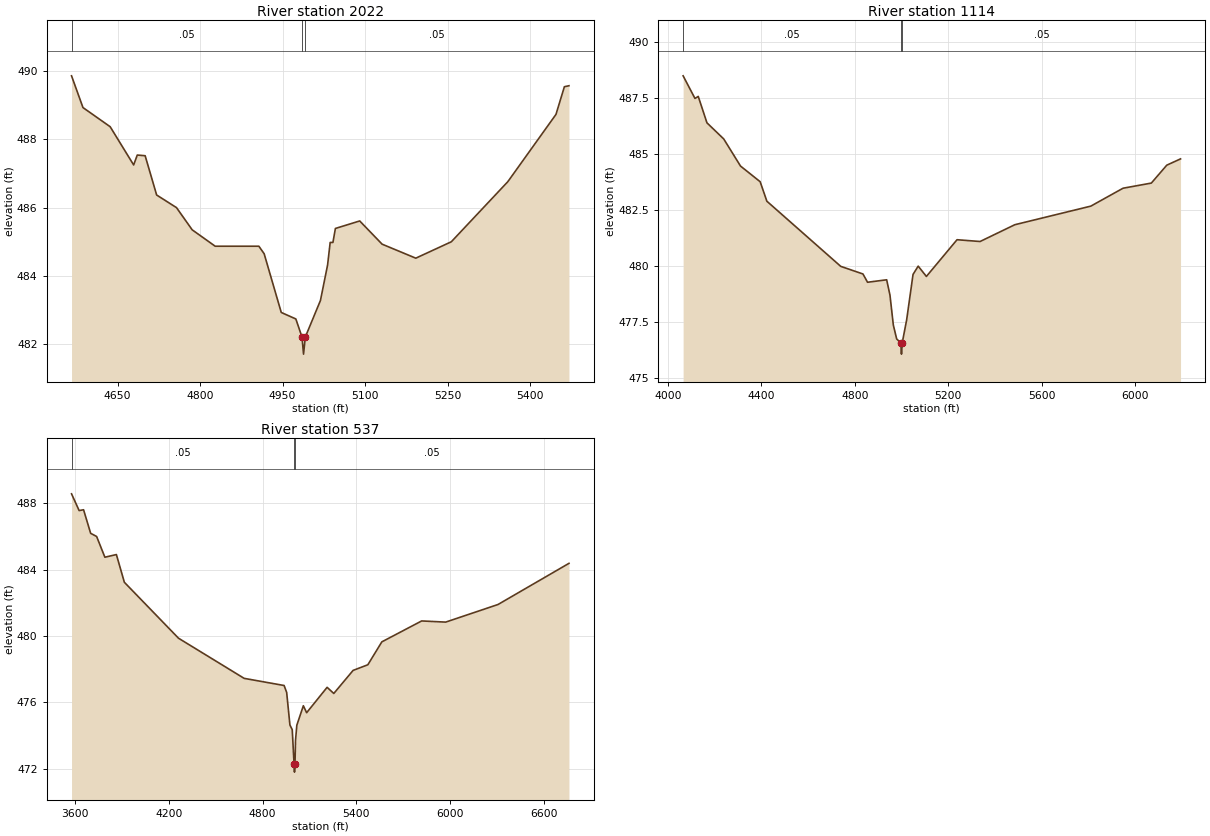
Type RM Length L Ch R = 1,2022,908,908,908
BEGIN DESCRIPTION:
UNT01180 IN SAND CR 1.01
END DESCRIPTION:
XS GIS Cut Line= 4
      3463928.35     10542924.10      3463699.16     10542726.16
      3463532.50     10542694.91      3463108.91     10542778.24
#Sta/Elev= 30
  4566.4  489.86  4587.2  488.93  4636.6  488.37  4679.3  487.25  4685.9  487.54
  4700.2  487.52  4721.1  486.37  4757.2  486.00  4785.7  485.35  4827.5  484.87
  4906.9  484.87  4916.5  484.65  4947.6  482.93  4974.1  482.74  4985.3  482.21
  4988.1  481.71  4991.3  482.21  5018.8  483.28  5031.8  484.32  5036.5  484.98
  5041.5  484.98  5046.0  485.39  5090.2  485.61  5130.9  484.93  5192.1  484.52
  5256.7  485.00  5359.4  486.76  5446.9  488.73  5462.2  489.54  5470.5  489.57
#Mann=3,-1,0
  4566.4    0.05       0  4985.3    0.03       0  4991.3    0.05       0
Bank Sta=4985.3,4991.3
Exp/Cntr=0.3,0.1

Type RM Length L Ch R = 1,1114,577,577,577
BEGIN DESCRIPTION:
UNT01180 IN SAND CR 1.03
END DESCRIPTION:
XS GIS Cut Line= 4
      3463932.67     10542851.06      3464127.98     10542015.55
      3463982.58     10541891.85      3463023.41     10542393.14
#Sta/Elev= 30
  4064.5  488.50  4115.2  487.49  4129.3  487.58  4166.6  486.40  4238.5  485.68
  4310.4  484.47  4394.6  483.77  4423.3  482.90  4739.8  479.99  4835.0  479.65
  4854.7  479.28  4936.6  479.39  4950.8  478.70  4965.1  477.37  4979.4  476.75
  4997.2  476.57  5000.0  476.07  5003.2  476.57  5022.2  477.60  5049.6  479.63
  5071.6  480.00  5106.8  479.54  5238.1  481.18  5336.8  481.10  5485.7  481.85
  5811.3  482.68  5949.4  483.48  6070.6  483.71  6136.8  484.51  6195.7  484.79
#Mann=3,-1,0
  4064.5    0.05       0  4997.2    0.03       0  5003.2    0.05       0
Bank Sta=4997.2,5003.2
Exp/Cntr=0.3,0.1

Type RM Length L Ch R = 1,537,0,0,0
BEGIN DESCRIPTION:
UNT01180 IN SAND CR 1.0
END DESCRIPTION:
XS GIS Cut Line= 4
      3463954.36     10542846.73      3464538.14     10541616.24
      3464329.81     10541466.50      3462985.75     10542268.60
#Sta/Elev= 30
  3576.6  488.56  3625.3  487.55  3653.6  487.60  3699.0  486.18  3737.2  485.99
  3790.0  484.74  3863.7  484.90  3914.7  483.23  4261.2  479.86  4681.5  477.44
  4937.1  477.01  4953.6  476.59  4974.4  474.63  4989.2  474.35  5000.9  472.29
  5003.6  471.79  5006.9  472.29  5010.1  473.69  5018.6  474.62  5060.4  475.79
  5081.4  475.37  5212.4  476.90  5255.2  476.53  5378.8  477.92  5473.2  478.26
  5562.7  479.64  5817.6  480.90  5971.4  480.83  6306.1  481.89  6760.3  484.37
#Mann=3,-1,0
  3576.6    0.05       0  5000.9    0.03       0  5006.9    0.05       0
Bank Sta=5000.9,5006.9
Exp/Cntr=0.3,0.1

Chan Stop Cuts=-1