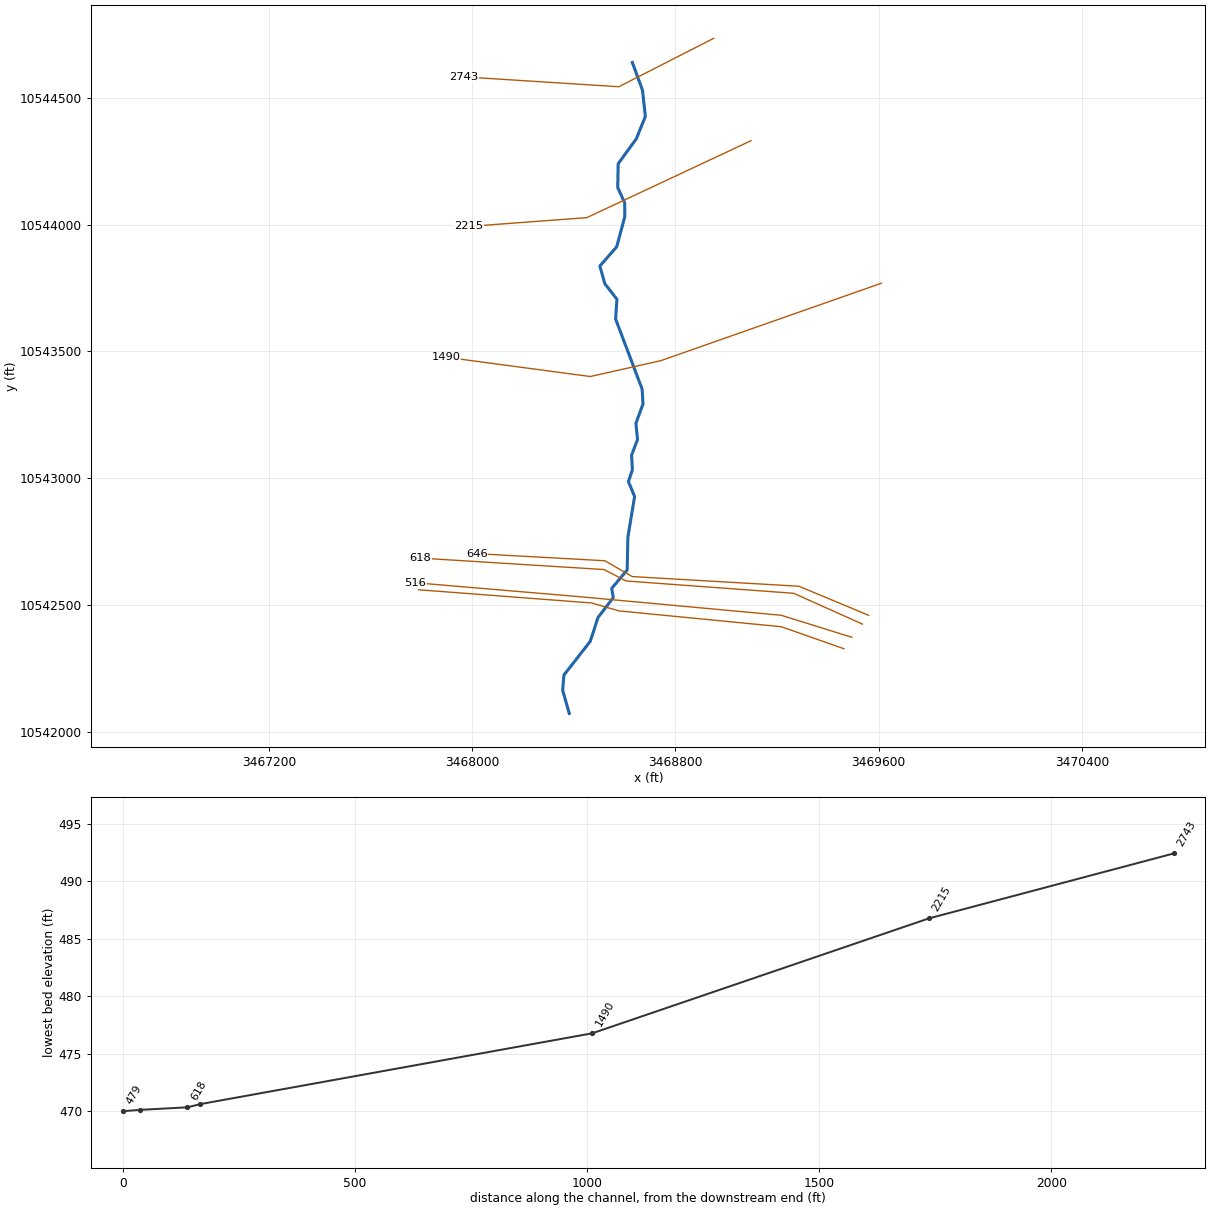
--- UNT01184 IN SAND CR.prj (project) ---

Proj Title=UNT01184 IN SAND CR Base Level Engineering
Current Plan=p01
Default Exp/Contr=0.3,0.1
English Units
Geom File=g01
Flow File=f01
Plan File=p01
BEGIN DESCRIPTION:
UNT01184 IN SAND CR
END DESCRIPTION:

--- UNT01184 IN SAND CR.p01 (plan) ---

Plan Title=Multiple Run
Short Identifier=Multiple
Geom File=g01
Flow File=f01
Subcritical Flow
K Sum by GR= 0
Std Step Tol= 0.01
Critical Tol= 0.01
Num of Std Step Trials= 20
Max Error Tol= 0.3
Flow Tol Ratio= 0.001
Split Flow NTrial= 30
Split Flow Tol= 0.02
Split Flow Ratio= 0.02
Log Output Level= 0
Friction Slope Method= 1
Unsteady Friction Slope Method= 2
Unsteady Bridges Friction Slope Method= 1
Parabolic Critical Depth
Global Vel Dist=  1 , 1 , 1
Global Log Level= 0
CheckData=True
Encroach Param= -1, 0, 0, 0
BEGIN DESCRIPTION:
Multiple Run
END DESCRIPTION:

--- UNT01184 IN SAND CR.f01 (steady flow) ---

Flow Title=Multiple
Number of Profiles=7
Profile Names=10-year,25-year,50-year,1pct_min,100-year,1pct_plu,500-year
River Rch & RM= UNT01184 IN SAND,Reach-1,2743
     459     599     709     614     830    1122    1132
Boundary for River Rch & Prof#=UNT01184 IN SAND,Reach-1,1
Up Type=0
Dn Type=3
Dn Slope=0.005
Boundary for River Rch & Prof#=UNT01184 IN SAND,Reach-1,2
Up Type=0
Dn Type=3
Dn Slope=0.005
Boundary for River Rch & Prof#=UNT01184 IN SAND,Reach-1,3
Up Type=0
Dn Type=3
Dn Slope=0.005
Boundary for River Rch & Prof#=UNT01184 IN SAND,Reach-1,4
Up Type=0
Dn Type=3
Dn Slope=0.005
Boundary for River Rch & Prof#=UNT01184 IN SAND,Reach-1,5
Up Type=0
Dn Type=3
Dn Slope=0.005
Boundary for River Rch & Prof#=UNT01184 IN SAND,Reach-1,6
Up Type=0
Dn Type=3
Dn Slope=0.005
Boundary for River Rch & Prof#=UNT01184 IN SAND,Reach-1,7
Up Type=0
Dn Type=3
Dn Slope=0.005

--- UNT01184 IN SAND CR.g01 (geometry) ---

Geom Title=Existing Conditions

River Reach=UNT01184 IN SAND,Reach-1
Reach XY= 30
      3468630.39     10544640.12      3468670.41     10544530.03
      3468681.60     10544426.98      3468646.19     10544339.14
      3468574.65     10544240.55      3468572.86     10544146.35
      3468600.24     10544086.04      3468600.73     10544031.73
      3468568.87     10543912.89      3468502.44     10543836.51
      3468522.24     10543766.72      3468569.80     10543705.65
      3468564.49     10543627.68      3468669.15     10543350.32
      3468672.09     10543291.81      3468644.40     10543215.86
      3468650.79     10543152.09      3468627.35     10543090.57
      3468630.50     10543032.21      3468615.07     10542986.07
      3468639.26     10542927.20      3468612.85     10542766.82
      3468609.91     10542637.36      3468549.08     10542564.54
      3468555.20     10542528.22      3468495.45     10542450.29
      3468464.39     10542355.41      3468360.97     10542222.70
      3468356.22     10542162.56      3468382.11     10542071.64

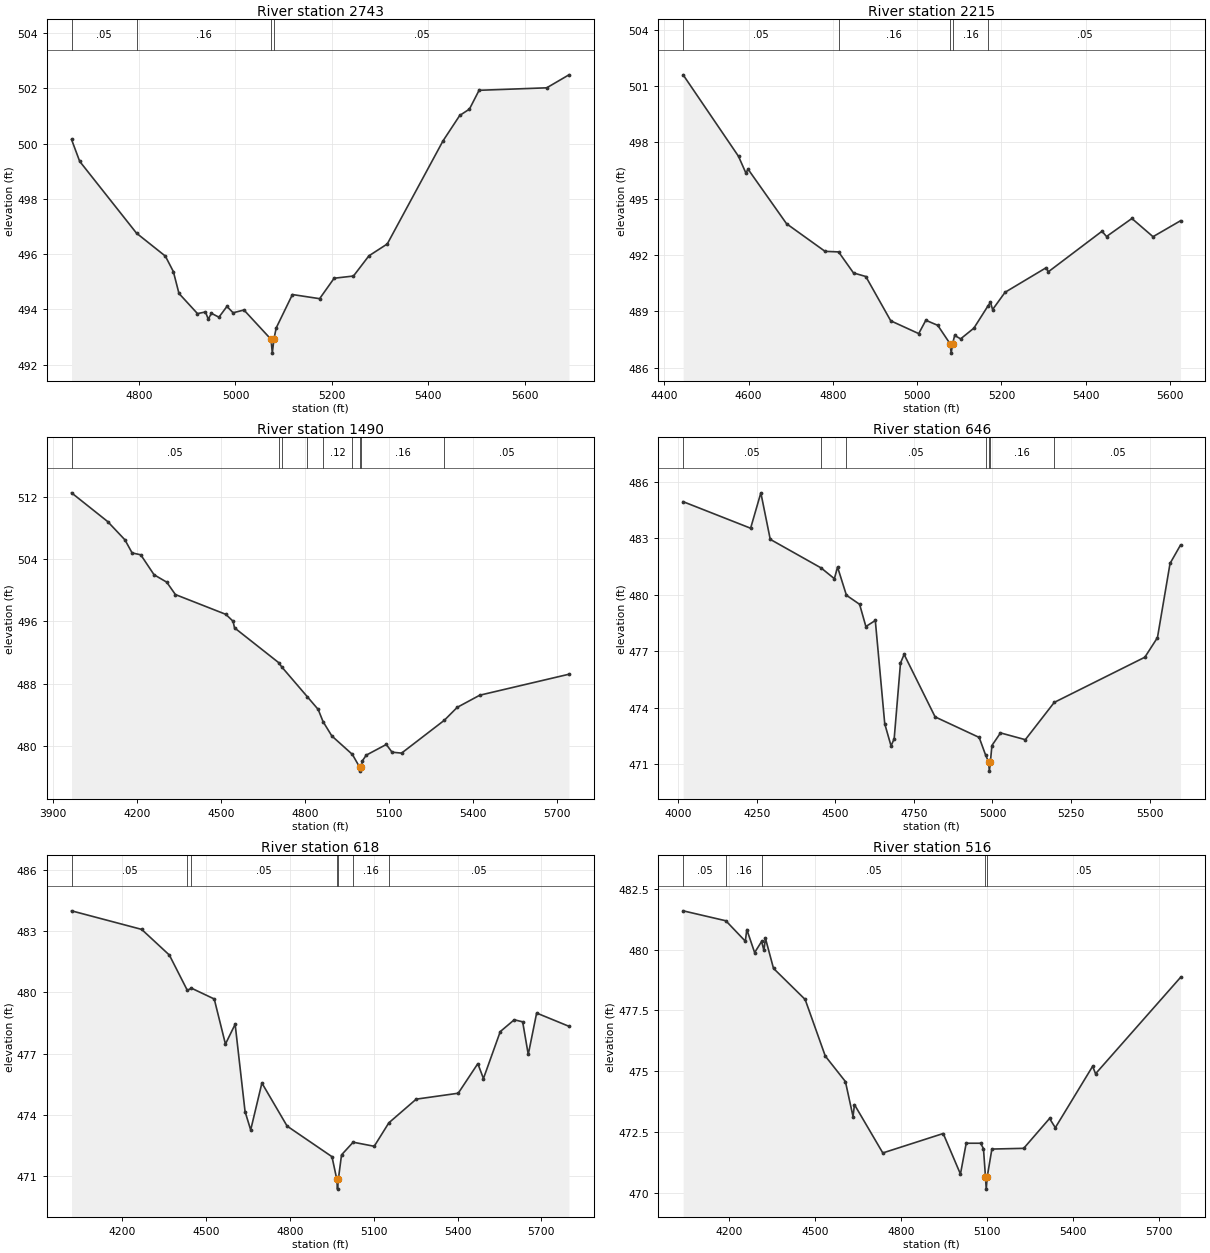
Type RM Length L Ch R = 1,2743,528,528,528
BEGIN DESCRIPTION:
UNT01184 IN SAND CR 5.0
END DESCRIPTION:
XS GIS Cut Line= 3
      3468950.43     10544735.24      3468577.15     10544544.26
      3467966.10     10544583.26
#Sta/Elev= 30
  4660.0  500.15  4676.9  499.36  4794.8  496.76  4854.6  495.93  4871.2  495.37
  4882.8  494.58  4921.2  493.85  4937.8  493.91  4943.5  493.65  4950.2  493.86
  4965.7  493.72  4982.3  494.11  4995.1  493.88  5017.6  493.98  5073.7  492.92
  5076.4  492.42  5079.7  492.92  5084.4  493.33  5118.1  494.54  5174.5  494.39
  5204.6  495.13  5244.7  495.21  5276.7  495.94  5314.8  496.37  5430.4  500.10
  5465.1  501.02  5485.2  501.25  5505.2  501.93  5645.5  502.02  5691.6  502.49
#Mann=4,-1,0
  4660.0    0.05       0  4794.8    0.16       0  5073.7    0.07       0
  5079.7    0.05       0
Bank Sta=5073.7,5079.7
Exp/Cntr=0.3,0.1

Type RM Length L Ch R = 1,2215,725,725,725
BEGIN DESCRIPTION:
UNT01184 IN SAND CR 5.1
END DESCRIPTION:
XS GIS Cut Line= 3
      3469097.98     10544331.59      3468451.28     10544027.77
      3467986.99     10543993.05
#Sta/Elev= 30
  4444.7  501.59  4576.1  497.25  4593.4  496.37  4598.9  496.56  4690.1  493.66
  4781.4  492.19  4813.5  492.16  4848.9  491.04  4878.1  490.85  4937.3  488.49
  5003.6  487.81  5020.5  488.52  5048.8  488.25  5078.0  487.27  5080.7  486.77
  5084.0  487.27  5088.9  487.71  5103.1  487.53  5134.5  488.10  5168.4  489.30
  5173.9  489.48  5178.9  489.09  5208.5  490.01  5306.1  491.32  5311.1  491.10
  5438.4  493.26  5449.2  492.98  5509.4  493.94  5559.5  492.97  5624.8  493.82
#Mann=5,-1,0
  4444.7    0.05       0  4813.5    0.16       0  5078.0    0.07       0
  5084.0    0.16       0  5168.4    0.05       0
Bank Sta=5078,5084
Exp/Cntr=0.3,0.1

Type RM Length L Ch R = 1,1490,844,844,844
BEGIN DESCRIPTION:
UNT01184 IN SAND CR 3.0
END DESCRIPTION:
XS GIS Cut Line= 4
      3469610.43     10543768.89      3468742.33     10543463.32
      3468464.55     10543400.82      3467896.07     10543477.08
#Sta/Elev= 30
  3965.7  512.49  4094.7  508.81  4156.6  506.46  4182.3  504.78  4213.2  504.54
  4260.8  501.98  4306.1  501.03  4337.1  499.44  4517.5  496.90  4543.2  496.02
  4548.5  495.17  4706.6  490.70  4716.6  490.19  4809.3  486.31  4847.5  484.71
  4865.2  483.13  4896.5  481.30  4970.0  478.93  4996.0  477.29  4998.7  476.79
  5002.0  477.29  5005.8  478.12  5019.5  478.84  5091.2  480.21  5111.7  479.22
  5145.9  479.10  5298.9  483.32  5344.7  484.97  5425.4  486.53  5744.3  489.22
#Mann=9,-1,0
  3965.7    0.05       0  4706.6    0.16       0  4716.6    0.12       0
  4809.3    0.16       0  4865.2    0.12       0  4970.0    0.16       0
  4996.0    0.07       0  5002.0    0.16       0  5298.9    0.05       0
Bank Sta=4996,5002
Exp/Cntr=0.3,0.1

Type RM Length L Ch R = 1,646,28,28,28
BEGIN DESCRIPTION:
UNT01184 IN SAND CR 1.3
END DESCRIPTION:
XS GIS Cut Line= 5
      3469560.34     10542458.66      3469286.03     10542573.25
      3468629.78     10542611.44      3468522.15     10542673.94
      3468018.72     10542701.72
#Sta/Elev= 30
  4015.4  484.95  4230.2  483.54  4262.8  485.42  4292.7  482.95  4454.7  481.43
  4496.9  480.86  4506.9  481.48  4535.2  479.98  4577.1  479.50  4597.1  478.32
  4627.1  478.64  4657.2  473.15  4677.2  471.98  4687.2  472.36  4707.3  476.38
  4718.8  476.84  4817.5  473.52  4957.7  472.43  4978.3  471.49  4987.5  471.14
  4990.2  470.64  4993.5  471.14  4998.3  472.00  5025.6  472.67  5104.6  472.31
  5196.7  474.29  5485.1  476.69  5525.2  477.73  5565.3  481.67  5598.7  482.65
#Mann=7,-1,0
  4015.4    0.05       0  4454.7    0.16       0  4535.2    0.05       0
  4978.3    0.16       0  4987.5    0.07       0  4993.5    0.16       0
  5196.7    0.05       0
Bank Sta=4987.5,4993.5
Exp/Cntr=0.3,0.1

Type RM Length L Ch R = 1,618,102,102,102
BEGIN DESCRIPTION:
UNT01184 IN SAND CR 1.0
END DESCRIPTION:
XS GIS Cut Line= 5
      3469536.03     10542423.95      3469265.20     10542545.47
      3468605.48     10542594.08      3468518.67     10542639.22
      3467796.78     10542684.34
#Sta/Elev= 30
  4019.2  484.00  4270.1  483.09  4369.3  481.83  4433.5  480.10  4448.0  480.21
  4529.7  479.68  4569.8  477.47  4604.5  478.44  4640.0  474.16  4660.1  473.26
  4700.2  475.56  4790.4  473.45  4950.9  471.95  4967.9  470.86  4970.7  470.36
  4973.9  470.86  4985.1  472.04  5026.7  472.66  5102.0  472.46  5154.4  473.61
  5252.3  474.77  5402.6  475.06  5472.7  476.51  5492.8  475.78  5552.9  478.08
  5603.0  478.66  5633.1  478.56  5653.1  476.96  5683.1  478.99  5798.7  478.34
#Mann=7,-1,0
  4019.2    0.05       0  4433.5    0.16       0  4448.0    0.05       0
  4967.9    0.04       0  4973.9    0.05       0  5026.7    0.16       0
  5154.4    0.05       0
Bank Sta=4967.9,4973.9
Exp/Cntr=0.3,0.1

Type RM Length L Ch R = 1,516,37,37,37
BEGIN DESCRIPTION:
UNT01184 IN SAND CR 1.1
END DESCRIPTION:
XS GIS Cut Line= 4
      3469494.39     10542371.86      3469216.59     10542458.67
      3468428.40     10542531.58      3467776.36     10542587.08
#Sta/Elev= 30
  4039.9  481.60  4189.1  481.19  4257.1  480.35  4262.3  480.83  4289.6  479.88
  4314.0  480.34  4322.0  479.97  4327.3  480.47  4355.5  479.23  4466.0  477.95
  4536.3  475.62  4606.6  474.57  4633.2  473.13  4638.2  473.62  4737.2  471.63
  4948.1  472.43  5008.3  470.76  5028.4  472.03  5078.6  472.03  5088.7  471.81
  5095.7  470.64  5098.4  470.14  5101.7  470.64  5118.1  471.79  5229.2  471.82
  5319.5  473.05  5339.6  472.67  5470.0  475.20  5480.1  474.89  5776.9  478.86
#Mann=5,-1,0
  4039.9    0.05       0  4189.1    0.16       0  4314.0    0.05       0
  5095.7   0.035       0  5101.7    0.05       0
Bank Sta=5095.7,5101.7
Exp/Cntr=0.3,0.1

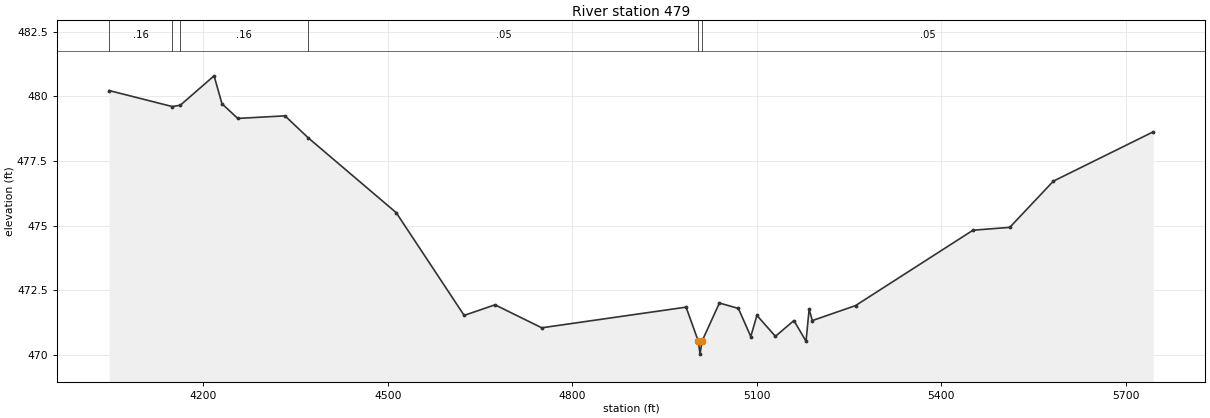
Type RM Length L Ch R = 1,479,0,0,0
BEGIN DESCRIPTION:
UNT01184 IN SAND CR 1.2
END DESCRIPTION:
XS GIS Cut Line= 5
      3469463.14     10542326.71      3469216.59     10542413.53
      3468577.70     10542476.03      3468470.06     10542507.28
      3467789.46     10542559.36
#Sta/Elev= 30
  4046.6  480.23  4149.3  479.61  4162.3  479.66  4217.3  480.80  4230.1  479.72
  4255.8  479.15  4332.6  479.25  4370.8  478.39  4513.5  475.50  4624.0  471.52
  4674.2  471.93  4750.2  471.04  4984.9  471.84  5004.8  470.52  5007.6  470.02
  5010.8  470.52  5039.1  472.00  5070.0  471.79  5090.1  470.70  5100.1  471.52
  5130.2  470.71  5160.3  471.32  5180.0  470.52  5185.0  471.75  5190.3  471.32
  5260.5  471.90  5451.5  474.82  5511.3  474.93  5582.2  476.72  5744.6  478.63
#Mann=6,-1,0
  4046.6    0.16       0  4149.3    0.05       0  4162.3    0.16       0
  4370.8    0.05       0  5004.8   0.035       0  5010.8    0.05       0
Bank Sta=5004.8,5010.8
Exp/Cntr=0.3,0.1

Chan Stop Cuts=-1