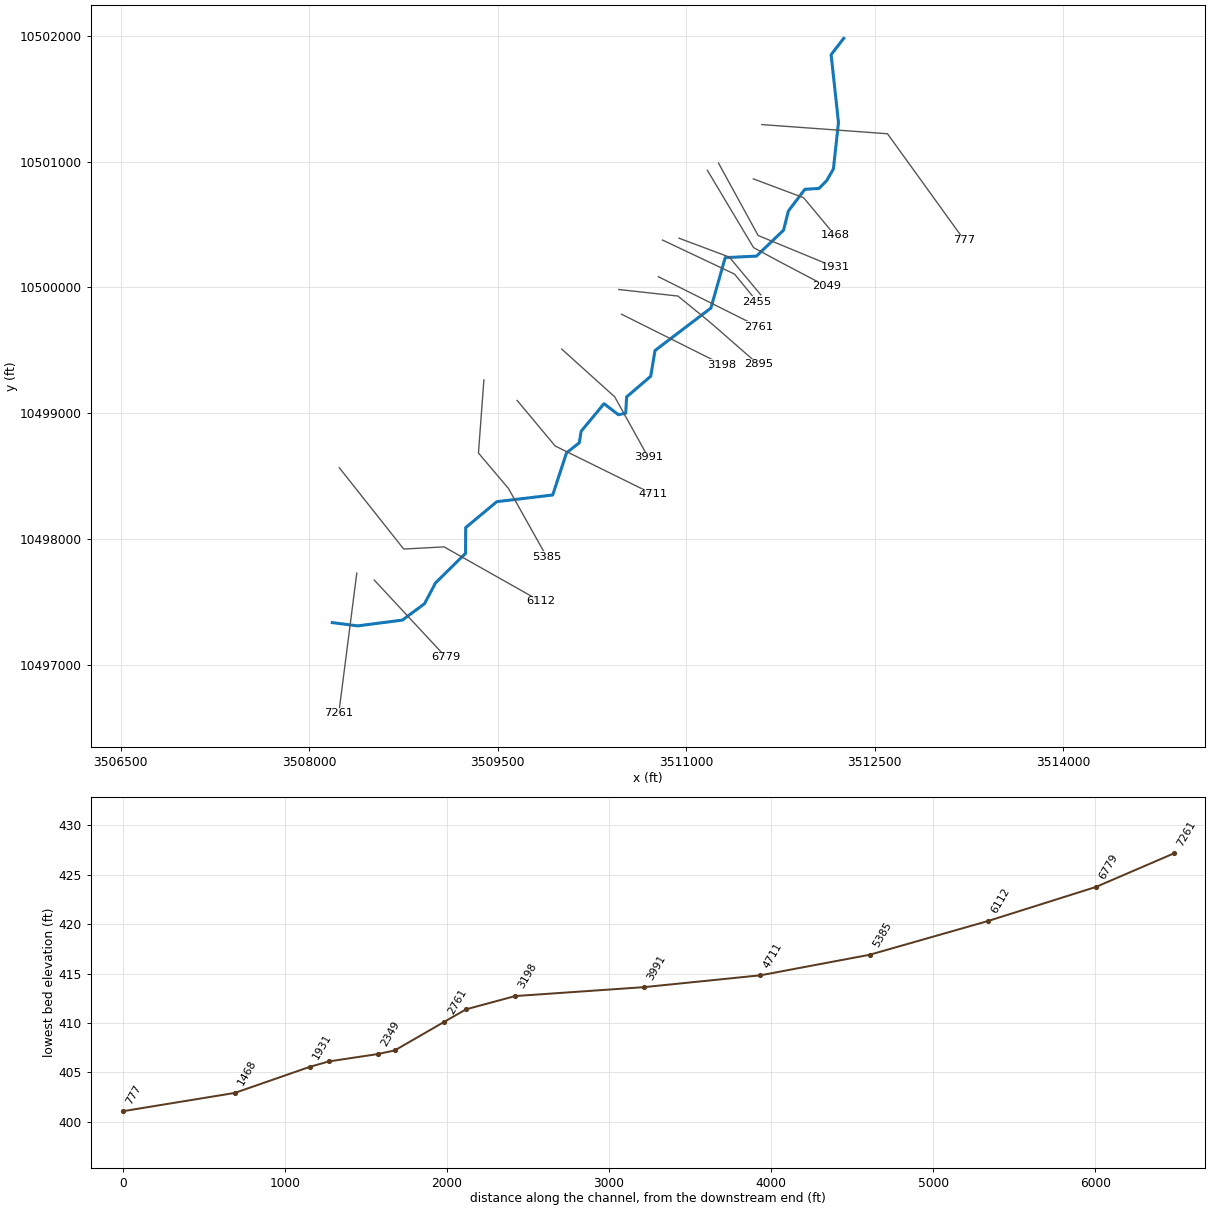
--- UNT0119 IN SAND CR.prj (project) ---

Proj Title=UNT0119 IN SAND CR Base Level Engineering
Current Plan=p01
Default Exp/Contr=0.3,0.1
English Units
Geom File=g01
Flow File=f01
Plan File=p01
BEGIN DESCRIPTION:
UNT0119 IN SAND CR
END DESCRIPTION:

--- UNT0119 IN SAND CR.p01 (plan) ---

Plan Title=Multiple Run
Short Identifier=Multiple
Geom File=g01
Flow File=f01
Subcritical Flow
K Sum by GR= 0
Std Step Tol= 0.01
Critical Tol= 0.01
Num of Std Step Trials= 20
Max Error Tol= 0.3
Flow Tol Ratio= 0.001
Split Flow NTrial= 30
Split Flow Tol= 0.02
Split Flow Ratio= 0.02
Log Output Level= 0
Friction Slope Method= 1
Unsteady Friction Slope Method= 2
Unsteady Bridges Friction Slope Method= 1
Parabolic Critical Depth
Global Vel Dist=  1 , 1 , 1
Global Log Level= 0
CheckData=True
Encroach Param= -1, 0, 0, 0
BEGIN DESCRIPTION:
Multiple Run
END DESCRIPTION:

--- UNT0119 IN SAND CR.f01 (steady flow) ---

Flow Title=Multiple
Number of Profiles=7
Profile Names=10-year,25-year,50-year,1pct_min,100-year,1pct_plu,500-year
River Rch & RM= UNT0119 IN SAND ,Reach-1,7261
    1695    2412    3025    2764    3737    5054    5694
River Rch & RM= UNT0119 IN SAND ,Reach-1,5385
    1959    2796    3513    3213    4345    5876    6636
Boundary for River Rch & Prof#=UNT0119 IN SAND ,Reach-1,1
Up Type=0
Dn Type=3
Dn Slope=0.005
Boundary for River Rch & Prof#=UNT0119 IN SAND ,Reach-1,2
Up Type=0
Dn Type=3
Dn Slope=0.005
Boundary for River Rch & Prof#=UNT0119 IN SAND ,Reach-1,3
Up Type=0
Dn Type=3
Dn Slope=0.005
Boundary for River Rch & Prof#=UNT0119 IN SAND ,Reach-1,4
Up Type=0
Dn Type=3
Dn Slope=0.005
Boundary for River Rch & Prof#=UNT0119 IN SAND ,Reach-1,5
Up Type=0
Dn Type=3
Dn Slope=0.005
Boundary for River Rch & Prof#=UNT0119 IN SAND ,Reach-1,6
Up Type=0
Dn Type=3
Dn Slope=0.005
Boundary for River Rch & Prof#=UNT0119 IN SAND ,Reach-1,7
Up Type=0
Dn Type=3
Dn Slope=0.005

--- UNT0119 IN SAND CR.g01 (geometry) ---

Geom Title=Existing Conditions

River Reach=UNT0119 IN SAND ,Reach-1
Reach XY= 30
      3508184.20     10497333.88      3508385.83     10497307.85
      3508741.22     10497353.78      3508917.26     10497483.59
      3509004.63     10497648.91      3509244.15     10497885.19
      3509245.07     10498089.67      3509492.96     10498295.93
      3509937.35     10498349.09      3510047.31     10498684.24
      3510148.78     10498764.75      3510163.48     10498855.90
      3510345.40     10499075.41      3510459.56     10498987.63
      3510518.15     10498999.32      3510525.54     10499129.36
      3510717.21     10499293.72      3510751.30     10499498.35
      3511195.92     10499836.20      3511309.52     10500237.16
      3511558.31     10500249.31      3511773.79     10500455.90
      3511812.16     10500607.82      3511942.99     10500780.52
      3512055.98     10500788.05      3512116.29     10500849.20
      3512170.38     10500943.26      3512210.56     10501312.28
      3512152.11     10501851.64      3512252.11     10501981.64

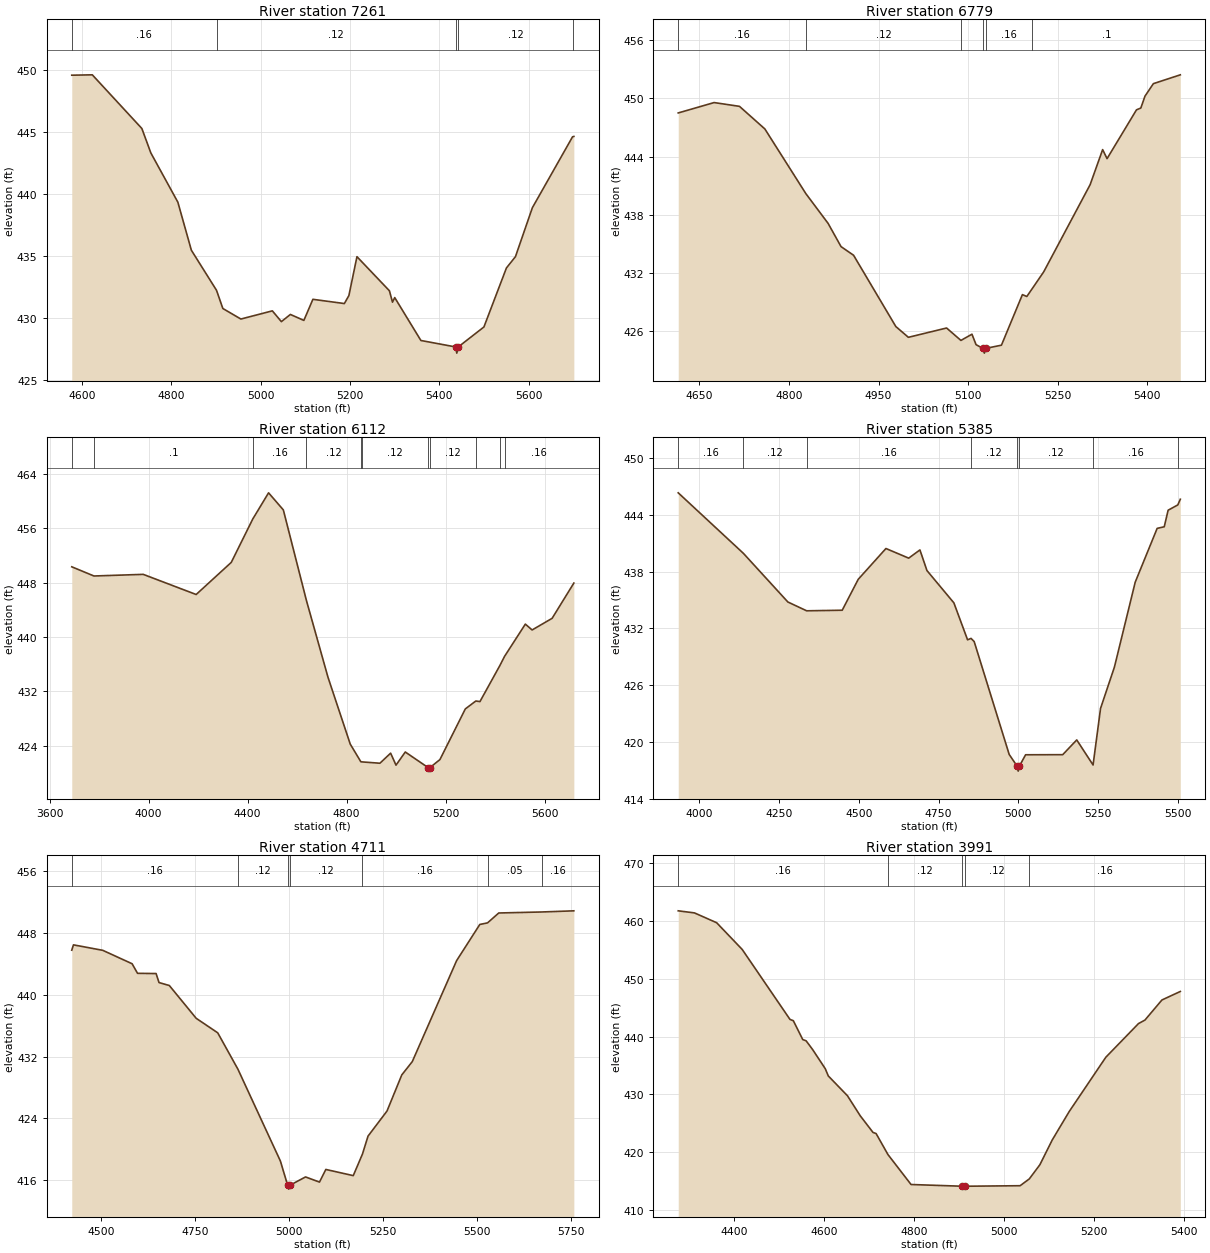
Type RM Length L Ch R = 1,7261,482,482,482
BEGIN DESCRIPTION:
UNT0119 IN SAND CR 14.1
END DESCRIPTION:
XS GIS Cut Line= 2
      3508378.84     10497727.32      3508235.61     10496611.87
#Sta/Elev= 30
  4576.8  449.57  4622.8  449.60  4733.8  445.27  4753.9  443.30  4814.4  439.33
  4844.7  435.45  4901.0  432.22  4915.2  430.75  4955.6  429.90  5026.1  430.56
  5046.3  429.69  5066.5  430.27  5096.7  429.79  5116.9  431.49  5187.4  431.15
  5197.5  431.79  5215.6  434.93  5288.3  432.18  5295.2  431.26  5300.2  431.63
  5358.8  428.17  5436.5  427.65  5439.2  427.15  5442.5  427.65  5500.0  429.26
  5550.4  434.02  5570.6  434.93  5608.5  438.88  5698.5  444.60  5701.4  444.63
#Mann=5,-1,0
  4576.8    0.16       0  4901.0    0.12       0  5436.5    0.07       0
  5442.5    0.12       0  5698.5    0.05       0
Bank Sta=5436.5,5442.5
Exp/Cntr=0.3,0.1

Type RM Length L Ch R = 1,6779,667,667,667
BEGIN DESCRIPTION:
UNT0119 IN SAND CR 14.0
END DESCRIPTION:
XS GIS Cut Line= 2
      3508517.74     10497672.33      3509090.33     10497056.36
#Sta/Elev= 30
  4614.4  448.51  4674.5  449.58  4717.0  449.19  4759.5  446.86  4828.2  440.19
  4865.5  437.12  4887.1  434.73  4908.1  433.84  4978.9  426.49  4999.9  425.38
  5063.9  426.34  5087.9  425.06  5106.4  425.70  5113.3  424.62  5124.4  424.25
  5127.2  423.75  5130.4  424.25  5155.8  424.57  5190.9  429.78  5198.3  429.59
  5207.6  430.42  5226.6  432.13  5304.3  441.11  5325.3  444.73  5332.7  443.80
  5382.0  448.83  5389.3  449.02  5396.2  450.24  5410.3  451.53  5455.4  452.44
#Mann=6,-1,0
  4614.4    0.16       0  4828.2    0.12       0  5087.9    0.16       0
  5124.4    0.07       0  5130.4    0.16       0  5207.6     0.1       0
Bank Sta=5124.4,5130.4
Exp/Cntr=0.3,0.1

Type RM Length L Ch R = 1,6112,727,727,727
BEGIN DESCRIPTION:
UNT0119 IN SAND CR 12.0
END DESCRIPTION:
XS GIS Cut Line= 4
      3508239.93     10498565.73      3508752.10     10497919.02
      3509073.28     10497936.38      3509841.54     10497502.33
#Sta/Elev= 30
  3689.5  450.32  3779.2  448.97  3978.3  449.21  4192.2  446.25  4334.1  450.97
  4420.8  457.33  4484.8  461.19  4544.5  458.68  4637.9  445.36  4724.8  434.11
  4814.9  424.27  4857.7  421.68  4860.6  421.66  4934.8  421.46  4978.1  422.94
  4999.8  421.18  5037.3  423.11  5130.4  420.80  5133.1  420.30  5136.4  420.80
  5177.4  422.00  5279.9  429.44  5322.3  430.60  5339.1  430.52  5419.8  435.83
  5438.5  437.16  5522.5  441.90  5549.9  441.04  5630.7  442.75  5718.5  447.93
#Mann=11,-1,0
  3689.5    0.16       0  3779.2     0.1       0  4420.8    0.16       0
  4637.9    0.12       0  4857.7    0.05       0  4860.6    0.12       0
  5130.4    0.07       0  5136.4    0.12       0  5322.3    0.16       0
  5419.8    0.05       0  5438.5    0.16       0
Bank Sta=5130.4,5136.4
Exp/Cntr=0.3,0.1

Type RM Length L Ch R = 1,5385,674,674,674
BEGIN DESCRIPTION:
UNT0119 IN SAND CR 11.0
END DESCRIPTION:
XS GIS Cut Line= 4
      3509390.12     10499264.54      3509346.72     10498682.90
      3509585.43     10498400.79      3509889.24     10497858.28
#Sta/Elev= 30
  3933.7  446.34  4138.0  439.94  4277.6  434.79  4336.4  433.86  4448.0  433.92
  4498.2  437.19  4585.1  440.45  4656.5  439.43  4691.7  440.30  4713.7  438.12
  4798.2  434.70  4841.1  430.79  4852.1  430.94  4861.9  430.60  4971.7  418.66
  4997.1  417.40  4999.9  416.90  5003.1  417.40  5023.1  418.63  5139.5  418.64
  5183.5  420.20  5234.7  417.55  5258.2  423.54  5301.6  427.90  5366.9  436.89
  5435.7  442.58  5457.9  442.75  5470.1  444.50  5500.4  445.06  5508.3  445.66
#Mann=8,-1,0
  3933.7    0.16       0  4138.0    0.12       0  4336.4    0.16       0
  4852.1    0.12       0  4997.1    0.07       0  5003.1    0.12       0
  5234.7    0.16       0  5500.4    0.05       0
Bank Sta=4997.1,5003.1
Exp/Cntr=0.3,0.1

Type RM Length L Ch R = 1,4711,720,720,720
BEGIN DESCRIPTION:
UNT0119 IN SAND CR 9.0
END DESCRIPTION:
XS GIS Cut Line= 3
      3509654.90     10499100.83      3509956.97     10498738.87
      3510732.40     10498356.36
#Sta/Elev= 30
  4422.4  445.79  4426.9  446.48  4504.9  445.77  4583.0  444.03  4597.4  442.79
  4646.8  442.76  4654.6  441.59  4682.0  441.21  4753.5  436.96  4810.8  435.08
  4864.6  430.36  4977.6  418.46  4996.9  415.32  4999.7  414.82  5002.9  415.32
  5044.5  416.40  5081.6  415.73  5098.5  417.37  5171.5  416.57  5196.0  419.37
  5210.8  421.69  5261.3  424.94  5300.6  429.62  5328.6  431.35  5446.5  444.43
  5508.2  449.12  5528.9  449.33  5558.7  450.61  5672.6  450.74  5758.5  450.89
#Mann=7,-1,0
  4422.4    0.16       0  4864.6    0.12       0  4996.9    0.07       0
  5002.9    0.12       0  5196.0    0.16       0  5528.9    0.05       0
  5672.6    0.16       0
Bank Sta=4996.9,5002.9
Exp/Cntr=0.3,0.1

Type RM Length L Ch R = 1,3991,793,793,793
BEGIN DESCRIPTION:
UNT0119 IN SAND CR 7.0
END DESCRIPTION:
XS GIS Cut Line= 3
      3510009.06     10499509.69      3510430.93     10499129.50
      3510696.56     10498650.31
#Sta/Elev= 30
  4276.0  461.79  4312.1  461.43  4361.4  459.73  4418.2  455.10  4524.3  443.00
  4531.8  442.77  4552.7  439.51  4560.2  439.29  4574.4  437.81  4602.8  434.46
  4609.5  433.21  4652.1  429.78  4680.5  426.31  4708.9  423.43  4715.7  423.24
  4742.2  419.59  4793.4  414.42  4907.1  414.12  4909.8  413.62  4913.1  414.12
  5035.8  414.21  5056.2  415.39  5079.7  417.84  5107.2  422.13  5144.9  427.05
  5226.2  436.44  5298.8  442.27  5313.2  442.88  5351.0  446.36  5391.8  447.83
#Mann=5,-1,0
  4276.0    0.16       0  4742.2    0.12       0  4907.1    0.07       0
  4913.1    0.12       0  5056.2    0.16       0
Bank Sta=4907.1,4913.1
Exp/Cntr=0.3,0.1

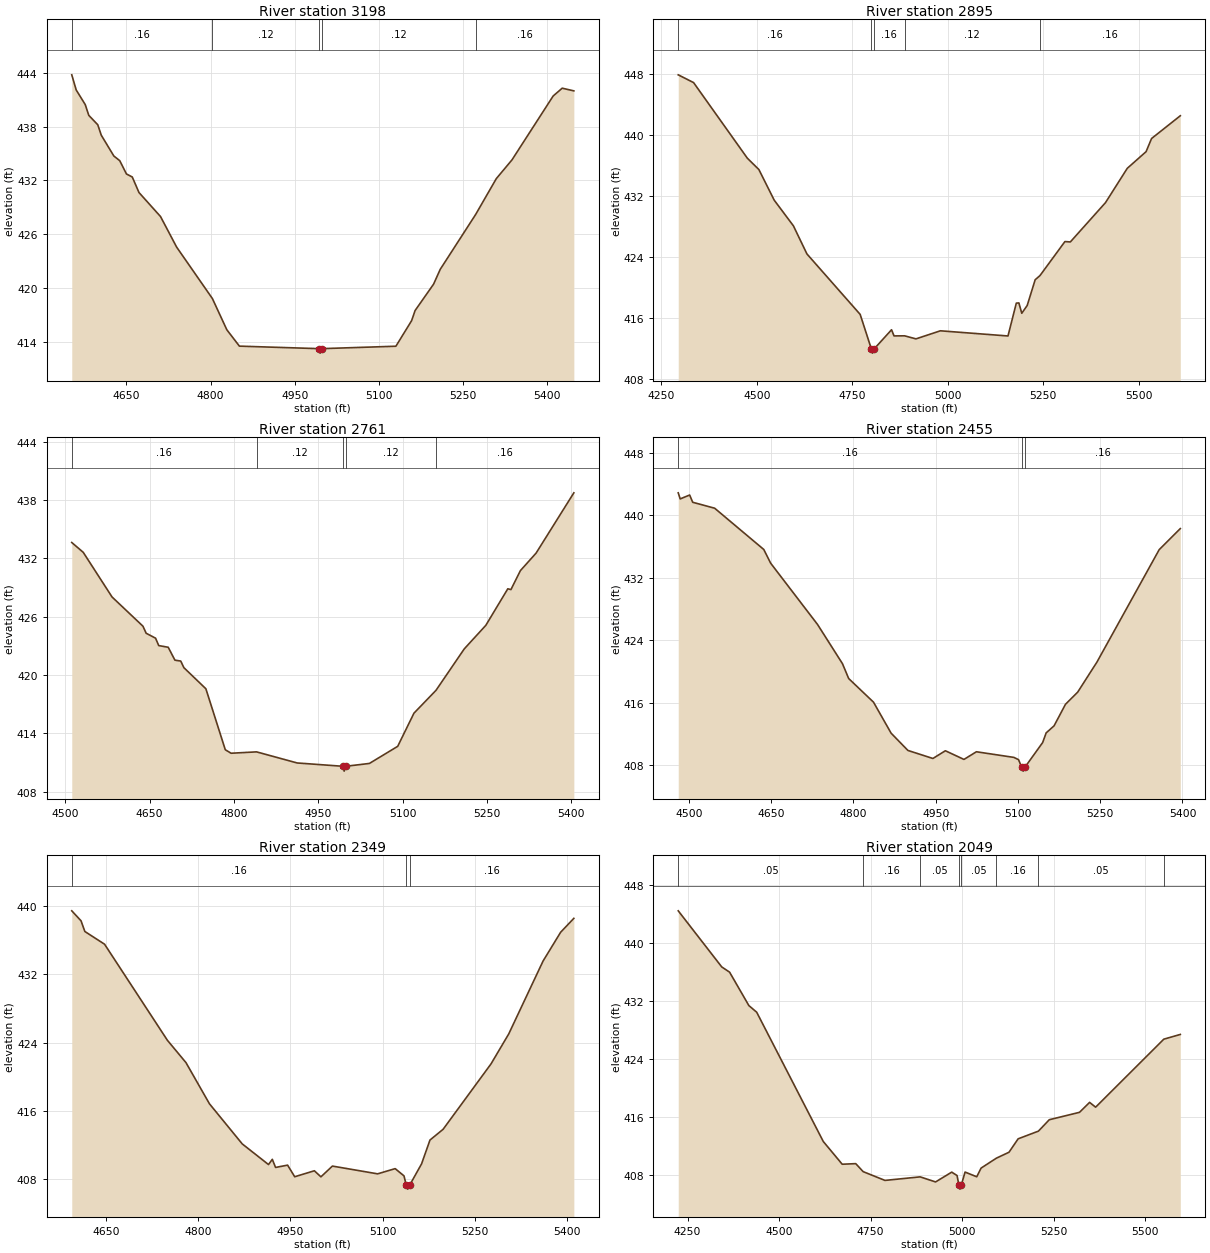
Type RM Length L Ch R = 1,3198,303,303,303
BEGIN DESCRIPTION:
UNT0119 IN SAND CR 6.2
END DESCRIPTION:
XS GIS Cut Line= 3
      3510485.03     10499787.05      3510885.02     10499587.06
      3511285.01     10499387.06
#Sta/Elev= 30
  4552.8  443.77  4560.7  442.08  4576.8  440.45  4583.1  439.25  4599.1  438.20
  4605.4  437.03  4627.8  434.71  4638.3  434.19  4650.2  432.71  4660.6  432.37
  4672.5  430.64  4710.9  427.96  4739.6  424.55  4803.3  418.81  4829.0  415.33
  4851.4  413.50  4992.6  413.22  4995.3  412.72  4998.6  413.22  5130.2  413.49
  5158.2  416.34  5164.4  417.47  5197.3  420.41  5209.2  422.07  5272.2  428.18
  5309.1  432.19  5337.0  434.28  5410.4  441.41  5426.5  442.28  5447.2  441.98
#Mann=5,-1,0
  4552.8    0.16       0  4803.3    0.12       0  4992.6    0.07       0
  4998.6    0.12       0  5272.2    0.16       0
Bank Sta=4992.6,4998.6
Exp/Cntr=0.3,0.1

Type RM Length L Ch R = 1,2895,134,134,134
BEGIN DESCRIPTION:
UNT0119 IN SAND CR 6.1
END DESCRIPTION:
XS GIS Cut Line= 4
      3510462.18     10499983.66      3510933.53     10499931.58
      3511188.74     10499723.25      3511574.13     10499387.33
#Sta/Elev= 30
  4294.2  447.90  4334.4  446.88  4475.2  436.96  4505.4  435.47  4545.6  431.45
  4595.9  428.08  4631.2  424.40  4770.7  416.46  4800.3  411.88  4803.1  411.38
  4806.3  411.88  4852.9  414.45  4859.3  413.64  4887.0  413.65  4916.8  413.25
  4980.7  414.31  5157.8  413.63  5179.6  417.94  5186.3  417.97  5193.9  416.61
  5208.1  417.63  5229.0  421.01  5241.5  421.55  5306.9  426.02  5321.1  425.97
  5413.2  431.13  5470.2  435.63  5519.5  437.82  5533.8  439.54  5609.1  442.53
#Mann=5,-1,0
  4294.2    0.16       0  4800.3    0.07       0  4806.3    0.16       0
  4887.0    0.12       0  5241.5    0.16       0
Bank Sta=4800.3,4806.3
Exp/Cntr=0.3,0.1

Type RM Length L Ch R = 1,2761,306,306,306
BEGIN DESCRIPTION:
UNT0119 IN SAND CR 6.0
END DESCRIPTION:
XS GIS Cut Line= 3
      3510778.06     10500085.38      3511178.04     10499885.39
      3511576.34     10499686.25
#Sta/Elev= 30
  4511.8  433.63  4532.2  432.62  4583.4  428.03  4638.4  425.02  4644.0  424.30
  4660.8  423.79  4666.4  423.03  4683.2  422.86  4695.2  421.53  4705.5  421.44
  4711.1  420.76  4750.2  418.59  4784.7  412.32  4795.0  411.96  4840.3  412.10
  4912.4  410.96  4993.2  410.62  4996.0  410.12  4999.2  410.62  5040.9  410.91
  5091.2  412.67  5120.1  416.08  5159.3  418.43  5209.5  422.69  5247.8  425.11
  5286.9  428.87  5292.5  428.79  5309.3  430.74  5337.2  432.54  5404.3  438.74
#Mann=5,-1,0
  4511.8    0.16       0  4840.3    0.12       0  4993.2    0.07       0
  4999.2    0.12       0  5159.3    0.16       0
Bank Sta=4993.2,4999.2
Exp/Cntr=0.3,0.1

Type RM Length L Ch R = 1,2455,106,106,106
BEGIN DESCRIPTION:
UNT0119 IN SAND CR 5.0
END DESCRIPTION:
XS GIS Cut Line= 3
      3510811.11     10500376.90      3511384.05     10500106.06
      3511562.38     10499887.90
#Sta/Elev= 30
  4480.6  442.87  4484.2  442.09  4501.4  442.59  4507.0  441.66  4547.0  440.90
  4636.6  435.61  4649.1  433.86  4734.6  426.01  4780.1  420.98  4791.4  419.08
  4836.7  416.05  4868.8  412.08  4899.4  409.87  4945.0  408.84  4967.7  409.83
  5001.6  408.72  5024.3  409.70  5092.6  408.98  5101.1  408.69  5106.8  407.72
  5109.6  407.22  5112.8  407.72  5145.1  410.88  5151.5  412.12  5165.9  413.02
  5186.7  415.78  5209.0  417.34  5244.1  421.19  5357.6  435.59  5396.1  438.29
#Mann=3,-1,0
  4480.6    0.16       0  5106.8    0.07       0  5112.8    0.16       0
Bank Sta=5106.8,5112.8
Exp/Cntr=0.3,0.1

Type RM Length L Ch R = 1,2349,300,300,300
BEGIN DESCRIPTION:
UNT0119 IN SAND CR 4.0
END DESCRIPTION:
XS GIS Cut Line= 3
      3510942.14     10500391.63      3511342.11     10500241.64
      3511592.12     10499941.62
#Sta/Elev= 30
  4593.8  439.45  4608.9  438.28  4615.1  437.03  4647.2  435.54  4749.5  424.29
  4779.8  421.67  4818.0  416.85  4871.4  412.15  4914.2  409.73  4920.4  410.34
  4925.7  409.39  4945.3  409.66  4956.9  408.30  4988.9  409.00  4999.6  408.29
  5018.3  409.55  5091.9  408.64  5120.5  409.25  5134.9  408.40  5138.4  407.35
  5141.1  406.85  5144.4  407.35  5163.5  409.81  5177.2  412.60  5198.6  413.86
  5276.7  421.53  5305.4  425.02  5361.4  433.57  5390.0  436.94  5411.5  438.57
#Mann=3,-1,0
  4593.8    0.16       0  5138.4    0.07       0  5144.4    0.16       0
Bank Sta=5138.4,5144.4
Exp/Cntr=0.3,0.1

Type RM Length L Ch R = 1,2049,118,118,118
BEGIN DESCRIPTION:
UNT0119 IN SAND CR 3.0
END DESCRIPTION:
XS GIS Cut Line= 4
      3511167.91     10500931.57      3511535.09     10500317.00
      3511722.59     10500215.43      3512113.19     10500009.72
#Sta/Elev= 30
  4224.7  444.45  4343.5  436.72  4364.9  436.00  4417.5  431.40  4438.9  430.48
  4620.7  412.67  4672.3  409.54  4709.3  409.62  4729.5  408.52  4789.1  407.31
  4885.1  407.80  4927.2  407.10  4971.3  408.45  4985.9  407.98  4991.1  406.61
  4993.8  406.11  4997.1  406.61  5007.7  408.46  5039.6  407.81  5051.5  409.01
  5093.4  410.38  5127.6  411.19  5152.6  413.04  5208.0  414.10  5237.6  415.67
  5320.1  416.69  5347.7  418.06  5364.1  417.40  5550.3  426.77  5595.3  427.42
#Mann=8,-1,0
  4224.7    0.05       0  4729.5    0.16       0  4885.1    0.05       0
  4991.1   0.035       0  4997.1    0.05       0  5093.4    0.16       0
  5208.0    0.05       0  5550.3     0.1       0
Bank Sta=4991.1,4997.1
Exp/Cntr=0.3,0.1

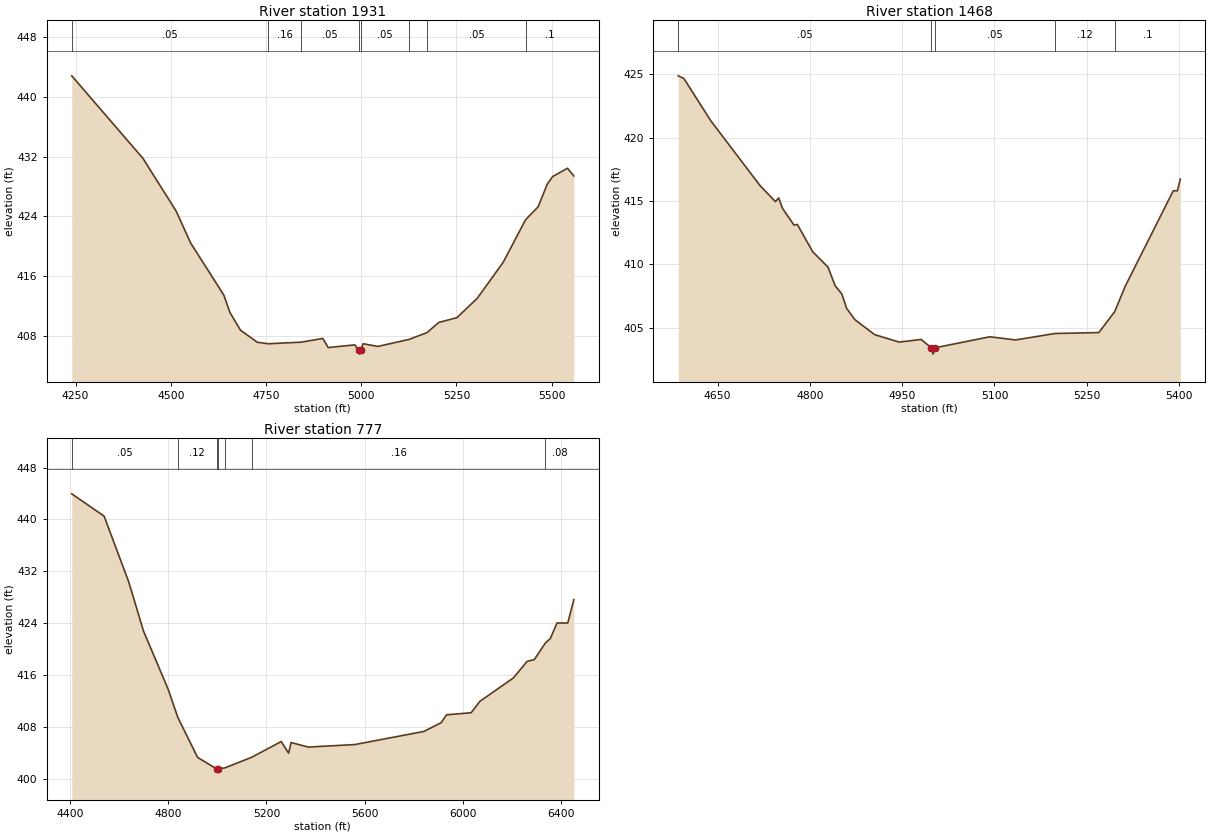
Type RM Length L Ch R = 1,1931,463,463,463
BEGIN DESCRIPTION:
UNT0119 IN SAND CR 5.1
END DESCRIPTION:
XS GIS Cut Line= 3
      3511256.45     10500988.86      3511571.55     10500413.35
      3512183.54     10500160.74
#Sta/Elev= 30
  4240.2  442.84  4427.1  431.78  4514.3  424.72  4552.2  420.46  4639.5  413.46
  4655.6  411.13  4683.1  408.77  4727.3  407.15  4756.1  406.95  4842.2  407.16
  4899.3  407.66  4913.5  406.44  4983.5  406.80  4993.1  406.06  4995.9  405.56
  4999.1  406.06  5005.1  406.95  5044.0  406.59  5126.4  407.54  5173.1  408.45
  5203.7  409.80  5251.6  410.45  5304.8  413.04  5372.9  417.86  5431.6  423.56
  5464.6  425.29  5488.5  428.32  5502.8  429.35  5541.8  430.46  5558.4  429.43
#Mann=8,-1,0
  4240.2    0.05       0  4756.1    0.16       0  4842.2    0.05       0
  4993.1   0.035       0  4999.1    0.05       0  5126.4    0.16       0
  5173.1    0.05       0  5431.6     0.1       0
Bank Sta=4993.1,4999.1
Exp/Cntr=0.3,0.1

Type RM Length L Ch R = 1,1468,691,691,691
BEGIN DESCRIPTION:
UNT0119 IN SAND CR 4.1
END DESCRIPTION:
XS GIS Cut Line= 3
      3511533.36     10500863.62      3511933.34     10500713.63
      3512182.07     10500415.16
#Sta/Elev= 30
  4586.2  424.89  4595.5  424.67  4639.1  421.34  4719.2  416.22  4744.1  414.96
  4749.4  415.25  4755.7  414.42  4774.4  413.10  4779.7  413.16  4804.6  411.01
  4829.5  409.79  4841.2  408.31  4851.9  407.68  4859.8  406.53  4873.2  405.64
  4905.3  404.46  4945.2  403.87  4980.8  404.08  4997.4  403.42  5000.2  402.92
  5003.4  403.42  5092.5  404.29  5134.1  404.04  5198.7  404.55  5269.5  404.62
  5295.4  406.28  5312.4  408.28  5390.5  415.82  5397.1  415.81  5401.9  416.74
#Mann=5,-1,0
  4586.2    0.05       0  4997.4   0.035       0  5003.4    0.05       0
  5198.7    0.12       0  5295.4     0.1       0
Bank Sta=4997.4,5003.4
Exp/Cntr=0.3,0.1

Type RM Length L Ch R = 1,777,0,0,0
BEGIN DESCRIPTION:
UNT0119 IN SAND CR 3.1
END DESCRIPTION:
XS GIS Cut Line= 3
      3511600.56     10501295.61      3512600.57     10501222.70
      3513211.28     10500376.03
#Sta/Elev= 30
  4406.5  443.95  4538.4  440.51  4638.7  430.38  4698.8  422.82  4799.1  413.87
  4838.8  409.50  4919.4  403.34  4996.6  401.57  4999.4  401.07  5002.6  401.57
  5030.3  401.72  5139.6  403.35  5260.3  405.78  5290.4  404.00  5300.4  405.63
  5370.6  404.93  5560.8  405.32  5841.8  407.34  5912.9  408.70  5933.8  409.90
  6034.4  410.22  6070.0  411.97  6206.2  415.57  6262.7  418.13  6292.1  418.42
  6337.3  420.98  6357.1  421.64  6384.5  424.05  6428.3  424.05  6453.1  427.65
#Mann=7,-1,0
  4406.5    0.05       0  4838.8    0.12       0  4996.6    0.07       0
  5002.6    0.12       0  5030.3     0.1       0  5139.6    0.16       0
  6337.3    0.08       0
Bank Sta=4996.6,5002.6
Exp/Cntr=0.3,0.1

Chan Stop Cuts=-1