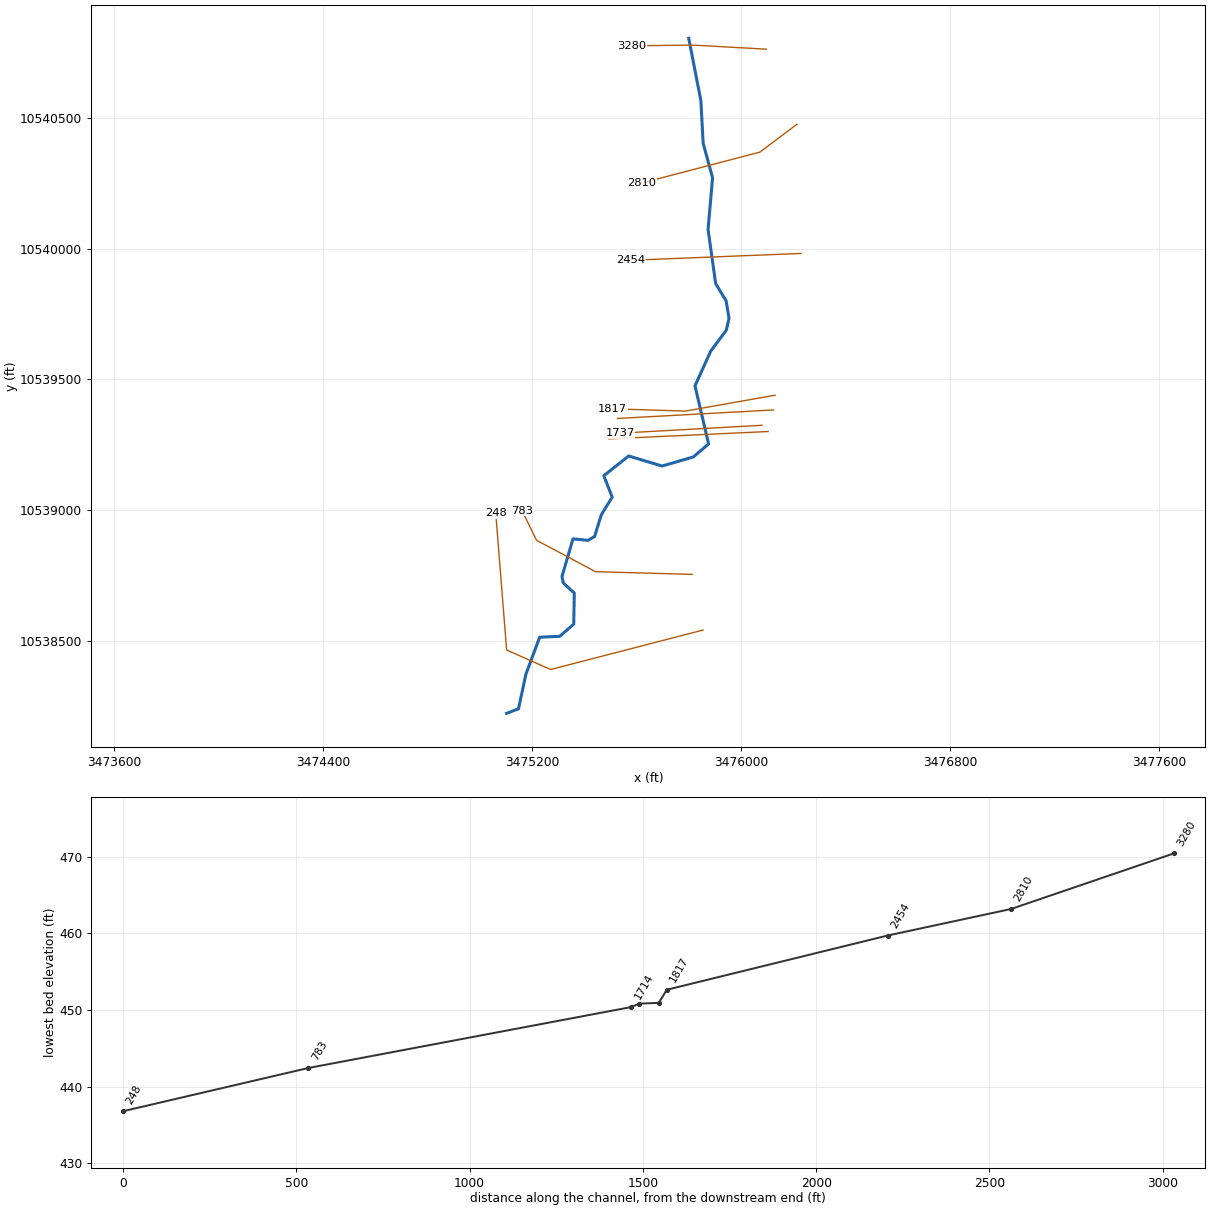
--- UNT01190 IN SAND CR.prj (project) ---

Proj Title=UNT01190 IN SAND CR Base Level Engineering
Current Plan=p01
Default Exp/Contr=0.3,0.1
English Units
Geom File=g01
Flow File=f01
Plan File=p01
BEGIN DESCRIPTION:
UNT01190 IN SAND CR
END DESCRIPTION:

--- UNT01190 IN SAND CR.p01 (plan) ---

Plan Title=Multiple Run
Short Identifier=Multiple
Geom File=g01
Flow File=f01
Subcritical Flow
K Sum by GR= 0
Std Step Tol= 0.01
Critical Tol= 0.01
Num of Std Step Trials= 20
Max Error Tol= 0.3
Flow Tol Ratio= 0.001
Split Flow NTrial= 30
Split Flow Tol= 0.02
Split Flow Ratio= 0.02
Log Output Level= 0
Friction Slope Method= 1
Unsteady Friction Slope Method= 2
Unsteady Bridges Friction Slope Method= 1
Parabolic Critical Depth
Global Vel Dist=  1 , 1 , 1
Global Log Level= 0
CheckData=True
Encroach Param= -1, 0, 0, 0
BEGIN DESCRIPTION:
Multiple Run
END DESCRIPTION:

--- UNT01190 IN SAND CR.f01 (steady flow) ---

Flow Title=Multiple
Number of Profiles=7
Profile Names=10-year,25-year,50-year,1pct_min,100-year,1pct_plu,500-year
River Rch & RM= UNT01190 IN SAND,Reach-1,3280
     226     280     321     270     366     495     470
Boundary for River Rch & Prof#=UNT01190 IN SAND,Reach-1,1
Up Type=0
Dn Type=3
Dn Slope=0.005
Boundary for River Rch & Prof#=UNT01190 IN SAND,Reach-1,2
Up Type=0
Dn Type=3
Dn Slope=0.005
Boundary for River Rch & Prof#=UNT01190 IN SAND,Reach-1,3
Up Type=0
Dn Type=3
Dn Slope=0.005
Boundary for River Rch & Prof#=UNT01190 IN SAND,Reach-1,4
Up Type=0
Dn Type=3
Dn Slope=0.005
Boundary for River Rch & Prof#=UNT01190 IN SAND,Reach-1,5
Up Type=0
Dn Type=3
Dn Slope=0.005
Boundary for River Rch & Prof#=UNT01190 IN SAND,Reach-1,6
Up Type=0
Dn Type=3
Dn Slope=0.005
Boundary for River Rch & Prof#=UNT01190 IN SAND,Reach-1,7
Up Type=0
Dn Type=3
Dn Slope=0.005

--- UNT01190 IN SAND CR.g01 (geometry) ---

Geom Title=Existing Conditions

River Reach=UNT01190 IN SAND,Reach-1
Reach XY= 30
      3475798.73     10540804.62      3475845.14     10540566.86
      3475854.00     10540402.80      3475889.94     10540271.03
      3475872.75     10540072.59      3475901.91     10539865.82
      3475942.02     10539799.67      3475952.96     10539733.01
      3475942.54     10539687.70      3475883.16     10539608.01
      3475822.70     10539474.94      3475874.79     10539252.50
      3475816.19     10539202.58      3475696.84     10539167.86
      3475568.91     10539206.40      3475473.74     10539130.74
      3475505.90     10539049.17      3475464.04     10538980.85
      3475438.45     10538898.05      3475413.18     10538883.52
      3475355.90     10538889.36      3475313.85     10538745.61
      3475318.36     10538721.00      3475360.80     10538681.60
      3475358.68     10538562.82      3475305.15     10538516.31
      3475228.33     10538512.89      3475175.40     10538370.32
      3475147.39     10538239.05      3475101.81     10538221.41

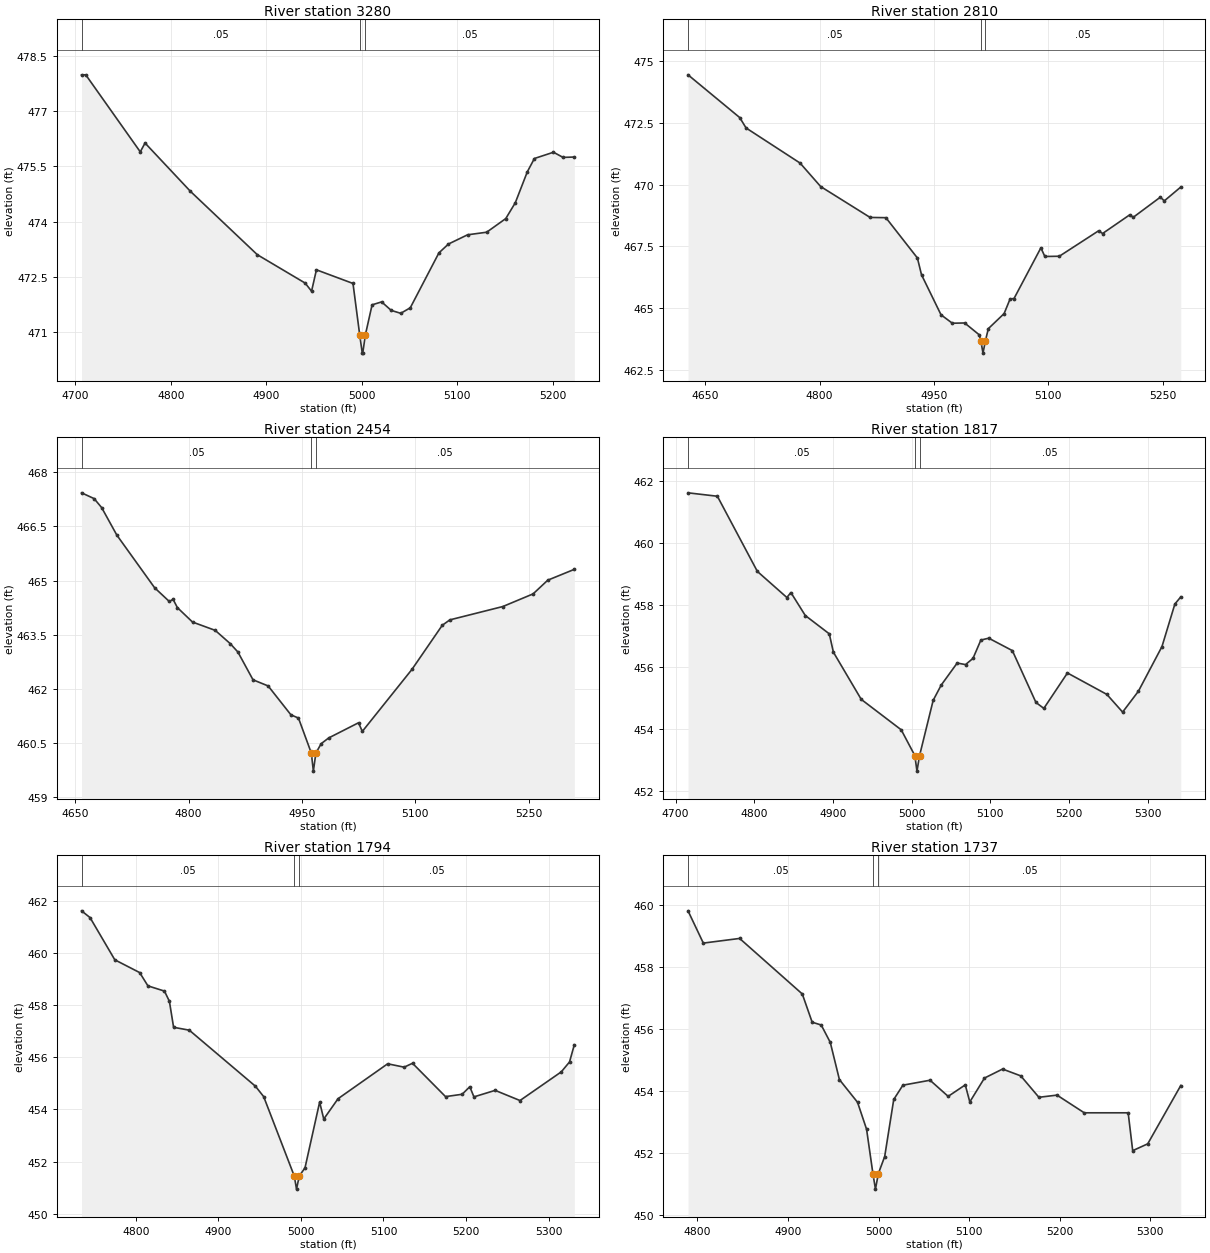
Type RM Length L Ch R = 1,3280,470,470,470
BEGIN DESCRIPTION:
UNT01190 IN SAND CR 6.0
END DESCRIPTION:
XS GIS Cut Line= 3
      3476095.94     10540763.05      3475817.28     10540778.68
      3475580.29     10540776.08
#Sta/Elev= 30
  4706.5  477.98  4710.9  477.98  4768.0  475.89  4773.0  476.13  4820.5  474.82
  4890.6  473.10  4940.7  472.33  4947.4  472.11  4952.5  472.69  4990.8  472.32
  4997.8  470.93  5000.5  470.43  5001.0  470.43  5003.8  470.93  5010.8  471.74
  5020.8  471.82  5030.8  471.59  5040.8  471.51  5050.8  471.66  5080.8  473.15
  5090.8  473.39  5110.8  473.64  5130.8  473.71  5150.8  474.08  5160.8  474.51
  5173.4  475.35  5180.8  475.71  5200.8  475.88  5210.8  475.74  5222.6  475.75
#Mann=3,-1,0
  4706.5    0.05       0  4997.8    0.04       0  5003.8    0.05       0
Bank Sta=4997.8,5003.8
Exp/Cntr=0.3,0.1

Type RM Length L Ch R = 1,2810,356,356,356
BEGIN DESCRIPTION:
UNT01190 IN SAND CR 6.1
END DESCRIPTION:
XS GIS Cut Line= 3
      3476213.13     10540475.96      3476071.19     10540369.18
      3475618.05     10540250.68
#Sta/Elev= 30
  4627.5  474.44  4695.3  472.71  4703.6  472.29  4774.4  470.87  4801.4  469.92
  4866.2  468.67  4886.9  468.66  4928.2  467.03  4933.6  466.35  4959.2  464.73
  4974.0  464.39  4990.2  464.40  5009.3  463.92  5011.4  463.68  5014.2  463.18
  5017.4  463.68  5021.2  464.17  5041.9  464.78  5049.7  465.37  5054.9  465.39
  5090.1  467.44  5095.3  467.09  5114.3  467.10  5165.8  468.13  5171.0  468.02
  5206.3  468.77  5211.4  468.68  5246.7  469.49  5251.9  469.34  5273.5  469.90
#Mann=3,-1,0
  4627.5    0.05       0  5011.4   0.035       0  5017.4    0.05       0
Bank Sta=5011.4,5017.4
Exp/Cntr=0.3,0.1

Type RM Length L Ch R = 1,2454,637,637,637
BEGIN DESCRIPTION:
UNT01190 IN SAND CR 5.0
END DESCRIPTION:
XS GIS Cut Line= 2
      3476228.66     10539981.45      3475577.68     10539955.41
#Sta/Elev= 30
  4658.6  467.43  4675.2  467.27  4685.2  467.02  4705.2  466.26  4755.2  464.80
  4774.6  464.42  4779.6  464.48  4785.3  464.25  4805.3  463.85  4835.3  463.62
  4855.3  463.25  4865.3  463.02  4885.3  462.25  4905.3  462.08  4935.4  461.28
  4945.4  461.19  4962.4  460.22  4965.1  459.72  4968.4  460.22  4975.4  460.48
  4985.4  460.64  5024.8  461.06  5029.8  460.82  5095.5  462.54  5135.5  463.76
  5145.5  463.91  5215.6  464.28  5255.6  464.63  5275.0  465.01  5310.1  465.31
#Mann=3,-1,0
  4658.6    0.05       0  4962.4   0.035       0  4968.4    0.05       0
Bank Sta=4962.4,4968.4
Exp/Cntr=0.3,0.1

Type RM Length L Ch R = 1,1817,23,23,23
BEGIN DESCRIPTION:
UNT01190 IN SAND CR 3.3
END DESCRIPTION:
XS GIS Cut Line= 3
      3476128.83     10539438.91      3475785.99     10539378.15
      3475508.21     10539386.84
#Sta/Elev= 30
  4715.9  461.61  4753.2  461.50  4804.0  459.08  4841.5  458.24  4846.6  458.40
  4864.9  457.66  4895.4  457.07  4900.6  456.48  4936.0  454.96  4986.8  453.98
  5004.1  453.15  5006.8  452.65  5010.1  453.15  5027.4  454.93  5037.6  455.42
  5057.9  456.13  5068.5  456.08  5078.0  456.28  5088.0  456.87  5098.0  456.93
  5128.0  456.53  5158.0  454.86  5168.0  454.67  5198.0  455.81  5248.1  455.12
  5268.1  454.55  5288.1  455.22  5318.1  456.66  5334.5  458.03  5342.0  458.26
#Mann=3,-1,0
  4715.9    0.05       0  5004.1   0.035       0  5010.1    0.05       0
Bank Sta=5004.1,5010.1
Exp/Cntr=0.3,0.1

Type RM Length L Ch R = 1,1794,57,57,57
BEGIN DESCRIPTION:
UNT01190 IN SAND CR 3.2
END DESCRIPTION:
XS GIS Cut Line= 2
      3476122.37     10539382.50      3475526.36     10539349.99
#Sta/Elev= 30
  4734.3  461.62  4744.6  461.36  4774.6  459.74  4804.7  459.25  4814.7  458.74
  4834.7  458.54  4840.7  458.15  4845.8  457.15  4864.8  457.04  4944.9  454.89
  4954.9  454.49  4992.0  451.44  4994.7  450.94  4998.0  451.44  5005.0  451.76
  5022.7  454.28  5027.7  453.63  5045.0  454.41  5105.1  455.75  5125.1  455.62
  5135.2  455.77  5175.2  454.49  5195.3  454.58  5204.6  454.87  5209.6  454.48
  5235.3  454.73  5265.4  454.34  5315.4  455.44  5325.4  455.82  5331.2  456.48
#Mann=3,-1,0
  4734.3    0.05       0  4992.0   0.035       0  4998.0    0.05       0
Bank Sta=4992,4998
Exp/Cntr=0.3,0.1

Type RM Length L Ch R = 1,1737,23,23,23
BEGIN DESCRIPTION:
UNT01190 IN SAND CR 3.0
END DESCRIPTION:
XS GIS Cut Line= 2
      3476079.00     10539323.90      3475535.64     10539293.60
#Sta/Elev= 30
  4789.6  459.81  4806.5  458.77  4846.6  458.92  4915.8  457.13  4926.7  456.22
  4936.7  456.13  4946.7  455.57  4956.8  454.37  4976.8  453.64  4986.8  452.77
  4993.8  451.34  4996.6  450.84  4999.8  451.34  5006.8  451.89  5016.8  453.73
  5026.9  454.19  5056.9  454.35  5076.9  453.83  5095.8  454.20  5100.8  453.65
  5117.0  454.42  5137.0  454.71  5157.1  454.49  5177.1  453.80  5197.1  453.87
  5227.2  453.30  5275.7  453.30  5280.7  452.08  5297.3  452.30  5333.8  454.18
#Mann=3,-1,0
  4789.6    0.05       0  4993.8   0.035       0  4999.8    0.05       0
Bank Sta=4993.8,4999.8
Exp/Cntr=0.3,0.1

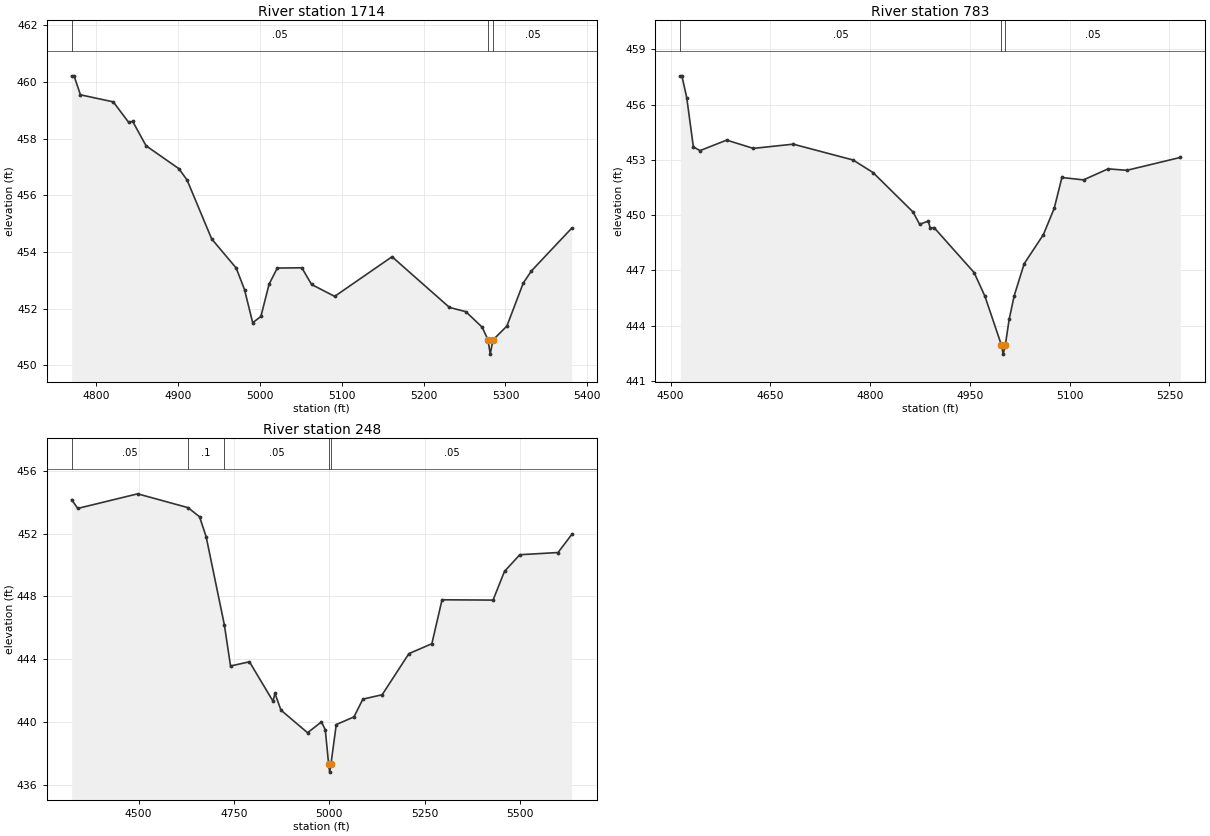
Type RM Length L Ch R = 1,1714,931,931,931
BEGIN DESCRIPTION:
UNT01190 IN SAND CR 3.1
END DESCRIPTION:
XS GIS Cut Line= 2
      3476102.83     10539300.03      3475492.99     10539271.82
#Sta/Elev= 30
  4770.4  460.22  4773.3  460.22  4781.1  459.55  4821.2  459.30  4839.9  458.58
  4844.9  458.61  4861.2  457.75  4901.3  456.94  4911.3  456.54  4941.3  454.46
  4971.3  453.43  4981.4  452.67  4991.4  451.50  5001.4  451.72  5011.4  452.86
  5021.4  453.43  5051.4  453.44  5063.3  452.85  5091.5  452.43  5161.5  453.83
  5231.6  452.04  5251.6  451.89  5271.6  451.34  5278.7  450.89  5281.4  450.39
  5284.7  450.89  5301.7  451.38  5321.7  452.90  5331.7  453.33  5380.9  454.84
#Mann=3,-1,0
  4770.4    0.05       0  5278.7   0.035       0  5284.7    0.05       0
Bank Sta=5278.7,5284.7
Exp/Cntr=0.3,0.1

Type RM Length L Ch R = 1,783,535,535,535
BEGIN DESCRIPTION:
UNT01190 IN SAND CR 1.0
END DESCRIPTION:
XS GIS Cut Line= 4
      3475811.74     10538753.25      3475441.98     10538763.67
      3475216.16     10538883.86      3475161.06     10538997.37
#Sta/Elev= 30
  4514.6  457.56  4516.9  457.56  4524.2  456.38  4534.2  453.70  4544.2  453.50
  4584.3  454.07  4624.3  453.62  4684.3  453.85  4774.3  452.99  4804.3  452.31
  4864.4  450.17  4874.4  449.50  4887.3  449.67  4890.4  449.29  4896.1  449.32
  4956.3  446.88  4972.6  445.59  4997.3  442.95  5000.0  442.45  5003.3  442.95
  5009.0  444.34  5016.6  445.62  5031.6  447.36  5060.5  448.94  5076.8  450.37
  5088.3  452.04  5120.8  451.91  5157.8  452.51  5185.9  452.43  5266.5  453.13
#Mann=3,-1,0
  4514.6    0.05       0  4997.3   0.035       0  5003.3    0.05       0
Bank Sta=4997.3,5003.3
Exp/Cntr=0.3,0.1

Type RM Length L Ch R = 1,248,0,0,0
BEGIN DESCRIPTION:
UNT01190 IN SAND CR 1.01
END DESCRIPTION:
XS GIS Cut Line= 4
      3475853.64     10538540.31      3475270.29     10538389.27
      3475101.89     10538463.92      3475060.28     10538987.48
#Sta/Elev= 30
  4324.3  454.17  4340.2  453.61  4497.4  454.54  4629.5  453.66  4659.8  453.08
  4677.1  451.81  4725.0  446.18  4741.1  443.57  4790.7  443.84  4852.5  441.33
  4857.7  441.83  4873.4  440.76  4943.2  439.32  4979.6  440.01  4989.7  439.51
  4998.5  437.31  5001.2  436.81  5004.5  437.31  5018.5  439.84  5065.0  440.33
  5088.3  441.46  5138.9  441.74  5209.1  444.36  5269.3  444.99  5296.0  447.79
  5429.8  447.77  5459.9  449.60  5500.0  450.66  5600.3  450.80  5636.3  451.95
#Mann=5,-1,0
  4324.3    0.05       0  4629.5     0.1       0  4725.0    0.05       0
  4998.5   0.035       0  5004.5    0.05       0
Bank Sta=4998.5,5004.5
Exp/Cntr=0.3,0.1

Chan Stop Cuts=-1