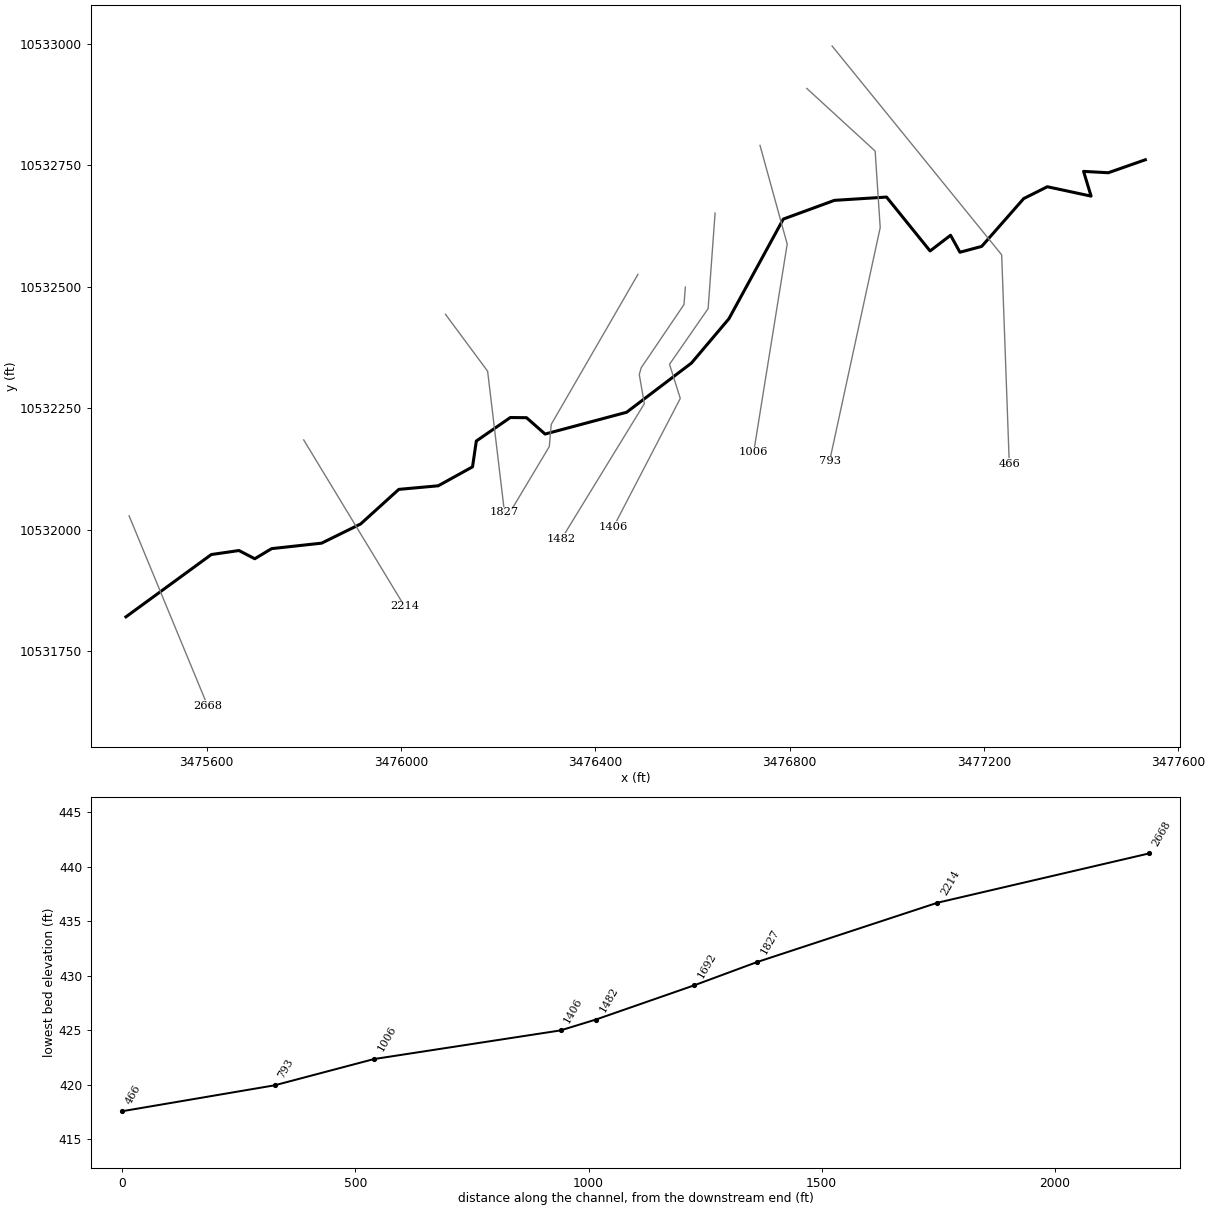
--- UNT01203 IN SAND CR.prj (project) ---

Proj Title=UNT01203 IN SAND CR Base Level Engineering
Current Plan=p01
Default Exp/Contr=0.3,0.1
English Units
Geom File=g01
Flow File=f01
Plan File=p01
BEGIN DESCRIPTION:
UNT01203 IN SAND CR
END DESCRIPTION:

--- UNT01203 IN SAND CR.p01 (plan) ---

Plan Title=Multiple Run
Short Identifier=Multiple
Geom File=g01
Flow File=f01
Subcritical Flow
K Sum by GR= 0
Std Step Tol= 0.01
Critical Tol= 0.01
Num of Std Step Trials= 20
Max Error Tol= 0.3
Flow Tol Ratio= 0.001
Split Flow NTrial= 30
Split Flow Tol= 0.02
Split Flow Ratio= 0.02
Log Output Level= 0
Friction Slope Method= 1
Unsteady Friction Slope Method= 2
Unsteady Bridges Friction Slope Method= 1
Parabolic Critical Depth
Global Vel Dist=  1 , 1 , 1
Global Log Level= 0
CheckData=True
Encroach Param= -1, 0, 0, 0
BEGIN DESCRIPTION:
Multiple Run
END DESCRIPTION:

--- UNT01203 IN SAND CR.f01 (steady flow) ---

Flow Title=Multiple
Number of Profiles=7
Profile Names=10-year,25-year,50-year,1pct_min,100-year,1pct_plu,500-year
River Rch & RM= UNT01203 IN SAND,Reach-1,2668
     227     281     321     270     365     493     467
Boundary for River Rch & Prof#=UNT01203 IN SAND,Reach-1,1
Up Type=0
Dn Type=3
Dn Slope=0.005
Boundary for River Rch & Prof#=UNT01203 IN SAND,Reach-1,2
Up Type=0
Dn Type=3
Dn Slope=0.005
Boundary for River Rch & Prof#=UNT01203 IN SAND,Reach-1,3
Up Type=0
Dn Type=3
Dn Slope=0.005
Boundary for River Rch & Prof#=UNT01203 IN SAND,Reach-1,4
Up Type=0
Dn Type=3
Dn Slope=0.005
Boundary for River Rch & Prof#=UNT01203 IN SAND,Reach-1,5
Up Type=0
Dn Type=3
Dn Slope=0.005
Boundary for River Rch & Prof#=UNT01203 IN SAND,Reach-1,6
Up Type=0
Dn Type=3
Dn Slope=0.005
Boundary for River Rch & Prof#=UNT01203 IN SAND,Reach-1,7
Up Type=0
Dn Type=3
Dn Slope=0.005

--- UNT01203 IN SAND CR.g01 (geometry) ---

Geom Title=Existing Conditions

River Reach=UNT01203 IN SAND,Reach-1
Reach XY= 30
      3475434.03     10531820.84      3475609.83     10531949.15
      3475666.69     10531957.39      3475699.24     10531940.47
      3475733.96     10531961.30      3475836.83     10531972.58
      3475917.12     10532012.08      3475995.68     10532083.26
      3476076.85     10532090.64      3476147.40     10532129.64
      3476155.21     10532182.77      3476225.19     10532231.13
      3476258.53     10532230.78      3476296.72     10532197.10
      3476464.52     10532241.94      3476597.92     10532343.19
      3476675.00     10532434.33      3476786.98     10532639.54
      3476892.19     10532678.08      3476999.48     10532684.85
      3477089.06     10532573.92      3477131.25     10532606.21
      3477150.52     10532571.31      3477195.31     10532583.29
      3477281.77     10532681.73      3477330.35     10532706.11
      3477420.45     10532686.77      3477404.98     10532737.70
      3477455.85     10532734.91      3477532.11     10532761.64

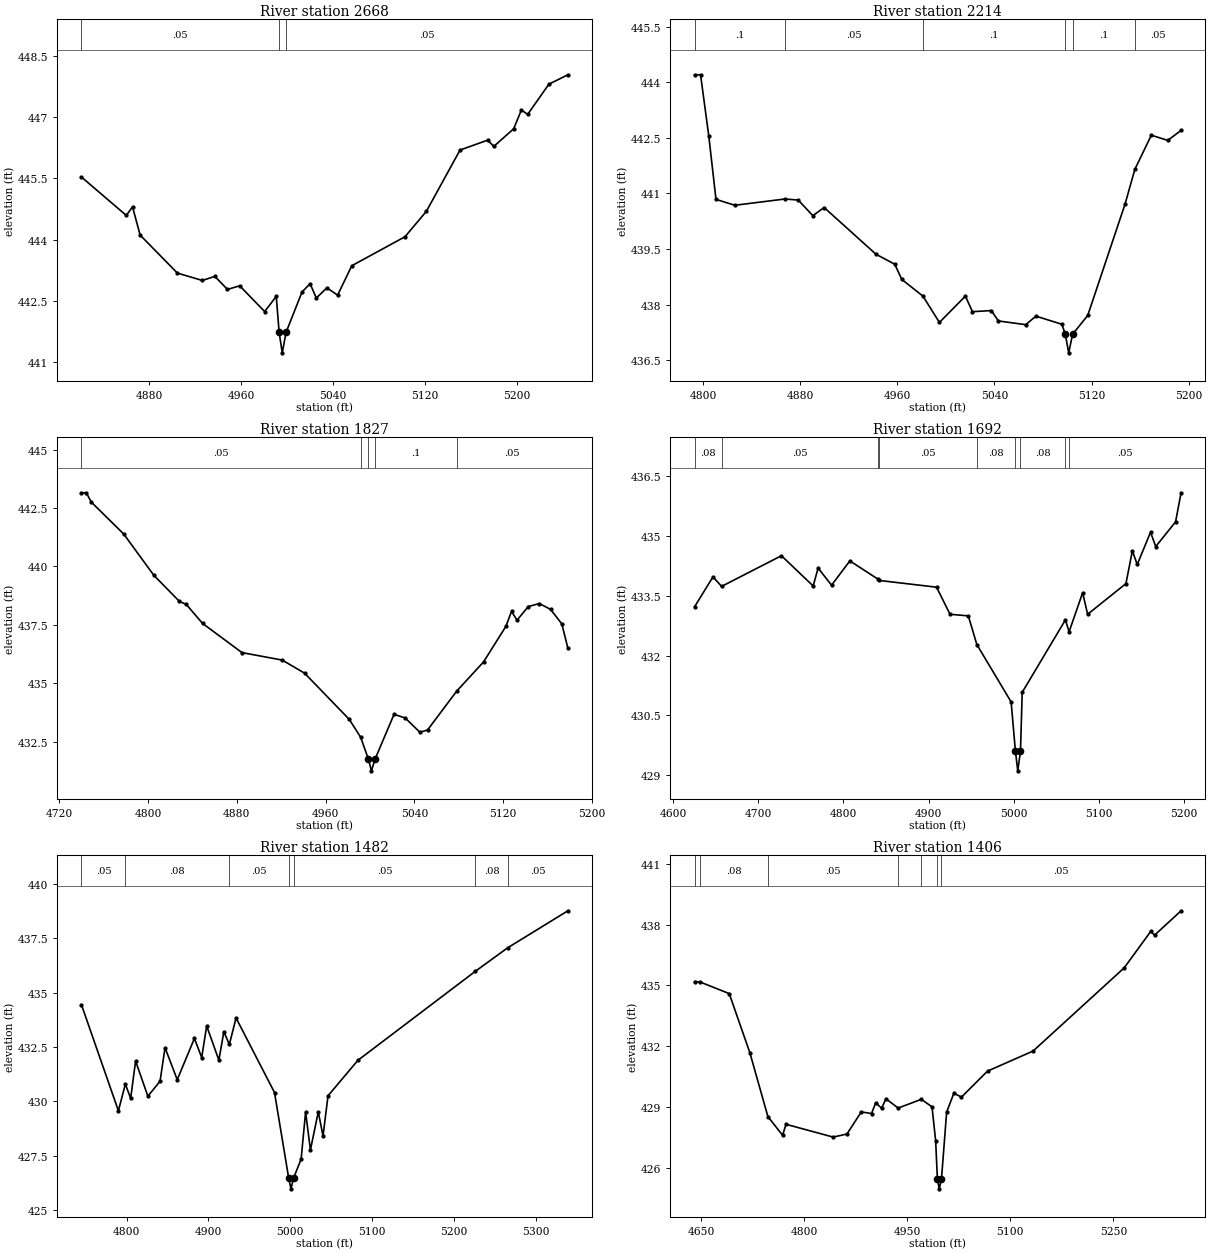
Type RM Length L Ch R = 1,2668,454,454,454
BEGIN DESCRIPTION:
UNT01203 IN SAND CR 3.0
END DESCRIPTION:
XS GIS Cut Line= 2
      3475440.60     10532028.76      3475602.07     10531638.11
#Sta/Elev= 30
  4821.3  445.53  4860.3  444.59  4865.7  444.80  4872.3  444.11  4904.7  443.18
  4926.4  443.00  4937.2  443.10  4948.2  442.78  4958.8  442.87  4980.5  442.24
  4990.6  442.61  4993.1  441.73  4995.8  441.23  4999.1  441.73  5013.0  442.72
  5020.0  442.92  5025.4  442.57  5034.6  442.82  5043.9  442.64  5056.2  443.36
  5102.5  444.07  5121.0  444.69  5150.3  446.19  5174.2  446.43  5179.7  446.28
  5196.9  446.71  5203.6  447.17  5209.0  447.06  5227.5  447.80  5244.0  448.03
#Mann=3,-1,0
  4821.3    0.05       0  4993.1    0.03       0  4999.1    0.05       0
Bank Sta=4993.1,4999.1
Exp/Cntr=0.3,0.1

Type RM Length L Ch R = 1,2214,387,387,387
BEGIN DESCRIPTION:
UNT01203 IN SAND CR 3.1
END DESCRIPTION:
XS GIS Cut Line= 2
      3475800.00     10532184.96      3476007.74     10531842.20
#Sta/Elev= 30
  4793.0  444.20  4797.9  444.20  4804.7  442.54  4810.6  440.84  4826.1  440.68
  4867.5  440.85  4878.4  440.82  4890.4  440.40  4899.7  440.62  4942.4  439.36
  4957.9  439.09  4963.7  438.68  4981.1  438.23  4994.7  437.52  5016.1  438.23
  5021.9  437.81  5037.4  437.84  5043.3  437.56  5065.8  437.46  5074.2  437.69
  5095.6  437.47  5098.4  437.20  5101.2  436.70  5104.4  437.20  5116.9  437.71
  5147.7  440.72  5155.7  441.65  5169.3  442.57  5182.8  442.43  5193.8  442.70
#Mann=6,-1,0
  4793.0     0.1       0  4867.5    0.05       0  4981.1     0.1       0
  5098.4    0.07       0  5104.4     0.1       0  5155.7    0.05       0
Bank Sta=5098.4,5104.4
Exp/Cntr=0.3,0.1

Type RM Length L Ch R = 1,1827,135,135,135
BEGIN DESCRIPTION:
UNT01203 IN SAND CR 2.01
END DESCRIPTION:
XS GIS Cut Line= 3
      3476091.66     10532443.65      3476178.47     10532326.46
      3476213.13     10532036.16
#Sta/Elev= 30
  4740.1  443.15  4744.5  443.15  4749.0  442.75  4778.3  441.38  4805.3  439.62
  4828.4  438.50  4834.6  438.37  4849.2  437.56  4884.7  436.31  4921.0  435.99
  4941.1  435.43  4981.4  433.45  4991.6  432.69  4998.6  431.75  5001.3  431.25
  5004.6  431.75  5021.7  433.67  5031.8  433.51  5045.0  432.90  5051.9  433.00
  5078.1  434.66  5102.3  435.91  5122.4  437.43  5127.5  438.07  5132.5  437.70
  5142.6  438.28  5152.6  438.41  5162.7  438.16  5172.8  437.54  5178.3  436.50
#Mann=5,-1,0
  4740.1    0.05       0  4991.6     0.1       0  4998.6    0.07       0
  5004.6     0.1       0  5078.1    0.05       0
Bank Sta=4998.6,5004.6
Exp/Cntr=0.3,0.1

Type RM Length L Ch R = 1,1692,210,210,210
BEGIN DESCRIPTION:
UNT01203 IN SAND CR 2.02
END DESCRIPTION:
XS GIS Cut Line= 4
      3476487.77     10532525.63      3476309.36     10532216.99
      3476305.45     10532171.42      3476218.51     10532026.07
#Sta/Elev= 30
  4625.1  433.23  4646.7  433.98  4656.8  433.74  4727.1  434.51  4764.4  433.75
  4770.2  434.20  4786.0  433.77  4807.5  434.38  4840.7  433.92  4841.7  433.89
  4909.4  433.72  4925.2  433.04  4946.7  433.00  4956.7  432.28  4997.0  430.84
  5002.0  429.61  5004.8  429.11  5008.0  429.61  5010.0  431.08  5060.8  432.90
  5065.1  432.60  5081.0  433.58  5086.9  433.04  5131.9  433.81  5139.4  434.63
  5145.2  434.29  5160.8  435.10  5166.9  434.74  5190.2  435.36  5196.7  436.09
#Mann=9,-1,0
  4625.1    0.08       0  4656.8    0.05       0  4840.7    0.08       0
  4841.7    0.05       0  4956.7    0.08       0  5002.0    0.07       0
  5008.0    0.08       0  5060.8     0.1       0  5065.1    0.05       0
Bank Sta=5002,5008
Exp/Cntr=0.3,0.1

Type RM Length L Ch R = 1,1482,76,76,76
BEGIN DESCRIPTION:
UNT01203 IN SAND CR 2.03
END DESCRIPTION:
XS GIS Cut Line= 6
      3476585.40     10532499.62      3476582.61     10532463.64
      3476494.50     10532333.43      3476490.59     10532319.55
      3476501.01     10532259.65      3476330.73     10531981.56
#Sta/Elev= 30
  4744.7  434.45  4789.9  429.57  4798.4  430.80  4804.9  430.14  4810.9  431.86
  4825.9  430.24  4840.8  430.93  4846.9  432.47  4861.8  431.00  4882.8  432.90
  4891.7  432.02  4897.8  433.47  4912.7  431.90  4918.8  433.21  4925.5  432.62
  4933.7  433.84  4980.7  430.41  4998.0  426.48  5000.8  425.98  5004.0  426.48
  5013.2  427.34  5018.7  429.51  5024.6  427.77  5034.2  429.52  5040.0  428.41
  5046.1  430.26  5082.6  431.89  5226.3  435.99  5265.8  437.07  5339.3  438.77
#Mann=7,-1,0
  4744.7    0.05       0  4798.4    0.08       0  4925.5    0.05       0
  4998.0    0.04       0  5004.0    0.05       0  5226.3    0.08       0
  5265.8    0.05       0
Bank Sta=4998,5004
Exp/Cntr=0.3,0.1

Type RM Length L Ch R = 1,1406,400,400,400
BEGIN DESCRIPTION:
UNT01203 IN SAND CR 2.04
END DESCRIPTION:
XS GIS Cut Line= 5
      3476646.60     10532651.86      3476632.28     10532455.27
      3476552.85     10532340.69      3476574.98     10532270.37
      3476437.51     10532005.81
#Sta/Elev= 30
  4640.3  435.19  4648.3  435.17  4690.7  434.60  4720.7  431.69  4747.0  428.54
  4768.4  427.62  4773.4  428.16  4842.0  427.53  4862.1  427.68  4883.0  428.77
  4897.9  428.69  4904.0  429.22  4912.7  428.95  4918.8  429.42  4936.7  428.96
  4970.4  429.39  4986.0  429.02  4991.3  427.34  4993.8  425.48  4996.5  424.98
  4999.8  425.48  5007.3  428.76  5017.8  429.69  5028.9  429.50  5066.8  430.78
  5133.2  431.77  5265.9  435.87  5304.4  437.66  5310.1  437.48  5348.7  438.68
#Mann=7,-1,0
  4640.3    0.05       0  4648.3    0.08       0  4747.0    0.05       0
  4936.7    0.08       0  4970.4    0.05       0  4993.8    0.04       0
  4999.8    0.05       0
Bank Sta=4993.8,4999.8
Exp/Cntr=0.3,0.1

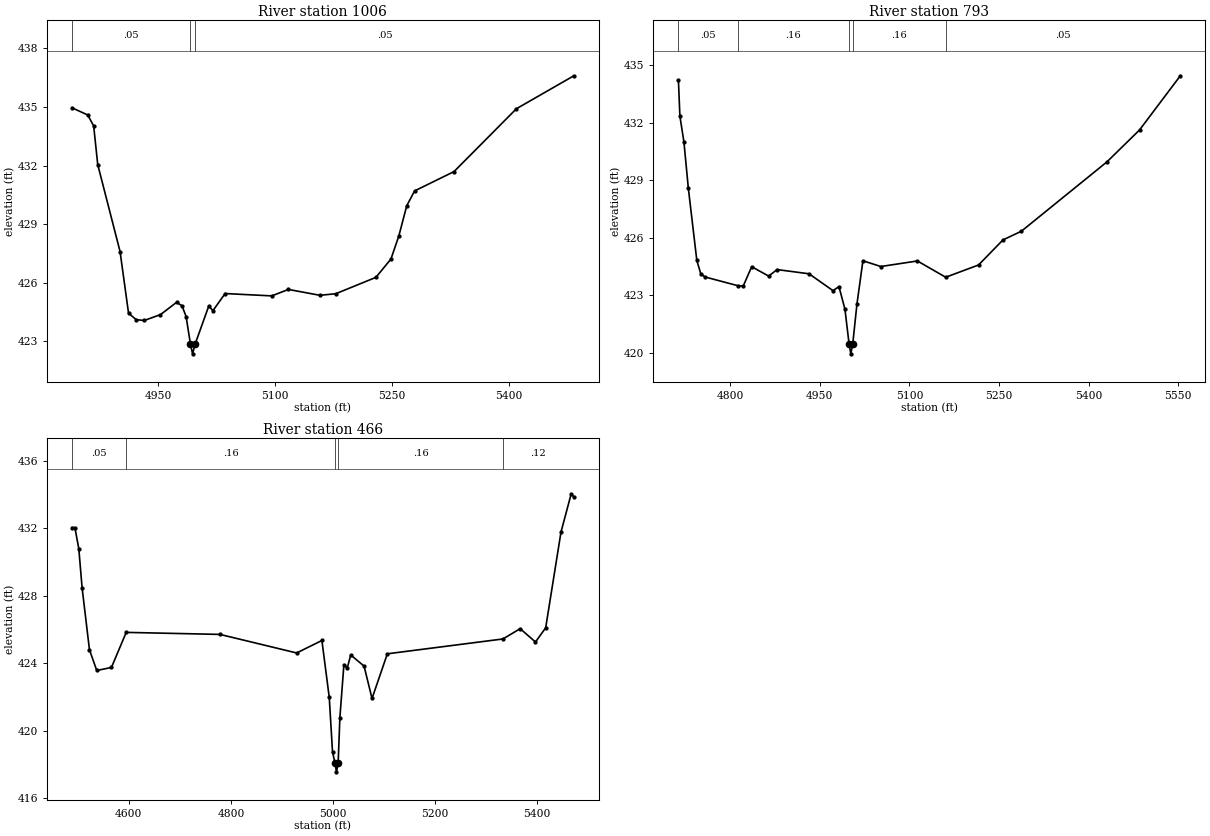
Type RM Length L Ch R = 1,1006,213,213,213
BEGIN DESCRIPTION:
UNT01203 IN SAND CR 2.05
END DESCRIPTION:
XS GIS Cut Line= 3
      3476739.04     10532791.23      3476795.04     10532588.08
      3476726.03     10532159.73
#Sta/Elev= 30
  4839.3  434.96  4859.6  434.59  4867.2  434.03  4872.4  432.05  4901.1  427.59
  4912.0  424.43  4921.9  424.10  4932.2  424.06  4953.0  424.36  4973.7  424.99
  4980.7  424.81  4985.9  424.26  4991.5  422.85  4994.2  422.35  4997.5  422.85
  5015.1  424.81  5020.3  424.56  5036.0  425.44  5095.9  425.32  5117.3  425.65
  5157.8  425.35  5178.1  425.43  5229.7  426.27  5249.0  427.21  5259.1  428.39
  5269.3  429.94  5279.4  430.70  5330.0  431.69  5410.1  434.91  5483.9  436.60
#Mann=3,-1,0
  4839.3    0.05       0  4991.5    0.04       0  4997.5    0.05       0
Bank Sta=4991.5,4997.5
Exp/Cntr=0.3,0.1

Type RM Length L Ch R = 1,793,327,327,327
BEGIN DESCRIPTION:
UNT01203 IN SAND CR 2.06
END DESCRIPTION:
XS GIS Cut Line= 4
      3476835.40     10532908.40      3476976.03     10532779.49
      3476986.44     10532621.94      3476882.28     10532141.47
#Sta/Elev= 30
  4713.3  434.23  4715.8  432.35  4722.5  431.01  4729.9  428.59  4744.1  424.82
  4750.9  424.10  4758.3  423.95  4812.6  423.50  4821.8  423.48  4836.0  424.49
  4864.4  424.00  4878.5  424.34  4932.0  424.12  4972.1  423.24  4982.1  423.45
  4992.1  422.27  4999.1  420.44  5001.9  419.94  5005.1  420.44  5012.2  422.54
  5022.2  424.80  5052.2  424.50  5113.4  424.79  5160.8  423.94  5215.8  424.58
  5256.7  425.89  5287.4  426.34  5430.6  429.96  5485.3  431.63  5553.6  434.46
#Mann=5,-1,0
  4713.3    0.05       0  4812.6    0.16       0  4999.1    0.07       0
  5005.1    0.16       0  5160.8    0.05       0
Bank Sta=4999.1,5005.1
Exp/Cntr=0.3,0.1

Type RM Length L Ch R = 1,466,0,0,0
BEGIN DESCRIPTION:
UNT01203 IN SAND CR 2.07
END DESCRIPTION:
XS GIS Cut Line= 3
      3476887.47     10532995.66      3477236.44     10532565.95
      3477252.06     10532136.49
#Sta/Elev= 30
  4488.5  432.04  4494.3  432.04  4501.9  430.80  4508.4  428.47  4522.8  424.80
  4537.1  423.57  4565.9  423.75  4594.8  425.83  4778.5  425.71  4928.7  424.61
  4978.2  425.35  4992.6  421.97  4999.0  418.74  5004.0  418.06  5006.7  417.56
  5010.0  418.06  5013.4  420.77  5021.3  423.92  5027.8  423.71  5034.7  424.49
  5060.8  423.83  5076.4  421.91  5106.4  424.56  5332.9  425.44  5366.6  426.05
  5396.6  425.26  5416.6  426.10  5446.6  431.78  5466.6  434.05  5471.8  433.87
#Mann=5,-1,0
  4488.5    0.05       0  4594.8    0.16       0  5004.0    0.07       0
  5010.0    0.16       0  5332.9    0.12       0
Bank Sta=5004,5010
Exp/Cntr=0.3,0.1

Chan Stop Cuts=-1