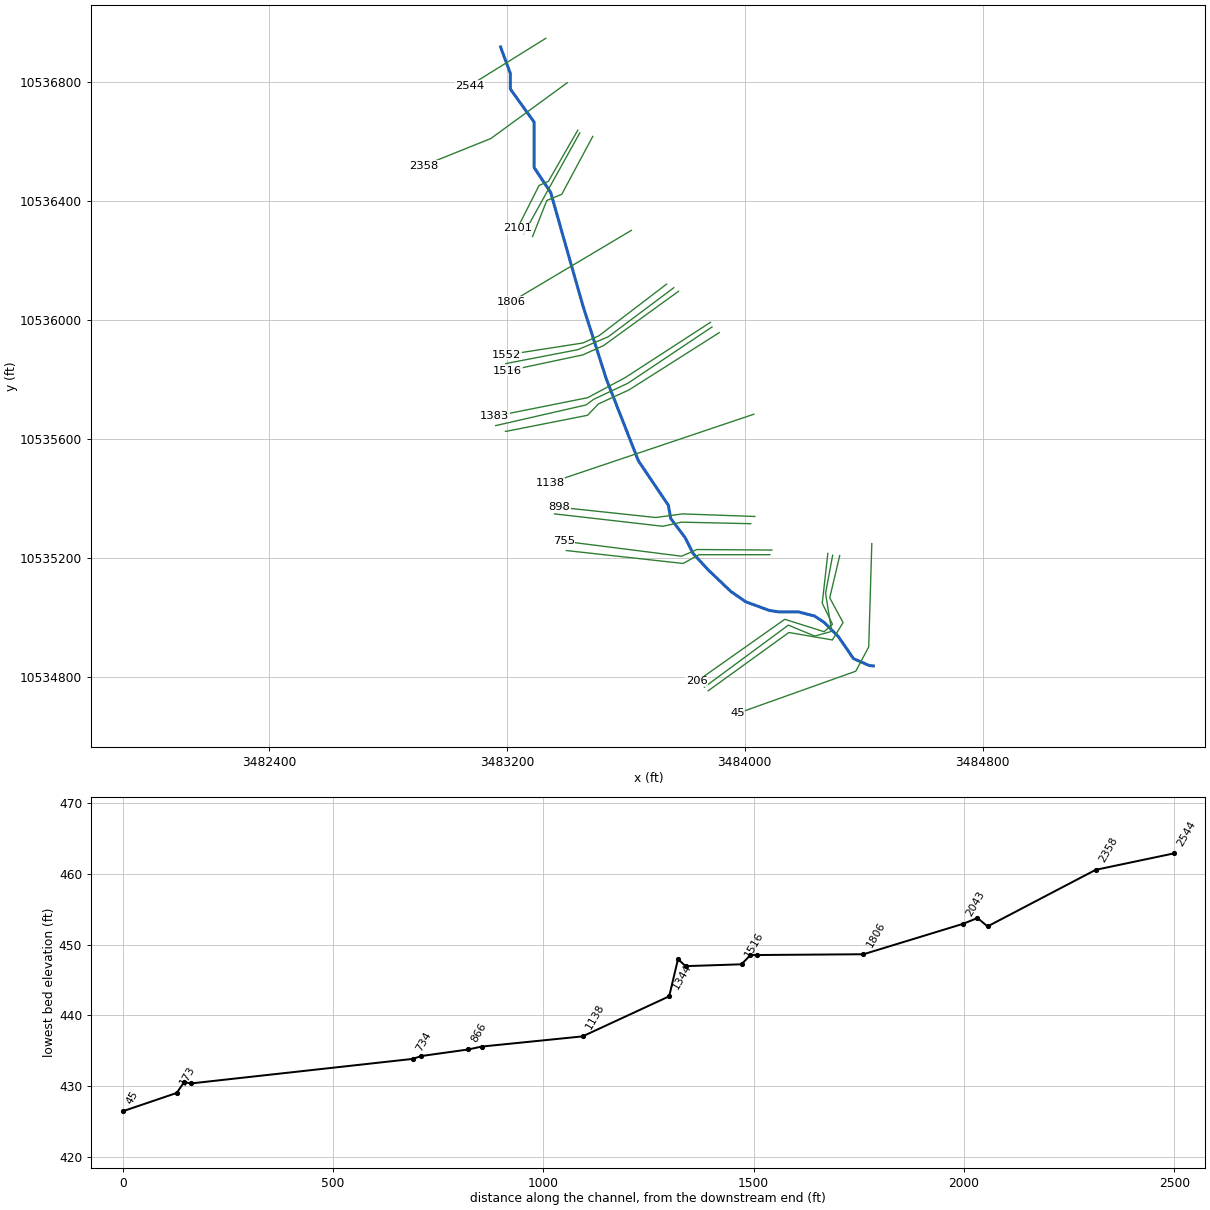
--- UNT01216 IN SAND CR.prj (project) ---

Proj Title=UNT01216 IN SAND CR Base Level Engineering
Current Plan=p01
Default Exp/Contr=0.3,0.1
English Units
Geom File=g01
Flow File=f01
Plan File=p01
BEGIN DESCRIPTION:
UNT01216 IN SAND CR
END DESCRIPTION:

--- UNT01216 IN SAND CR.p01 (plan) ---

Plan Title=Multiple Run
Short Identifier=Multiple
Geom File=g01
Flow File=f01
Subcritical Flow
K Sum by GR= 0
Std Step Tol= 0.01
Critical Tol= 0.01
Num of Std Step Trials= 20
Max Error Tol= 0.3
Flow Tol Ratio= 0.001
Split Flow NTrial= 30
Split Flow Tol= 0.02
Split Flow Ratio= 0.02
Log Output Level= 0
Friction Slope Method= 1
Unsteady Friction Slope Method= 2
Unsteady Bridges Friction Slope Method= 1
Parabolic Critical Depth
Global Vel Dist=  1 , 1 , 1
Global Log Level= 0
CheckData=True
Encroach Param= -1, 0, 0, 0
BEGIN DESCRIPTION:
Multiple Run
END DESCRIPTION:

--- UNT01216 IN SAND CR.f01 (steady flow) ---

Flow Title=Multiple
Number of Profiles=7
Profile Names=10-year,25-year,50-year,1pct_min,100-year,1pct_plu,500-year
River Rch & RM= UNT01216 IN SAND,Reach-1,2544
     270     340     393     333     450     608     586
Boundary for River Rch & Prof#=UNT01216 IN SAND,Reach-1,1
Up Type=0
Dn Type=3
Dn Slope=0.005
Boundary for River Rch & Prof#=UNT01216 IN SAND,Reach-1,2
Up Type=0
Dn Type=3
Dn Slope=0.005
Boundary for River Rch & Prof#=UNT01216 IN SAND,Reach-1,3
Up Type=0
Dn Type=3
Dn Slope=0.005
Boundary for River Rch & Prof#=UNT01216 IN SAND,Reach-1,4
Up Type=0
Dn Type=3
Dn Slope=0.005
Boundary for River Rch & Prof#=UNT01216 IN SAND,Reach-1,5
Up Type=0
Dn Type=3
Dn Slope=0.005
Boundary for River Rch & Prof#=UNT01216 IN SAND,Reach-1,6
Up Type=0
Dn Type=3
Dn Slope=0.005
Boundary for River Rch & Prof#=UNT01216 IN SAND,Reach-1,7
Up Type=0
Dn Type=3
Dn Slope=0.005

--- UNT01216 IN SAND CR.g01 (geometry) ---

Geom Title=Existing Conditions

River Reach=UNT01216 IN SAND,Reach-1
Reach XY= 25
      3483178.78     10536918.25      3483211.77     10536829.05
      3483211.77     10536776.76      3483291.63     10536665.65
      3483291.63     10536512.87      3483347.18     10536429.54
      3483454.82     10536051.07      3483534.68     10535801.07
      3483642.32     10535526.76      3483743.05     10535377.29
      3483750.94     10535333.14      3483798.68     10535269.77
      3483826.46     10535215.08      3483875.94     10535161.27
      3483953.19     10535087.48      3484003.54     10535052.76
      3484081.67     10535024.11      3484114.65     10535018.90
      3484180.62     10535018.90      3484234.44     10535005.02
      3484267.43     10534983.31      3484314.30     10534936.44
      3484365.52     10534861.79      3484419.34     10534838.35
      3484432.37     10534837.26

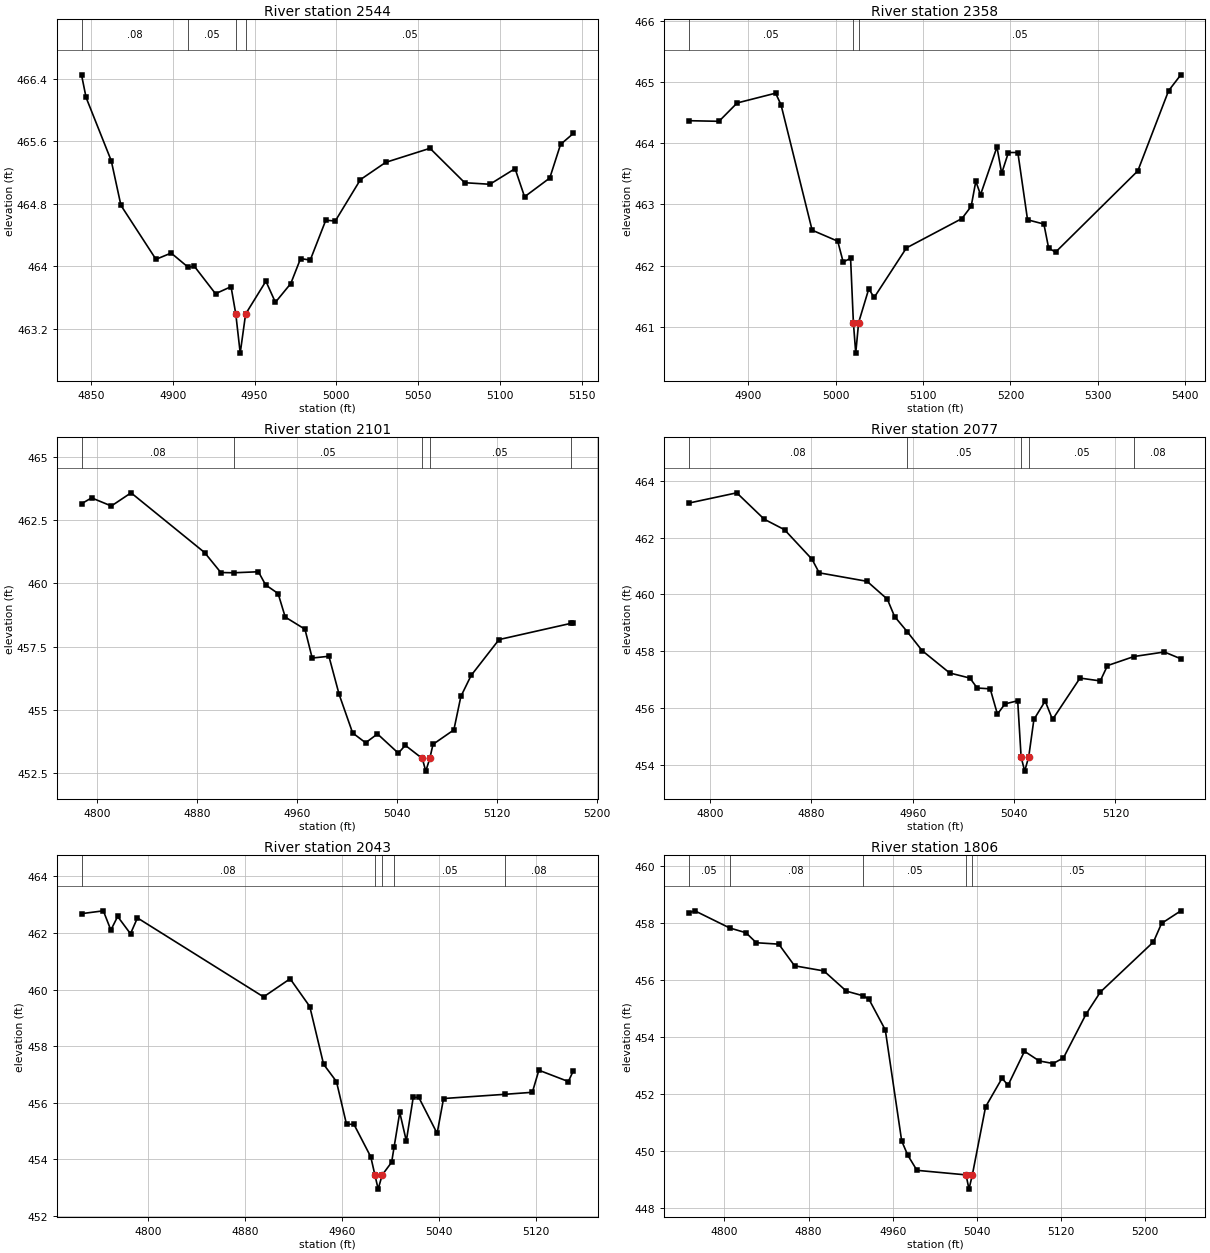
Type RM Length L Ch R = 1,2544,186,186,186
BEGIN DESCRIPTION:
UNT01216 IN SAND CR 5.3
END DESCRIPTION:
XS GIS Cut Line= 2
      3483330.74     10536947.38      3483075.45     10536788.68
#Sta/Elev= 30
  4844.2  466.45  4847.0  466.16  4862.4  465.35  4868.3  464.78  4889.7  464.09
  4899.0  464.17  4909.3  463.99  4913.2  464.00  4926.1  463.65  4935.6  463.74
  4938.5  463.39  4941.2  462.89  4944.5  463.39  4956.9  463.81  4962.7  463.54
  4972.1  463.78  4978.1  464.10  4984.0  464.08  4993.5  464.59  4999.3  464.58
  5014.7  465.11  5030.1  465.33  5057.2  465.51  5078.4  465.07  5093.8  465.05
  5109.2  465.25  5115.0  464.89  5130.4  465.13  5137.0  465.56  5144.8  465.70
#Mann=4,-1,0
  4844.2    0.08       0  4909.3    0.05       0  4938.5    0.04       0
  4944.5    0.05       0
Bank Sta=4938.5,4944.5
Exp/Cntr=0.3,0.1

Type RM Length L Ch R = 1,2358,257,257,257
BEGIN DESCRIPTION:
UNT01216 IN SAND CR 5.5
END DESCRIPTION:
XS GIS Cut Line= 3
      3483403.09     10536798.08      3483146.17     10536610.60
      3482919.11     10536519.23
#Sta/Elev= 30
  4832.2  464.37  4866.5  464.36  4887.3  464.66  4931.3  464.82  4937.5  464.63
  4973.1  462.58  5002.4  462.40  5008.6  462.06  5017.1  462.12  5020.3  461.07
  5023.0  460.57  5026.3  461.07  5037.9  461.62  5044.1  461.48  5081.0  462.29
  5144.5  462.77  5155.1  462.97  5160.4  463.38  5165.8  463.16  5184.6  463.94
  5190.0  463.51  5197.7  463.85  5208.5  463.85  5219.6  462.75  5238.3  462.68
  5243.7  462.29  5251.6  462.22  5345.8  463.55  5381.0  464.86  5395.0  465.12
#Mann=3,-1,0
  4832.2    0.05       0  5020.3    0.04       0  5026.3    0.05       0
Bank Sta=5020.3,5026.3
Exp/Cntr=0.3,0.1

Type RM Length L Ch R = 1,2101,24,24,24
BEGIN DESCRIPTION:
UNT01216 IN SAND CR 5.1
END DESCRIPTION:
XS GIS Cut Line= 4
      3483438.41     10536638.37      3483339.46     10536466.50
      3483308.21     10536452.61      3483235.30     10536308.52
#Sta/Elev= 30
  4787.4  463.15  4795.5  463.38  4811.3  463.06  4827.1  463.58  4886.0  461.22
  4899.0  460.43  4909.3  460.42  4929.1  460.46  4934.9  459.94  4944.9  459.60
  4950.6  458.67  4966.4  458.19  4972.2  457.05  4985.6  457.12  4993.8  455.61
  5004.6  454.09  5015.0  453.70  5024.5  454.05  5041.2  453.29  5046.8  453.60
  5060.4  453.08  5063.2  452.58  5066.4  453.08  5069.0  453.64  5085.7  454.21
  5091.3  455.53  5099.5  456.36  5121.9  457.78  5179.4  458.42  5181.4  458.42
#Mann=5,-1,0
  4787.4    0.08       0  4909.3    0.05       0  5060.4    0.04       0
  5066.4    0.05       0  5179.4    0.08       0
Bank Sta=5060.4,5066.4
Exp/Cntr=0.3,0.1

Type RM Length L Ch R = 1,2077,34,34,34
BEGIN DESCRIPTION:
UNT01216 IN SAND CR 5.0
END DESCRIPTION:
XS GIS Cut Line= 2
      3483445.34     10536629.66      3483256.62     10536290.31
#Sta/Elev= 30
  4783.3  463.22  4821.0  463.58  4842.7  462.65  4858.7  462.28  4880.4  461.24
  4886.1  460.76  4923.9  460.46  4939.9  459.83  4945.6  459.22  4955.5  458.69
  4967.3  458.02  4989.1  457.23  5005.1  457.05  5010.8  456.70  5021.1  456.67
  5026.8  455.78  5032.8  456.14  5042.8  456.25  5045.5  454.27  5048.3  453.77
  5051.5  454.27  5055.6  455.59  5064.5  456.24  5070.3  455.59  5092.0  457.05
  5108.0  456.95  5113.7  457.49  5134.6  457.81  5158.6  457.97  5171.6  457.73
#Mann=5,-1,0
  4783.3    0.08       0  4955.5    0.05       0  5045.5    0.04       0
  5051.5    0.05       0  5134.6    0.08       0
Bank Sta=5045.5,5051.5
Exp/Cntr=0.3,0.1

Type RM Length L Ch R = 1,2043,237,237,237
BEGIN DESCRIPTION:
UNT01216 IN SAND CR 5.2
END DESCRIPTION:
XS GIS Cut Line= 4
      3483488.74     10536617.50      3483384.60     10536423.10
      3483334.25     10536402.26      3483286.39     10536280.89
#Sta/Elev= 30
  4745.0  462.68  4763.0  462.78  4769.2  462.10  4774.8  462.58  4785.4  461.97
  4791.1  462.53  4895.1  459.74  4917.0  460.38  4933.2  459.40  4944.6  457.36
  4955.2  456.75  4963.5  455.24  4969.6  455.24  4983.5  454.09  4986.9  453.45
  4989.6  452.95  4992.9  453.45  5000.7  453.90  5002.7  454.43  5007.4  455.66
  5012.8  454.65  5018.5  456.19  5023.1  456.19  5038.2  454.92  5043.5  456.15
  5094.4  456.30  5116.7  456.37  5122.1  457.15  5146.4  456.75  5150.5  457.13
#Mann=5,-1,0
  4745.0    0.08       0  4986.9    0.07       0  4992.9    0.08       0
  5002.7    0.05       0  5094.4    0.08       0
Bank Sta=4986.9,4992.9
Exp/Cntr=0.3,0.1

Type RM Length L Ch R = 1,1806,254,254,254
BEGIN DESCRIPTION:
UNT01216 IN SAND CR 5.4
END DESCRIPTION:
XS GIS Cut Line= 2
      3483618.41     10536301.58      3483216.36     10536062.43
#Sta/Elev= 30
  4766.3  458.35  4771.9  458.42  4804.9  457.82  4820.5  457.65  4830.3  457.30
  4851.7  457.25  4866.7  456.49  4894.6  456.31  4916.0  455.60  4931.7  455.44
  4937.4  455.32  4953.0  454.24  4968.6  450.34  4974.4  449.84  4983.1  449.31
  5029.8  449.15  5032.6  448.65  5035.8  449.15  5048.4  451.54  5064.0  452.54
  5069.8  452.30  5085.4  453.49  5099.4  453.15  5112.7  453.06  5122.5  453.26
  5143.9  454.79  5157.6  455.57  5208.1  457.33  5215.8  457.98  5234.1  458.42
#Mann=5,-1,0
  4766.3    0.05       0  4804.9    0.08       0  4931.7    0.05       0
  5029.8    0.04       0  5035.8    0.05       0
Bank Sta=5029.8,5035.8
Exp/Cntr=0.3,0.1

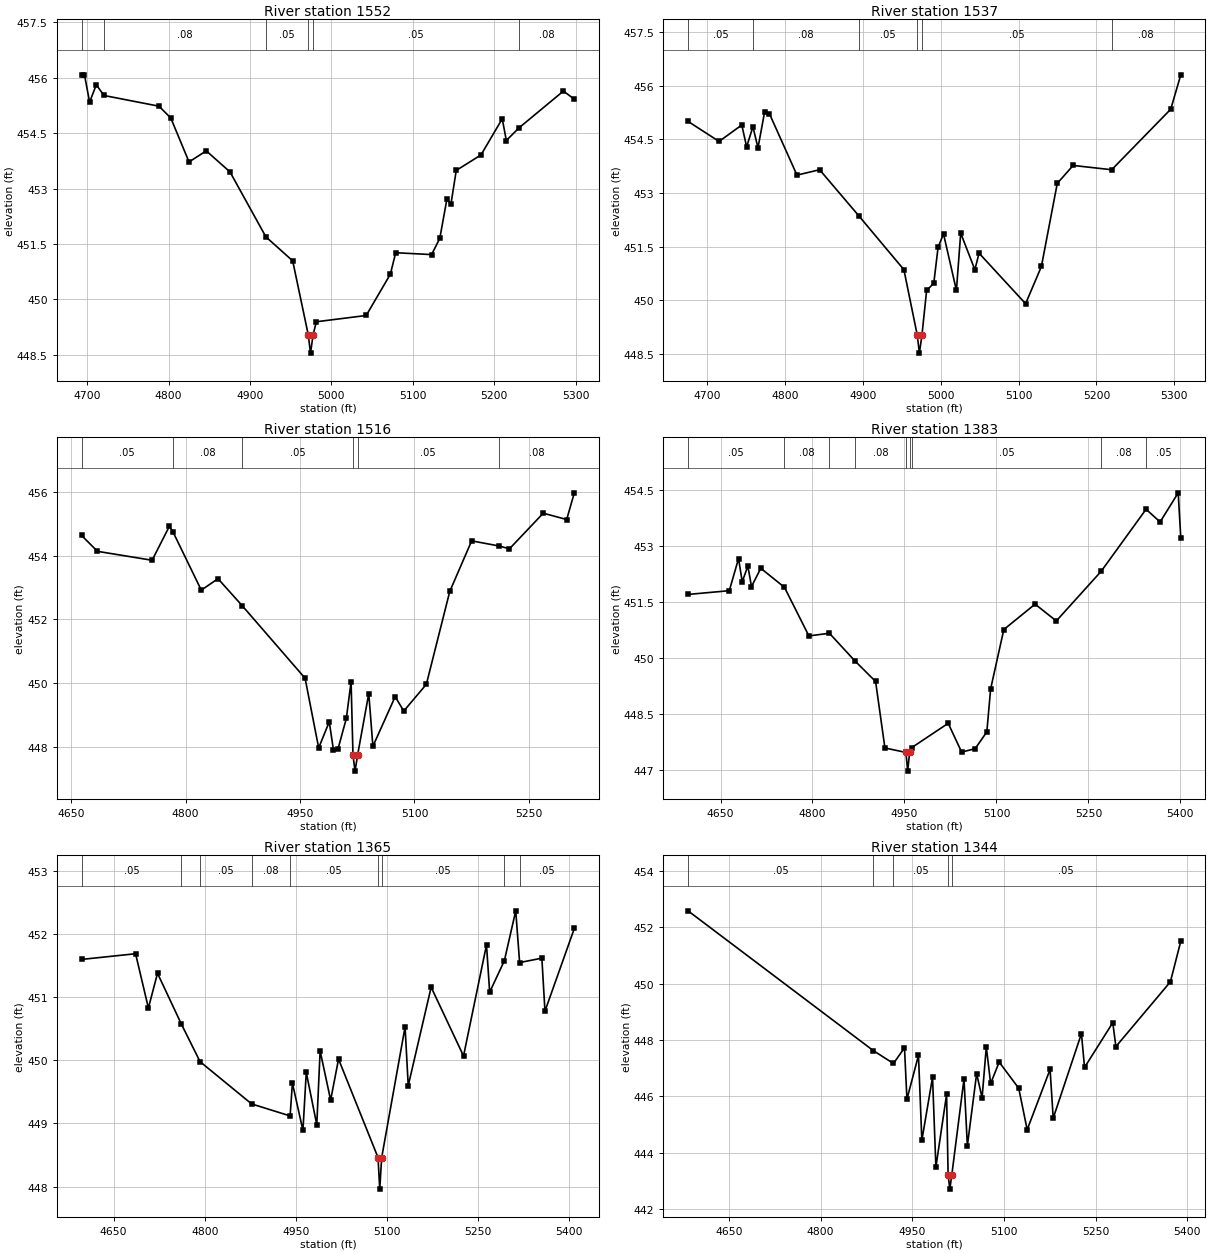
Type RM Length L Ch R = 1,1552,15,15,15
BEGIN DESCRIPTION:
UNT01216 IN SAND CR 4.2
END DESCRIPTION:
XS GIS Cut Line= 4
      3483737.03     10536121.02      3483509.60     10535947.40
      3483455.78     10535923.10      3483198.84     10535883.17
#Sta/Elev= 30
  4693.1  456.08  4696.7  456.08  4703.0  455.34  4711.2  455.81  4720.7  455.52
  4788.2  455.23  4802.7  454.91  4825.1  453.72  4846.3  454.02  4875.4  453.45
  4919.5  451.69  4952.4  451.04  4971.5  449.04  4974.3  448.54  4977.5  449.04
  4981.5  449.39  5042.7  449.56  5072.4  450.68  5078.9  451.26  5123.0  451.21
  5133.1  451.65  5141.8  452.71  5146.8  452.58  5153.3  453.49  5183.7  453.91
  5209.8  454.89  5214.8  454.30  5230.2  454.64  5284.9  455.64  5298.3  455.42
#Mann=6,-1,0
  4693.1    0.05       0  4720.7    0.08       0  4919.5    0.05       0
  4971.5    0.04       0  4977.5    0.05       0  5230.2    0.08       0
Bank Sta=4971.5,4977.5
Exp/Cntr=0.3,0.1

Type RM Length L Ch R = 1,1537,21,21,21
BEGIN DESCRIPTION:
UNT01216 IN SAND CR 4.0
END DESCRIPTION:
XS GIS Cut Line= 4
      3483761.33     10536108.86      3483540.85     10535943.93
      3483438.42     10535900.53      3483196.27     10535853.83
#Sta/Elev= 30
  4675.1  455.00  4715.0  454.44  4744.2  454.90  4750.4  454.29  4758.5  454.85
  4765.0  454.26  4773.4  455.25  4779.6  455.22  4815.1  453.50  4844.2  453.65
  4894.3  452.37  4952.5  450.86  4969.7  449.03  4972.4  448.53  4975.7  449.03
  4981.7  450.28  4990.9  450.48  4996.4  451.48  5003.4  451.86  5020.0  450.28
  5025.5  451.88  5043.7  450.86  5049.1  451.32  5108.9  449.91  5129.2  450.95
  5149.6  453.27  5170.0  453.77  5219.5  453.65  5295.4  455.34  5308.3  456.30
#Mann=6,-1,0
  4675.1    0.05       0  4758.5    0.08       0  4894.3    0.05       0
  4969.7    0.04       0  4975.7    0.05       0  5219.5    0.08       0
Bank Sta=4969.7,4975.7
Exp/Cntr=0.3,0.1

Type RM Length L Ch R = 1,1516,133,133,133
BEGIN DESCRIPTION:
UNT01216 IN SAND CR 4.1
END DESCRIPTION:
XS GIS Cut Line= 4
      3483777.00     10536096.74      3483525.22     10535914.42
      3483455.78     10535883.17      3483202.33     10535829.35
#Sta/Elev= 30
  4663.5  454.64  4684.4  454.14  4756.0  453.86  4778.7  454.93  4783.4  454.75
  4820.5  452.92  4842.4  453.28  4874.2  452.43  4956.6  450.15  4974.4  447.96
  4988.3  448.78  4993.8  447.89  4999.7  447.92  5010.7  448.89  5016.9  450.04
  5019.4  447.73  5022.1  447.23  5025.4  447.73  5040.1  449.67  5045.5  448.01
  5074.7  449.57  5086.0  449.12  5115.6  449.96  5146.3  452.88  5175.0  454.47
  5210.6  454.31  5224.6  454.22  5268.9  455.34  5299.6  455.14  5309.6  455.98
#Mann=6,-1,0
  4663.5    0.05       0  4783.4    0.08       0  4874.2    0.05       0
  5019.4    0.04       0  5025.4    0.05       0  5210.6    0.08       0
Bank Sta=5019.4,5025.4
Exp/Cntr=0.3,0.1

Type RM Length L Ch R = 1,1383,18,18,18
BEGIN DESCRIPTION:
UNT01216 IN SAND CR 3.4
END DESCRIPTION:
XS GIS Cut Line= 4
      3483884.60     10535992.54      3483598.14     10535806.78
      3483471.40     10535739.07      3483159.10     10535676.61
#Sta/Elev= 30
  4597.0  451.70  4664.3  451.80  4679.4  452.66  4685.4  452.04  4694.6  452.46
  4700.5  451.91  4715.7  452.40  4754.3  451.89  4794.1  450.59  4827.6  450.66
  4869.2  449.92  4902.9  449.37  4918.1  447.59  4952.4  447.47  4955.2  446.97
  4958.4  447.47  4961.9  447.60  5021.3  448.25  5043.2  447.48  5065.2  447.57
  5084.3  448.02  5090.5  449.17  5112.0  450.76  5163.0  451.44  5197.6  450.99
  5270.8  452.32  5344.0  453.98  5366.9  453.64  5396.4  454.42  5400.6  453.22
#Mann=9,-1,0
  4597.0    0.05       0  4754.3    0.08       0  4827.6    0.05       0
  4869.2    0.08       0  4952.4    0.04       0  4958.4    0.08       0
  4961.9    0.05       0  5270.8    0.08       0  5344.0    0.05       0
Bank Sta=4952.4,4958.4
Exp/Cntr=0.3,0.1

Type RM Length L Ch R = 1,1365,21,21,21
BEGIN DESCRIPTION:
UNT01216 IN SAND CR 3.2
END DESCRIPTION:
XS GIS Cut Line= 5
      3483889.79     10535976.90      3483606.82     10535787.68
      3483492.24     10535733.86      3483466.20     10535714.76
      3483162.42     10535645.33
#Sta/Elev= 30
  4597.2  451.60  4686.1  451.69  4707.2  450.83  4722.2  451.38  4761.2  450.58
  4792.2  449.98  4877.1  449.31  4940.4  449.12  4944.2  449.64  4961.5  448.89
  4967.0  449.81  4984.3  448.98  4989.8  450.15  5007.1  449.37  5020.1  450.02
  5085.1  448.46  5087.9  447.96  5091.1  448.46  5129.6  450.53  5134.8  449.60
  5172.5  451.16  5225.8  450.07  5263.6  451.83  5268.8  451.08  5293.0  451.58
  5311.7  452.37  5318.1  451.55  5354.7  451.62  5359.8  450.78  5408.1  452.09
#Mann=9,-1,0
  4597.2    0.05       0  4761.2    0.08       0  4792.2    0.05       0
  4877.1    0.08       0  4940.4    0.05       0  5085.1    0.04       0
  5091.1    0.05       0  5293.0    0.08       0  5318.1    0.05       0
Bank Sta=5085.1,5091.1
Exp/Cntr=0.3,0.1

Type RM Length L Ch R = 1,1344,206,206,206
BEGIN DESCRIPTION:
UNT01216 IN SAND CR 3.3
END DESCRIPTION:
XS GIS Cut Line= 6
      3483914.09     10535957.81      3483610.29     10535765.11
      3483507.86     10535718.24      3483471.40     10535680.04
      3483198.83     10535626.22      3483195.38     10535626.22
#Sta/Elev= 30
  4582.9  452.59  4886.0  447.63  4919.2  447.17  4937.2  447.73  4941.2  445.90
  4960.1  447.46  4965.6  444.44  4983.1  446.68  4988.6  443.49  5006.1  446.07
  5008.6  443.21  5011.4  442.71  5014.6  443.21  5034.6  446.62  5040.1  444.25
  5055.3  446.81  5064.2  445.95  5071.1  447.76  5078.2  446.46  5092.2  447.22
  5124.2  446.29  5138.0  444.82  5175.5  446.96  5180.6  445.23  5226.8  448.23
  5231.9  447.03  5278.1  448.62  5283.2  447.77  5372.4  450.07  5389.4  451.51
#Mann=5,-1,0
  4582.9    0.05       0  4886.0    0.08       0  4919.2    0.05       0
  5008.6    0.04       0  5014.6    0.05       0
Bank Sta=5008.6,5014.6
Exp/Cntr=0.3,0.1

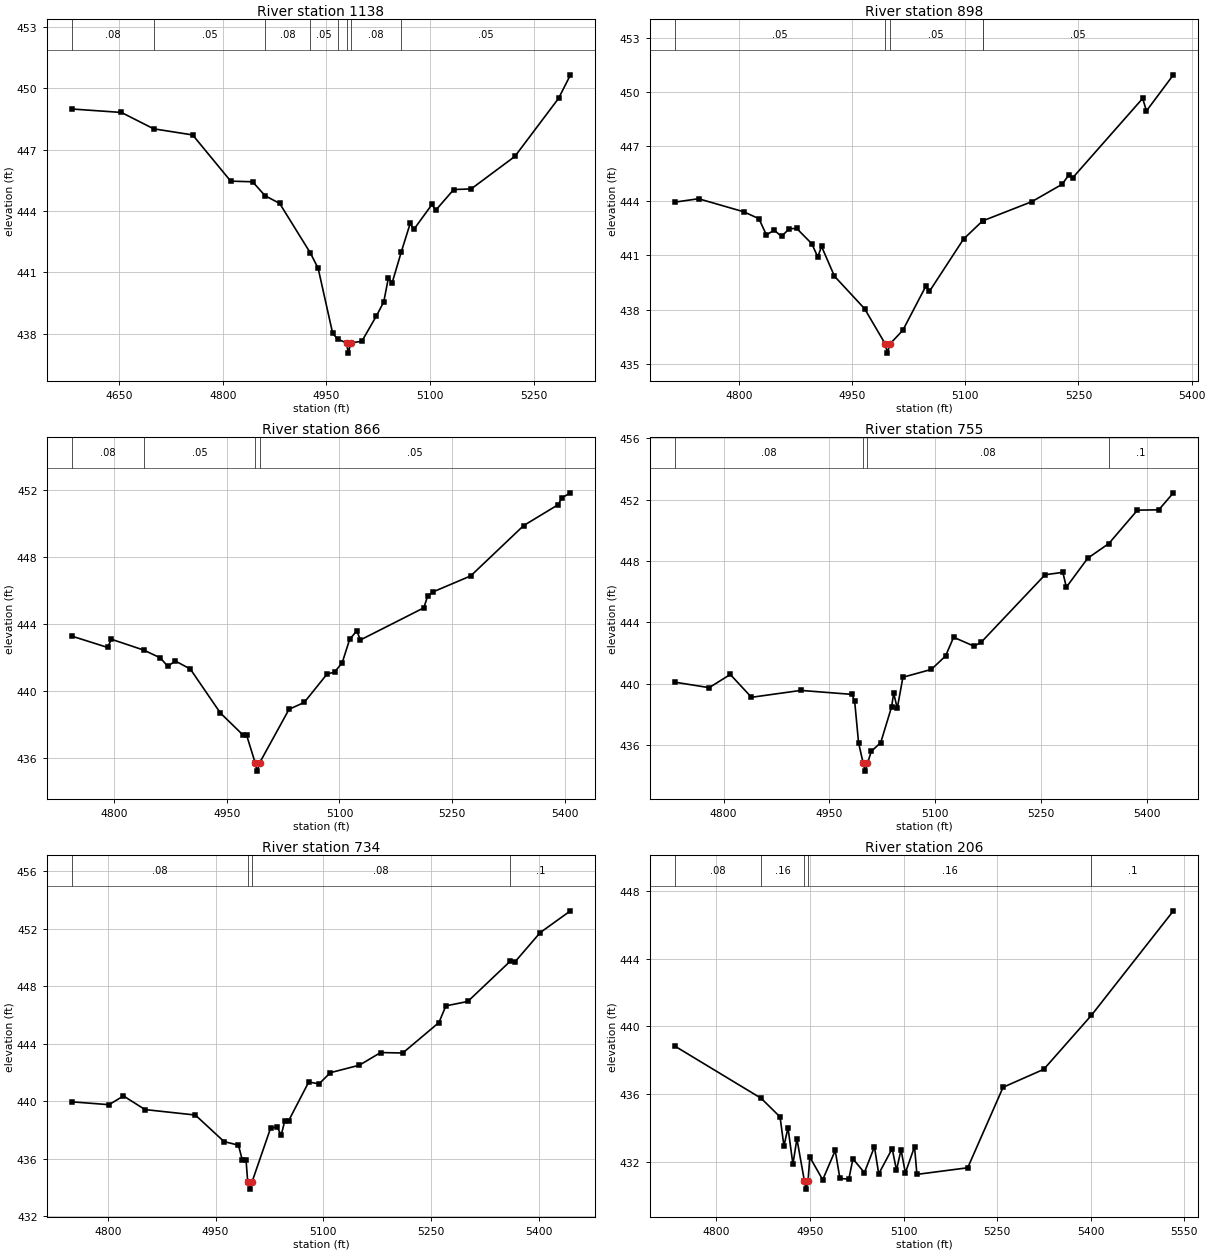
Type RM Length L Ch R = 1,1138,240,240,240
BEGIN DESCRIPTION:
UNT01216 IN SAND CR 2.2
END DESCRIPTION:
XS GIS Cut Line= 2
      3484030.47     10535683.53      3483345.84     10535453.01
#Sta/Elev= 30
  4580.9  448.99  4653.0  448.82  4699.7  448.02  4756.2  447.72  4811.3  445.46
  4843.0  445.43  4861.0  444.75  4882.2  444.37  4926.6  441.95  4937.9  441.20
  4959.0  438.01  4966.5  437.73  4979.0  437.55  4981.7  437.05  4985.0  437.55
  5001.2  437.63  5022.3  438.87  5032.9  439.55  5039.7  440.74  5045.0  440.48
  5058.5  442.02  5071.2  443.39  5076.5  443.10  5102.7  444.32  5108.0  444.03
  5134.2  445.05  5159.5  445.08  5222.8  446.67  5286.1  449.51  5303.3  450.66
#Mann=8,-1,0
  4580.9    0.08       0  4699.7    0.05       0  4861.0    0.08       0
  4926.6    0.05       0  4966.5    0.08       0  4979.0    0.07       0
  4985.0    0.08       0  5058.5    0.05       0
Bank Sta=4979,4985
Exp/Cntr=0.3,0.1

Type RM Length L Ch R = 1,898,32,32,32
BEGIN DESCRIPTION:
UNT01216 IN SAND CR 3.0
END DESCRIPTION:
XS GIS Cut Line= 4
      3484033.87     10535339.77      3483790.85     10535348.44
      3483700.57     10535336.29      3483375.68     10535370.86
#Sta/Elev= 30
  4714.8  443.93  4746.6  444.12  4806.6  443.40  4826.6  443.02  4836.6  442.12
  4846.7  442.39  4856.7  442.04  4866.7  442.47  4876.7  442.48  4896.7  441.64
  4904.6  440.91  4909.6  441.49  4926.7  439.85  4966.6  438.06  4994.1  436.11
  4996.8  435.61  5000.1  436.11  5017.3  436.87  5047.8  439.30  5052.5  439.01
  5097.8  441.90  5123.0  442.90  5123.8  442.91  5188.3  443.96  5228.5  444.92
  5237.5  445.45  5242.5  445.28  5335.1  449.65  5340.1  448.96  5375.8  450.95
#Mann=5,-1,0
  4714.8    0.05       0  4994.1    0.04       0  5000.1    0.05       0
  5123.0    0.08       0  5123.8    0.05       0
Bank Sta=4994.1,5000.1
Exp/Cntr=0.3,0.1

Type RM Length L Ch R = 1,866,111,111,111
BEGIN DESCRIPTION:
UNT01216 IN SAND CR 2.0
END DESCRIPTION:
XS GIS Cut Line= 4
      3484019.99     10535315.46      3483787.38     10535320.67
      3483724.88     10535306.78      3483360.25     10535348.45
#Sta/Elev= 30
  4743.6  443.28  4791.5  442.60  4796.5  443.09  4839.6  442.44  4861.5  441.98
  4871.5  441.47  4881.5  441.79  4901.5  441.31  4941.5  438.68  4971.4  437.37
  4976.3  437.37  4987.8  435.70  4990.6  435.20  4993.8  435.70  5032.9  438.90
  5053.1  439.31  5083.3  441.00  5093.4  441.13  5103.5  441.67  5113.5  443.08
  5122.9  443.59  5127.9  443.05  5212.2  444.97  5217.2  445.66  5224.3  445.92
  5274.6  446.88  5345.0  449.89  5390.9  451.14  5395.9  451.55  5407.3  451.85
#Mann=4,-1,0
  4743.6    0.08       0  4839.6    0.05       0  4987.8    0.04       0
  4993.8    0.05       0
Bank Sta=4987.8,4993.8
Exp/Cntr=0.3,0.1

Type RM Length L Ch R = 1,755,21,21,21
BEGIN DESCRIPTION:
UNT01216 IN SAND CR 3.1
END DESCRIPTION:
XS GIS Cut Line= 4
      3484091.18     10535226.92      3483839.46     10535228.65
      3483787.38     10535206.08      3483391.56     10535256.43
#Sta/Elev= 30
  4730.5  440.09  4779.6  439.73  4809.6  440.59  4839.6  439.10  4909.6  439.55
  4982.2  439.29  4986.0  438.83  4991.5  436.13  4998.1  434.78  5000.9  434.28
  5004.1  434.78  5009.5  435.57  5022.9  436.14  5038.3  438.47  5041.3  439.37
  5046.4  438.38  5054.4  440.41  5094.7  440.92  5114.9  441.80  5126.3  443.02
  5155.2  442.44  5165.3  442.69  5256.0  447.10  5281.2  447.26  5286.2  446.29
  5316.5  448.18  5346.5  449.14  5387.0  451.32  5417.3  451.34  5438.0  452.45
#Mann=4,-1,0
  4730.5    0.08       0  4998.1    0.07       0  5004.1    0.08       0
  5346.5     0.1       0
Bank Sta=4998.1,5004.1
Exp/Cntr=0.3,0.1

Type RM Length L Ch R = 1,734,528,528,528
BEGIN DESCRIPTION:
UNT01216 IN SAND CR 2.1
END DESCRIPTION:
XS GIS Cut Line= 4
      3484084.22     10535211.29      3483846.40     10535211.29
      3483792.58     10535181.78      3483400.18     10535225.19
#Sta/Elev= 30
  4749.7  439.95  4801.8  439.75  4821.8  440.36  4851.8  439.41  4921.8  439.03
  4961.8  437.18  4981.8  436.93  4987.2  435.89  4992.4  435.89  4994.7  434.37
  4997.4  433.87  5000.7  434.37  5026.6  438.13  5035.6  438.19  5041.3  437.63
  5046.3  438.64  5051.7  438.64  5079.6  441.33  5093.9  441.20  5109.7  441.98
  5150.0  442.50  5179.6  443.38  5210.4  443.35  5260.7  445.47  5270.4  446.63
  5300.9  446.94  5359.9  449.74  5366.1  449.67  5401.5  451.73  5443.7  453.25
#Mann=4,-1,0
  4749.7    0.08       0  4994.7    0.07       0  5000.7    0.08       0
  5359.9     0.1       0
Bank Sta=4994.7,5000.7
Exp/Cntr=0.3,0.1

Type RM Length L Ch R = 1,206,15,15,15
BEGIN DESCRIPTION:
UNT01216 IN SAND CR 1.1
END DESCRIPTION:
XS GIS Cut Line= 6
      3484279.23     10535215.36      3484260.48     10535048.17
      3484294.86     10534977.34      3484266.73     10534952.34
      3484134.44     10534994.01      3483839.10     10534785.70
#Sta/Elev= 30
  4733.0  438.85  4871.8  435.76  4902.1  434.66  4908.3  432.94  4914.8  434.02
  4922.7  431.87  4929.1  433.37  4941.0  430.90  4943.8  430.40  4947.0  430.90
  4949.8  432.29  4970.4  430.95  4990.5  432.68  4998.0  431.03  5012.3  430.99
  5018.9  432.19  5037.2  431.37  5053.3  432.90  5060.2  431.30  5081.8  432.79
  5088.6  431.52  5096.0  432.72  5102.9  431.36  5117.6  432.90  5121.4  431.27
  5202.8  431.66  5259.5  436.41  5324.7  437.47  5400.9  440.65  5532.4  446.82
#Mann=5,-1,0
  4733.0    0.08       0  4871.8    0.16       0  4941.0    0.07       0
  4947.0    0.16       0  5400.9     0.1       0
Bank Sta=4941,4947
Exp/Cntr=0.3,0.1

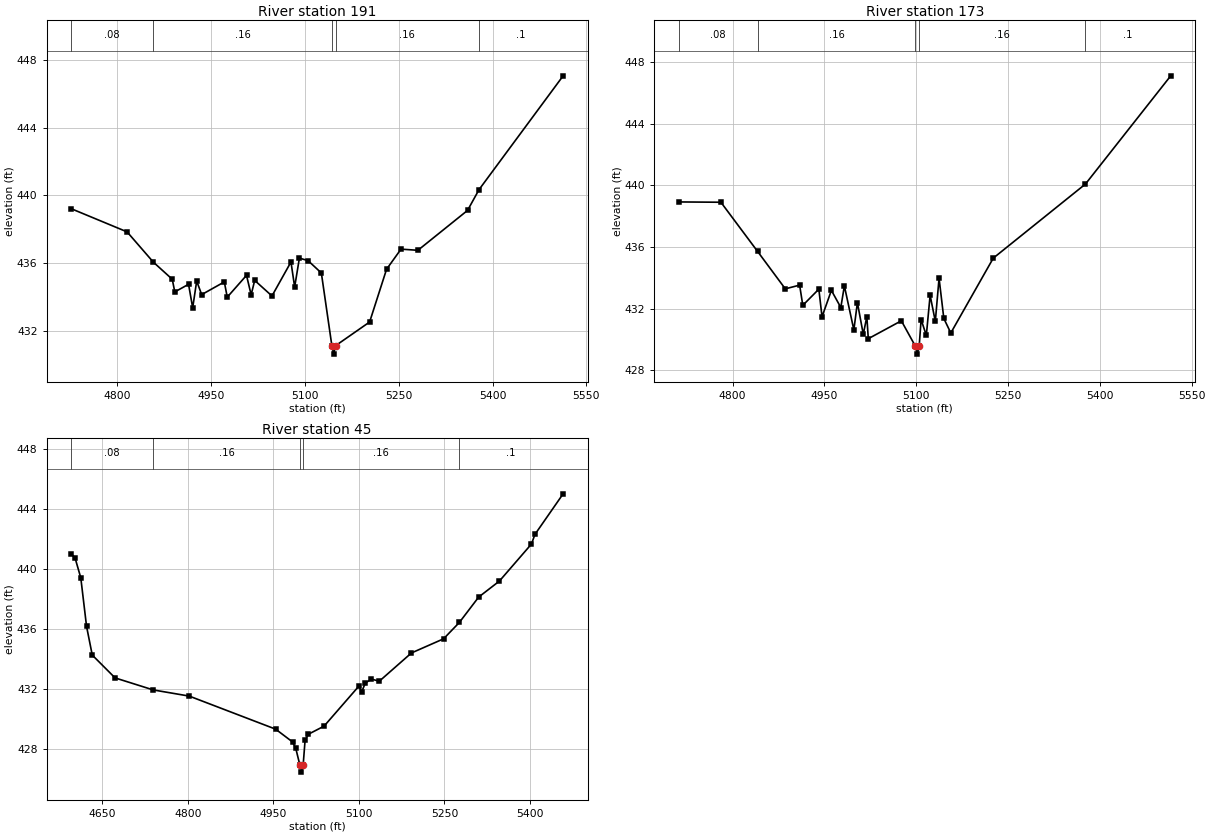
Type RM Length L Ch R = 1,191,18,18,18
BEGIN DESCRIPTION:
UNT01216 IN SAND CR 1.0
END DESCRIPTION:
XS GIS Cut Line= 6
      3484295.48     10535209.40      3484271.60     10535081.34
      3484292.35     10534953.56      3484235.41     10534937.59
      3484146.52     10534974.40      3483864.09     10534765.82
#Sta/Elev= 30
  4726.2  439.21  4815.5  437.84  4857.5  436.05  4887.7  435.04  4891.8  434.29
  4913.8  434.74  4920.4  433.35  4926.8  434.93  4934.8  434.13  4971.0  434.88
  4975.7  433.98  5006.5  435.27  5013.9  434.12  5019.6  434.97  5047.2  434.05
  5077.6  436.06  5083.5  434.58  5091.1  436.29  5104.9  436.14  5126.2  435.41
  5143.0  431.11  5145.7  430.61  5149.0  431.11  5203.4  432.51  5230.5  435.63
  5253.6  436.82  5280.6  436.75  5360.0  439.11  5378.4  440.34  5512.9  447.07
#Mann=5,-1,0
  4726.2    0.08       0  4857.5    0.16       0  5143.0    0.07       0
  5149.0    0.16       0  5378.4     0.1       0
Bank Sta=5143,5149
Exp/Cntr=0.3,0.1

Type RM Length L Ch R = 1,173,128,128,128
BEGIN DESCRIPTION:
UNT01216 IN SAND CR 1.2
END DESCRIPTION:
XS GIS Cut Line= 6
      3484319.30     10535208.46      3484285.65     10535066.27
      3484330.53     10534982.98      3484294.59     10534924.65
      3484148.24     10534949.65      3483876.70     10534753.54
#Sta/Elev= 30
  4712.2  438.92  4780.9  438.90  4840.9  435.71  4886.1  433.29  4909.5  433.53
  4914.7  432.22  4940.9  433.27  4946.1  431.48  4961.4  433.19  4976.8  432.08
  4982.6  433.48  4998.1  430.63  5003.9  432.40  5013.5  430.34  5019.3  431.49
  5021.7  430.06  5075.7  431.22  5098.8  429.56  5101.6  429.06  5104.8  429.56
  5108.0  431.30  5116.5  430.27  5122.7  432.87  5131.2  431.18  5137.3  433.98
  5145.1  431.37  5156.5  430.43  5225.9  435.28  5376.5  440.08  5515.8  447.09
#Mann=5,-1,0
  4712.2    0.08       0  4840.9    0.16       0  5098.8    0.07       0
  5104.8    0.16       0  5376.5     0.1       0
Bank Sta=5098.8,5104.8
Exp/Cntr=0.3,0.1

Type RM Length L Ch R = 1,45,0,0,0
BEGIN DESCRIPTION:
UNT01216 IN SAND CR 1.21
END DESCRIPTION:
XS GIS Cut Line= 4
      3484427.15     10535248.38      3484416.73     10534901.13
      3484373.33     10534819.54      3483975.58     10534677.73
#Sta/Elev= 30
  4595.9  441.01  4602.6  440.73  4612.6  439.41  4622.7  436.18  4632.7  434.27
  4672.7  432.75  4739.6  431.95  4802.7  431.54  4954.1  429.34  4983.7  428.49
  4989.4  428.06  4996.4  426.98  4999.1  426.48  5002.4  426.98  5005.7  428.59
  5011.4  429.00  5039.0  429.54  5099.7  432.19  5105.0  431.83  5111.3  432.41
  5122.0  432.67  5135.8  432.53  5192.1  434.41  5248.4  435.35  5276.1  436.44
  5310.0  438.13  5346.2  439.19  5402.5  441.66  5408.6  442.30  5458.0  445.00
#Mann=5,-1,0
  4595.9    0.08       0  4739.6    0.16       0  4996.4    0.07       0
  5002.4    0.16       0  5276.1     0.1       0
Bank Sta=4996.4,5002.4
Exp/Cntr=0.3,0.1

Chan Stop Cuts=-1