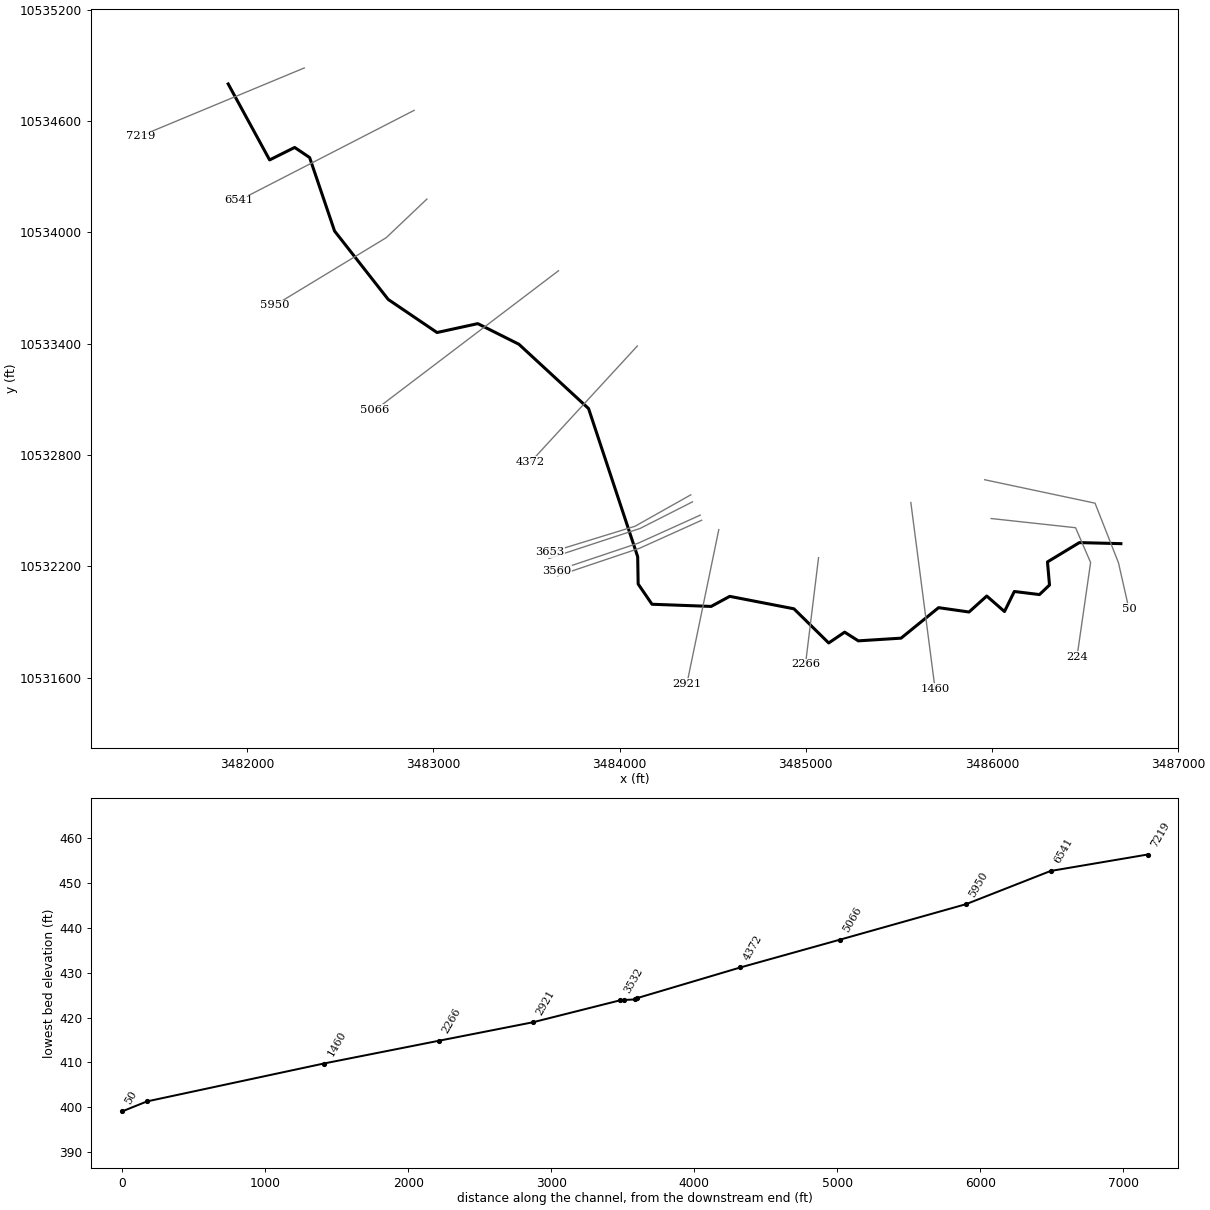
--- UNT01217 IN SAND CR.prj (project) ---

Proj Title=UNT01217 IN SAND CR Base Level Engineering
Current Plan=p01
Default Exp/Contr=0.3,0.1
English Units
Geom File=g01
Flow File=f01
Plan File=p01
Y Axis Title=Elevation
X Axis Title(PF)=Main Channel Distance
X Axis Title(XS)=Station
BEGIN DESCRIPTION:
UNT01217 IN SAND CR
END DESCRIPTION:
DSS Export Rating Curves= 0
DSS Export Rating Curve Sorted= 0
DSS Export Volume Flow Curves= 0
DXF OffsetX= 0
DXF OffsetY= 0
DXF ScaleX= 1
DXF ScaleY= 10

--- UNT01217 IN SAND CR.p01 (plan) ---

Plan Title=Multiple Run
Short Identifier=Multiple
Geom File=g01
Flow File=f01
Subcritical Flow
K Sum by GR= 0
Std Step Tol= 0.01
Critical Tol= 0.01
Num of Std Step Trials= 20
Max Error Tol= 0.3
Flow Tol Ratio= 0.001
Split Flow NTrial= 30
Split Flow Tol= 0.02
Split Flow Ratio= 0.02
Log Output Level= 0
Friction Slope Method= 1
Unsteady Friction Slope Method= 2
Unsteady Bridges Friction Slope Method= 1
Parabolic Critical Depth
Global Vel Dist=  1 , 1 , 1
Global Log Level= 0
CheckData=True
Encroach Param= -1, 0, 0, 0
BEGIN DESCRIPTION:
Multiple Run
END DESCRIPTION:

--- UNT01217 IN SAND CR.f01 (steady flow) ---

Flow Title=Multiple
Number of Profiles=7
Profile Names=10-year,25-year,50-year,1pct_min,100-year,1pct_plu,500-year
River Rch & RM= UNT01217 IN SAND,Reach-1,7219
     405     522     613     527     712     963     957
Boundary for River Rch & Prof#=UNT01217 IN SAND,Reach-1,1
Up Type=0
Dn Type=3
Dn Slope=0.005
Boundary for River Rch & Prof#=UNT01217 IN SAND,Reach-1,2
Up Type=0
Dn Type=3
Dn Slope=0.005
Boundary for River Rch & Prof#=UNT01217 IN SAND,Reach-1,3
Up Type=0
Dn Type=3
Dn Slope=0.005
Boundary for River Rch & Prof#=UNT01217 IN SAND,Reach-1,4
Up Type=0
Dn Type=3
Dn Slope=0.005
Boundary for River Rch & Prof#=UNT01217 IN SAND,Reach-1,5
Up Type=0
Dn Type=3
Dn Slope=0.005
Boundary for River Rch & Prof#=UNT01217 IN SAND,Reach-1,6
Up Type=0
Dn Type=3
Dn Slope=0.005
Boundary for River Rch & Prof#=UNT01217 IN SAND,Reach-1,7
Up Type=0
Dn Type=3
Dn Slope=0.005

--- UNT01217 IN SAND CR.g01 (geometry) ---

Geom Title=Existing Conditions
Program Version=4.10

River Reach=UNT01217 IN SAND,Reach-1
Reach XY= 30
      3481898.17      10534799.1      3482120.61     10534389.67
      3482255.16     10534456.94      3482335.45     10534402.69
      3482469.38     10534006.52      3482757.54     10533637.72
      3483019.63     10533459.53      3483238.38     10533507.45
      3483459.22      10533396.4      3483833.39     10533049.73
      3484097.21     10532251.13      3484099.72     10532104.16
      3484174.07     10531995.03      3484491.76     10531983.37
      3484591.49      10532037.6      3484936.26     10531970.49
      3485122.94     10531786.35      3485208.72     10531844.65
      3485281.95     10531797.79      3485511.64     10531812.35
      3485713.02     10531976.68      3485876.45     10531953.23
      3485971.74     10532039.39      3486066.94     10531955.83
      3486119.79     10532063.83      3486254.78      10532047.2
      3486308.72     10532098.73      3486297.86     10532223.27
      3486469.14     10532327.32      3486692.11     10532321.64

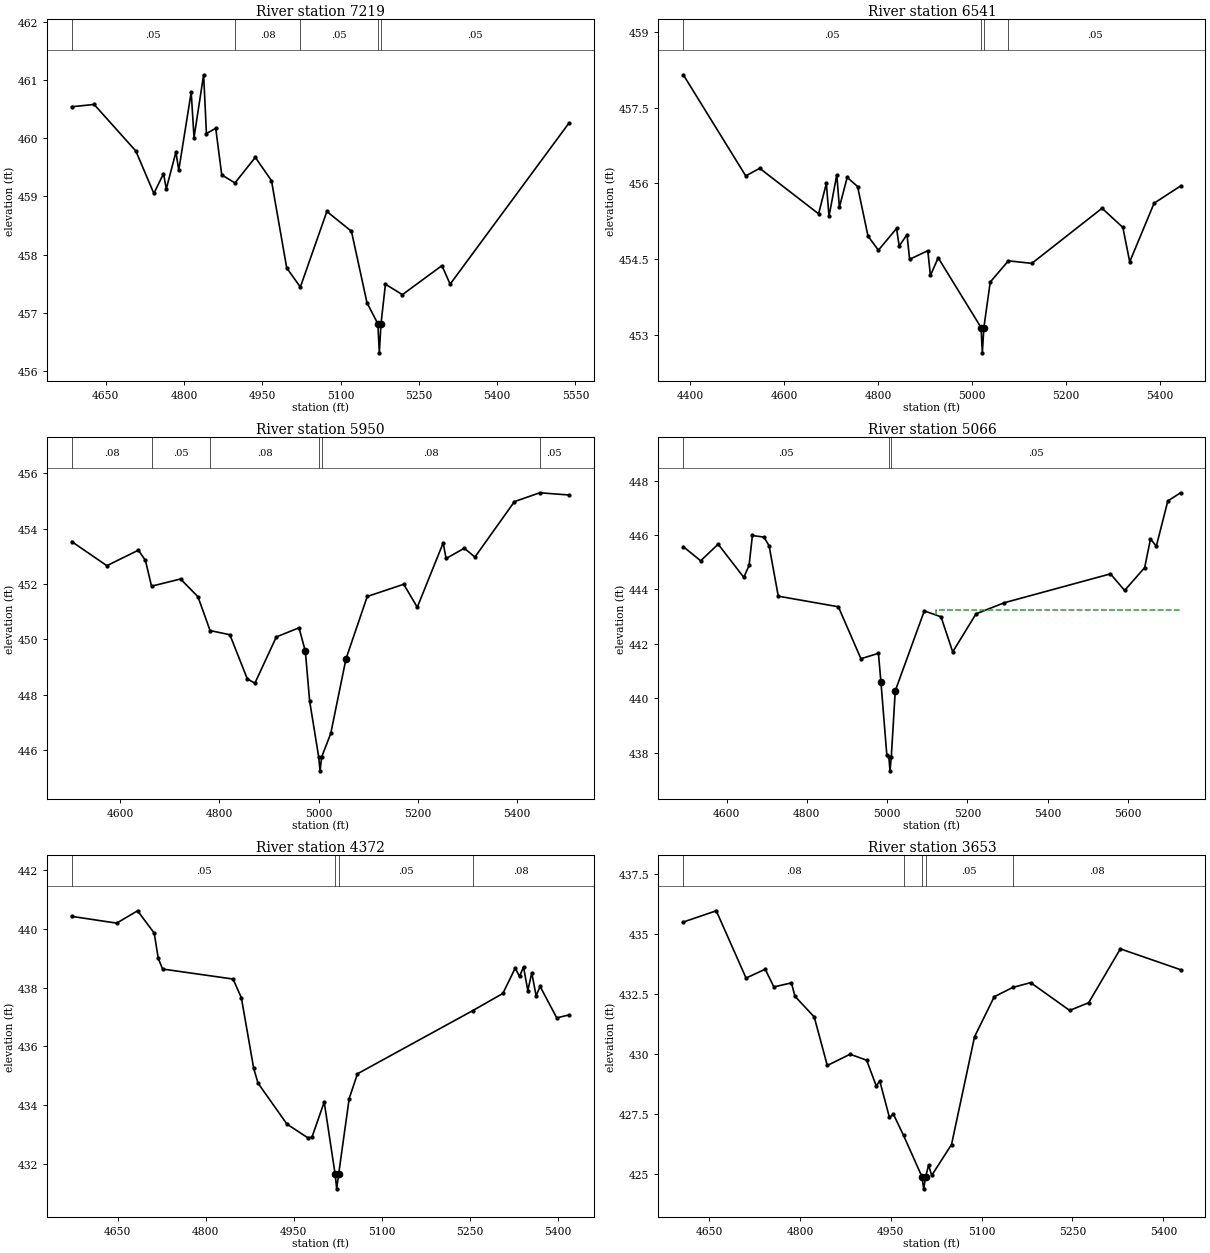
Type RM Length L Ch R = 1 ,7219    ,678,678,678
BEGIN DESCRIPTION:
UNT01217 IN SAND CR 12.1
END DESCRIPTION:
XS GIS Cut Line= 3
      3482306.75     10534885.43      3481495.15      10534546.9
      3481428.32     10534516.96
#Sta/Elev= 30
    4585  460.54  4627.9  460.58  4707.8  459.78  4742.4  459.05  4760.8  459.39
  4766.2  459.13  4784.6  459.76  4790.1  459.45  4813.9  460.79  4819.3  460.01
  4837.7  461.09  4843.1  460.08  4860.9  460.17  4872.4  459.37  4897.7  459.23
  4936.7  459.67  4967.7  459.27  4996.9  457.77    5023  457.44  5073.8  458.74
  5120.9   458.4  5150.7  457.17  5171.5  456.81  5174.3  456.31  5177.5  456.81
    5186  457.49  5218.5  457.31  5294.3  457.81  5309.9  457.49  5537.6  460.26
#Mann= 5 ,-1 , 0
    4585     .05       0  4897.7     .08       0    5023     .05       0
  5171.5     .07       0  5177.5     .05       0
Bank Sta=5171.5,5177.5
XS Rating Curve= 0 ,0
Exp/Cntr=0.3,0.1

Type RM Length L Ch R = 1 ,6541    ,591,591,591
BEGIN DESCRIPTION:
UNT01217 IN SAND CR 12.2
END DESCRIPTION:
XS GIS Cut Line= 2
      3482896.61      10534656.9      3481955.92     10534171.38
#Sta/Elev= 30
  4385.3  458.15  4518.2  456.15  4547.9   456.3  4673.3   455.4  4689.8     456
  4695.5  455.35    4712  456.17  4717.6  455.53  4734.2  456.12  4756.3  455.94
  4778.5  454.96  4800.6  454.68  4839.3  455.11  4844.9  454.76  4861.5  454.99
  4867.1   454.5  4905.8  454.67  4911.4  454.18  4927.9  454.53  5019.2  453.15
  5021.9  452.65  5025.2  453.15  5038.7  454.05  5077.4  454.47  5127.3  454.42
  5276.8  455.51  5321.1  455.13  5335.7  454.45  5387.6  455.61  5443.9  455.95
#Mann= 4 ,-1 , 0
  4385.3     .05       0  5019.2     .04       0  5025.2     .05       0
  5077.4     .05       0
Bank Sta=5019.2,5025.2
XS Rating Curve= 0 ,0
Exp/Cntr=0.3,0.1

Type RM Length L Ch R = 1 ,5950    ,884,884,884
BEGIN DESCRIPTION:
UNT01217 IN SAND CR 12.0
END DESCRIPTION:
XS GIS Cut Line= 3
      3482965.14     10534178.66      3482746.37     10533970.31
      3482148.18      10533606.2
#Sta/Elev= 30
  4502.1  453.53    4573  452.66  4636.5  453.22  4650.7  452.85    4663  451.92
  4721.4  452.18  4756.6  451.54    4781  450.32  4820.9  450.17    4856  448.58
  4871.3  448.42  4914.6  450.09  4960.3  450.42  4973.1  449.57  4981.7  447.78
    5000  445.76  5002.7  445.26    5006  445.76  5024.3  446.61    5055   449.3
  5097.9  451.55  5171.5  451.99  5198.7  451.16  5250.9  453.48  5256.8  452.92
  5293.6  453.29  5314.9  452.97  5394.5  454.97  5445.6  455.29  5504.5  455.21
#Mann= 6 ,-1 , 0
  4502.1     .08       0    4663     .05       0    4781     .08       0
    5000     .07       0    5006     .08       0  5445.6     .05       0
Bank Sta=4973.1,5055
XS Rating Curve= 0 ,0
Exp/Cntr=0.3,0.1

Type RM Length L Ch R = 1 ,5066    ,694,694,694
BEGIN DESCRIPTION:
UNT01217 IN SAND CR 11.0
END DESCRIPTION:
XS GIS Cut Line= 2
      3483671.94     10533792.49       3482686.9     10533041.78
#Sta/Elev= 30
  4492.3  445.57  4535.5  445.05  4579.1  445.66    4643  444.44  4656.1  444.88
  4664.4  445.98  4693.3  445.92    4706   445.6  4728.8  443.75  4878.5  443.36
  4934.7  441.45  4978.3  441.65  4984.6  440.58  4999.1  437.93  5004.3  437.83
  5007.1  437.33  5010.3  437.83  5020.2  440.27  5092.6  443.21  5134.2  442.99
  5163.3   441.7  5221.3   443.1  5292.2  443.51  5556.2  444.57  5591.5  443.96
  5641.4   444.8  5655.9  445.85  5670.5  445.59  5699.1  447.25  5730.8  447.55
#Mann= 3 ,-1 , 0
  4492.3     .05       0  5004.3     .03       0  5010.3     .05       0
#XS Ineff= 2 , 0
                         5121.86          443.25
Permanent Ineff=
       F       F
Bank Sta=4984.6,5020.2
XS Rating Curve= 0 ,0
Exp/Cntr=0.3,0.1

Type RM Length L Ch R = 1 ,4372    ,719,719,719
BEGIN DESCRIPTION:
UNT01217 IN SAND CR 9.0
END DESCRIPTION:
XS GIS Cut Line= 2
       3484095.3     10533386.95      3483522.42     10532761.99
#Sta/Elev= 30
  4571.7  440.42  4648.3  440.19    4684  440.61  4712.4  439.85  4719.2     439
  4726.6  438.63  4846.8  438.29    4861  437.65    4882  435.25  4889.4  434.75
  4938.7  433.36  4973.8   432.9  4981.2  432.91  5002.2  434.11  5020.8  431.66
  5023.5  431.16  5026.8  431.66  5044.8  434.23  5058.9  435.07  5255.7  437.22
  5306.8   437.8  5327.8  438.66  5335.2  438.38    5342   438.7  5349.4   437.9
  5356.1   438.5  5363.5  437.72  5370.3  438.04  5398.7  436.97  5419.5  437.07
#Mann= 4 ,-1 , 0
  4571.7     .05       0  5020.8     .03       0  5026.8     .05       0
  5255.7     .08       0
Bank Sta=5020.8,5026.8
XS Rating Curve= 0 ,0
Exp/Cntr=0.3,0.1

Type RM Length L Ch R = 1 ,3653    ,20,20,20
BEGIN DESCRIPTION:
UNT01217 IN SAND CR 8.1
END DESCRIPTION:
XS GIS Cut Line= 3
      3484382.29     10532584.63       3484082.8     10532415.36
      3483627.12     10532274.75
#Sta/Elev= 30
  4607.5   435.5  4661.9  435.97  4711.1  433.16  4742.7  433.53    4757  432.79
    4786  432.96  4791.8   432.4  4823.6  431.54  4845.2  429.51  4882.8  429.98
  4910.2  429.73  4926.1  428.65  4931.8  428.87  4947.7  427.35  4954.5  427.47
  4971.1  426.59  5001.6  424.86  5004.3  424.36  5007.6  424.86  5012.4  425.35
  5017.6  424.92  5050.3  426.21  5088.3  430.71  5120.8  432.38  5151.5  432.77
  5180.9  432.97  5245.3  431.81  5276.7  432.13    5329  434.38  5428.4  433.51
#Mann= 5 ,-1 , 0
  4607.5     .08       0  4971.1     .05       0  5001.6     .04       0
  5007.6     .05       0  5151.5     .08       0
Bank Sta=5001.6,5007.6
XS Rating Curve= 0 ,0
Exp/Cntr=0.3,0.1

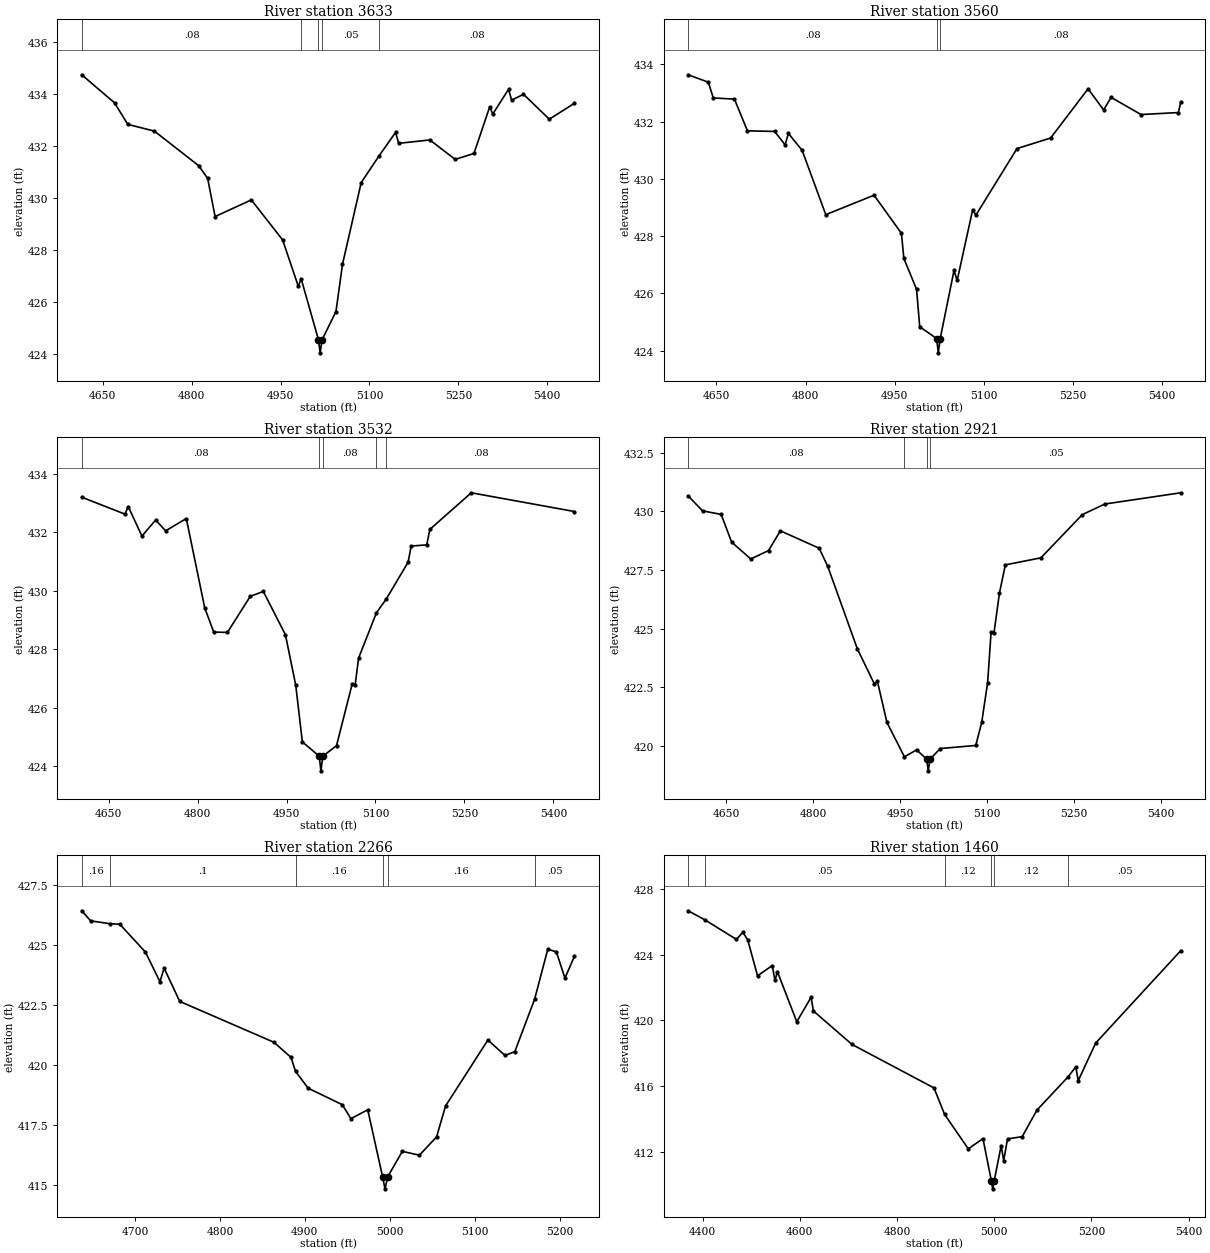
Type RM Length L Ch R = 1 ,3633    ,73,73,73
BEGIN DESCRIPTION:
UNT01217 IN SAND CR 8.0
END DESCRIPTION:
XS GIS Cut Line= 3
      3484391.37     10532546.85      3484110.15     10532403.64
      3483620.57     10532242.18
#Sta/Elev= 30
  4614.6  434.75  4669.9  433.67  4692.3  432.84  4737.2  432.58  4811.8  431.25
    4827  430.76  4839.6  429.29  4900.7  429.93  4953.5  428.39    4980   426.6
  4984.7   426.9    5014  424.54  5016.8  424.04    5020  424.54  5043.5  425.63
  5054.5  427.45  5086.1   430.6  5116.6  431.64    5144  432.53  5149.3  432.11
  5201.9  432.24  5244.6  431.49  5276.3  431.72  5302.8  433.51  5308.1  433.24
  5334.6  434.19  5339.9  433.77  5359.8     434  5403.4  433.04  5445.7  433.65
#Mann= 5 ,-1 , 0
  4614.6     .08       0  4984.7     .05       0    5014     .04       0
    5020     .05       0  5116.6     .08       0
Bank Sta=5014,5020
XS Rating Curve= 0 ,0
Exp/Cntr=0.3,0.1

Type RM Length L Ch R = 1 ,3560    ,28,28,28
BEGIN DESCRIPTION:
UNT01217 IN SAND CR 8.2
END DESCRIPTION:
XS GIS Cut Line= 3
      3484433.04     10532475.24      3484099.73     10532324.21
      3483660.95     10532176.22
#Sta/Elev= 30
  4602.4  433.64  4636.4  433.38  4644.7  432.83  4680.3  432.79  4702.2  431.68
    4748  431.66  4765.6  431.19  4771.1  431.59  4794.2     431    4834  428.75
  4915.2  429.43  4961.3   428.1  4965.4  427.22  4986.8  426.14  4992.1  424.83
  5020.6  424.42  5023.3  423.92  5026.6  424.42  5049.8   426.8  5055.1  426.45
  5081.3  428.93  5086.5  428.73  5155.8  431.06  5212.4  431.43  5275.4  433.15
  5301.6  432.41  5314.1  432.85  5364.5  432.25  5427.5  432.32  5431.4   432.7
#Mann= 3 ,-1 , 0
  4602.4     .08       0  5020.6     .07       0  5026.6     .08       0
Bank Sta=5020.6,5026.6
XS Rating Curve= 0 ,0
Exp/Cntr=0.3,0.1

Type RM Length L Ch R = 1 ,3532    ,611,611,611
BEGIN DESCRIPTION:
UNT01217 IN SAND CR 8.21
END DESCRIPTION:
XS GIS Cut Line= 3
      3484440.92     10532447.93      3484107.54     10532296.87
      3483667.41     10532148.42
#Sta/Elev= 30
  4604.8   433.2  4677.7  432.62  4683.2  432.88  4706.3  431.87  4729.4  432.42
  4746.2  432.05  4781.1  432.47  4812.1  429.42  4827.3  428.59  4850.4  428.58
  4888.9  429.81  4910.9  429.98  4948.2   428.5  4965.6  426.77  4976.7  424.84
  5005.2  424.35    5008  423.85  5011.2  424.35  5034.3  424.71  5060.5   426.8
  5065.8  426.79  5071.5   427.7  5101.6  429.25  5118.5  429.73    5155  430.98
  5160.2  431.53  5186.4  431.57  5191.7   432.1  5261.5  433.35  5435.3  432.71
#Mann= 5 ,-1 , 0
  4604.8     .08       0  5005.2     .07       0  5011.2     .08       0
  5101.6     .05       0  5118.5     .08       0
Bank Sta=5005.2,5011.2
XS Rating Curve= 0 ,0
Exp/Cntr=0.3,0.1

Type RM Length L Ch R = 1 ,2921    ,655,655,655
BEGIN DESCRIPTION:
UNT01217 IN SAND CR 6.0
END DESCRIPTION:
XS GIS Cut Line= 2
      3484532.83     10532397.37      3484361.23     10531565.39
#Sta/Elev= 30
  4584.2  430.66    4609  430.02  4641.1  429.87  4659.2  428.69  4692.2  427.97
  4722.8  428.33  4743.2  429.17  4810.1  428.43  4824.9  427.66  4875.9  424.15
  4905.5  422.64  4910.6  422.76    4927  421.01  4957.1  419.55  4978.1  419.84
  4995.5  419.45  4998.2  418.95  5001.5  419.45  5018.9   419.9  5080.2  420.03
  5090.4  421.01  5100.6   422.7  5106.6  424.86  5111.7  424.84    5121  426.52
  5131.2  427.72  5192.5  428.02  5263.9  429.86  5302.6  430.31  5433.7  430.79
#Mann= 4 ,-1 , 0
  4584.2     .08       0  4957.1     .05       0  4995.5     .03       0
  5001.5     .05       0
Bank Sta=4995.5,5001.5
XS Rating Curve= 0 ,0
Exp/Cntr=0.3,0.1

Type RM Length L Ch R = 1 ,2266    ,806,806,806
BEGIN DESCRIPTION:
UNT01217 IN SAND CR 4.0
END DESCRIPTION:
XS GIS Cut Line= 2
      3485068.49     10532246.12      3484998.17      10531670.6
#Sta/Elev= 30
  4637.4  426.42  4647.9     426  4671.1  425.88  4682.2  425.86  4712.4   424.7
  4729.4  423.47  4734.4  424.03  4752.7  422.65  4863.5  420.95  4883.7  420.32
    4889  419.74  4903.8  419.04  4944.1  418.35  4954.2  417.77    4974  418.14
  4991.5  415.35  4994.3  414.85  4997.5  415.35  5014.7  416.41  5034.8  416.25
    5055  417.01  5065.6   418.3  5115.4  421.04  5135.6   420.4  5147.1  420.56
  5170.4  422.74  5185.9  424.82    5196  424.71  5206.1  423.62  5217.2  424.52
#Mann= 6 ,-1 , 0
  4637.4     .16       0  4671.1      .1       0    4889     .16       0
  4991.5     .07       0  4997.5     .16       0  5170.4     .05       0
Bank Sta=4991.5,4997.5
XS Rating Curve= 0 ,0
Exp/Cntr=0.3,0.1

Type RM Length L Ch R = 1 ,1460    ,1236,1236,1236
BEGIN DESCRIPTION:
UNT01217 IN SAND CR 3.0
END DESCRIPTION:
XS GIS Cut Line= 2
      3485564.08     10532543.26      3485694.29     10531538.05
#Sta/Elev= 30
  4370.3  426.66  4405.9  426.09  4469.7  424.92  4482.8  425.36  4492.9  424.89
  4513.1  422.71  4543.3  423.33    4549  422.43    4554  422.96  4593.8  419.92
  4623.2   421.4  4628.2  420.57  4707.5  418.54  4876.1   415.9    4898  414.29
  4946.7   412.2  4976.9  412.82  4994.1  410.27  4996.9  409.77  5000.1  410.27
  5014.4   412.4  5019.5  411.48  5027.4   412.8  5057.6  412.94  5087.9  414.55
  5152.2  416.58  5167.9  417.18  5172.9  416.34  5208.9  418.63  5383.9  424.24
#Mann= 6 ,-1 , 0
  4370.3      .1       0  4405.9     .05       0    4898     .12       0
  4994.1     .07       0  5000.1     .12       0  5152.2     .05       0
Bank Sta=4994.1,5000.1
XS Rating Curve= 0 ,0
Exp/Cntr=0.3,0.1

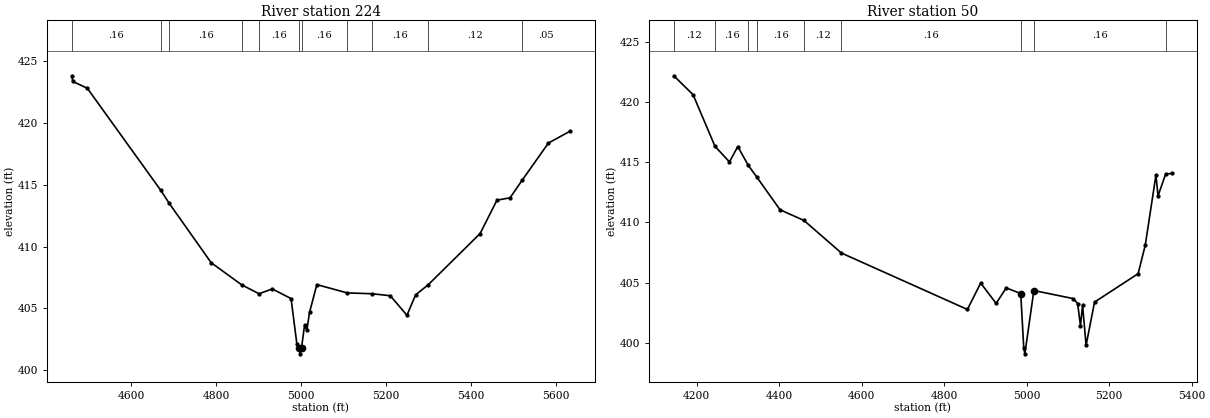
Type RM Length L Ch R = 1 ,224     ,174,174,174
BEGIN DESCRIPTION:
UNT01217 IN SAND CR 1.0
END DESCRIPTION:
XS GIS Cut Line= 4
      3485995.59     10532457.02      3486448.69     10532407.54
      3486529.42     10532220.04       3486456.5     10531712.19
#Sta/Elev= 30
  4459.9  423.82  4462.4  423.36  4496.6  422.81  4669.7  414.55  4689.8  413.49
  4788.4   408.7  4860.3  406.91  4901.2  406.19  4932.3  406.58  4976.6   405.8
  4990.2  402.14  4995.3  401.83  4998.1  401.33  5001.3  401.83  5008.3  403.63
  5013.8  403.25  5020.1  404.68  5037.3  406.93  5108.6  406.26  5167.4  406.19
  5210.3  406.03  5249.6  404.45  5269.8  406.09  5300.1  406.93  5421.9  411.06
  5461.7  413.76  5492.5  413.95  5520.6  415.35  5582.9  418.38  5632.9  419.32
#Mann= 11 ,-1 , 0
  4459.9     .16       0  4669.7     .12       0  4689.8     .16       0
  4860.3     .12       0  4901.2     .16       0  4995.3     .07       0
  5001.3     .16       0  5108.6     .12       0  5167.4     .16       0
  5300.1     .12       0  5520.6     .05       0
Bank Sta=4995.3,5001.3
XS Rating Curve= 0 ,0
Exp/Cntr=0.3,0.1

Type RM Length L Ch R = 1 ,50      ,0,0,0
BEGIN DESCRIPTION:
UNT01217 IN SAND CR 1.01
END DESCRIPTION:
XS GIS Cut Line= 4
       3485960.3     10532666.14      3486553.21     10532539.83
      3486679.08     10532218.65       3486735.5     10531969.12
#Sta/Elev= 30
  4144.5  422.16  4191.2  420.59  4244.3  416.31  4279.3  415.02  4299.7  416.29
  4324.6  414.75  4346.3  413.73    4402  411.05  4460.1  410.16  4550.8  407.46
  4856.2  402.78  4888.4  404.97  4925.9  403.28  4950.3  404.57  4985.5   404.1
  4992.8   399.6  4995.5   399.1  5017.3  404.35  5113.1  403.68  5123.4  403.27
  5130.3  401.44  5135.4  403.13  5143.9  399.81  5164.4  403.39  5270.1  405.75
  5287.4  408.12  5313.2  413.91  5318.4  412.21  5336.8  414.01  5351.5  414.06
#Mann= 9 ,-1 , 0
  4144.5     .12       0  4244.3     .16       0  4324.6     .12       0
  4346.3     .16       0  4460.1     .12       0  4550.8     .16       0
  4985.5     .07       0  5017.3     .16       0  5336.8     .12       0
Bank Sta=4985.5,5017.3
XS Rating Curve= 0 ,0
Exp/Cntr=0.3,0.1

Chan Stop Cuts=-1
Use User Specified Reach Order=0
Composite Channel Slope=5