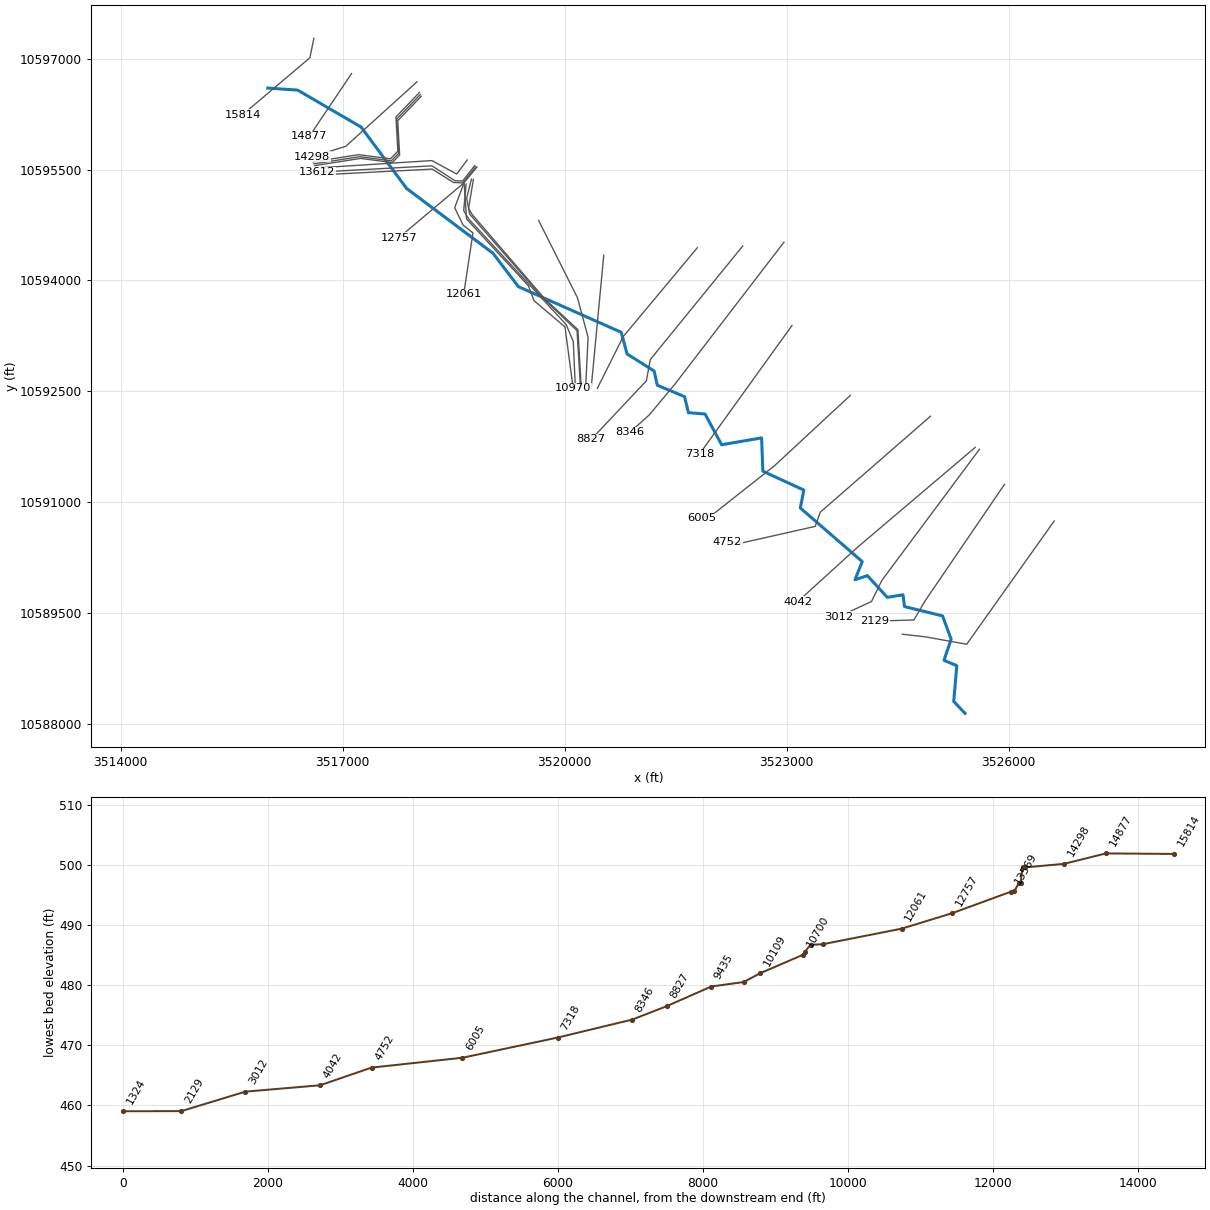
--- UNT0122 IN SAND CR.prj (project) ---

Proj Title=UNT0122 IN SAND CR Base Level Engineering
Current Plan=p01
Default Exp/Contr=0.3,0.1
English Units
Geom File=g01
Flow File=f01
Plan File=p01
Y Axis Title=Elevation
X Axis Title(PF)=Main Channel Distance
X Axis Title(XS)=Station
BEGIN DESCRIPTION:
UNT0122 IN SAND CR
END DESCRIPTION:
DSS Export Rating Curves= 0
DSS Export Rating Curve Sorted= 0
DSS Export Volume Flow Curves= 0
DXF OffsetX= 0
DXF OffsetY= 0
DXF ScaleX= 1
DXF ScaleY= 10

--- UNT0122 IN SAND CR.p01 (plan) ---

Plan Title=Multiple Run
Short Identifier=Multiple
Geom File=g01
Flow File=f01
Subcritical Flow
K Sum by GR= 0
Std Step Tol= 0.01
Critical Tol= 0.01
Num of Std Step Trials= 20
Max Error Tol= 0.3
Flow Tol Ratio= 0.001
Split Flow NTrial= 30
Split Flow Tol= 0.02
Split Flow Ratio= 0.02
Log Output Level= 0
Friction Slope Method= 1
Unsteady Friction Slope Method= 2
Unsteady Bridges Friction Slope Method= 1
Parabolic Critical Depth
Global Vel Dist=  1 , 1 , 1
Global Log Level= 0
CheckData=True
Encroach Param= -1, 0, 0, 0
BEGIN DESCRIPTION:
Multiple Run
END DESCRIPTION:

--- UNT0122 IN SAND CR.f01 (steady flow) ---

Flow Title=Multiple
Number of Profiles=7
Profile Names=10-year,25-year,50-year,1pct_min,100-year,1pct_plu,500-year
River Rch & RM= UNT0122 IN SAND ,Reach-1,15814
     634     846    1014     889    1202    1626    1682
River Rch & RM= UNT0122 IN SAND ,Reach-1,13569
     948    1291    1571    1395    1886    2551    2710
River Rch & RM= UNT0122 IN SAND ,Reach-1,9435
    1602    2239    2770    2495    3374    4563    4996
Boundary for River Rch & Prof#=UNT0122 IN SAND ,Reach-1,1
Up Type=0
Dn Type=3
Dn Slope=0.005
Boundary for River Rch & Prof#=UNT0122 IN SAND ,Reach-1,2
Up Type=0
Dn Type=3
Dn Slope=0.005
Boundary for River Rch & Prof#=UNT0122 IN SAND ,Reach-1,3
Up Type=0
Dn Type=3
Dn Slope=0.005
Boundary for River Rch & Prof#=UNT0122 IN SAND ,Reach-1,4
Up Type=0
Dn Type=3
Dn Slope=0.005
Boundary for River Rch & Prof#=UNT0122 IN SAND ,Reach-1,5
Up Type=0
Dn Type=3
Dn Slope=0.005
Boundary for River Rch & Prof#=UNT0122 IN SAND ,Reach-1,6
Up Type=0
Dn Type=3
Dn Slope=0.005
Boundary for River Rch & Prof#=UNT0122 IN SAND ,Reach-1,7
Up Type=0
Dn Type=3
Dn Slope=0.005

--- UNT0122 IN SAND CR.g01 (geometry) ---

Geom Title=Existing Conditions
Program Version=4.10

River Reach=UNT0122 IN SAND ,Reach-1
Reach XY= 30
      3515988.21     10596601.03      3516391.83     10596573.87
      3517249.17     10596074.11       3517864.2     10595243.87
      3519030.25     10594368.74      3519375.11     10593915.55
      3520763.85     10593299.19      3520843.36     10593005.79
      3521208.74       10592775.      3521252.12     10592582.11
      3521619.48     10592428.76       3521672.2     10592211.94
      3521897.06     10592193.22      3522120.92     10591777.87
      3522661.08     10591870.95      3522678.02      10591420.2
      3523231.55     10591165.09      3523184.42     10590923.01
      3524020.57     10590198.38      3523922.66     10589952.47
      3524090.28     10590008.76      3524358.93     10589714.62
      3524571.71     10589748.91      3524591.85     10589590.01
       3525105.9     10589463.43      3525222.36     10589148.99
      3525125.86     10588862.62      3525298.67     10588790.56
      3525257.58     10588307.44      3525409.47     10588145.48

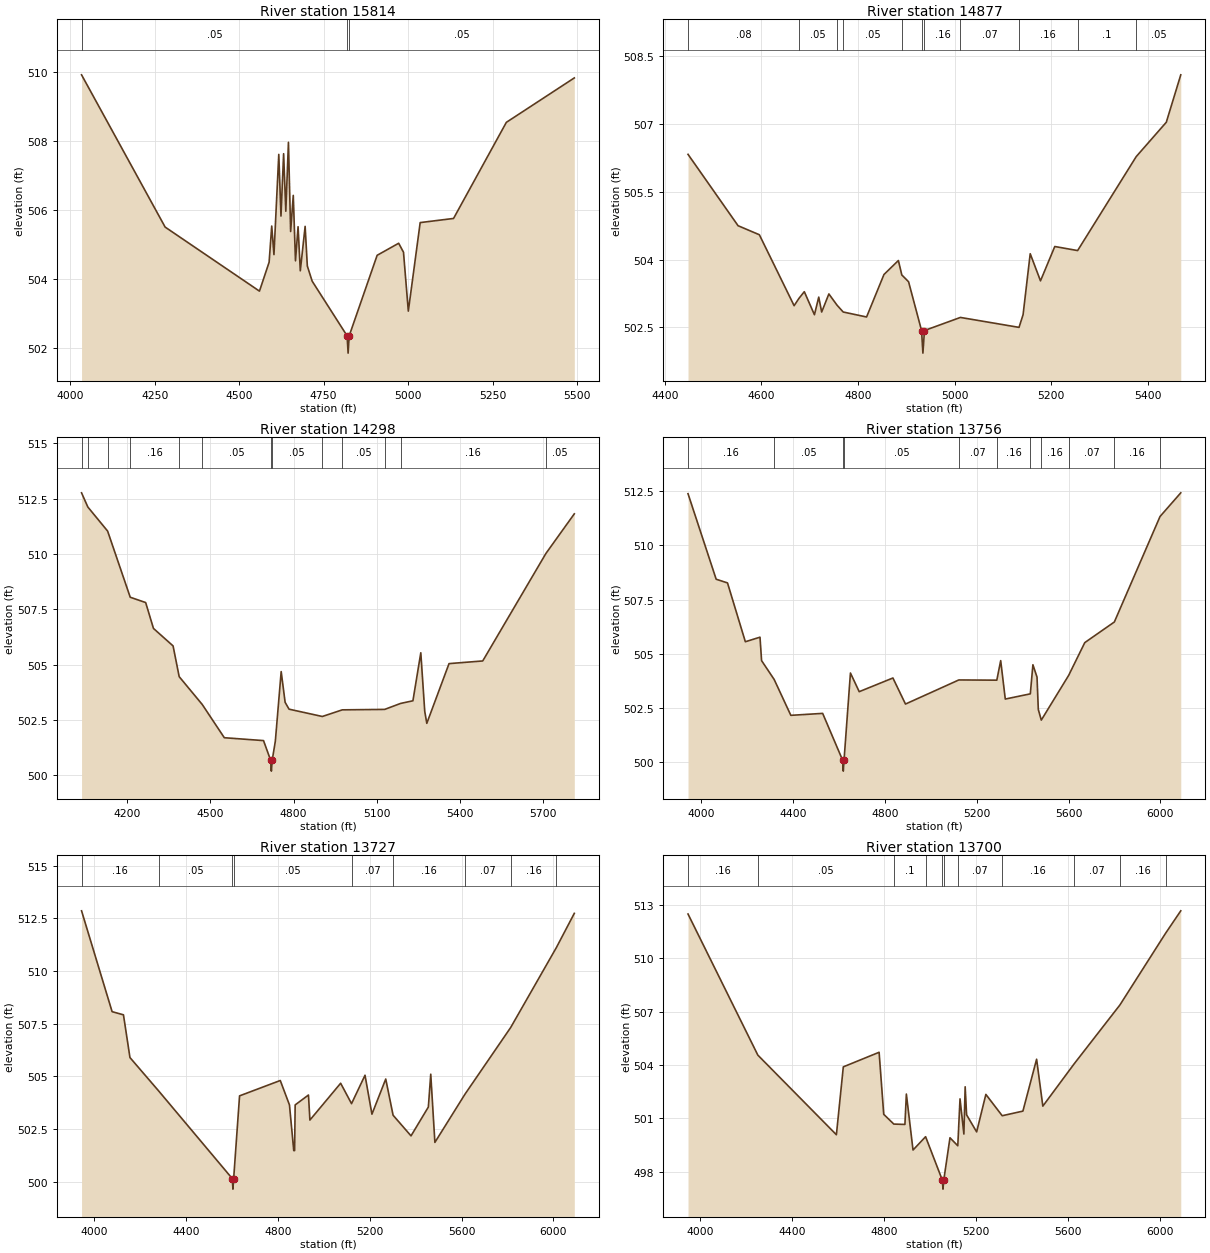
Type RM Length L Ch R = 1 ,15814   ,937,937,937
BEGIN DESCRIPTION:
UNT0122 IN SAND CR 22.0
END DESCRIPTION:
XS GIS Cut Line= 3
      3516611.38     10597273.89       3516556.9     10597010.33
      3515648.47     10596242.17
#Sta/Elev= 30
  4033.3  509.92  4280.7   505.5    4560  503.64  4588.6  504.48  4596.3  505.53
  4602.9   504.7  4617.2  507.61  4623.7  505.82  4631.5  507.63    4638  505.96
  4645.8  507.96  4652.3  505.37  4660.1  506.42  4666.6  504.52  4674.3  505.51
  4680.9  504.23  4695.2  505.52  4701.7  504.37    4716  503.93  4819.6  502.34
  4822.4  501.84  4825.6  502.34  4908.4  504.68  4972.1  505.03  4986.4  504.77
  5000.7  503.06  5035.8  505.63  5134.6  505.75  5290.9  508.54  5492.1  509.83
#Mann= 3 ,-1 , 0
  4033.3     .05       0  4819.6    .035       0  4825.6     .05       0
Bank Sta=4819.6,4825.6
XS Rating Curve= 0 ,0
Exp/Cntr=0.3,0.1

Type RM Length L Ch R = 1 ,14877   ,579,579,579
BEGIN DESCRIPTION:
UNT0122 IN SAND CR 22.1
END DESCRIPTION:
XS GIS Cut Line= 2
      3517120.68     10596797.71      3516551.24      10595950.5
#Sta/Elev= 30
  4447.9  506.33  4551.6  504.75  4595.7  504.55  4667.7  502.98  4677.6  503.14
  4688.8  503.29  4709.8  502.78  4718.7  503.17  4724.8  502.84  4739.7  503.24
  4756.7  502.99  4769.4  502.84  4817.8  502.73  4853.8  503.67  4883.7  503.98
  4890.8  503.66  4904.8  503.51  4931.7  502.43  4934.5  501.93  4937.7  502.43
  5012.2  502.72  5133.6   502.5    5142  502.78  5156.8  504.13  5178.1  503.53
  5207.7  504.29    5255   504.2  5376.4  506.28  5438.7  507.04  5468.7  508.09
#Mann= 11 ,-1 , 0
  4447.9     .08       0  4677.6     .05       0  4756.7      .1       0
  4769.4     .05       0  4890.8     .16       0  4931.7     .07       0
  4937.7     .16       0  5012.2     .07       0  5133.6     .16       0
    5255      .1       0  5376.4     .05       0
Bank Sta=4931.7,4937.7
XS Rating Curve= 0 ,0
Exp/Cntr=0.3,0.1

Type RM Length L Ch R = 1 ,14298   ,542,542,542
BEGIN DESCRIPTION:
UNT0122 IN SAND CR 22.11
END DESCRIPTION:
XS GIS Cut Line= 3
        3518004.     10596685.54      3517042.21     10595814.03
      3516587.38     10595671.67
#Sta/Elev= 30
  4036.7  512.77  4059.3  512.13  4130.6  511.04    4212  508.05  4267.6  507.81
  4295.7  506.64  4366.3  505.85  4388.3  504.46  4471.5   503.2  4550.8   501.7
    4692  501.57  4717.4  500.69  4720.2  500.19  4723.4  500.69  4734.6  501.55
  4755.6  504.69  4769.8   503.3    4784  502.99  4903.8  502.66  4975.7  502.96
  5128.4  502.98  5185.6  503.25    5230  503.37  5258.4  505.54  5272.6  502.89
    5280  502.35  5360.1  505.05  5481.4  505.17    5709  510.03  5811.2  511.82
#Mann= 13 ,-1 , 0
  4036.7     .05       0  4059.3     .16       0  4130.6     .05       0
    4212     .16       0  4388.3     .08       0  4471.5     .05       0
  4717.4    .033       0  4723.4     .05       0  4903.8     .16       0
  4975.7     .05       0  5128.4     .07       0  5185.6     .16       0
    5709     .05       0
Bank Sta=4717.4,4723.4
XS Rating Curve= 0 ,0
Exp/Cntr=0.3,0.1

Type RM Length L Ch R = 1 ,13756   ,29,29,29
BEGIN DESCRIPTION:
UNT0122 IN SAND CR 21.2
END DESCRIPTION:
XS GIS Cut Line= 6
      3518036.55     10596540.36      3517719.74     10596210.52
      3517745.78     10595746.65      3517645.14     10595644.57
      3517217.62     10595700.99      3516599.13     10595603.61
#Sta/Elev= 30
  3942.6  512.38  4065.2  508.44  4114.6  508.27  4192.3  505.56  4256.1  505.77
    4263  504.69  4317.9  503.82  4390.4  502.17    4529  502.26  4616.1   500.1
  4618.8   499.6  4622.1   500.1    4650  504.12  4688.2  503.26    4835  503.89
  4889.7  502.69  5122.1   503.8  5287.5  503.79  5304.4  504.69  5324.4  502.92
  5433.4  503.16  5444.7   504.5  5462.6  503.93  5468.2  502.44  5481.2  501.95
  5600.4  504.01  5670.6  505.52  5799.4  506.47  5998.4  511.33  6088.7  512.42
#Mann= 11 ,-1 , 0
  3942.6     .16       0  4317.9     .05       0  4616.1    .033       0
  4622.1     .05       0  5122.1     .07       0  5287.5     .16       0
  5433.4     .07       0  5481.2     .16       0  5600.4     .07       0
  5799.4     .16       0  5998.4     .05       0
Bank Sta=4616.1,4622.1
XS Rating Curve= 0 ,0
Exp/Cntr=0.3,0.1

Type RM Length L Ch R = 1 ,13727   ,27,27,27
BEGIN DESCRIPTION:
UNT0122 IN SAND CR 21.0
END DESCRIPTION:
XS GIS Cut Line= 6
      3518048.82     10596513.04      3517731.98     10596183.18
      3517758.02     10595719.31      3517657.38     10595617.22
      3517229.86     10595673.65      3516612.59     10595576.45
#Sta/Elev= 30
  3945.7  512.86  4078.7  508.07  4128.1  507.92  4156.4  505.89  4280.9  504.31
  4601.8  500.14  4604.6  499.64  4607.8  500.14  4633.5  504.07  4810.7   504.8
  4850.7  503.64  4869.4  501.47  4873.1  501.47  4875.5  503.64  4933.4  504.11
  4939.7  502.92  5073.5  504.67  5120.9   503.7  5179.6  505.05  5209.7   503.2
  5269.8  504.87  5301.8  503.15  5379.8  502.17  5455.3  503.54  5465.7   505.1
  5483.7  501.86  5614.7  504.15  5813.8  507.32  6012.8  511.12  6090.6  512.74
#Mann= 9 ,-1 , 0
  3945.7     .16       0  4280.9     .05       0  4601.8    .033       0
  4607.8     .05       0  5120.9     .07       0  5301.8     .16       0
  5614.7     .07       0  5813.8     .16       0  6012.8     .05       0
Bank Sta=4601.8,4607.8
XS Rating Curve= 0 ,0
Exp/Cntr=0.3,0.1

Type RM Length L Ch R = 1 ,13700   ,19,19,19
BEGIN DESCRIPTION:
UNT0122 IN SAND CR 21.1
END DESCRIPTION:
XS GIS Cut Line= 6
        3518061.     10596489.64      3517744.13     10596159.74
      3517770.17     10595695.87      3517669.53     10595593.79
      3517242.01     10595650.21      3516625.28      10595553.1
#Sta/Elev= 30
  3946.9  512.49  4250.8  504.55  4592.6  500.07  4622.7  503.89  4778.5  504.71
  4798.6  501.22  4842.5  500.67  4890.8  500.65  4897.1  502.36  4926.1  499.21
  4980.8  499.96  5053.8  497.51  5056.5  497.01  5059.8  497.51  5086.9   499.9
  5120.9  499.45  5130.6  502.09  5147.4  500.11    5153  502.77  5159.2  501.19
    5203  500.23  5243.1  502.34  5314.2  501.14  5404.3   501.4  5463.9  504.32
    5491  501.68  5627.3  504.06  5826.3  507.37  6025.3  511.41  6091.3  512.67
#Mann= 11 ,-1 , 0
  3946.9     .16       0  4250.8     .05       0  4842.5      .1       0
  4980.8     .05       0  5053.8    .033       0  5059.8     .05       0
  5120.9     .07       0  5314.2     .16       0  5627.3     .07       0
  5826.3     .16       0  6025.3     .05       0
Bank Sta=5053.8,5059.8
XS Rating Curve= 0 ,0
Exp/Cntr=0.3,0.1

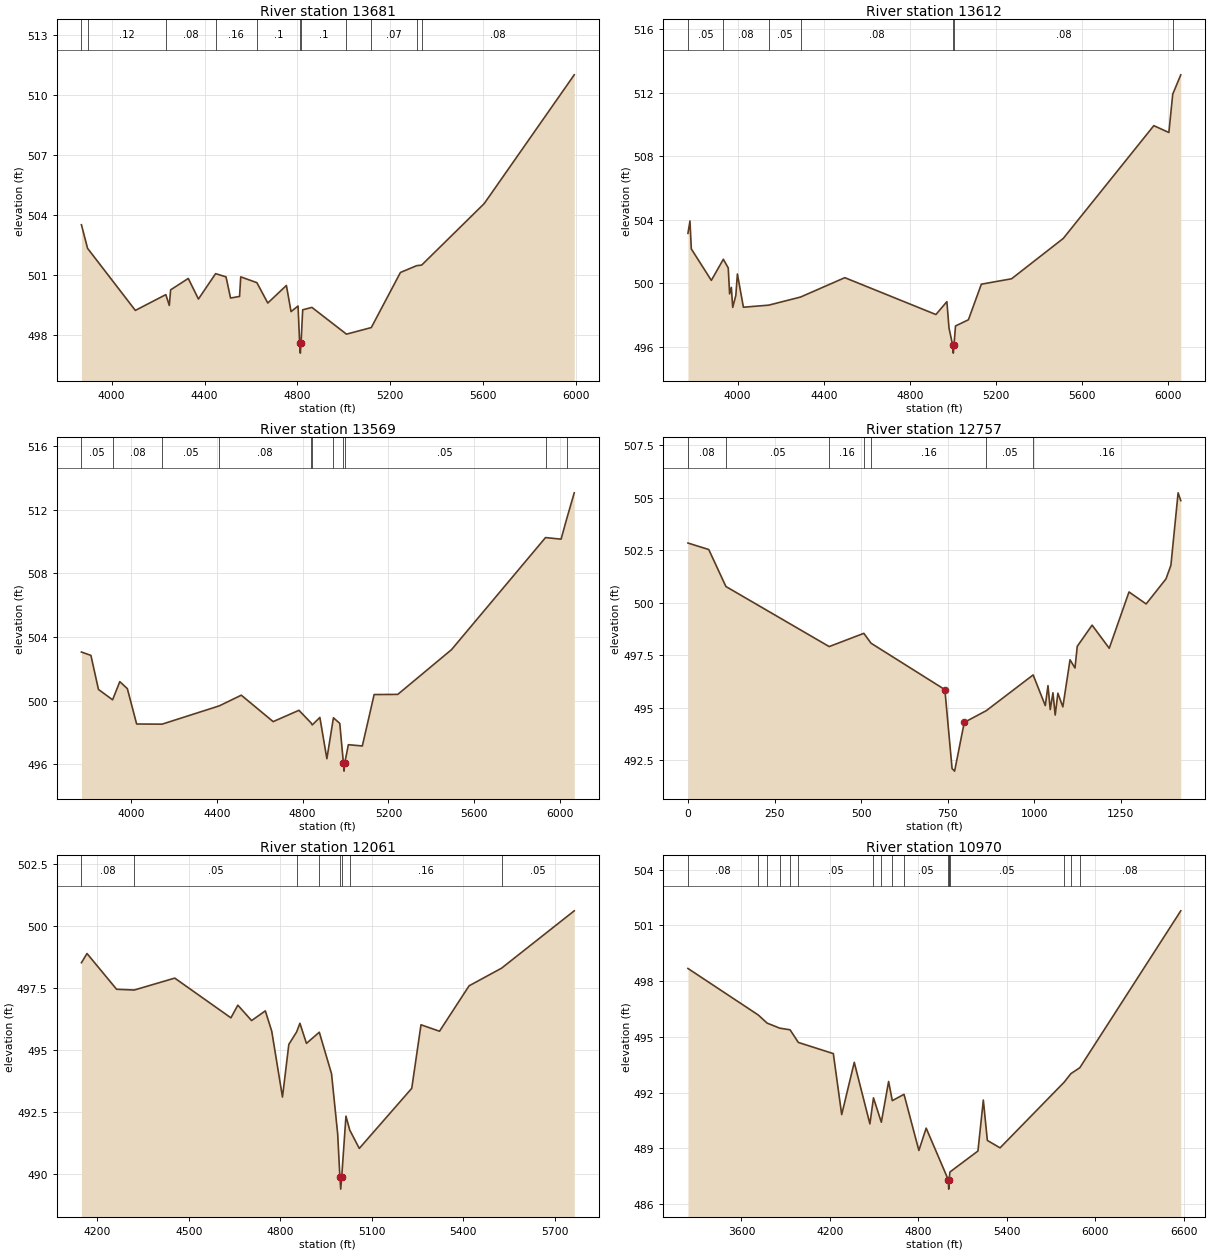
Type RM Length L Ch R = 1 ,13681   ,69,69,69
BEGIN DESCRIPTION:
UNT0122 IN SAND CR 20.0
END DESCRIPTION:
XS GIS Cut Line= 4
      3518682.86     10595628.74      3518540.99     10595438.95
      3518205.94      10595620.9      3516705.24     10595524.66
#Sta/Elev= 30
  3869.8  503.51  3896.2  502.33    4102  499.22  4233.2  500.01  4248.2  499.47
  4253.9  500.25  4329.9  500.82  4373.6  499.79  4447.5  501.06  4492.4   500.9
  4511.9  499.84  4550.7  499.92  4555.7   500.9  4625.3  500.61  4672.2  499.59
  4752.4  500.47  4772.4  499.16  4802.5  499.44  4809.5  497.58  4812.3  497.08
  4815.5  497.58  4822.5  499.25  4862.3  499.37  5011.1  498.03  5117.9  498.36
  5243.4  501.12    5313  501.46  5334.9  501.49  5604.1  504.57  5991.8  511.02
#Mann= 11 ,-1 , 0
  3869.8     .05       0  3896.2     .12       0  4233.2     .08       0
  4447.5     .16       0  4625.3      .1       0  4809.5     .07       0
  4815.5      .1       0  5011.1     .05       0  5117.9     .07       0
    5313     .16       0  5334.9     .08       0
Bank Sta=4809.5,4815.5
XS Rating Curve= 0 ,0
Exp/Cntr=0.3,0.1

Type RM Length L Ch R = 1 ,13612   ,43,43,43
BEGIN DESCRIPTION:
UNT0122 IN SAND CR 19.0
END DESCRIPTION:
XS GIS Cut Line= 5
      3518784.41     10595551.92      3518620.29     10595344.05
      3518516.12     10595349.26      3518206.23     10595549.78
      3516656.96     10595463.86
#Sta/Elev= 30
  3769.3  503.14  3778.6  503.92  3784.9  502.16  3877.9  500.18  3933.8  501.51
  3956.5  500.96  3962.9  499.33  3970.9  499.74  3977.3  498.48  3991.7  499.23
    3999  500.58    4027  498.49  4144.3  498.62  4292.3  499.13  4498.2  500.35
  4921.4  498.03  4972.4  498.84  4982.4  497.17  4999.4   496.1  5002.2   495.6
  5005.4   496.1  5012.5  497.31  5072.5   497.7  5132.6  499.94  5272.9  500.28
  5513.2  502.82  5933.9  509.92  6003.9  509.49  6021.8   511.9  6059.2  513.12
#Mann= 7 ,-1 , 0
  3769.3     .05       0  3933.8     .08       0  4144.3     .05       0
  4292.3     .08       0  4999.4     .07       0  5005.4     .08       0
  6021.8     .05       0
Bank Sta=4999.4,5005.4
XS Rating Curve= 0 ,0
Exp/Cntr=0.3,0.1

Type RM Length L Ch R = 1 ,13569   ,812,812,812
BEGIN DESCRIPTION:
UNT0122 IN SAND CR 18.0
END DESCRIPTION:
XS GIS Cut Line= 5
      3518797.45     10595537.62      3518624.45     10595319.31
      3518498.15     10595324.52      3518210.39     10595505.51
      3516660.92     10595426.08
#Sta/Elev= 30
  3769.2  503.05  3813.4  502.84  3848.6   500.7  3914.4  500.05    3948  501.19
  3983.2  500.75  4026.5  498.53    4145  498.52  4411.8  499.67  4514.1  500.34
  4662.6  498.68  4782.7  499.39  4839.8  498.59  4844.5  498.47  4880.3  498.94
  4912.9  496.35  4943.4  498.92    4973  498.57    4990  496.07  4992.8  495.57
    4996  496.07    5013  497.23  5078.1  497.15  5133.2  500.38  5243.3  500.39
  5493.7   503.2  5931.8  510.24  6004.3  510.14  6030.7  511.43  6065.6  513.05
#Mann= 11 ,-1 , 0
  3769.2     .05       0  3914.4     .08       0    4145     .05       0
  4411.8     .08       0  4839.8     .05       0  4844.5     .16       0
  4943.4     .05       0    4990     .03       0    4996     .05       0
  5931.8     .08       0  6030.7     .05       0
Bank Sta=4990,4996
XS Rating Curve= 0 ,0
Exp/Cntr=0.3,0.1

Type RM Length L Ch R = 1 ,12757   ,696,696,696
BEGIN DESCRIPTION:
UNT0122 IN SAND CR 17.0
END DESCRIPTION:
XS GIS Cut Line= 3
        3518815.     10595533.39       3518636.8     10595317.56
      3517762.82     10594580.36
#Sta/Elev= 30
       0  502.84    60.1  502.53   109.6  500.77   407.9  497.91   507.9  498.54
   528.8  498.07     742  495.86   762.8   492.1   770.1  491.98     798   494.3
   861.7  494.86   996.9  496.56    1032   495.1  1039.8  496.05  1046.3  494.91
  1054.1  495.71  1060.6  494.65  1068.4  495.69  1082.7  495.04  1103.5  497.28
  1117.8  496.89  1124.3  497.92  1167.2  498.93  1216.7  497.83  1273.8  500.51
  1323.3  499.94  1380.5  501.13  1394.8  501.78  1415.6  505.23  1423.3  504.86
#Mann= 7 ,-1 , 0
       0     .08       0   109.6     .05       0   407.9     .16       0
   507.9     .07       0   528.8     .16       0   861.7     .05       0
   996.9     .16       0
Bank Sta=742,798
XS Rating Curve= 0 ,0
Exp/Cntr=0.3,0.1

Type RM Length L Ch R = 1 ,12061   ,1091,1091,1091
BEGIN DESCRIPTION:
UNT0122 IN SAND CR 17.01
END DESCRIPTION:
XS GIS Cut Line= 5
      3518635.94     10595308.77       3518514.1      10594983.2
      3518628.69     10594747.09      3518760.63     10594642.92
       3518635.9     10593814.84
#Sta/Elev= 30
  4148.3  498.53  4166.6   498.9  4263.6  497.46  4321.5  497.43  4454.2  497.91
  4638.4  496.31    4661  496.82  4706.1   496.2  4751.2  496.59  4772.2  495.77
  4807.4  493.12  4828.2  495.24  4853.7  495.74  4864.6  496.09    4886  495.28
  4928.1  495.73  4968.2  494.06  4988.4  491.63  4995.6  489.91  4998.3  489.41
  5001.6  489.91  5015.5  492.35  5027.9  491.79  5059.2  491.05  5231.2  493.47
  5261.5  496.03  5322.2  495.77  5419.2   497.6  5525.6  498.31  5763.9  500.62
#Mann= 8 ,-1 , 0
  4148.3     .08       0  4321.5     .05       0  4853.7     .12       0
  4928.1     .05       0  4995.6     .03       0  5001.6     .05       0
  5027.9     .16       0  5525.6     .05       0
Bank Sta=4995.6,5001.6
XS Rating Curve= 0 ,0
Exp/Cntr=0.3,0.1

Type RM Length L Ch R = 1 ,10970   ,164,164,164
BEGIN DESCRIPTION:
UNT0122 IN SAND CR 16.0
END DESCRIPTION:
XS GIS Cut Line= 6
      3518641.38     10595311.16      3518674.36     10594830.24
      3519510.93     10593926.65      3519585.24     10593727.34
      3520004.34      10593371.7      3520115.01     10592540.59
#Sta/Elev= 30
  3236.9  498.68  3713.4  496.18  3774.2  495.74  3859.3  495.47  3929.9  495.38
  3986.1   494.7  4223.3   494.1  4280.1  490.82  4365.3  493.63  4471.4  490.32
  4495.7  491.72  4548.9  490.41  4598.4   492.6  4623.4  491.57    4703  491.91
  4803.7  488.89  4853.3  490.09  5003.5  487.31  5006.3  486.81  5009.5  487.31
  5011.1  487.47  5014.2  487.73  5204.5  488.86  5241.1   491.6  5268.4  489.43
  5354.6  489.03  5790.5  492.57  5834.8  493.02  5895.7  493.34  6580.8  501.78
#Mann= 17 ,-1 , 0
  3236.9     .08       0  3713.4     .05       0  3774.2     .08       0
  3859.3     .12       0  3929.9     .08       0  3986.1     .05       0
  4495.7      .1       0  4548.9     .05       0  4623.4      .1       0
    4703     .05       0  5003.5     .04       0  5009.5     .05       0
  5011.1     .12       0  5014.2     .05       0  5790.5     .08       0
  5834.8     .05       0  5895.7     .08       0
Bank Sta=5003.5,5009.5
XS Rating Curve= 0 ,0
Exp/Cntr=0.3,0.1

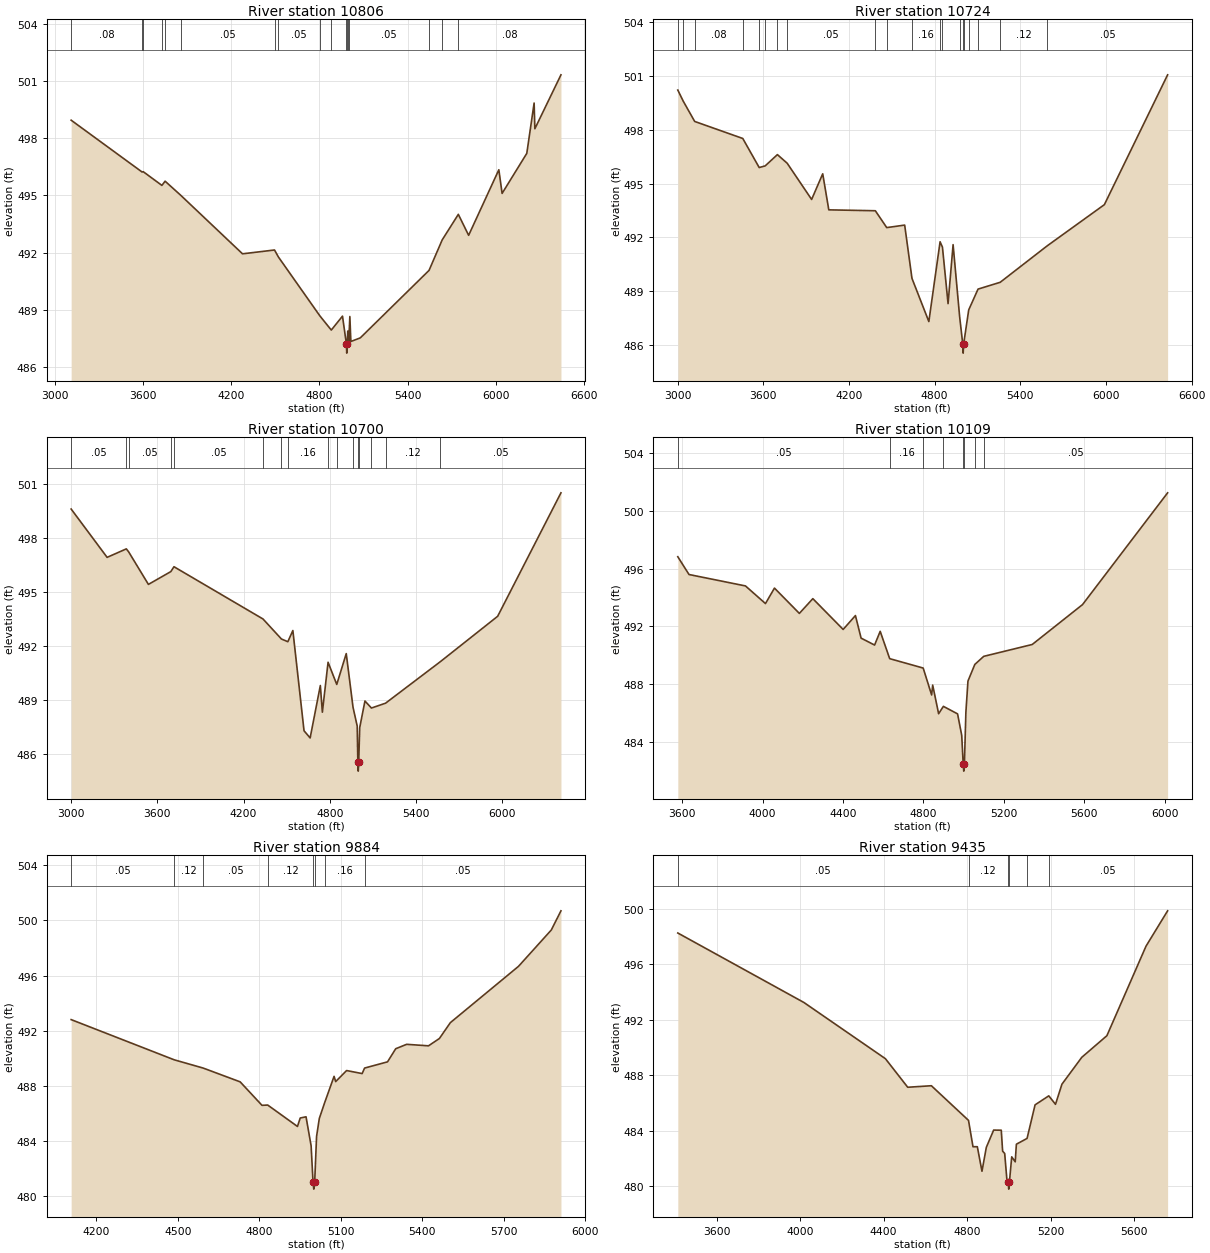
Type RM Length L Ch R = 1 ,10806   ,82,82,82
BEGIN DESCRIPTION:
UNT0122 IN SAND CR 17.1
END DESCRIPTION:
XS GIS Cut Line= 6
      3518668.44     10595302.86      3518635.89     10594943.52
       3518706.2     10594827.64      3520020.01     10593403.16
      3520116.36     10593173.99      3520145.01     10592529.47
#Sta/Elev= 30
  3111.7  498.95  3594.5  496.23  3601.9  496.25    3729  495.53  3750.9  495.75
  3857.3  495.01  4277.5  491.94  4495.2  492.14    4522  491.77  4804.2  488.68
  4881.5  487.94  4957.7  488.67  4983.9  487.23  4986.7  486.73  4989.9  487.23
  4993.6  487.89  5000.3  487.38  5007.8  488.65  5014.6  487.34  5078.8  487.53
  5546.5  491.07    5636  492.67  5745.8  494.01  5815.9  492.91  6021.4  496.35
  6043.6  495.11  6211.6  497.21  6261.4  499.85  6266.4   498.5    6444  501.33
#Mann= 17 ,-1 , 0
  3111.7     .08       0  3594.5     .05       0  3601.9     .08       0
    3729     .12       0  3750.9     .08       0  3857.3     .05       0
  4495.2      .1       0    4522     .05       0  4804.2     .16       0
  4881.5     .05       0  4983.9     .07       0  4989.9     .05       0
  4993.6     .16       0  5000.3     .05       0  5546.5     .12       0
    5636     .05       0  5745.8     .08       0
Bank Sta=4983.9,4989.9
XS Rating Curve= 0 ,0
Exp/Cntr=0.3,0.1

Type RM Length L Ch R = 1 ,10724   ,24,24,24
BEGIN DESCRIPTION:
UNT0122 IN SAND CR 15.0
END DESCRIPTION:
XS GIS Cut Line= 6
      3518740.14     10595369.79       3518675.9     10595112.82
      3518715.83     10594897.54      3519713.23     10593755.18
      3520167.22     10593320.29       3520214.1       10592539.
#Sta/Elev= 30
  3001.5  500.22  3038.9  499.61  3119.7  498.47  3456.5  497.52  3571.4   495.9
    3613  495.99    3699  496.62  3767.4  496.14  3938.6  494.12  4016.3  495.55
  4058.9  493.54  4384.8  493.49  4464.6  492.55  4590.2  492.69  4641.3  489.72
  4759.5  487.31  4838.2  491.76  4854.8  491.46  4894.1  488.31  4929.3   491.6
  4975.2  487.58  4997.1  486.05  4999.9  485.55  5003.1  486.05  5038.7  487.96
    5104  489.12  5259.1   489.5  5587.9  491.53  5988.7  493.83  6431.6  501.07
#Mann= 20 ,-1 , 0
  3001.5     .08       0  3038.9     .05       0  3119.7     .08       0
  3456.5     .05       0  3571.4     .08       0    3613     .05       0
    3699     .08       0  3767.4     .05       0  4384.8     .16       0
  4464.6     .05       0  4641.3     .16       0  4838.2     .05       0
  4854.8     .16       0  4975.2     .05       0  4997.1     .04       0
  5003.1     .05       0  5038.7     .12       0    5104     .05       0
  5259.1     .12       0  5587.9     .05       0
Bank Sta=4997.1,5003.1
XS Rating Curve= 0 ,0
Exp/Cntr=0.3,0.1

Type RM Length L Ch R = 1 ,10700   ,591,591,591
BEGIN DESCRIPTION:
UNT0122 IN SAND CR 14.0
END DESCRIPTION:
XS GIS Cut Line= 6
      3518766.62     10595365.91      3518701.51     10594973.93
      3518752.29      10594889.3      3519734.23     10593747.63
      3520179.37     10593333.83      3520223.64     10592551.28
#Sta/Elev= 30
  3000.7   499.6  3250.9  496.92  3384.6  497.39  3400.4  497.23  3538.3  495.42
  3694.3  496.13  3716.2   496.4  4335.8   493.5    4464  492.39  4508.6  492.24
  4543.5  492.86  4621.2   487.3  4663.7   486.9  4734.7  489.81  4748.8  488.33
  4788.5   491.1  4848.9  489.87    4915  491.58  4962.2   488.6  4991.2  487.56
  4995.7  485.56  4998.4  485.06  5001.7  485.56  5008.6  487.47  5045.1  488.95
  5090.3  488.56  5188.7  488.83  5569.4  491.13  5968.6  493.65  6409.1   500.5
#Mann= 16 ,-1 , 0
  3000.7     .05       0  3384.6     .08       0  3400.4     .05       0
  3694.3     .08       0  3716.2     .05       0  4335.8     .16       0
    4464     .05       0  4508.6     .16       0  4788.5     .05       0
  4848.9     .16       0  4962.2     .05       0  4995.7     .07       0
  5001.7     .05       0  5090.3     .05       0  5188.7     .12       0
  5569.4     .05       0
Bank Sta=4995.7,5001.7
XS Rating Curve= 0 ,0
Exp/Cntr=0.3,0.1

Type RM Length L Ch R = 1 ,10109   ,225,225,225
BEGIN DESCRIPTION:
UNT0122 IN SAND CR 13.0
END DESCRIPTION:
XS GIS Cut Line= 4
      3519648.11     10594811.42       3520173.3     10593764.53
      3520316.53     10593230.68      3520281.81      10592518.9
#Sta/Elev= 30
  3578.5  496.82  3634.2  495.59  3915.1   494.8  4014.6  493.58  4059.3  494.65
  4183.2   492.9  4250.2  493.92    4401  491.79  4462.1  492.75  4490.3  491.19
  4557.4  490.71  4585.3  491.66  4632.5  489.77  4799.1  489.12  4841.2  487.26
  4846.4  487.94    4876  485.96  4899.6  486.47  4970.2  485.95  4990.8  484.47
  4998.2  482.49    5001  481.99  5004.2  482.49  5011.6  486.07  5021.9  488.22
    5056  489.37  5100.5  489.93  5341.6  490.75  5591.9  493.51  6015.1  501.24
#Mann= 8 ,-1 , 0
  3578.5     .05       0  4632.5     .16       0  4799.1     .05       0
  4899.6     .12       0  4998.2     .07       0  5004.2     .12       0
    5056     .16       0  5100.5     .05       0
Bank Sta=4998.2,5004.2
XS Rating Curve= 0 ,0
Exp/Cntr=0.3,0.1

Type RM Length L Ch R = 1 ,9884    ,449,449,449
BEGIN DESCRIPTION:
UNT0122 IN SAND CR 12.0
END DESCRIPTION:
XS GIS Cut Line= 2
      3520528.33     10594340.94      3520358.23     10592546.18
#Sta/Elev= 30
  4107.3  492.81  4486.3   489.9  4593.2   489.3  4729.4   488.3  4809.7   486.6
  4830.8  486.62  4940.3  485.07  4950.4  485.68  4971.8  485.77  4990.5  483.67
  4997.6  481.03  5000.3  480.53  5003.6  481.03  5010.6  484.35  5020.7  485.65
  5040.5   486.8    5075   488.7  5080.9  488.32  5121.1  489.12  5178.3   488.9
  5187.4   489.3  5271.8  489.75  5301.9   490.7  5342.1  491.02  5422.5  490.91
  5462.6  491.44    5503  492.59  5753.9  496.67  5874.5   499.3  5910.1  500.69
#Mann= 8 ,-1 , 0
  4107.3     .05       0  4486.3     .12       0  4593.2     .05       0
  4830.8     .12       0  4997.6     .07       0  5003.6     .12       0
  5040.5     .16       0  5187.4     .05       0
Bank Sta=4997.6,5003.6
XS Rating Curve= 0 ,0
Exp/Cntr=0.3,0.1

Type RM Length L Ch R = 1 ,9435    ,608,608,608
BEGIN DESCRIPTION:
UNT0122 IN SAND CR 11.0
END DESCRIPTION:
XS GIS Cut Line= 3
       3521792.1     10594441.64      3520792.11     10593241.64
      3520442.09     10592541.62
#Sta/Elev= 30
  3414.5  498.26  4017.8  493.25  4408.4  489.19  4515.1  487.13  4628.3  487.24
  4806.1  484.74  4827.5  482.84  4848.3  482.84  4870.5  481.07  4891.3  482.79
  4926.4  484.04  4962.9  484.03  4969.4  482.52  4979.3  482.35  4990.5  480.34
  4995.9  480.28  4998.7  479.78  5001.9  480.28  5012.9  482.11  5029.7  481.75
  5035.2  483.02  5086.4  483.44  5124.7  485.86  5190.3  486.51  5222.5   485.9
  5253.3  487.35  5348.3  489.29  5468.5  490.85  5655.8  497.31  5759.2  499.86
#Mann= 6 ,-1 , 0
  3414.5     .05       0  4806.1     .12       0  4995.9     .07       0
  5001.9     .12       0  5086.4     .16       0  5190.3     .05       0
Bank Sta=4995.9,5001.9
XS Rating Curve= 0 ,0
Exp/Cntr=0.3,0.1

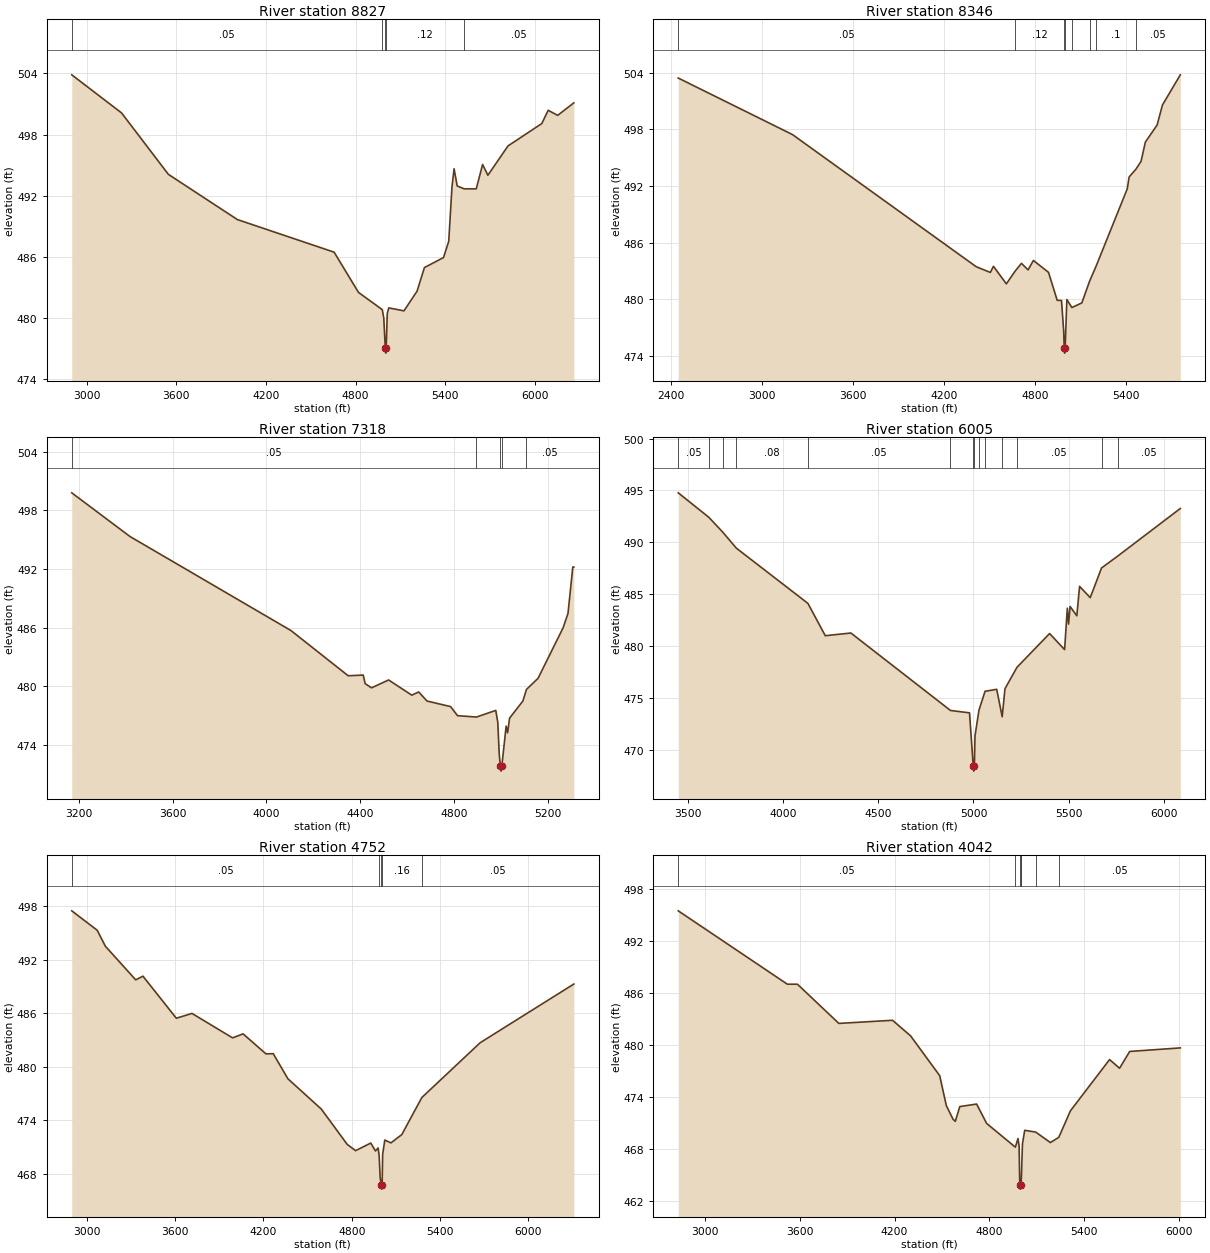
Type RM Length L Ch R = 1 ,8827    ,481,481,481
BEGIN DESCRIPTION:
UNT0122 IN SAND CR 10.0
END DESCRIPTION:
XS GIS Cut Line= 4
       3522406.6     10594465.96      3521156.58     10592929.46
      3521104.49       10592643.      3520359.67      10591851.3
#Sta/Elev= 30
  2901.4  503.86  3234.5  500.12  3547.7  494.09  4009.5  489.65  4656.6  486.45
  4819.6   482.5  4978.8  480.81  4988.8  479.99  4998.9  477.04  5001.7  476.54
  5004.9  477.04  5012.1  480.43  5022.2  480.98  5123.9  480.69  5211.4  482.62
  5260.7  484.94  5388.2  485.92  5423.4  487.52  5444.8  492.82    5459  494.64
    5480  492.95    5526  492.67  5607.5  492.67    5650  495.06  5685.2     494
  5819.9  496.88  6046.1  499.08  6088.6  500.38  6152.1  499.88  6260.3  501.11
#Mann= 5 ,-1 , 0
  2901.4     .05       0  4978.8     .12       0  4998.9     .07       0
  5004.9     .12       0    5526     .05       0
Bank Sta=4998.9,5004.9
XS Rating Curve= 0 ,0
Exp/Cntr=0.3,0.1

Type RM Length L Ch R = 1 ,8346    ,1028,1028,1028
BEGIN DESCRIPTION:
UNT0122 IN SAND CR 9.0
END DESCRIPTION:
XS GIS Cut Line= 4
      3522963.89     10594518.04       3521484.7     10592590.92
      3521146.16     10592184.67      3520881.42     10591945.88
#Sta/Elev= 30
  2446.6  503.43  3200.8  497.44  4413.5  483.44  4506.9  482.83  4527.7  483.48
  4612.9  481.62  4672.7  483.01  4712.6  483.79  4756.2   483.1  4791.5   484.1
  4891.2  482.84  4948.5  479.88  4977.1  479.85  4991.4   476.6  4994.9  474.78
  4997.7  474.28  5000.9  474.78  5012.2  479.96  5045.4  479.11  5111.2   479.6
  5161.8  481.88    5205  483.48  5410.8  491.68  5423.7  492.95  5468.2  493.77
  5502.1   494.6  5530.5  496.64  5608.2  498.45  5643.3  500.57  5761.3  503.77
#Mann= 8 ,-1 , 0
  2446.6     .05       0  4672.7     .12       0  4994.9     .07       0
  5000.9     .12       0  5045.4     .16       0  5161.8     .05       0
    5205      .1       0  5468.2     .05       0
Bank Sta=4994.9,5000.9
XS Rating Curve= 0 ,0
Exp/Cntr=0.3,0.1

Type RM Length L Ch R = 1 ,7318    ,1313,1313,1313
BEGIN DESCRIPTION:
UNT0122 IN SAND CR 7.0
END DESCRIPTION:
XS GIS Cut Line= 2
      3523070.92      10593389.7       3521820.2     10591649.54
#Sta/Elev= 30
    3169   499.8  3417.2  495.33  4104.7  485.69  4348.8  481.06  4412.9  481.13
  4421.4  480.25  4448.5  479.82  4521.3  480.63  4620.4  479.07  4649.8   479.4
  4685.4  478.47  4786.1   477.9  4815.5  476.97  4896.4  476.83  4978.8  477.51
  4987.4  476.28  4993.6  473.01  4998.5  471.79  5001.3  471.29  5004.5  471.79
    5023   475.9  5029.2  475.22  5037.7  476.72  5094.2  478.46  5109.9  479.66
  5159.3   480.8  5266.1  485.97    5287  487.44  5307.6   492.2    5312   492.2
#Mann= 5 ,-1 , 0
    3169     .05       0  4896.4     .12       0  4998.5     .07       0
  5004.5     .12       0  5109.9     .05       0
Bank Sta=4998.5,5004.5
XS Rating Curve= 0 ,0
Exp/Cntr=0.3,0.1

Type RM Length L Ch R = 1 ,6005    ,1253,1253,1253
BEGIN DESCRIPTION:
UNT0122 IN SAND CR 4.0
END DESCRIPTION:
XS GIS Cut Line= 6
      3523859.68     10592445.07      3522838.87     10591497.17
      3522015.95     10590846.13      3521943.03      10590825.3
      3521943.03     10590814.88      3521859.71     10590783.63
#Sta/Elev= 30
    3450  494.77    3610  492.42  3683.7  490.98  3755.4  489.43  4130.8  484.11
  4222.1  480.99  4356.5  481.25  4879.5  473.78  4979.4  473.55  4998.9  468.43
  5001.7  467.93  5004.9  468.43  5008.3  471.34  5029.2  473.82    5061  475.63
  5122.2  475.82    5151  473.17  5165.6  475.88  5228.9  477.95  5399.9   481.2
  5478.6  479.65    5493  483.64  5499.4  482.11  5507.5  483.81  5542.8  482.91
  5557.3  485.75  5613.3  484.66  5672.5  487.52  5759.8   488.7  6086.2  493.26
#Mann= 14 ,-1 , 0
    3450     .05       0    3610     .08       0  3683.7     .05       0
  3755.4     .08       0  4130.8     .05       0  4879.5     .16       0
  4998.9     .07       0  5004.9     .16       0  5029.2     .12       0
    5061     .05       0    5151     .16       0  5228.9     .05       0
  5672.5     .16       0  5759.8     .05       0
Bank Sta=4998.9,5004.9
XS Rating Curve= 0 ,0
Exp/Cntr=0.3,0.1

Type RM Length L Ch R = 1 ,4752    ,710,710,710
BEGIN DESCRIPTION:
UNT0122 IN SAND CR 2.0
END DESCRIPTION:
XS GIS Cut Line= 6
      3524943.06     10592163.86      3523453.95     10590866.21
      3523385.74     10590674.25      3522370.12     10590445.09
      3522380.53     10590445.09      3522198.28     10590465.92
#Sta/Elev= 30
  2896.5  497.46  3069.2  495.29  3125.2  493.49  3331.3  489.73  3380.6  490.14
  3607.5  485.43  3713.9  485.97  3990.1  483.23  4061.3  483.68    4217  481.44
  4266.4  481.46  4366.1  478.65    4593  475.26  4769.6   471.3  4826.5   470.6
  4929.6  471.45  4961.4  470.56  4979.5   470.9  4986.5  470.07  4993.3  467.59
  5000.9  466.79  5003.6  466.29  5006.9  466.79  5010.4  470.21  5025.1  471.79
  5066.8  471.47  5140.6   472.4  5276.8  476.55  5673.7  482.69  6310.4  489.26
#Mann= 5 ,-1 , 0
  2896.5     .05       0  4986.5     .16       0  5000.9     .07       0
  5006.9     .16       0  5276.8     .05       0
Bank Sta=5000.9,5006.9
XS Rating Curve= 0 ,0
Exp/Cntr=0.3,0.1

Type RM Length L Ch R = 1 ,4042    ,1030,1030,1030
BEGIN DESCRIPTION:
UNT0122 IN SAND CR 3.0
END DESCRIPTION:
XS GIS Cut Line= 3
      3525547.19     10591741.96      3523958.66       10590393.
      3523146.61     10589653.83
#Sta/Elev= 30
  2828.8  495.51  3520.5  487.03  3584.2  487.03  3846.7   482.5  4187.2  482.86
  4301.5  481.06    4486  476.46  4527.8  473.01  4570.5  471.43  4584.8  471.18
  4613.4  472.89  4719.9  473.18  4783.6  470.94  4965.5   468.2  4982.1   469.2
  4989.3   468.3  4993.3  463.85    4996  463.35  4999.3  463.85  5002.7  464.12
  5010.5  468.57  5024.7  470.15  5094.6  469.94  5187.5  468.73    5241  469.34
  5314.5   472.4  5562.5  478.32    5626  477.32  5690.2  479.26  6010.9  479.67
#Mann= 7 ,-1 , 0
  2828.8     .05       0  4965.5     .16       0  4993.3     .07       0
  4999.3     .16       0  5002.7     .12       0  5094.6     .16       0
    5241     .05       0
Bank Sta=4993.3,4999.3
XS Rating Curve= 0 ,0
Exp/Cntr=0.3,0.1

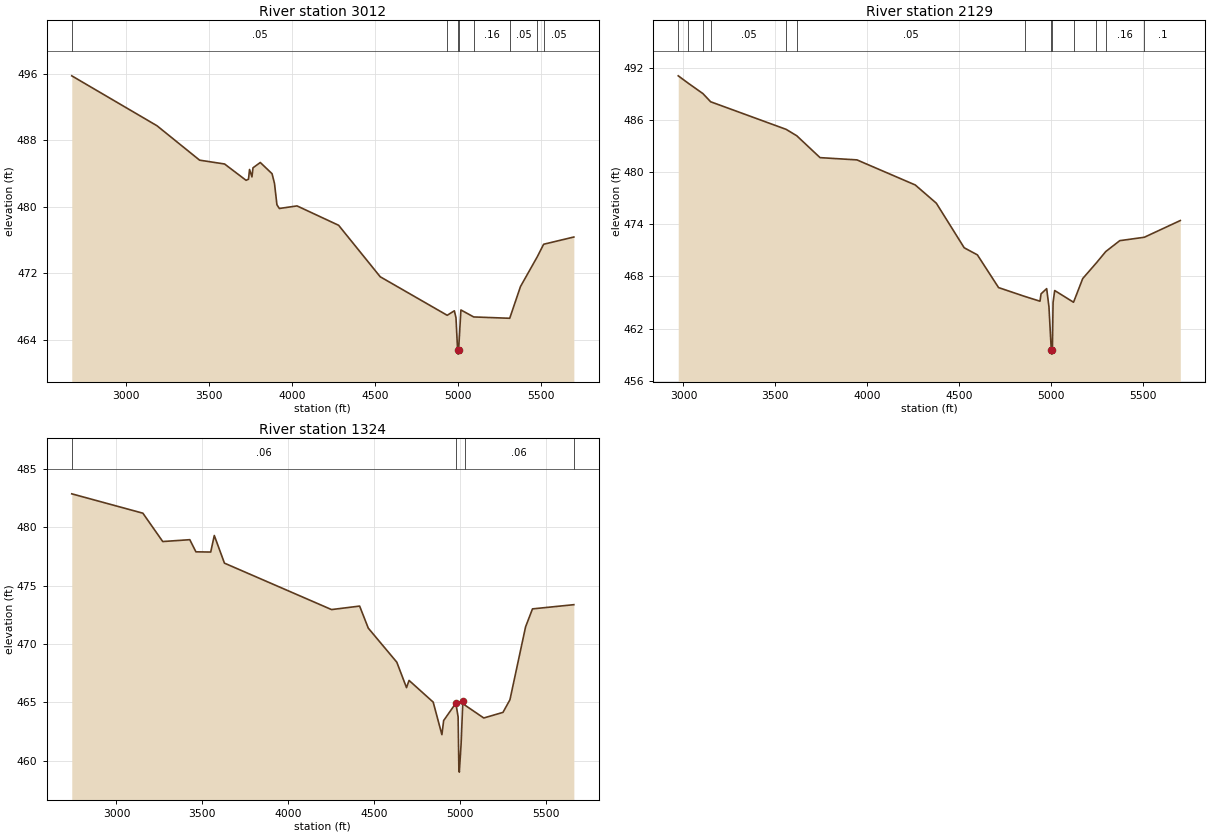
Type RM Length L Ch R = 1 ,3012    ,883,883,883
BEGIN DESCRIPTION:
UNT0122 IN SAND CR 1.1
END DESCRIPTION:
XS GIS Cut Line= 4
       3525604.5     10591715.93      3524286.78     10589945.09
      3524146.16     10589658.63      3523698.26     10589450.31
#Sta/Elev= 30
  2676.5  495.75    3189  489.75  3445.6  485.61  3595.7  485.15    3725  483.19
  3739.7  483.32  3745.9  484.49  3760.5   483.6  3766.7  484.69  3810.6  485.33
  3881.4  483.98  3896.1  482.81  3910.7  480.25  3925.3   479.8  4031.6  480.11
  4281.9  477.78  4532.2  471.59    4935  466.96  4978.1   467.5  4987.9  466.66
  4997.6  462.79  5000.3  462.29  5003.6  462.79  5017.5   467.6  5094.5  466.76
  5311.1   466.6    5376  470.42  5477.6  474.02  5515.2   475.5  5696.9  476.37
#Mann= 8 ,-1 , 0
  2676.5     .05       0    4935     .12       0  4997.6     .07       0
  5003.6     .12       0  5094.5     .16       0  5311.1     .05       0
  5477.6     .12       0  5515.2     .05       0
Bank Sta=4997.6,5003.6
XS Rating Curve= 0 ,0
Exp/Cntr=0.3,0.1

Type RM Length L Ch R = 1 ,2129    ,805,805,805
BEGIN DESCRIPTION:
UNT0122 IN SAND CR 2.1
END DESCRIPTION:
XS GIS Cut Line= 4
      3525943.03     10591241.96      3524875.33     10589674.25
      3524719.08     10589408.63      3524193.04       10589393.
#Sta/Elev= 30
  2971.7  491.13  3026.1  490.28  3106.1  489.08    3148  488.14  3558.6  484.96
  3616.5  484.22  3743.2   481.7  3943.8  481.44    4261  478.55  4375.6  476.45
  4527.3  471.31  4599.1  470.49  4714.3  466.72  4855.4  465.71  4939.6  465.15
  4945.4     466  4975.9   466.6  4988.3  464.52    5001  459.55  5003.7  459.05
    5007  459.55  5010.7     465  5019.6  466.38  5122.1  465.03    5172  467.76
    5246  469.56  5297.6  470.88  5373.7  472.13  5506.9  472.52  5702.9  474.45
#Mann= 13 ,-1 , 0
  2971.7     .16       0  3026.1      .1       0  3106.1     .16       0
    3148     .05       0  3558.6      .1       0  3616.5     .05       0
  4855.4     .12       0    5001     .07       0    5007     .12       0
  5122.1      .1       0    5246     .12       0  5297.6     .16       0
  5506.9      .1       0
Bank Sta=5001,5007
XS Rating Curve= 0 ,0
Exp/Cntr=0.3,0.1

Type RM Length L Ch R = 1 ,1324    ,0,0,0
BEGIN DESCRIPTION:
UNT0122 IN SAND CR 1.0
END DESCRIPTION:
XS GIS Cut Line= 4
      3526614.89     10590747.15      3525432.62      10589080.5
      3524880.53     10589179.46       3524562.8     10589215.92
#Sta/Elev= 30
  2739.7  482.88  3153.9  481.22  3269.6  478.79  3427.1  478.95  3462.7  477.91
  3548.9  477.89  3569.8  479.31  3628.9  476.94  4252.6  472.96  4416.2  473.26
  4466.6  471.37  4632.8  468.45  4689.3  466.27  4704.1  466.89  4844.6  465.03
  4895.4  462.24  4905.5  463.45  4976.6  464.94  4989.9  463.75    4994  459.53
  4996.7  459.03  5007.1  461.41  5017.3  465.09  5027.4  464.79  5139.2  463.67
    5251  464.15  5291.6  465.23  5382.7  471.48  5422.9  473.02  5663.8  473.38
#Mann= 4 ,-1 , 0
  2739.7     .06       0  4976.6     .04       0  5027.4     .06       0
  5663.8     .16       0
Bank Sta=4976.6,5017.3
XS Rating Curve= 0 ,0
Exp/Cntr=0.3,0.1

Chan Stop Cuts=-1
Use User Specified Reach Order=0
Composite Channel Slope=5