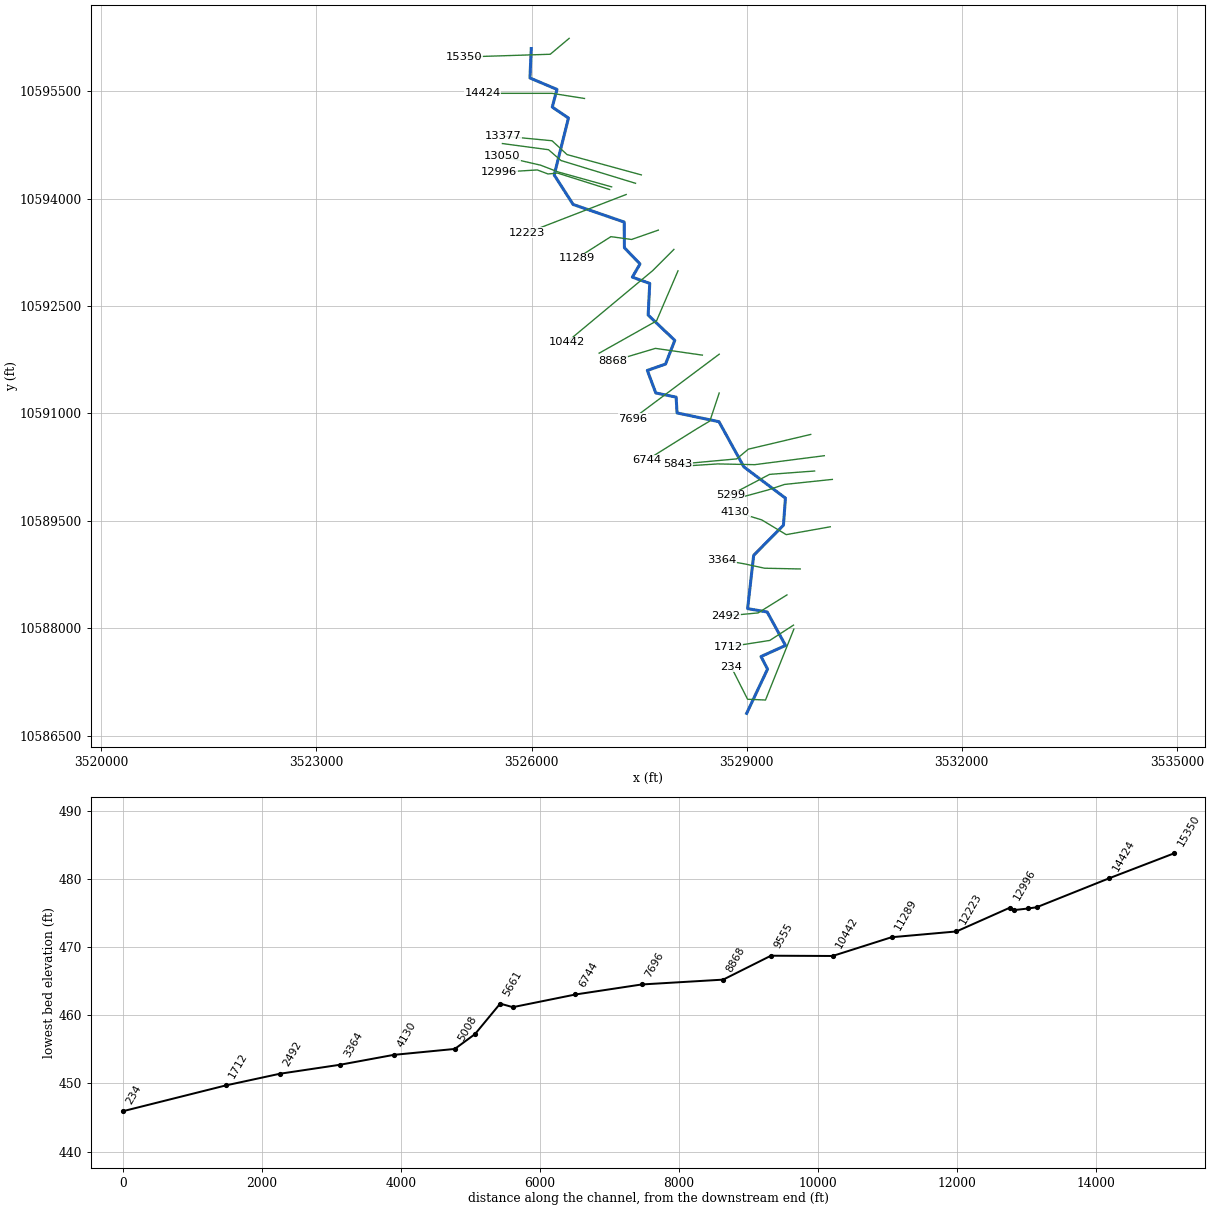
--- UNT0123 IN SAND CR.prj (project) ---

Proj Title=UNT0123 IN SAND CR Base Level Engineering
Current Plan=p01
Default Exp/Contr=0.3,0.1
English Units
Geom File=g01
Flow File=f01
Plan File=p01
BEGIN DESCRIPTION:
UNT0123 IN SAND CR
END DESCRIPTION:

--- UNT0123 IN SAND CR.p01 (plan) ---

Plan Title=Multiple Run
Short Identifier=Multiple
Geom File=g01
Flow File=f01
Subcritical Flow
K Sum by GR= 0
Std Step Tol= 0.01
Critical Tol= 0.01
Num of Std Step Trials= 20
Max Error Tol= 0.3
Flow Tol Ratio= 0.001
Split Flow NTrial= 30
Split Flow Tol= 0.02
Split Flow Ratio= 0.02
Log Output Level= 0
Friction Slope Method= 1
Unsteady Friction Slope Method= 2
Unsteady Bridges Friction Slope Method= 1
Parabolic Critical Depth
Global Vel Dist=  1 , 1 , 1
Global Log Level= 0
CheckData=True
Encroach Param= -1, 0, 0, 0
BEGIN DESCRIPTION:
Multiple Run
END DESCRIPTION:

--- UNT0123 IN SAND CR.f01 (steady flow) ---

Flow Title=Multiple
Number of Profiles=7
Profile Names=10-year,25-year,50-year,1pct_min,100-year,1pct_plu,500-year
River Rch & RM= UNT0123 IN SAND ,Reach-1,15350
     912    1235    1496    1322    1787    2417    2543
River Rch & RM= UNT0123 IN SAND ,Reach-1,13050
    1457    2019    2485    2226    3010    4071    4407
River Rch & RM= UNT0123 IN SAND ,Reach-1,5299
    1479    2048    2517    2252    3045    4119    4448
Boundary for River Rch & Prof#=UNT0123 IN SAND ,Reach-1,1
Up Type=0
Dn Type=3
Dn Slope=0.005
Boundary for River Rch & Prof#=UNT0123 IN SAND ,Reach-1,2
Up Type=0
Dn Type=3
Dn Slope=0.005
Boundary for River Rch & Prof#=UNT0123 IN SAND ,Reach-1,3
Up Type=0
Dn Type=3
Dn Slope=0.005
Boundary for River Rch & Prof#=UNT0123 IN SAND ,Reach-1,4
Up Type=0
Dn Type=3
Dn Slope=0.005
Boundary for River Rch & Prof#=UNT0123 IN SAND ,Reach-1,5
Up Type=0
Dn Type=3
Dn Slope=0.005
Boundary for River Rch & Prof#=UNT0123 IN SAND ,Reach-1,6
Up Type=0
Dn Type=3
Dn Slope=0.005
Boundary for River Rch & Prof#=UNT0123 IN SAND ,Reach-1,7
Up Type=0
Dn Type=3
Dn Slope=0.005

--- UNT0123 IN SAND CR.g01 (geometry) ---

Geom Title=Existing Conditions

River Reach=UNT0123 IN SAND ,Reach-1
Reach XY= 30
      3525995.35     10596093.14      3525977.36     10595682.61
      3526354.10     10595523.05      3526288.21     10595276.87
      3526514.34     10595123.23      3526315.56     10594328.96
      3526579.41     10593917.28      3527291.50     10593671.88
      3527294.83     10593312.91      3527512.32     10593086.82
      3527405.14     10592903.14      3527648.14     10592815.16
      3527625.85     10592373.62      3527997.12     10592020.64
      3527868.34     10591689.79      3527614.57     10591600.77
      3527732.22     10591286.45      3528015.84     10591228.28
      3528028.84     10591007.84      3528613.62     10590885.09
      3528959.99     10590255.66      3529540.34     10589818.73
      3529512.74     10589440.26      3529097.29     10589019.95
      3529012.91     10588276.20      3529285.88     10588229.48
      3529541.57     10587762.40      3529199.77     10587607.63
      3529290.91     10587432.25      3528999.47     10586814.39

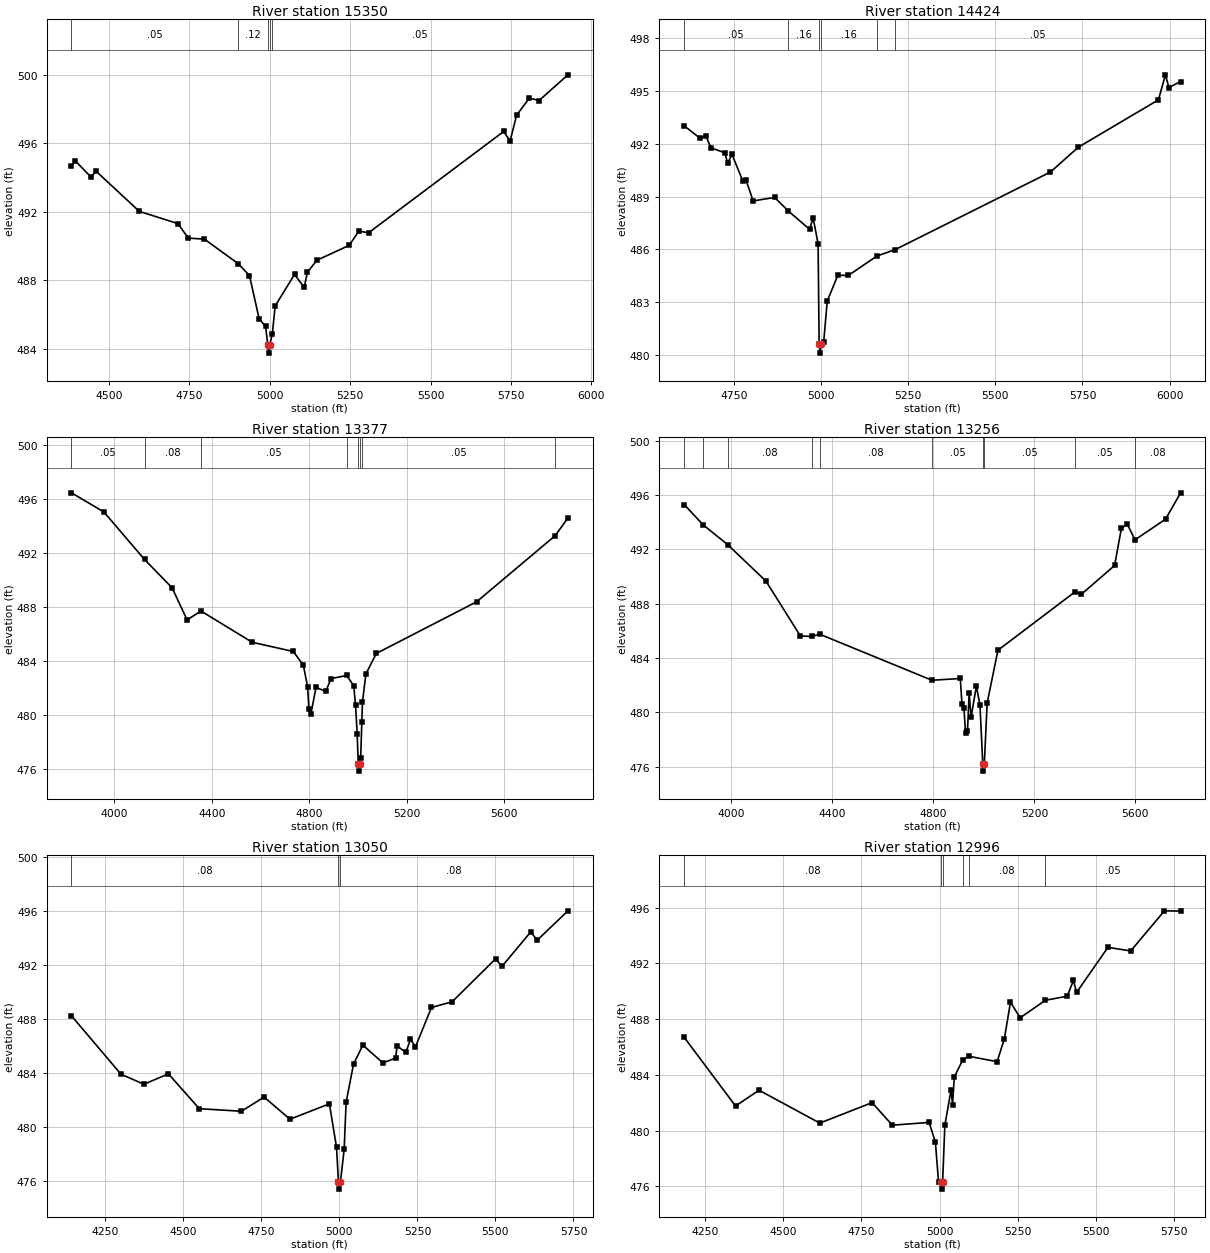
Type RM Length L Ch R = 1,15350,926,926,926
BEGIN DESCRIPTION:
UNT0123 IN SAND CR 23.0
END DESCRIPTION:
XS GIS Cut Line= 3
      3526524.30     10596236.07      3526260.44     10596013.86
      3525062.51     10595975.67
#Sta/Elev= 30
  4383.5  494.65  4395.5  494.97  4445.0  494.01  4459.3  494.38  4594.5  492.02
  4714.2  491.31  4746.8  490.46  4796.8  490.40  4902.3  488.96  4936.9  488.27
  4966.9  485.75  4986.9  485.30  4993.9  484.24  4996.7  483.74  4999.9  484.24
  5007.7  484.83  5016.9  486.50  5077.0  488.34  5107.0  487.58  5117.0  488.47
  5147.0  489.17  5247.1  490.04  5277.1  490.87  5307.1  490.77  5727.3  496.69
  5747.3  496.13  5767.3  497.64  5807.3  498.64  5837.4  498.50  5927.0  500.00
#Mann=5,-1,0
  4383.5    0.05       0  4902.3    0.12       0  4993.9    0.07       0
  4999.9    0.12       0  5007.7    0.05       0
Bank Sta=4993.9,4999.9
Exp/Cntr=0.3,0.1

Type RM Length L Ch R = 1,14424,1047,1047,1047
BEGIN DESCRIPTION:
UNT0123 IN SAND CR 22.0
END DESCRIPTION:
XS GIS Cut Line= 3
      3526737.72     10595396.83      3526284.21     10595468.43
      3525318.54     10595468.43
#Sta/Elev= 30
  4606.9  493.02  4653.1  492.30  4669.1  492.46  4683.5  491.77  4723.9  491.48
  4731.5  490.89  4744.2  491.39  4774.6  489.91  4784.7  489.92  4804.9  488.75
  4866.5  488.95  4905.8  488.18  4966.9  487.14  4977.0  487.79  4991.3  486.32
  4994.3  480.61  4997.0  480.11  5000.3  480.61  5007.4  480.75  5017.5  483.06
  5047.9  484.53  5078.1  484.52  5160.0  485.62  5212.8  485.99  5658.1  490.39
  5738.1  491.80  5968.1  494.49  5988.1  495.91  5998.1  495.19  6031.7  495.53
#Mann=6,-1,0
  4606.9    0.05       0  4905.8    0.16       0  4994.3    0.07       0
  5000.3    0.16       0  5160.0    0.12       0  5212.8    0.05       0
Bank Sta=4994.3,5000.3
Exp/Cntr=0.3,0.1

Type RM Length L Ch R = 1,13377,121,121,121
BEGIN DESCRIPTION:
UNT0123 IN SAND CR 21.0
END DESCRIPTION:
XS GIS Cut Line= 4
      3527530.51     10594329.98      3526494.09     10594613.82
      3526285.76     10594806.53      3525608.66     10594871.63
#Sta/Elev= 30
  3823.4  496.47  3956.5  495.05  4123.3  491.53  4236.5  489.43  4298.2  487.05
  4355.3  487.71  4565.5  485.39  4734.2  484.71  4775.6  483.69  4793.1  482.08
  4798.3  480.47  4806.7  480.09  4827.5  482.05  4867.3  481.75  4889.7  482.70
  4953.1  482.93  4982.5  482.18  4989.9  480.72  4996.7  478.57  5001.0  476.34
  5003.8  475.84  5007.0  476.34  5010.9  476.78  5015.6  479.46  5018.2  480.95
  5032.4  483.04  5074.9  484.56  5486.8  488.39  5810.1  493.30  5862.0  494.61
#Mann=8,-1,0
  3823.4    0.05       0  4123.3    0.08       0  4355.3    0.05       0
  4953.1    0.16       0  5001.0    0.07       0  5007.0    0.16       0
  5015.6    0.05       0  5810.1    0.08       0
Bank Sta=5001,5007
Exp/Cntr=0.3,0.1

Type RM Length L Ch R = 1,13256,206,206,206
BEGIN DESCRIPTION:
UNT0123 IN SAND CR 20.0
END DESCRIPTION:
XS GIS Cut Line= 4
      3527449.85     10594212.77      3526410.76     10594530.48
      3526236.28     10594681.53      3525593.05     10594767.46
#Sta/Elev= 30
  3812.8  495.29  3888.1  493.79  3984.9  492.34  4136.8  489.65  4273.2  485.61
  4317.9  485.58  4349.8  485.74  4794.3  482.35  4906.5  482.48  4913.1  480.63
  4920.8  480.33  4927.4  478.47  4935.0  478.60  4941.6  481.38  4949.3  479.62
  4970.1  481.92  4984.4  480.53  4995.6  476.16  4998.4  475.66  5001.6  476.16
  5012.9  480.67  5055.6  484.56  5362.4  488.88  5386.6  488.69  5517.7  490.80
  5544.7  493.55  5568.2  493.83  5598.6  492.69  5719.5  494.21  5779.1  496.15
#Mann=10,-1,0
  3812.8    0.08       0  3888.1    0.05       0  3984.9    0.08       0
  4317.9    0.05       0  4349.8    0.08       0  4794.3    0.05       0
  4995.6    0.04       0  5001.6    0.05       0  5362.4    0.05       0
  5598.6    0.08       0
Bank Sta=4995.6,5001.6
Exp/Cntr=0.3,0.1

Type RM Length L Ch R = 1,13050,54,54,54
BEGIN DESCRIPTION:
UNT0123 IN SAND CR 19.0
END DESCRIPTION:
XS GIS Cut Line= 4
      3527116.52     10594163.29      3526369.09     10594371.63
      3526126.91     10594465.38      3525586.14     10594590.17
#Sta/Elev= 30
  4141.7  488.26  4300.0  483.94  4373.6  483.19  4452.3  483.96  4551.2  481.38
  4686.1  481.19  4758.8  482.24  4841.8  480.60  4968.0  481.74  4990.9  478.52
  4997.2  475.92  4999.9  475.42  5003.2  475.92  5015.4  478.37  5021.6  481.85
  5045.4  484.69  5075.3  486.09  5139.6  484.77  5180.1  485.13  5185.2  486.03
  5213.0  485.55  5227.9  486.52  5243.8  485.96  5295.1  488.88  5361.3  489.30
  5500.4  492.48  5520.9  491.92  5613.3  494.48  5633.8  493.86  5732.3  496.04
#Mann=3,-1,0
  4141.7    0.08       0  4997.2    0.07       0  5003.2    0.08       0
Bank Sta=4997.2,5003.2
Exp/Cntr=0.3,0.1

Type RM Length L Ch R = 1,12996,773,773,773
BEGIN DESCRIPTION:
UNT0123 IN SAND CR 18.0
END DESCRIPTION:
XS GIS Cut Line= 5
      3527089.12     10594125.85      3526359.98     10594355.88
      3526229.77     10594342.85      3526080.03     10594399.28
      3525550.47     10594366.72
#Sta/Elev= 30
  4183.8  486.70  4347.9  481.77  4423.1  482.90  4617.2  480.54  4784.2  482.01
  4848.9  480.39  4966.3  480.59  4986.4  479.18  4996.5  476.34  5003.5  476.30
  5006.3  475.80  5009.5  476.30  5016.6  480.38  5036.4  482.91  5041.4  481.87
  5046.7  483.85  5074.2  485.09  5092.8  485.34  5183.6  484.95  5206.9  486.60
  5226.3  489.22  5257.2  488.10  5338.1  489.36  5407.5  489.65  5427.5  490.78
  5437.5  489.92  5537.7  493.16  5610.5  492.90  5718.1  495.78  5769.8  495.76
#Mann=6,-1,0
  4183.8    0.08       0  5003.5    0.07       0  5009.5    0.08       0
  5074.2    0.16       0  5092.8    0.08       0  5338.1    0.05       0
Bank Sta=5003.5,5009.5
Exp/Cntr=0.3,0.1

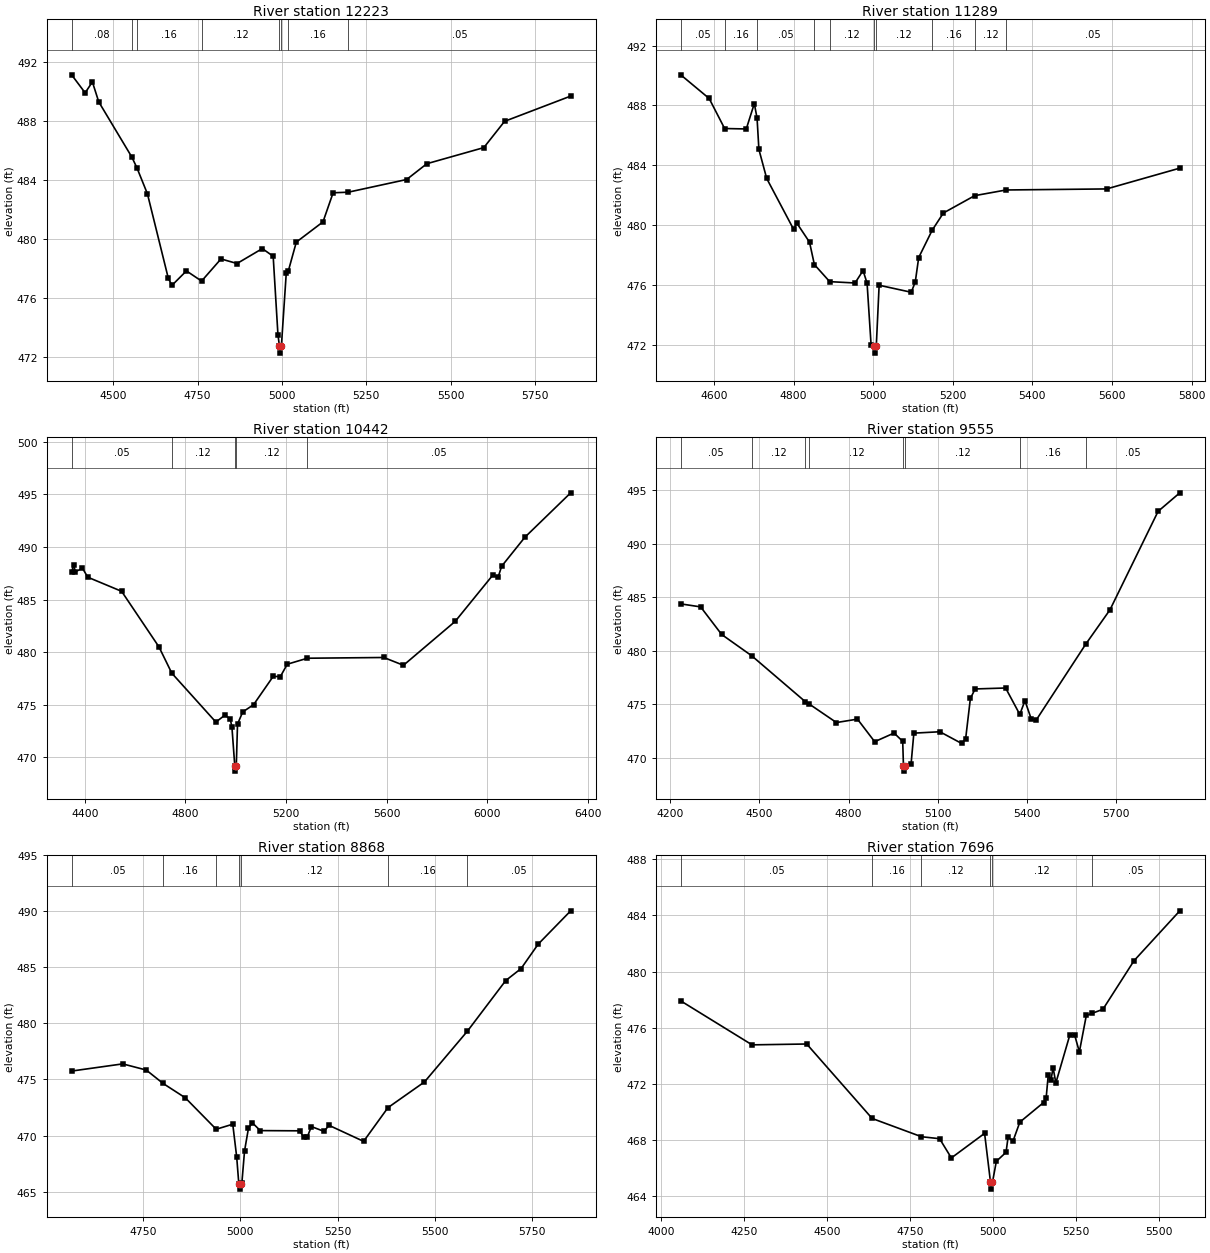
Type RM Length L Ch R = 1,12223,934,934,934
BEGIN DESCRIPTION:
UNT0123 IN SAND CR 17.0
END DESCRIPTION:
XS GIS Cut Line= 2
      3527319.54     10594056.65      3525939.29     10593522.78
#Sta/Elev= 30
  4376.3  491.14  4416.4  489.92  4437.9  490.66  4456.7  489.31  4554.6  485.58
  4569.8  484.85  4601.1  483.08  4663.0  477.36  4673.8  476.88  4716.7  477.86
  4761.7  477.17  4819.2  478.67  4866.8  478.36  4941.8  479.37  4974.0  478.85
  4988.1  473.55  4992.4  472.79  4995.2  472.29  4998.4  472.79  5012.7  477.69
  5018.5  477.82  5042.6  479.81  5121.7  481.18  5151.7  483.15  5196.5  483.19
  5369.8  484.05  5429.7  485.12  5598.6  486.21  5660.2  487.99  5856.2  489.70
#Mann=8,-1,0
  4376.3    0.08       0  4554.6    0.12       0  4569.8    0.16       0
  4761.7    0.12       0  4992.4    0.07       0  4998.4    0.12       0
  5018.5    0.16       0  5196.5    0.05       0
Bank Sta=4992.4,4998.4
Exp/Cntr=0.3,0.1

Type RM Length L Ch R = 1,11289,847,847,847
BEGIN DESCRIPTION:
UNT0123 IN SAND CR 16.0
END DESCRIPTION:
XS GIS Cut Line= 4
      3527767.54     10593559.13      3527395.14     10593428.92
      3527106.07     10593467.98      3526627.02     10593163.37
#Sta/Elev= 30
  4516.4  490.05  4587.8  488.47  4626.7  486.46  4681.1  486.43  4701.3  488.13
  4708.2  487.15  4712.8  485.06  4732.4  483.12  4799.8  479.73  4808.2  480.13
  4840.0  478.86  4852.2  477.36  4890.7  476.22  4954.3  476.13  4974.5  476.96
  4984.6  476.12  4994.7  471.98  5001.8  471.94  5004.5  471.44  5007.8  471.94
  5014.9  475.98  5095.6  475.51  5105.7  476.20  5114.3  477.83  5148.2  479.66
  5176.3  480.81  5255.0  481.97  5333.8  482.35  5586.5  482.42  5770.3  483.81
#Mann=10,-1,0
  4516.4    0.05       0  4626.7    0.16       0  4708.2    0.05       0
  4852.2    0.16       0  4890.7    0.12       0  5001.8    0.07       0
  5007.8    0.12       0  5148.2    0.16       0  5255.0    0.12       0
  5333.8    0.05       0
Bank Sta=5001.8,5007.8
Exp/Cntr=0.3,0.1

Type RM Length L Ch R = 1,10442,887,887,887
BEGIN DESCRIPTION:
UNT0123 IN SAND CR 15.0
END DESCRIPTION:
XS GIS Cut Line= 3
      3527984.81     10593290.07      3527684.81     10592990.08
      3526485.97     10591991.04
#Sta/Elev= 30
  4347.1  487.60  4355.0  488.29  4362.0  487.64  4390.3  487.97  4411.5  487.12
  4545.9  485.78  4694.4  480.50  4745.5  478.00  4920.9  473.35  4957.1  474.02
  4978.2  473.63  4984.7  472.86  4996.0  469.19  4998.8  468.69  5002.0  469.19
  5006.9  473.16  5027.7  474.32  5070.6  475.00  5148.7  477.69  5177.4  477.68
  5204.7  478.85  5284.6  479.42  5588.7  479.49  5666.8  478.75  5872.5  482.92
  6022.2  487.32  6043.0  487.10  6057.3  488.16  6149.8  490.92  6331.9  495.14
#Mann=5,-1,0
  4347.1    0.05       0  4745.5    0.12       0  4996.0    0.07       0
  5002.0    0.12       0  5284.6    0.05       0
Bank Sta=4996,5002
Exp/Cntr=0.3,0.1

Type RM Length L Ch R = 1,9555,687,687,687
BEGIN DESCRIPTION:
UNT0123 IN SAND CR 13.0
END DESCRIPTION:
XS GIS Cut Line= 3
      3528042.09     10592991.60      3527742.11     10592291.64
      3526942.11     10591841.65
#Sta/Elev= 30
  4235.1  484.36  4302.1  484.08  4372.9  481.50  4474.0  479.51  4654.8  475.21
  4668.1  474.99  4759.1  473.27  4829.8  473.59  4887.8  471.48  4953.1  472.29
  4982.1  471.51  4984.6  469.23  4987.3  468.73  4990.6  469.23  5010.3  469.42
  5019.6  472.28  5107.2  472.41  5180.2  471.32  5193.9  471.76  5209.8  475.52
  5225.8  476.41  5328.4  476.50  5376.1  474.03  5393.4  475.31  5415.1  473.57
  5431.0  473.49  5598.1  480.60  5679.6  483.81  5841.5  493.01  5914.5  494.74
#Mann=8,-1,0
  4235.1    0.05       0  4474.0    0.12       0  4654.8    0.05       0
  4668.1    0.12       0  4984.6    0.07       0  4990.6    0.12       0
  5376.1    0.16       0  5598.1    0.05       0
Bank Sta=4984.6,4990.6
Exp/Cntr=0.3,0.1

Type RM Length L Ch R = 1,8868,1172,1172,1172
BEGIN DESCRIPTION:
UNT0123 IN SAND CR 12.0
END DESCRIPTION:
XS GIS Cut Line= 3
      3528382.07     10591814.35      3527727.25     10591908.87
      3527132.07     10591730.99
#Sta/Elev= 30
  4566.1  475.75  4697.4  476.39  4758.0  475.84  4801.0  474.65  4858.1  473.37
  4937.7  470.56  4980.3  471.01  4990.4  468.09  4995.8  465.72  4998.5  465.22
  5001.8  465.72  5003.8  465.81  5010.6  468.63  5020.7  470.66  5030.8  471.13
  5051.0  470.44  5152.1  470.42  5162.2  469.89  5172.3  469.91  5182.4  470.80
  5214.9  470.37  5227.7  470.91  5316.6  469.48  5379.3  472.49  5473.1  474.78
  5583.5  479.31  5681.9  483.82  5721.4  484.89  5765.4  487.07  5848.9  490.04
#Mann=7,-1,0
  4566.1    0.05       0  4801.0    0.16       0  4937.7    0.12       0
  4995.8    0.07       0  5001.8    0.12       0  5379.3    0.16       0
  5583.5    0.05       0
Bank Sta=4995.8,5001.8
Exp/Cntr=0.3,0.1

Type RM Length L Ch R = 1,7696,952,952,952
BEGIN DESCRIPTION:
UNT0123 IN SAND CR 11.0
END DESCRIPTION:
XS GIS Cut Line= 2
      3528616.47     10591827.34      3527413.60     10590926.49
#Sta/Elev= 30
  4059.6  477.91  4274.4  474.78  4439.0  474.84  4636.0  469.54  4784.6  468.24
  4839.1  468.10  4874.5  466.73  4974.6  468.48  4992.4  465.01  4995.1  464.51
  4998.4  465.01  5010.0  466.49  5039.2  467.13  5045.4  468.22  5060.0  467.92
  5080.8  469.28  5152.0  470.67  5160.0  471.01  5166.3  472.63  5174.6  472.29
  5180.8  473.16  5189.2  472.07  5230.9  475.45  5245.4  475.51  5260.0  474.28
  5280.9  476.87  5297.9  477.02  5330.9  477.31  5424.6  480.77  5562.4  484.32
#Mann=6,-1,0
  4059.6    0.05       0  4636.0    0.16       0  4784.6    0.12       0
  4992.4    0.07       0  4998.4    0.12       0  5297.9    0.05       0
Bank Sta=4992.4,4998.4
Exp/Cntr=0.3,0.1

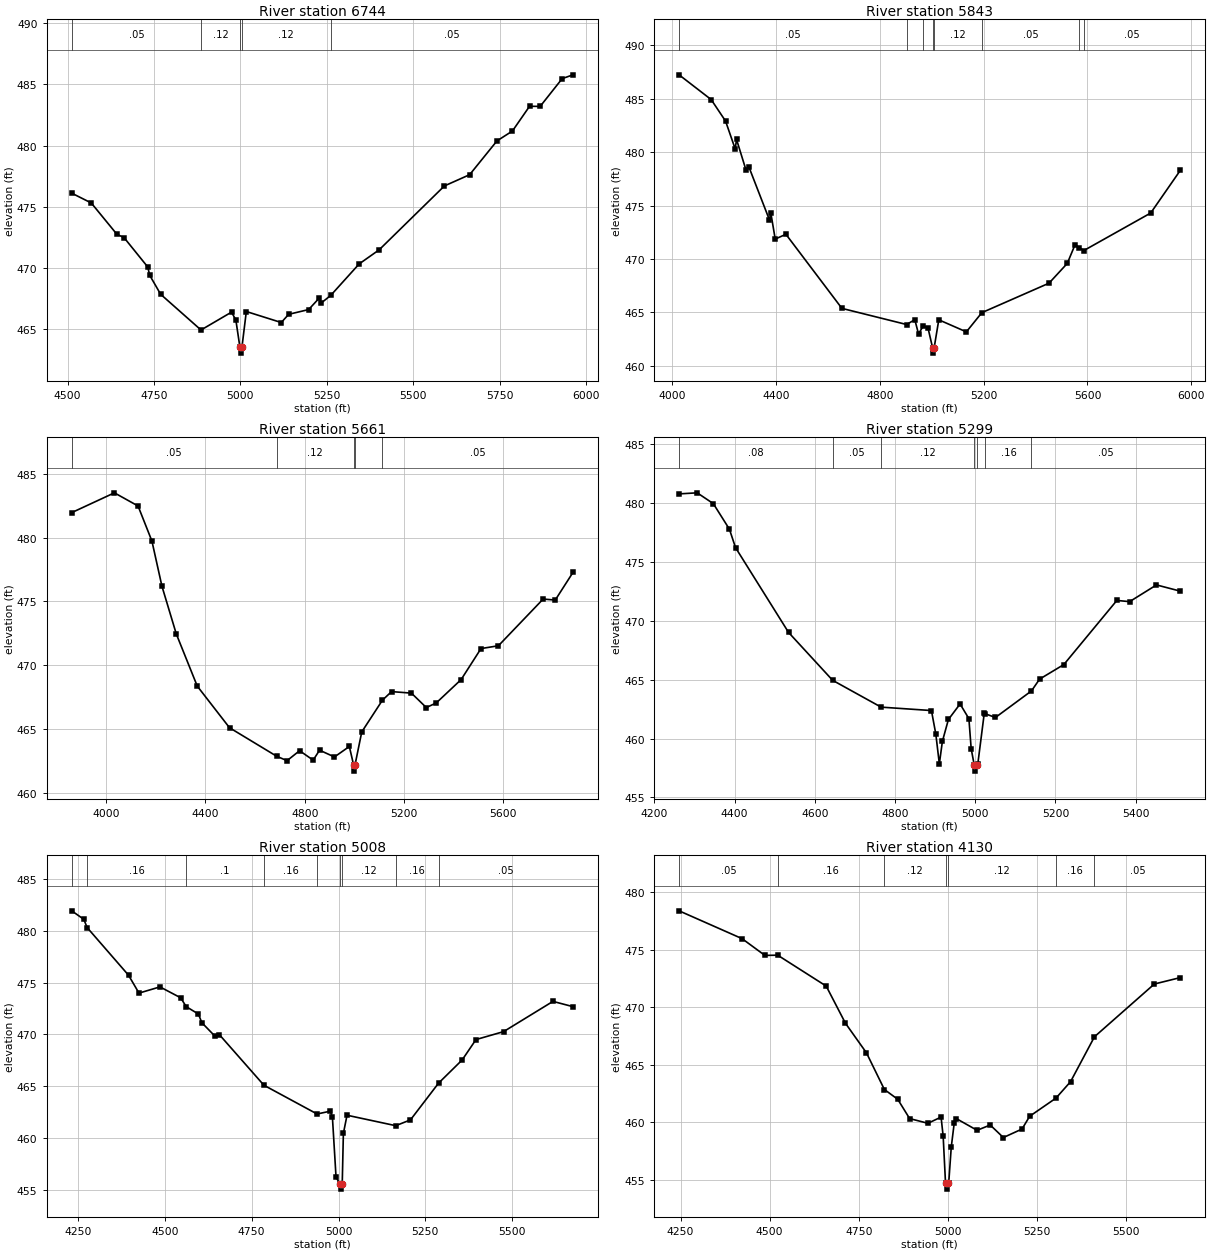
Type RM Length L Ch R = 1,6744,901,901,901
BEGIN DESCRIPTION:
UNT0123 IN SAND CR 10.0
END DESCRIPTION:
XS GIS Cut Line= 4
      3528616.48     10591285.66      3528486.28     10590895.07
      3528311.80     10590790.90      3527603.49     10590348.21
#Sta/Elev= 30
  4512.1  476.11  4568.6  475.31  4642.8  472.75  4663.4  472.48  4732.0  470.08
  4737.7  469.40  4769.3  467.85  4886.1  464.93  4974.4  466.39  4986.9  465.75
  4998.6  463.54  5001.3  463.04  5004.6  463.54  5017.2  466.44  5118.3  465.54
  5139.7  466.21  5197.5  466.60  5228.2  467.54  5234.1  467.14  5261.2  467.75
  5343.7  470.33  5401.5  471.48  5590.2  476.70  5663.3  477.62  5742.3  480.38
  5787.1  481.19  5836.6  483.21  5867.3  483.20  5931.0  485.47  5962.3  485.78
#Mann=5,-1,0
  4512.1    0.05       0  4886.1    0.12       0  4998.6    0.07       0
  5004.6    0.12       0  5261.2    0.05       0
Bank Sta=4998.6,5004.6
Exp/Cntr=0.3,0.1

Type RM Length L Ch R = 1,5843,182,182,182
BEGIN DESCRIPTION:
UNT0123 IN SAND CR 9.0
END DESCRIPTION:
XS GIS Cut Line= 4
      3529892.51     10590707.56      3529022.74     10590501.84
      3528861.28     10590366.42      3528038.34     10590290.90
#Sta/Elev= 30
  4027.0  487.24  4150.7  484.92  4206.0  482.91  4243.1  480.30  4248.3  481.19
  4284.3  478.36  4295.7  478.63  4375.1  473.65  4380.2  474.33  4397.3  471.86
  4438.5  472.31  4654.2  465.37  4903.3  463.86  4935.0  464.31  4949.3  462.98
  4967.5  463.72  4985.7  463.55  5003.5  461.68  5006.3  461.18  5009.5  461.68
  5027.4  464.30  5133.6  463.17  5193.3  464.97  5452.0  467.73  5522.3  469.58
  5552.4  471.34  5568.1  471.06  5586.4  470.79  5843.7  474.30  5957.9  478.30
#Mann=8,-1,0
  4027.0    0.05       0  4903.3    0.16       0  4967.5    0.12       0
  5003.5    0.07       0  5009.5    0.12       0  5193.3    0.05       0
  5568.1    0.16       0  5586.4    0.05       0
Bank Sta=5003.5,5009.5
Exp/Cntr=0.3,0.1

Type RM Length L Ch R = 1,5661,362,362,362
BEGIN DESCRIPTION:
UNT0123 IN SAND CR 8.0
END DESCRIPTION:
XS GIS Cut Line= 4
      3530082.60     10590410.69      3529111.28     10590285.69
      3528595.66     10590296.11      3528072.21     10590262.25
#Sta/Elev= 30
  3861.3  481.95  4033.2  483.50  4128.5  482.47  4184.4  479.72  4224.8  476.18
  4282.5  472.45  4367.0  468.36  4497.0  465.10  4687.5  462.86  4728.9  462.52
  4779.3  463.30  4834.0  462.56  4859.8  463.34  4919.8  462.81  4979.8  463.63
  4996.8  462.20  4999.6  461.70  5002.8  462.20  5029.8  464.77  5113.2  467.26
  5149.9  467.93  5229.9  467.81  5289.9  466.68  5329.9  467.04  5430.1  468.87
  5510.2  471.30  5580.4  471.52  5760.7  475.18  5809.4  475.10  5880.9  477.27
#Mann=5,-1,0
  3861.3    0.05       0  4687.5    0.12       0  4996.8    0.07       0
  5002.8    0.12       0  5113.2    0.05       0
Bank Sta=4996.8,5002.8
Exp/Cntr=0.3,0.1

Type RM Length L Ch R = 1,5299,291,291,291
BEGIN DESCRIPTION:
UNT0123 IN SAND CR 7.0
END DESCRIPTION:
XS GIS Cut Line= 3
      3529947.23     10590197.15      3529319.62     10590150.28
      3528770.17     10589861.23
#Sta/Elev= 30
  4261.5  480.80  4306.7  480.89  4346.9  479.97  4387.0  477.80  4402.3  476.23
  4534.6  469.02  4644.5  464.95  4765.4  462.67  4890.9  462.38  4901.8  460.38
  4910.6  457.85  4918.2  459.76  4933.2  461.62  4962.3  462.94  4984.3  461.69
  4990.0  459.14  4997.7  457.73  5000.5  457.23  5003.7  457.73  5006.4  457.80
  5022.8  462.19  5025.5  462.10  5050.5  461.79  5140.4  464.05  5160.6  465.05
  5221.1  466.29  5353.3  471.74  5385.2  471.64  5452.2  473.06  5511.7  472.53
#Mann=7,-1,0
  4261.5    0.08       0  4644.5    0.05       0  4765.4    0.12       0
  4997.7    0.07       0  5003.7    0.12       0  5025.5    0.16       0
  5140.4    0.05       0
Bank Sta=4997.7,5003.7
Exp/Cntr=0.3,0.1

Type RM Length L Ch R = 1,5008,878,878,878
BEGIN DESCRIPTION:
UNT0123 IN SAND CR 6.0
END DESCRIPTION:
XS GIS Cut Line= 4
      3530194.66     10590079.97      3529527.95     10590009.65
      3529293.57     10589931.53      3528786.43     10589793.69
#Sta/Elev= 30
  4232.0  481.94  4266.7  481.12  4276.4  480.32  4395.5  475.72  4425.6  473.99
  4486.0  474.59  4545.5  473.54  4561.6  472.68  4596.6  471.97  4606.6  471.13
  4643.4  469.86  4656.9  469.98  4785.2  465.09  4938.3  462.31  4976.1  462.58
  4982.4  462.02  4992.9  456.19  5004.7  455.55  5007.5  455.05  5010.7  455.55
  5014.0  460.43  5024.5  462.19  5164.7  461.18  5207.1  461.74  5288.0  465.29
  5355.9  467.53  5395.7  469.50  5475.3  470.27  5617.3  473.19  5675.0  472.68
#Mann=9,-1,0
  4232.0    0.05       0  4276.4    0.16       0  4561.6     0.1       0
  4785.2    0.16       0  4938.3    0.12       0  5004.7    0.07       0
  5010.7    0.12       0  5164.7    0.16       0  5288.0    0.05       0
Bank Sta=5004.7,5010.7
Exp/Cntr=0.3,0.1

Type RM Length L Ch R = 1,4130,766,766,766
BEGIN DESCRIPTION:
UNT0123 IN SAND CR 5.0
END DESCRIPTION:
XS GIS Cut Line= 4
      3530165.93     10589418.50      3529551.39     10589309.13
      3529210.24     10589514.86      3528843.39     10589626.74
#Sta/Elev= 30
  4246.0  478.40  4422.6  475.98  4486.7  474.52  4522.6  474.54  4658.7  471.85
  4712.6  468.62  4771.6  466.04  4821.9  462.85  4859.3  462.00  4892.7  460.32
  4944.0  459.91  4980.9  460.45  4986.8  458.77  4993.4  454.68  4996.2  454.18
  4999.4  454.68  5002.3  454.70  5009.5  457.85  5017.8  459.93  5023.6  460.32
  5081.9  459.30  5118.8  459.76  5155.6  458.67  5208.0  459.41  5229.4  460.52
  5303.2  462.10  5344.1  463.53  5411.2  467.44  5579.1  472.03  5652.1  472.59
#Mann=7,-1,0
  4246.0    0.05       0  4522.6    0.16       0  4821.9    0.12       0
  4993.4    0.07       0  4999.4    0.12       0  5303.2    0.16       0
  5411.2    0.05       0
Bank Sta=4993.4,4999.4
Exp/Cntr=0.3,0.1

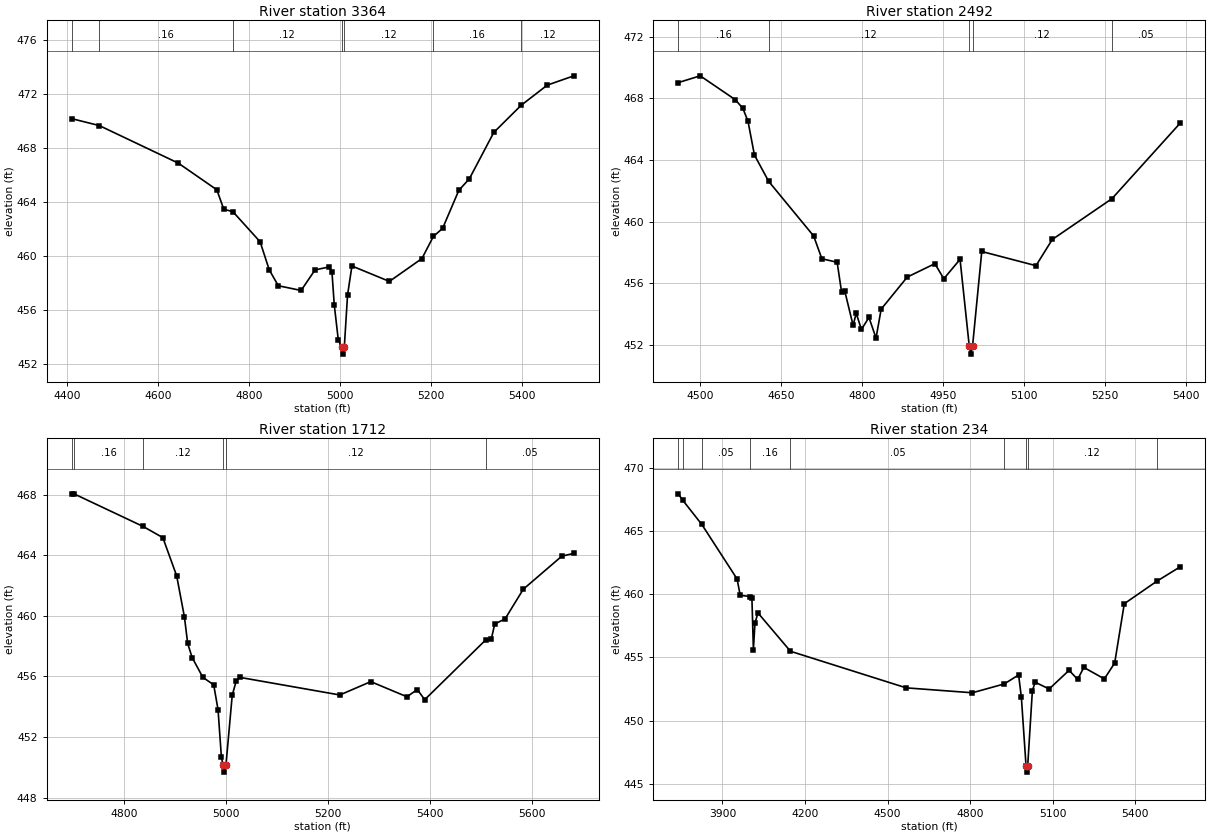
Type RM Length L Ch R = 1,3364,872,872,872
BEGIN DESCRIPTION:
UNT0123 IN SAND CR 3.0
END DESCRIPTION:
XS GIS Cut Line= 4
      3529746.69     10588829.96      3529249.30     10588840.38
      3528973.26     10588900.28      3528652.90     10588957.58
#Sta/Elev= 30
  4409.8  470.16  4470.4  469.65  4644.4  466.87  4729.1  464.90  4744.5  463.46
  4764.5  463.28  4824.5  461.05  4844.5  458.98  4864.5  457.80  4914.7  457.45
  4945.4  458.97  4976.1  459.19  4982.6  458.84  4987.7  456.39  4996.5  453.82
  5003.8  453.24  5006.5  452.74  5009.8  453.24  5017.0  457.12  5026.6  459.26
  5109.1  458.12  5180.7  459.81  5206.0  461.45  5226.2  462.04  5262.0  464.86
  5285.1  465.71  5338.9  469.14  5399.2  471.15  5456.6  472.64  5515.2  473.33
#Mann=7,-1,0
  4409.8    0.05       0  4470.4    0.16       0  4764.5    0.12       0
  5003.8    0.07       0  5009.8    0.12       0  5206.0    0.16       0
  5399.2    0.12       0
Bank Sta=5003.8,5009.8
Exp/Cntr=0.3,0.1

Type RM Length L Ch R = 1,2492,780,780,780
BEGIN DESCRIPTION:
UNT0123 IN SAND CR 2.0
END DESCRIPTION:
XS GIS Cut Line= 3
      3529561.84     10588468.01      3529158.39     10588216.50
      3528706.03     10588173.81
#Sta/Elev= 30
  4459.0  469.03  4499.7  469.47  4564.7  467.92  4578.7  467.36  4588.2  466.52
  4600.1  464.33  4626.5  462.62  4709.7  459.08  4725.0  457.60  4753.3  457.37
  4761.6  455.41  4767.5  455.49  4782.8  453.28  4788.7  454.06  4798.2  453.01
  4812.2  453.79  4825.3  452.45  4834.8  454.33  4883.1  456.41  4934.3  457.28
  4950.8  456.30  4980.9  457.56  4998.0  451.91  5000.8  451.41  5004.0  451.91
  5021.1  458.07  5121.5  457.15  5151.7  458.85  5262.3  461.50  5388.8  466.41
#Mann=5,-1,0
  4459.0    0.16       0  4626.5    0.12       0  4998.0    0.07       0
  5004.0    0.12       0  5262.3    0.05       0
Bank Sta=4998,5004
Exp/Cntr=0.3,0.1

Type RM Length L Ch R = 1,1712,1478,1478,1478
BEGIN DESCRIPTION:
UNT0123 IN SAND CR 1.0
END DESCRIPTION:
XS GIS Cut Line= 3
      3529652.97     10588046.12      3529322.22     10587832.57
      3528738.90     10587741.42
#Sta/Elev= 30
  4697.9  468.05  4702.2  468.05  4837.6  465.90  4876.4  465.16  4903.5  462.64
  4918.7  459.93  4925.1  458.18  4933.8  457.25  4954.9  455.94  4976.1  455.45
  4984.6  453.81  4991.2  450.67  4994.2  450.19  4996.9  449.69  5000.2  450.19
  5012.4  454.76  5020.3  455.71  5027.5  455.94  5223.3  454.78  5284.0  455.66
  5354.9  454.66  5375.1  455.14  5389.7  454.47  5508.9  458.40  5520.3  458.48
  5526.9  459.46  5547.2  459.80  5583.0  461.76  5658.5  463.94  5682.0  464.12
#Mann=6,-1,0
  4697.9    0.05       0  4702.2    0.16       0  4837.6    0.12       0
  4994.2    0.07       0  5000.2    0.12       0  5508.9    0.05       0
Bank Sta=4994.2,5000.2
Exp/Cntr=0.3,0.1

Type RM Length L Ch R = 1,234,0,0,0
BEGIN DESCRIPTION:
UNT0123 IN SAND CR 1.1
END DESCRIPTION:
XS GIS Cut Line= 4
      3529658.34     10587990.51      3529262.50     10587000.90
      3529012.50     10587011.32      3528783.35     10587464.40
#Sta/Elev= 30
  3739.5  467.97  3756.3  467.45  3825.2  465.54  3953.3  461.22  3964.5  459.93
  3998.7  459.83  4007.1  459.72  4012.5  455.63  4018.3  457.73  4029.1  458.53
  4147.2  455.49  4567.6  452.59  4808.0  452.20  4923.5  452.90  4975.9  453.61
  4985.9  451.85  5002.9  446.41  5005.7  445.91  5008.9  446.41  5025.9  452.36
  5035.9  453.04  5086.8  452.50  5159.3  453.98  5190.4  453.26  5212.8  454.21
  5287.4  453.30  5324.9  454.56  5359.8  459.26  5478.5  461.05  5563.3  462.19
#Mann=9,-1,0
  3739.5    0.05       0  3756.3    0.16       0  3825.2    0.05       0
  3998.7    0.16       0  4147.2    0.05       0  4923.5    0.12       0
  5002.9    0.07       0  5008.9    0.12       0  5478.5    0.16       0
Bank Sta=5002.9,5008.9
Exp/Cntr=0.3,0.1

Chan Stop Cuts=-1