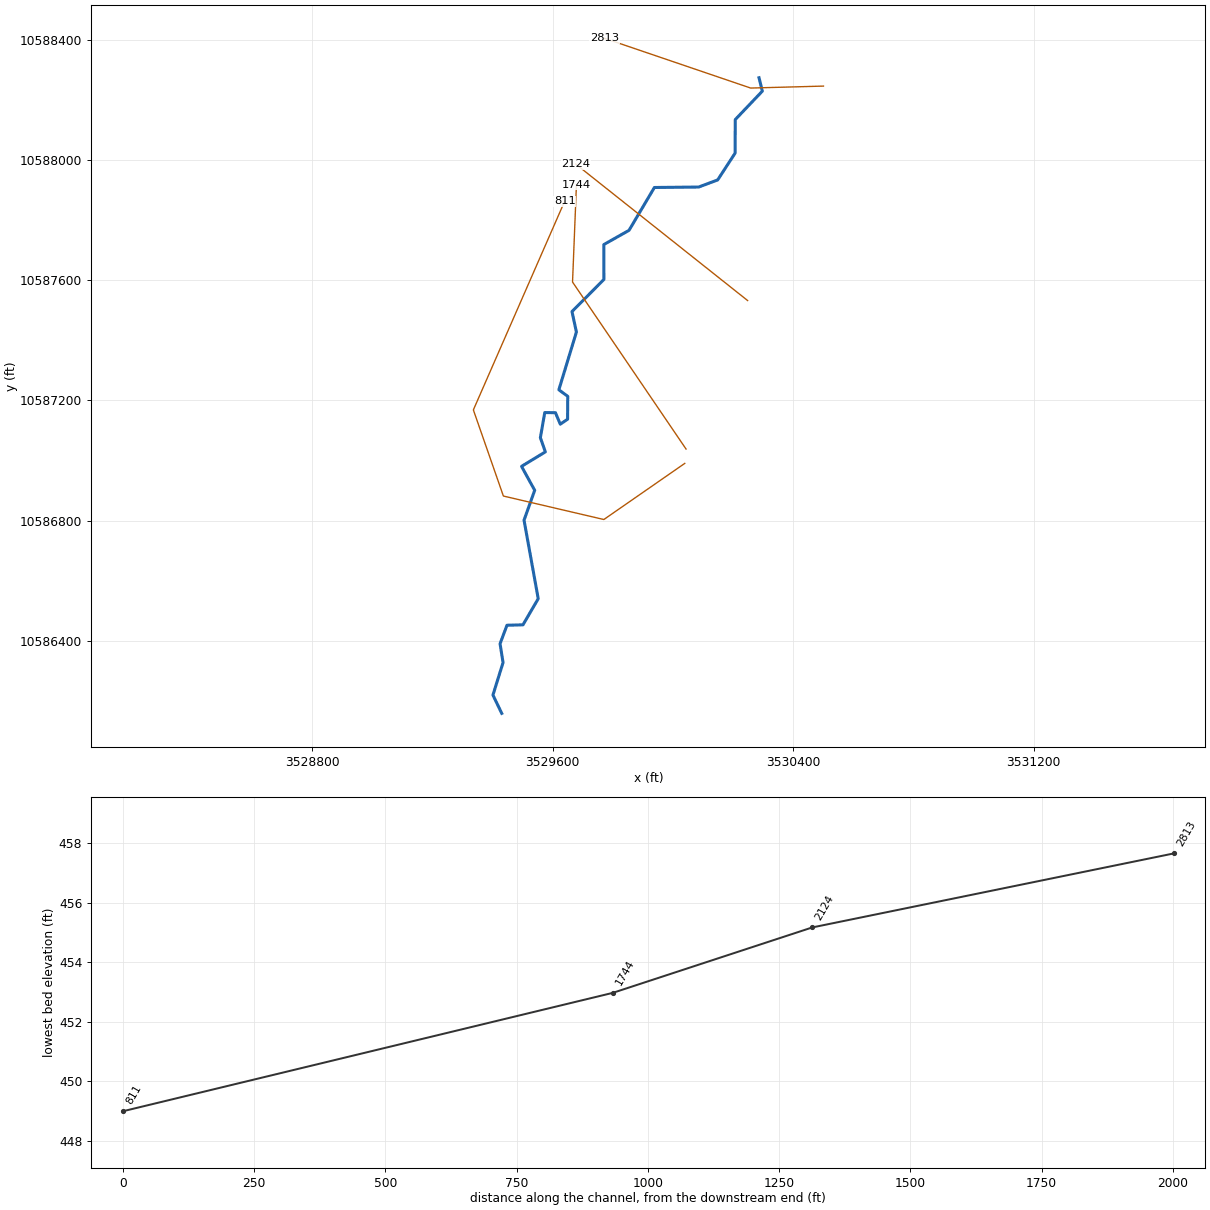
--- UNT0124 IN SAND CR.prj (project) ---

Proj Title=UNT0124 IN SAND CR Base Level Engineering
Current Plan=p01
Default Exp/Contr=0.3,0.1
English Units
Geom File=g01
Flow File=f01
Plan File=p01
BEGIN DESCRIPTION:
UNT0124 IN SAND CR
END DESCRIPTION:

--- UNT0124 IN SAND CR.p01 (plan) ---

Plan Title=Multiple Run
Short Identifier=Multiple
Geom File=g01
Flow File=f01
Subcritical Flow
K Sum by GR= 0
Std Step Tol= 0.01
Critical Tol= 0.01
Num of Std Step Trials= 20
Max Error Tol= 0.3
Flow Tol Ratio= 0.001
Split Flow NTrial= 30
Split Flow Tol= 0.02
Split Flow Ratio= 0.02
Log Output Level= 0
Friction Slope Method= 1
Unsteady Friction Slope Method= 2
Unsteady Bridges Friction Slope Method= 1
Parabolic Critical Depth
Global Vel Dist=  1 , 1 , 1
Global Log Level= 0
CheckData=True
Encroach Param= -1, 0, 0, 0
BEGIN DESCRIPTION:
Multiple Run
END DESCRIPTION:

--- UNT0124 IN SAND CR.f01 (steady flow) ---

Flow Title=Multiple
Number of Profiles=7
Profile Names=10-year,25-year,50-year,1pct_min,100-year,1pct_plu,500-year
River Rch & RM= UNT0124 IN SAND ,Reach-1,2813
     832    1121    1355    1194    1615    2184    2288
Boundary for River Rch & Prof#=UNT0124 IN SAND ,Reach-1,1
Up Type=0
Dn Type=3
Dn Slope=0.005
Boundary for River Rch & Prof#=UNT0124 IN SAND ,Reach-1,2
Up Type=0
Dn Type=3
Dn Slope=0.005
Boundary for River Rch & Prof#=UNT0124 IN SAND ,Reach-1,3
Up Type=0
Dn Type=3
Dn Slope=0.005
Boundary for River Rch & Prof#=UNT0124 IN SAND ,Reach-1,4
Up Type=0
Dn Type=3
Dn Slope=0.005
Boundary for River Rch & Prof#=UNT0124 IN SAND ,Reach-1,5
Up Type=0
Dn Type=3
Dn Slope=0.005
Boundary for River Rch & Prof#=UNT0124 IN SAND ,Reach-1,6
Up Type=0
Dn Type=3
Dn Slope=0.005
Boundary for River Rch & Prof#=UNT0124 IN SAND ,Reach-1,7
Up Type=0
Dn Type=3
Dn Slope=0.005

--- UNT0124 IN SAND CR.g01 (geometry) ---

Geom Title=Existing Conditions

River Reach=UNT0124 IN SAND ,Reach-1
Reach XY= 30
      3530286.60     10588273.28      3530297.58     10588228.66
      3530207.58     10588134.13      3530207.08     10588022.62
      3530149.10     10587933.37      3530085.71     10587909.72
      3529938.57     10587908.25      3529854.24     10587765.78
      3529770.30     10587718.33      3529770.62     10587602.31
      3529664.48     10587495.51      3529679.16     10587427.32
      3529620.84     10587235.38      3529650.35     10587213.51
      3529649.80     10587137.44      3529625.53     10587120.97
      3529609.47     10587159.17      3529573.88     10587159.60
      3529559.29     10587076.00      3529575.90     10587028.76
      3529496.65     10586980.64      3529540.43     10586900.99
      3529504.99     10586801.64      3529552.16     10586540.44
      3529501.42     10586453.51      3529448.24     10586452.11
      3529425.22     10586390.48      3529435.15     10586328.02
      3529401.53     10586219.90      3529430.82     10586158.99

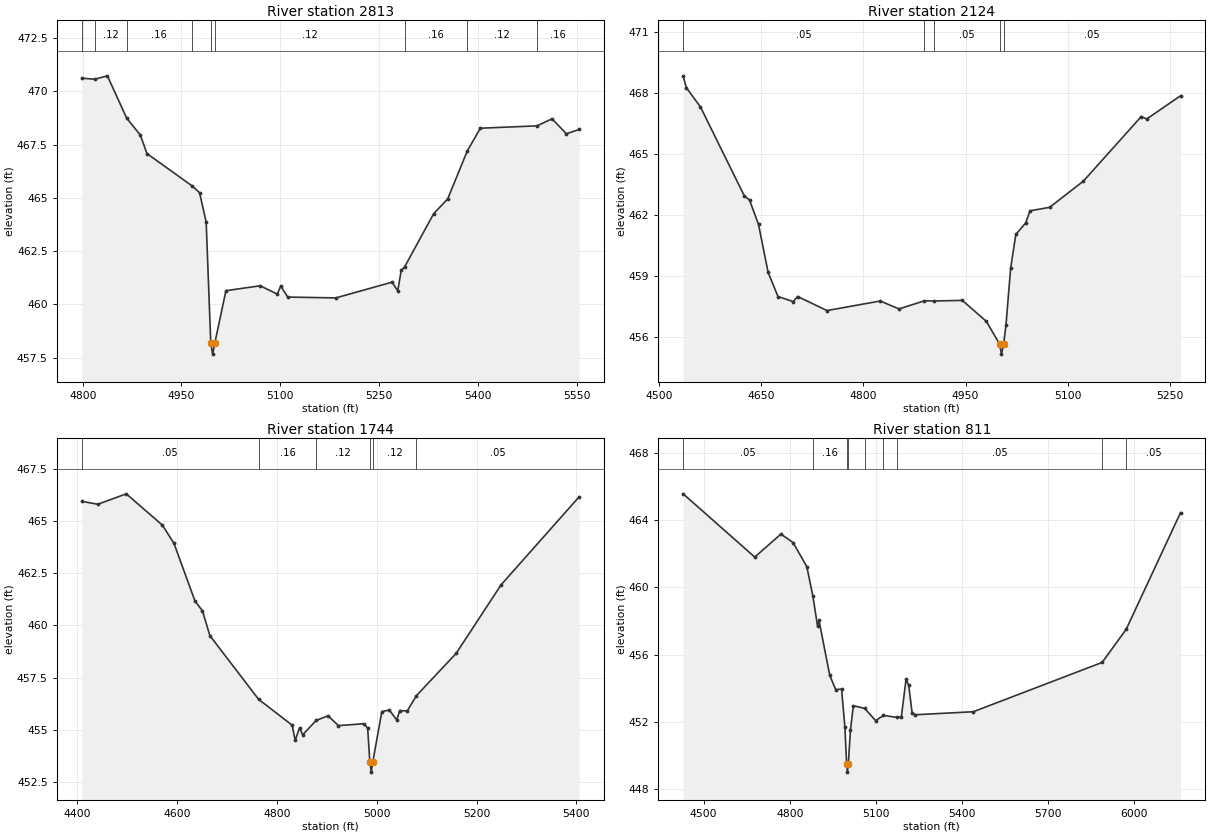
Type RM Length L Ch R = 1,2813,689,689,689
BEGIN DESCRIPTION:
UNT0124 IN SAND CR 1.0
END DESCRIPTION:
XS GIS Cut Line= 3
      3530500.96     10588245.51      3530258.74     10588239.00
      3529773.03     10588404.37
#Sta/Elev= 30
  4798.6  470.62  4818.1  470.57  4837.5  470.73  4866.8  468.74  4887.5  467.95
  4897.5  467.08  4965.7  465.57  4977.5  465.24  4987.5  463.86  4994.5  458.16
  4997.3  457.66  5000.5  458.16  5017.5  460.64  5069.5  460.87  5095.5  460.48
  5100.8  460.86  5111.3  460.34  5184.3  460.30  5269.8  461.04  5278.4  460.63
  5283.7  461.59  5288.9  461.76  5333.1  464.26  5354.3  464.95  5384.0  467.20
  5403.9  468.27  5489.9  468.38  5512.7  468.71  5534.6  468.01  5554.0  468.21
#Mann=9,-1,0
  4798.6    0.05       0  4818.1    0.12       0  4866.8    0.16       0
  4965.7    0.12       0  4994.5    0.07       0  5000.5    0.12       0
  5288.9    0.16       0  5384.0    0.12       0  5489.9    0.16       0
Bank Sta=4994.5,5000.5
Exp/Cntr=0.3,0.1

Type RM Length L Ch R = 1,2124,380,380,380
BEGIN DESCRIPTION:
UNT0124 IN SAND CR 2.0
END DESCRIPTION:
XS GIS Cut Line= 2
      3530248.78     10587532.11      3529676.67     10587986.33
#Sta/Elev= 30
  4535.2  468.84  4539.9  468.26  4560.7  467.31  4624.8  462.96  4632.8  462.73
  4645.9  461.54  4660.0  459.19  4674.5  458.00  4696.9  457.75  4703.3  458.00
  4746.6  457.31  4824.6  457.78  4852.3  457.39  4889.6  457.79  4903.6  457.78
  4945.2  457.81  4980.5  456.78  4999.9  455.67  5002.7  455.17  5005.9  455.67
  5009.3  456.59  5016.2  459.39  5023.8  461.05  5038.2  461.61  5044.6  462.21
  5073.4  462.38  5123.1  463.67  5208.0  466.84  5216.0  466.72  5265.7  467.86
#Mann=5,-1,0
  4535.2    0.05       0  4889.6    0.12       0  4903.6    0.05       0
  4999.9    0.03       0  5005.9    0.05       0
Bank Sta=4999.9,5005.9
Exp/Cntr=0.3,0.1

Type RM Length L Ch R = 1,1744,933,933,933
BEGIN DESCRIPTION:
UNT0124 IN SAND CR 3.0
END DESCRIPTION:
XS GIS Cut Line= 3
      3530043.91     10587038.19      3529666.30     10587593.76
      3529679.26     10587917.95
#Sta/Elev= 30
  4409.4  465.95  4441.5  465.81  4498.5  466.31  4570.8  464.81  4594.1  463.93
  4636.1  461.17  4651.1  460.70  4666.0  459.51  4763.5  456.46  4830.7  455.22
  4836.8  454.49  4845.6  455.10  4851.7  454.76  4879.0  455.45  4902.5  455.67
  4923.5  455.20  4974.4  455.29  4981.9  455.08  4986.3  453.47  4989.1  452.97
  4992.3  453.47  5010.3  455.87  5025.3  455.95  5040.2  455.47  5046.2  455.92
  5061.2  455.90  5079.4  456.63  5159.1  458.66  5249.2  461.95  5405.6  466.17
#Mann=6,-1,0
  4409.4    0.05       0  4763.5    0.16       0  4879.0    0.12       0
  4986.3    0.07       0  4992.3    0.12       0  5079.4    0.05       0
Bank Sta=4986.3,4992.3
Exp/Cntr=0.3,0.1

Type RM Length L Ch R = 1,811,0,0,0
BEGIN DESCRIPTION:
UNT0124 IN SAND CR 3.1
END DESCRIPTION:
XS GIS Cut Line= 5
      3530039.58     10586990.47      3529770.46     10586803.83
      3529436.26     10586881.95      3529336.43     10587168.41
      3529640.27     10587862.88
#Sta/Elev= 30
  4428.7  465.58  4678.1  461.81  4769.2  463.18  4811.8  462.67  4859.4  461.24
  4880.8  459.46  4896.8  457.69  4901.9  458.03  4939.3  454.76  4959.9  453.91
  4980.5  453.94  4992.0  451.67  4998.0  449.49  5000.7  448.99  5004.0  449.49
  5011.3  451.50  5021.5  452.95  5061.0  452.79  5099.0  452.06  5126.2  452.37
  5174.4  452.25  5188.6  452.29  5205.0  454.53  5214.3  454.16  5226.2  452.50
  5236.8  452.41  5439.0  452.59  5887.9  455.53  5971.7  457.51  6160.8  464.46
#Mann=9,-1,0
  4428.7    0.05       0  4880.8    0.16       0  4998.0    0.07       0
  5004.0    0.16       0  5061.0    0.12       0  5126.2    0.16       0
  5174.4    0.05       0  5887.9    0.16       0  5971.7    0.05       0
Bank Sta=4998,5004
Exp/Cntr=0.3,0.1

Chan Stop Cuts=-1