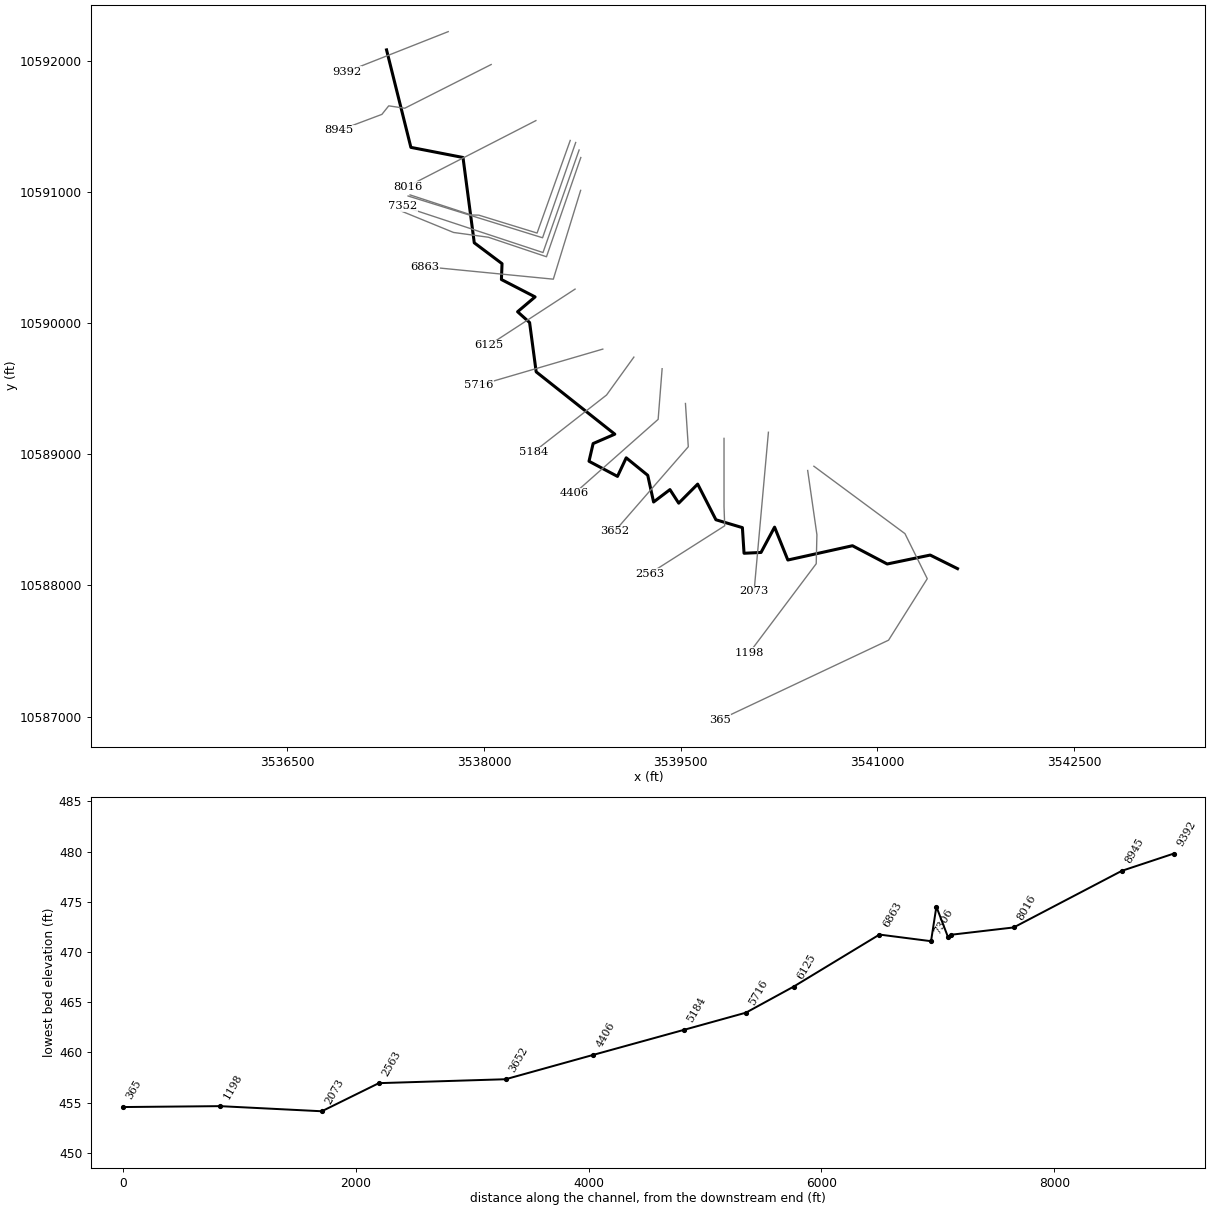
--- UNT0127 IN SAND CR.prj (project) ---

Proj Title=UNT0127 IN SAND CR Base Level Engineering
Current Plan=p01
Default Exp/Contr=0.3,0.1
English Units
Geom File=g01
Flow File=f01
Plan File=p01
BEGIN DESCRIPTION:
UNT0127 IN SAND CR
END DESCRIPTION:

--- UNT0127 IN SAND CR.p01 (plan) ---

Plan Title=Multiple Run
Short Identifier=Multiple
Geom File=g01
Flow File=f01
Subcritical Flow
K Sum by GR= 0
Std Step Tol= 0.01
Critical Tol= 0.01
Num of Std Step Trials= 20
Max Error Tol= 0.3
Flow Tol Ratio= 0.001
Split Flow NTrial= 30
Split Flow Tol= 0.02
Split Flow Ratio= 0.02
Log Output Level= 0
Friction Slope Method= 1
Unsteady Friction Slope Method= 2
Unsteady Bridges Friction Slope Method= 1
Parabolic Critical Depth
Global Vel Dist=  1 , 1 , 1
Global Log Level= 0
CheckData=True
Encroach Param= -1, 0, 0, 0
BEGIN DESCRIPTION:
Multiple Run
END DESCRIPTION:

--- UNT0127 IN SAND CR.f01 (steady flow) ---

Flow Title=Multiple
Number of Profiles=7
Profile Names=10-year,25-year,50-year,1pct_min,100-year,1pct_plu,500-year
River Rch & RM= UNT0127 IN SAND ,Reach-1,9392
     852    1145    1381    1215    1643    2222    2317
River Rch & RM= UNT0127 IN SAND ,Reach-1,7352
    1230    1687    2061    1834    2480    3354    3583
Boundary for River Rch & Prof#=UNT0127 IN SAND ,Reach-1,1
Up Type=0
Dn Type=3
Dn Slope=0.005
Boundary for River Rch & Prof#=UNT0127 IN SAND ,Reach-1,2
Up Type=0
Dn Type=3
Dn Slope=0.005
Boundary for River Rch & Prof#=UNT0127 IN SAND ,Reach-1,3
Up Type=0
Dn Type=3
Dn Slope=0.005
Boundary for River Rch & Prof#=UNT0127 IN SAND ,Reach-1,4
Up Type=0
Dn Type=3
Dn Slope=0.005
Boundary for River Rch & Prof#=UNT0127 IN SAND ,Reach-1,5
Up Type=0
Dn Type=3
Dn Slope=0.005
Boundary for River Rch & Prof#=UNT0127 IN SAND ,Reach-1,6
Up Type=0
Dn Type=3
Dn Slope=0.005
Boundary for River Rch & Prof#=UNT0127 IN SAND ,Reach-1,7
Up Type=0
Dn Type=3
Dn Slope=0.005

--- UNT0127 IN SAND CR.g01 (geometry) ---

Geom Title=Existing Conditions

River Reach=UNT0127 IN SAND ,Reach-1
Reach XY= 30
      3537256.38     10592084.02      3537441.99     10591340.70
      3537839.38     10591263.61      3537925.34     10590612.93
      3538137.00     10590453.97      3538132.41     10590332.85
      3538389.12     10590200.36      3538255.69     10590087.18
      3538347.25     10590004.99      3538397.33     10589628.88
      3538997.08     10589153.58      3538831.75     10589082.03
      3538800.28     10588947.01      3539017.43     10588831.58
      3539084.03     10588973.28      3539248.22     10588839.91
      3539292.83     10588636.29      3539417.48     10588730.86
      3539484.38     10588627.49      3539629.02     10588772.76
      3539768.18     10588500.91      3539970.05     10588440.86
      3539982.59     10588245.42      3540112.11     10588251.64
      3540215.43     10588444.73      3540316.56     10588193.87
      3540809.42     10588302.83      3541074.35     10588163.59
      3541402.13     10588231.65      3541610.45     10588128.12

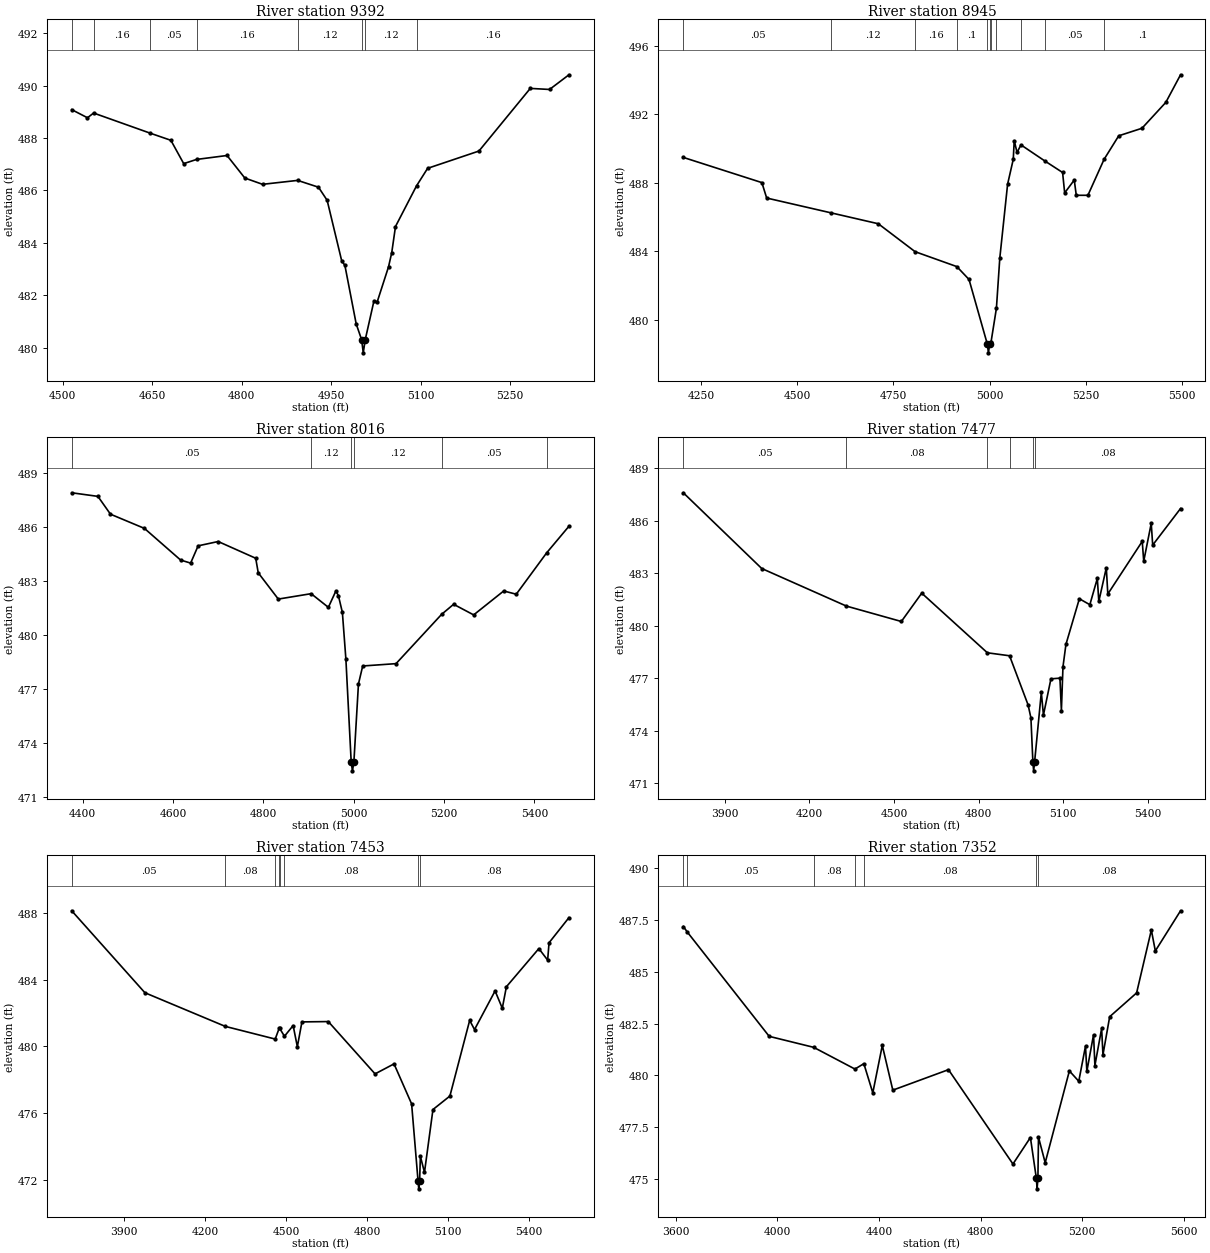
Type RM Length L Ch R = 1,9392,447,447,447
BEGIN DESCRIPTION:
UNT0127 IN SAND CR 13.0
END DESCRIPTION:
XS GIS Cut Line= 2
      3537726.61     10592223.23      3536951.85     10591917.23
#Sta/Elev= 30
  4515.4  489.08  4541.8  488.77  4552.1  488.95  4647.1  488.18  4681.5  487.91
  4703.0  487.02  4724.6  487.18  4775.6  487.33  4805.4  486.47  4835.1  486.23
  4893.9  486.38  4928.8  486.12  4943.3  485.62  4967.7  483.31  4973.0  483.14
  4992.0  480.90  5001.1  480.30  5003.8  479.80  5007.1  480.30  5021.8  481.79
  5027.1  481.74  5046.1  483.08  5051.5  483.62  5057.8  484.62  5093.0  486.17
  5111.6  486.84  5197.6  487.50  5283.6  489.89  5315.9  489.85  5348.4  490.41
#Mann=8,-1,0
  4515.4    0.05       0  4552.1    0.16       0  4647.1    0.05       0
  4724.6    0.16       0  4893.9    0.12       0  5001.1    0.07       0
  5007.1    0.12       0  5093.0    0.16       0
Bank Sta=5001.1,5007.1
Exp/Cntr=0.3,0.1

Type RM Length L Ch R = 1,8945,929,929,929
BEGIN DESCRIPTION:
UNT0127 IN SAND CR 13.1
END DESCRIPTION:
XS GIS Cut Line= 5
      3538054.31     10591972.51      3537395.41     10591639.16
      3537273.01     10591657.39      3537220.93     10591592.28
      3536896.26     10591470.21
#Sta/Elev= 30
  4203.7  489.48  4407.9  488.01  4420.4  487.11  4588.8  486.24  4710.5  485.61
  4806.2  483.98  4914.7  483.11  4946.3  482.36  4994.0  478.58  4996.7  478.08
  5000.0  478.58  5003.4  478.69  5017.5  480.68  5026.3  483.61  5046.6  487.92
  5061.3  489.37  5063.8  490.46  5071.1  489.77  5081.3  490.21  5144.2  489.26
  5189.5  488.60  5194.9  487.41  5219.8  488.16  5225.1  487.27  5255.3  487.27
  5297.4  489.37  5335.4  490.74  5395.8  491.18  5457.8  492.69  5496.1  494.30
#Mann=11,-1,0
  4203.7    0.05       0  4588.8    0.12       0  4806.2    0.16       0
  4914.7     0.1       0  4994.0    0.07       0  5000.0     0.1       0
  5003.4    0.16       0  5017.5    0.05       0  5081.3     0.1       0
  5144.2    0.05       0  5297.4     0.1       0
Bank Sta=4994,5000
Exp/Cntr=0.3,0.1

Type RM Length L Ch R = 1,8016,539,539,539
BEGIN DESCRIPTION:
UNT0127 IN SAND CR 12.0
END DESCRIPTION:
XS GIS Cut Line= 2
      3538395.30     10591544.85      3537415.79     10591042.09
#Sta/Elev= 30
  4375.7  487.90  4433.7  487.70  4461.5  486.71  4536.7  485.92  4616.8  484.16
  4639.0  483.99  4655.6  484.95  4700.0  485.19  4783.1  484.26  4788.7  483.45
  4833.1  481.99  4905.8  482.29  4944.0  481.53  4960.6  482.44  4966.2  482.18
  4975.0  481.25  4982.8  478.64  4994.5  472.94  4997.3  472.44  5000.5  472.94
  5010.6  477.27  5020.0  478.27  5093.8  478.40  5194.7  481.14  5221.3  481.70
  5265.7  481.11  5332.2  482.44  5360.0  482.26  5427.3  484.56  5476.7  486.04
#Mann=6,-1,0
  4375.7    0.05       0  4905.8    0.12       0  4994.5    0.07       0
  5000.5    0.12       0  5194.7    0.05       0  5427.3    0.08       0
Bank Sta=4994.5,5000.5
Exp/Cntr=0.3,0.1

Type RM Length L Ch R = 1,7477,24,24,24
BEGIN DESCRIPTION:
UNT0127 IN SAND CR 11.0
END DESCRIPTION:
XS GIS Cut Line= 5
      3538657.08     10591393.48      3538404.33     10590687.29
      3537960.30     10590823.77      3537903.35     10590825.16
      3537435.82     10590978.23
#Sta/Elev= 30
  3753.0  487.61  4031.1  483.28  4331.6  481.13  4526.3  480.25  4598.6  481.87
  4831.4  478.46  4910.1  478.29  4975.8  475.48  4985.8  474.74  4992.8  472.21
  4995.5  471.71  4998.8  472.21  5022.7  476.20  5030.2  474.90  5056.8  476.97
  5088.7  477.01  5093.9  475.16  5099.5  477.66  5110.0  478.94  5157.6  481.55
  5194.8  481.21  5221.3  482.71  5226.6  481.40  5253.2  483.32  5258.5  481.82
  5380.6  484.83  5385.9  483.70  5412.5  485.86  5417.7  484.62  5516.5  486.71
#Mann=6,-1,0
  3753.0    0.05       0  4331.6    0.08       0  4831.4    0.05       0
  4910.1    0.08       0  4992.8    0.07       0  4998.8    0.08       0
Bank Sta=4992.8,4998.8
Exp/Cntr=0.3,0.1

Type RM Length L Ch R = 1,7453,101,101,101
BEGIN DESCRIPTION:
UNT0127 IN SAND CR 10.0
END DESCRIPTION:
XS GIS Cut Line= 3
      3538698.75     10591377.87      3538446.15     10590651.33
      3537420.65     10590969.78
#Sta/Elev= 30
  3705.6  488.13  3976.9  483.21  4274.9  481.19  4459.8  480.43  4474.4  481.07
  4476.3  481.07  4494.1  480.60  4526.3  481.24  4541.9  479.97  4558.9  481.46
  4656.6  481.48  4829.9  478.34  4900.2  478.94  4965.4  476.54  4989.1  471.94
  4991.9  471.44  4995.1  471.94  4997.9  473.39  5013.1  472.43  5044.5  476.20
  5107.3  477.01  5180.6  481.55  5198.6  481.00  5274.8  483.32  5301.5  482.28
  5316.7  483.57  5437.0  485.86  5469.6  485.17  5474.8  486.21  5548.6  487.72
#Mann=8,-1,0
  3705.6    0.05       0  4274.9    0.08       0  4459.8    0.05       0
  4474.4    0.08       0  4476.3    0.05       0  4494.1    0.08       0
  4989.1    0.07       0  4995.1    0.08       0
Bank Sta=4989.1,4995.1
Exp/Cntr=0.3,0.1

Type RM Length L Ch R = 1,7352,46,46,46
BEGIN DESCRIPTION:
UNT0127 IN SAND CR 9.0
END DESCRIPTION:
XS GIS Cut Line= 3
      3538724.80     10591320.60      3538449.40     10590538.64
      3537377.83     10590892.73
#Sta/Elev= 30
  3629.5  487.19  3646.0  486.91  3967.7  481.88  4142.7  481.35  4305.2  480.30
  4340.3  480.56  4375.5  479.15  4412.9  481.44  4454.3  479.28  4673.4  480.27
  4927.3  475.71  4996.0  476.99  5019.5  475.01  5022.3  474.51  5025.5  475.01
  5027.8  477.01  5054.2  475.77  5149.4  480.21  5186.4  479.71  5212.9  481.41
  5218.2  480.19  5244.6  481.96  5249.9  480.47  5276.4  482.26  5281.6  480.99
  5308.1  482.83  5414.1  483.98  5472.1  487.02  5487.8  486.01  5587.1  487.95
#Mann=7,-1,0
  3629.5    0.08       0  3646.0    0.05       0  4142.7    0.08       0
  4305.2    0.05       0  4340.3    0.08       0  5019.5    0.07       0
  5025.5    0.08       0
Bank Sta=5019.5,5025.5
Exp/Cntr=0.3,0.1

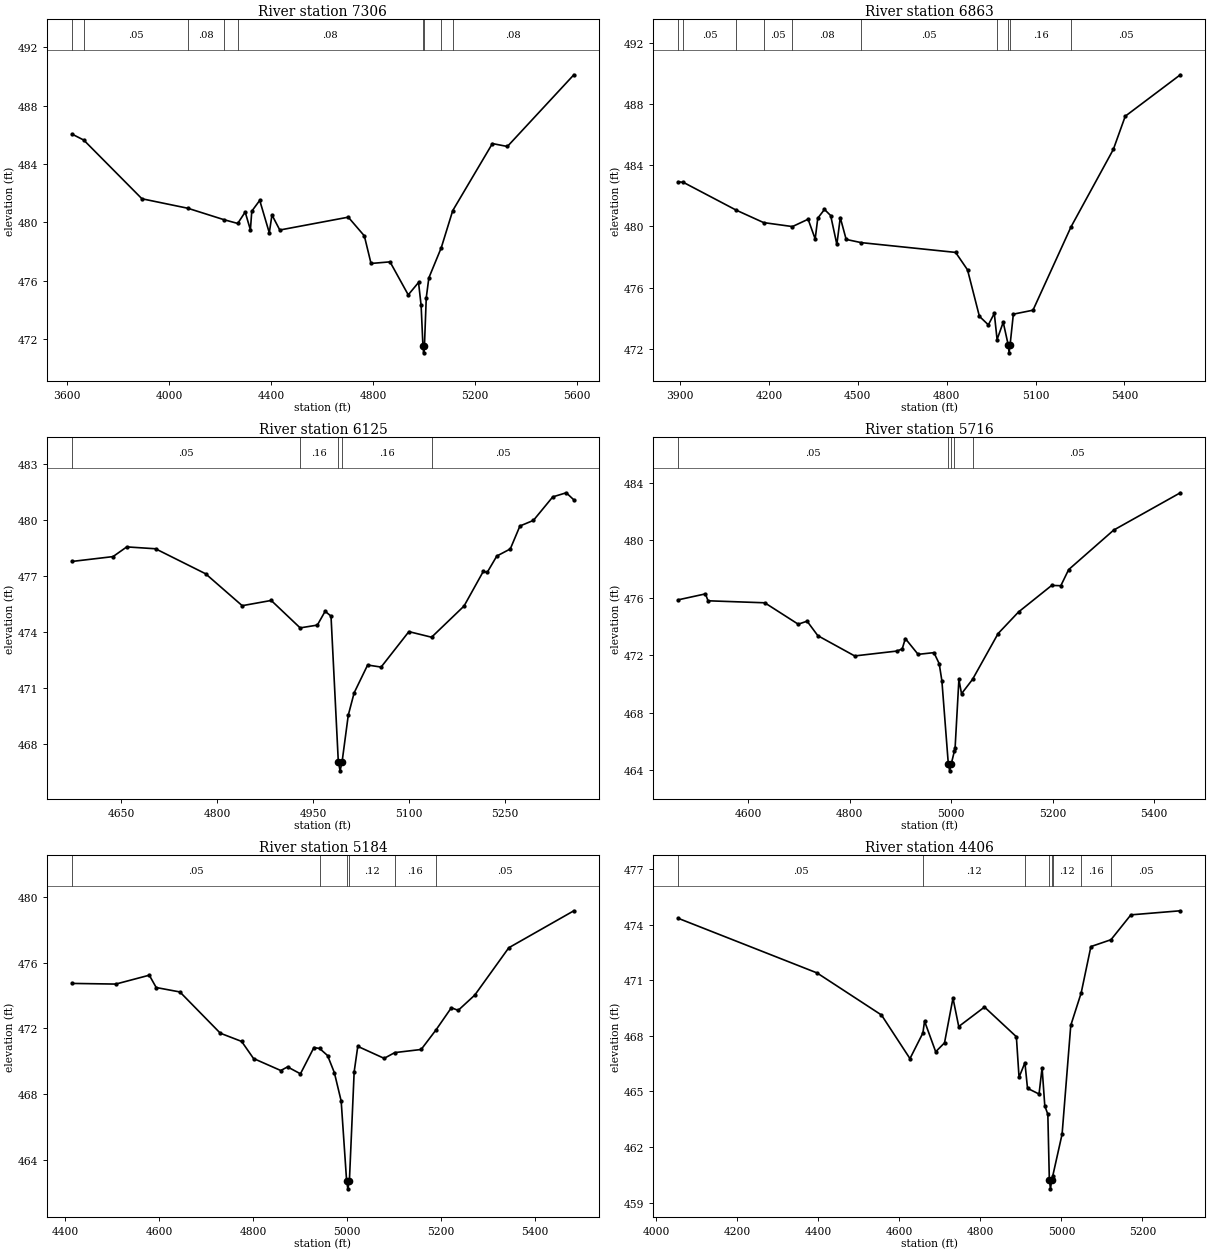
Type RM Length L Ch R = 1,7306,443,443,443
BEGIN DESCRIPTION:
UNT0127 IN SAND CR 8.0
END DESCRIPTION:
XS GIS Cut Line= 5
      3538737.83     10591263.35      3538476.00     10590506.52
      3538032.78     10590655.40      3537767.15     10590691.86
      3537366.59     10590855.72
#Sta/Elev= 30
  3618.4  486.05  3664.7  485.64  3893.0  481.62  4073.2  480.97  4216.2  480.18
  4268.8  479.93  4298.1  480.71  4318.6  479.49  4324.0  480.77  4355.2  481.51
  4392.7  479.29  4403.2  480.51  4433.9  479.48  4702.6  480.36  4765.6  479.08
  4791.9  477.19  4866.4  477.30  4937.9  475.04  4978.3  475.89  4988.4  474.32
  4995.5  471.57  4998.3  471.07  5001.5  471.57  5008.6  474.84  5018.7  476.20
  5067.5  478.27  5112.5  480.81  5268.1  485.40  5326.9  485.20  5587.7  490.11
#Mann=9,-1,0
  3618.4    0.08       0  3664.7    0.05       0  4073.2    0.08       0
  4216.2    0.05       0  4268.8    0.08       0  4995.5    0.07       0
  5001.5    0.08       0  5067.5    0.16       0  5112.5    0.08       0
Bank Sta=4995.5,5001.5
Exp/Cntr=0.3,0.1

Type RM Length L Ch R = 1,6863,738,738,738
BEGIN DESCRIPTION:
UNT0127 IN SAND CR 7.2
END DESCRIPTION:
XS GIS Cut Line= 3
      3538736.50     10591012.91      3538528.14     10590335.59
      3537547.08     10590431.69
#Sta/Elev= 30
  3894.4  482.92  3911.4  482.88  4090.0  481.06  4182.1  480.25  4279.3  479.99
  4332.2  480.47  4356.1  479.18  4364.9  480.54  4387.5  481.11  4408.4  480.71
  4429.3  478.82  4440.8  480.58  4460.7  479.15  4511.4  478.94  4830.2  478.30
  4870.4  477.16  4910.5  474.12  4940.7  473.56  4960.8  474.31  4970.2  472.60
  4990.9  473.73  5008.0  472.23  5010.8  471.73  5014.0  472.23  5025.1  474.26
  5091.4  474.52  5219.8  479.97  5362.7  485.04  5402.9  487.21  5588.8  489.92
#Mann=10,-1,0
  3894.4    0.08       0  3911.4    0.05       0  4090.0    0.08       0
  4182.1    0.05       0  4279.3    0.08       0  4511.4    0.05       0
  4970.2    0.16       0  5008.0    0.07       0  5014.0    0.16       0
  5219.8    0.05       0
Bank Sta=5008,5014
Exp/Cntr=0.3,0.1

Type RM Length L Ch R = 1,6125,409,409,409
BEGIN DESCRIPTION:
UNT0127 IN SAND CR 7.0
END DESCRIPTION:
XS GIS Cut Line= 2
      3538693.99     10590259.80      3538035.71     10589831.05
#Sta/Elev= 30
  4572.7  477.76  4637.0  478.02  4658.5  478.54  4703.5  478.44  4781.9  477.10
  4839.2  475.39  4884.6  475.67  4929.9  474.20  4956.8  474.35  4969.0  475.09
  4978.2  474.83  4989.6  467.04  4992.4  466.54  4995.6  467.04  5005.2  469.52
  5014.4  470.72  5035.5  472.21  5056.6  472.10  5100.1  474.00  5135.6  473.70
  5186.4  475.37  5216.6  477.23  5222.6  477.17  5237.7  478.05  5258.8  478.43
  5273.9  479.66  5295.0  479.96  5325.3  481.22  5346.4  481.44  5358.3  481.06
#Mann=5,-1,0
  4572.7    0.05       0  4929.9    0.16       0  4989.6    0.07       0
  4995.6    0.16       0  5135.6    0.05       0
Bank Sta=4989.6,4995.6
Exp/Cntr=0.3,0.1

Type RM Length L Ch R = 1,5716,532,532,532
BEGIN DESCRIPTION:
UNT0127 IN SAND CR 7.1
END DESCRIPTION:
XS GIS Cut Line= 2
      3538905.51     10589802.35      3537956.03     10589524.87
#Sta/Elev= 30
  4462.2  475.86  4515.4  476.27  4520.6  475.79  4632.4  475.65  4698.3  474.16
  4715.8  474.37  4737.0  473.36  4809.6  471.95  4892.9  472.29  4903.3  472.44
  4909.4  473.16  4934.6  472.06  4965.8  472.18  4976.2  471.41  4981.5  470.21
  4994.1  464.45  4996.8  463.95  5000.1  464.45  5006.1  465.33  5007.5  465.54
  5015.0  470.31  5020.2  469.32  5041.9  470.32  5092.3  473.51  5132.5  475.01
  5197.9  476.86  5215.9  476.84  5231.3  477.96  5320.0  480.71  5451.4  483.31
#Mann=5,-1,0
  4462.2    0.05       0  4994.1    0.03       0  5000.1    0.05       0
  5006.1    0.12       0  5041.9    0.05       0
Bank Sta=4994.1,5000.1
Exp/Cntr=0.3,0.1

Type RM Length L Ch R = 1,5184,778,778,778
BEGIN DESCRIPTION:
UNT0127 IN SAND CR 5.0
END DESCRIPTION:
XS GIS Cut Line= 3
      3539142.41     10589741.20      3538934.08     10589452.14
      3538374.16     10589014.62
#Sta/Elev= 30
  4415.1  474.74  4508.3  474.70  4579.5  475.24  4594.2  474.49  4644.6  474.22
  4730.5  471.71  4775.8  471.21  4801.1  470.17  4859.0  469.44  4873.4  469.66
  4900.8  469.24  4929.5  470.84  4941.6  470.78  4958.5  470.35  4972.9  469.31
  4987.4  467.58  4998.9  462.74  5001.6  462.24  5004.9  462.74  5015.0  469.36
  5022.7  470.91  5078.8  470.18  5101.3  470.53  5157.4  470.72  5189.2  471.92
  5221.6  473.26  5236.1  473.10  5271.4  474.03  5343.7  476.91  5482.0  479.16
#Mann=6,-1,0
  4415.1    0.05       0  4941.6    0.12       0  4998.9    0.07       0
  5004.9    0.12       0  5101.3    0.16       0  5189.2    0.05       0
Bank Sta=4998.9,5004.9
Exp/Cntr=0.3,0.1

Type RM Length L Ch R = 1,4406,754,754,754
BEGIN DESCRIPTION:
UNT0127 IN SAND CR 4.0
END DESCRIPTION:
XS GIS Cut Line= 3
      3539357.88     10589652.83      3539327.51     10589266.58
      3538689.46     10588702.32
#Sta/Elev= 30
  4054.2  474.33  4396.4  471.39  4555.6  469.12  4625.9  466.77  4657.8  468.15
  4661.9  468.79  4689.4  467.14  4711.2  467.62  4732.1  470.03  4746.3  468.50
  4809.9  469.55  4888.6  467.95  4895.2  465.76  4909.7  466.55  4916.1  465.17
  4944.6  464.86  4952.1  466.28  4958.8  464.22  4966.3  463.77  4970.0  460.25
  4972.8  459.75  4976.0  460.25  4978.4  460.44  5001.5  462.70  5022.9  468.56
  5048.6  470.31  5072.6  472.81  5122.2  473.18  5171.3  474.52  5293.4  474.74
#Mann=8,-1,0
  4054.2    0.05       0  4657.8    0.12       0  4909.7    0.16       0
  4970.0    0.07       0  4976.0    0.16       0  4978.4    0.12       0
  5048.6    0.16       0  5122.2    0.05       0
Bank Sta=4970,4976
Exp/Cntr=0.3,0.1

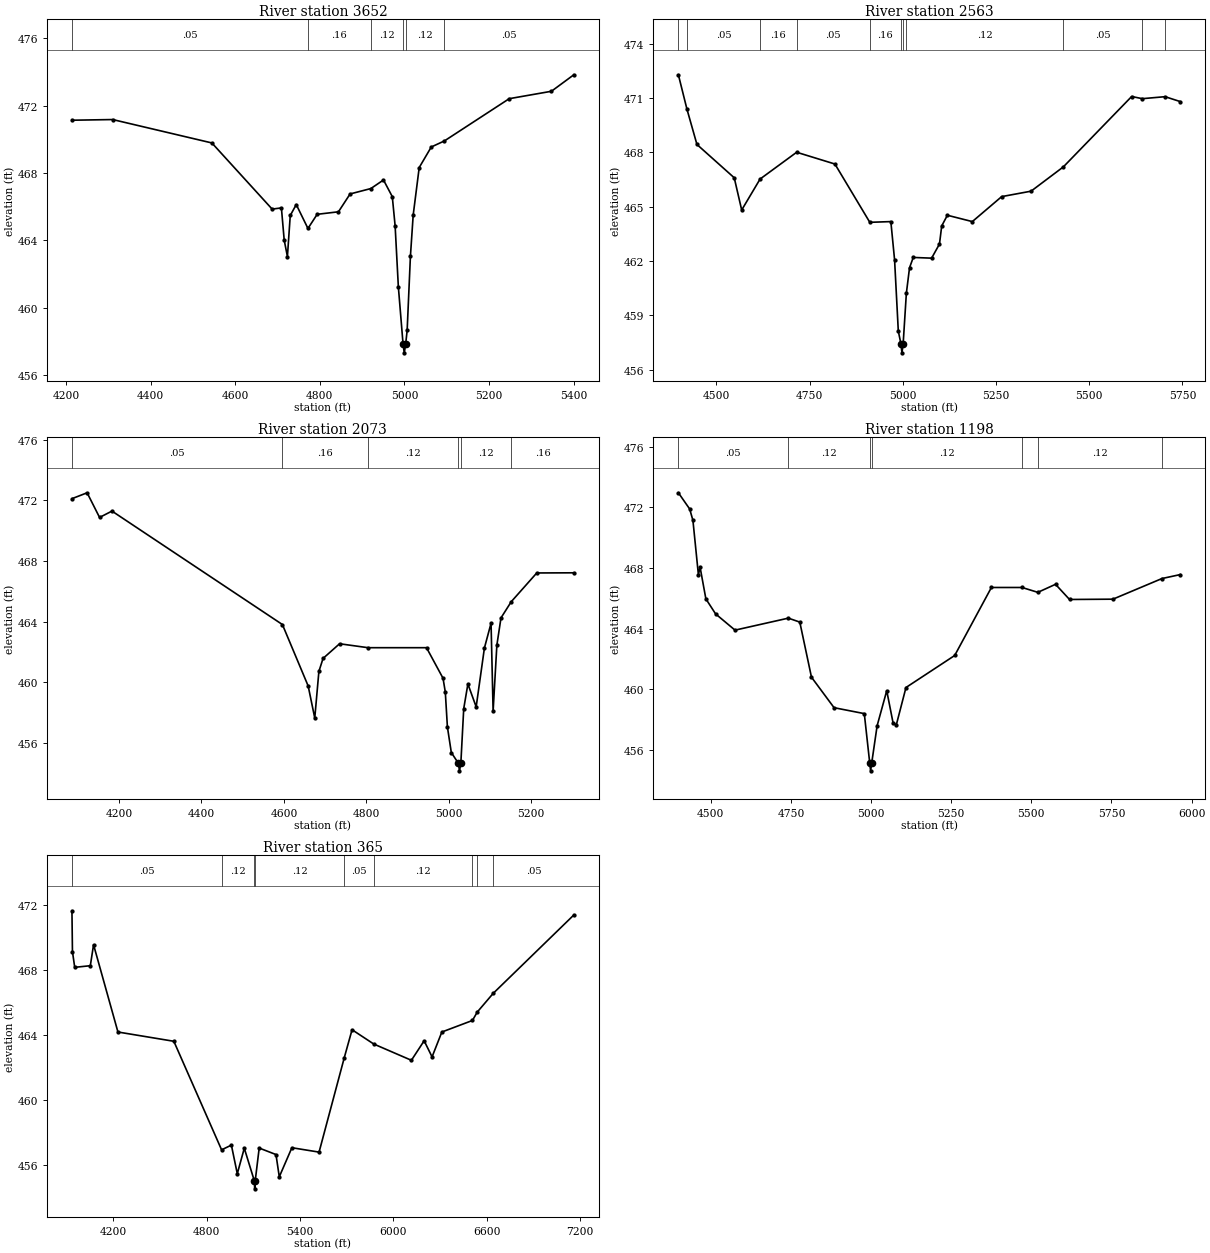
Type RM Length L Ch R = 1,3652,1089,1089,1089
BEGIN DESCRIPTION:
UNT0127 IN SAND CR 3.0
END DESCRIPTION:
XS GIS Cut Line= 3
      3539535.75     10589387.60      3539557.45     10589057.72
      3538995.96     10588412.66
#Sta/Elev= 30
  4214.4  471.14  4310.6  471.18  4545.0  469.79  4687.4  465.86  4709.3  465.93
  4715.9  464.02  4723.5  463.04  4730.2  465.48  4744.4  466.13  4772.0  464.71
  4793.8  465.55  4844.1  465.70  4871.6  466.76  4920.6  467.08  4950.5  467.59
  4971.3  466.60  4978.0  464.86  4985.6  461.25  4996.8  457.82  4999.6  457.32
  5002.8  457.82  5006.4  458.65  5014.1  463.05  5020.7  465.51  5034.9  468.33
  5063.4  469.55  5094.4  469.91  5247.6  472.42  5347.3  472.86  5400.2  473.84
#Mann=6,-1,0
  4214.4    0.05       0  4772.0    0.16       0  4920.6    0.12       0
  4996.8    0.07       0  5002.8    0.12       0  5094.4    0.05       0
Bank Sta=4996.8,5002.8
Exp/Cntr=0.3,0.1

Type RM Length L Ch R = 1,2563,490,490,490
BEGIN DESCRIPTION:
UNT0127 IN SAND CR 2.0
END DESCRIPTION:
XS GIS Cut Line= 4
      3539829.92     10589121.43      3539829.92     10588600.58
      3539835.13     10588454.75      3539262.18     10588090.14
#Sta/Elev= 30
  4398.2  472.29  4421.2  470.39  4448.0  468.44  4548.0  466.60  4568.0  464.82
  4617.3  466.53  4715.4  468.01  4818.0  467.36  4911.6  464.14  4968.0  464.18
  4978.0  462.07  4988.0  458.13  4995.0  457.43  4997.8  456.93  5001.0  457.43
  5009.6  460.22  5018.1  461.63  5028.1  462.20  5077.3  462.16  5098.4  462.94
  5104.4  463.94  5119.6  464.53  5186.5  464.18  5265.2  465.56  5344.0  465.86
  5430.5  467.20  5613.8  471.09  5642.5  470.97  5703.4  471.08  5744.1  470.81
#Mann=11,-1,0
  4398.2    0.16       0  4421.2    0.05       0  4617.3    0.16       0
  4715.4    0.05       0  4911.6    0.16       0  4995.0    0.07       0
  5001.0    0.16       0  5009.6    0.12       0  5430.5    0.05       0
  5642.5     0.1       0  5703.4    0.05       0
Bank Sta=4995,5001
Exp/Cntr=0.3,0.1

Type RM Length L Ch R = 1,2073,875,875,875
BEGIN DESCRIPTION:
UNT0127 IN SAND CR 2.1
END DESCRIPTION:
XS GIS Cut Line= 2
      3540168.46     10589168.33      3540059.16     10587955.65
#Sta/Elev= 30
  4085.8  472.12  4122.6  472.51  4152.8  470.88  4182.9  471.30  4596.4  463.80
  4658.9  459.74  4674.9  457.62  4684.9  460.70  4695.0  461.56  4735.1  462.53
  4804.2  462.27  4946.0  462.27  4986.1  460.25  4991.6  459.34  4996.7  457.03
  5006.2  455.34  5023.3  454.63  5026.0  454.13  5029.3  454.63  5036.3  458.24
  5046.4  459.87  5066.5  458.36  5086.5  462.25  5102.6  463.89  5107.6  458.08
  5116.7  462.44  5126.7  464.24  5151.6  465.31  5213.5  467.21  5303.4  467.22
#Mann=6,-1,0
  4085.8    0.05       0  4596.4    0.16       0  4804.2    0.12       0
  5023.3    0.07       0  5029.3    0.12       0  5151.6    0.16       0
Bank Sta=5023.3,5029.3
Exp/Cntr=0.3,0.1

Type RM Length L Ch R = 1,1198,833,833,833
BEGIN DESCRIPTION:
UNT0127 IN SAND CR 1.0
END DESCRIPTION:
XS GIS Cut Line= 4
      3540467.94     10588876.59      3540538.25     10588387.04
      3540533.04     10588165.68      3540022.86     10587486.31
#Sta/Elev= 30
  4398.9  472.96  4434.2  471.89  4444.3  471.14  4461.4  467.55  4466.5  468.07
  4484.7  465.97  4515.0  464.98  4575.6  463.91  4741.9  464.70  4777.7  464.44
  4814.1  460.81  4884.6  458.80  4978.9  458.41  4995.9  455.14  4998.6  454.64
  5001.9  455.14  5018.9  457.61  5048.9  459.92  5068.9  457.77  5078.9  457.68
  5108.9  460.13  5260.9  462.24  5375.4  466.72  5471.1  466.72  5520.3  466.40
  5575.4  466.93  5619.1  465.93  5754.5  465.95  5907.5  467.31  5964.5  467.57
#Mann=7,-1,0
  4398.9    0.05       0  4741.9    0.12       0  4995.9    0.07       0
  5001.9    0.12       0  5471.1    0.16       0  5520.3    0.12       0
  5907.5    0.05       0
Bank Sta=4995.9,5001.9
Exp/Cntr=0.3,0.1

Type RM Length L Ch R = 1,365,0,0,0
BEGIN DESCRIPTION:
UNT0127 IN SAND CR 1.1
END DESCRIPTION:
XS GIS Cut Line= 5
      3540515.22     10588909.03      3541209.68     10588395.13
      3541379.82     10588051.38      3541084.68     10587582.63
      3539798.58     10586975.98
#Sta/Elev= 30
  3935.3  471.66  3938.5  469.15  3953.1  468.18  4053.3  468.28  4074.1  469.57
  4230.7  464.20  4589.7  463.63  4896.4  456.95  4959.3  457.24  4997.3  455.48
  5042.2  457.05  5106.5  455.05  5109.2  454.55  5112.5  455.05  5137.9  457.06
  5245.8  456.66  5267.0  455.29  5347.9  457.08  5522.5  456.81  5684.7  462.63
  5734.4  464.34  5873.9  463.46  6115.5  462.46  6197.3  463.66  6248.3  462.67
  6311.1  464.20  6507.5  464.91  6538.7  465.43  6641.1  466.58  7158.7  471.40
#Mann=9,-1,0
  3935.3    0.05       0  4896.4    0.12       0  5106.5    0.07       0
  5112.5    0.12       0  5684.7    0.05       0  5873.9    0.12       0
  6507.5    0.05       0  6538.7    0.12       0  6641.1    0.05       0
Bank Sta=5106.5,5112.5
Exp/Cntr=0.3,0.1

Chan Stop Cuts=-1