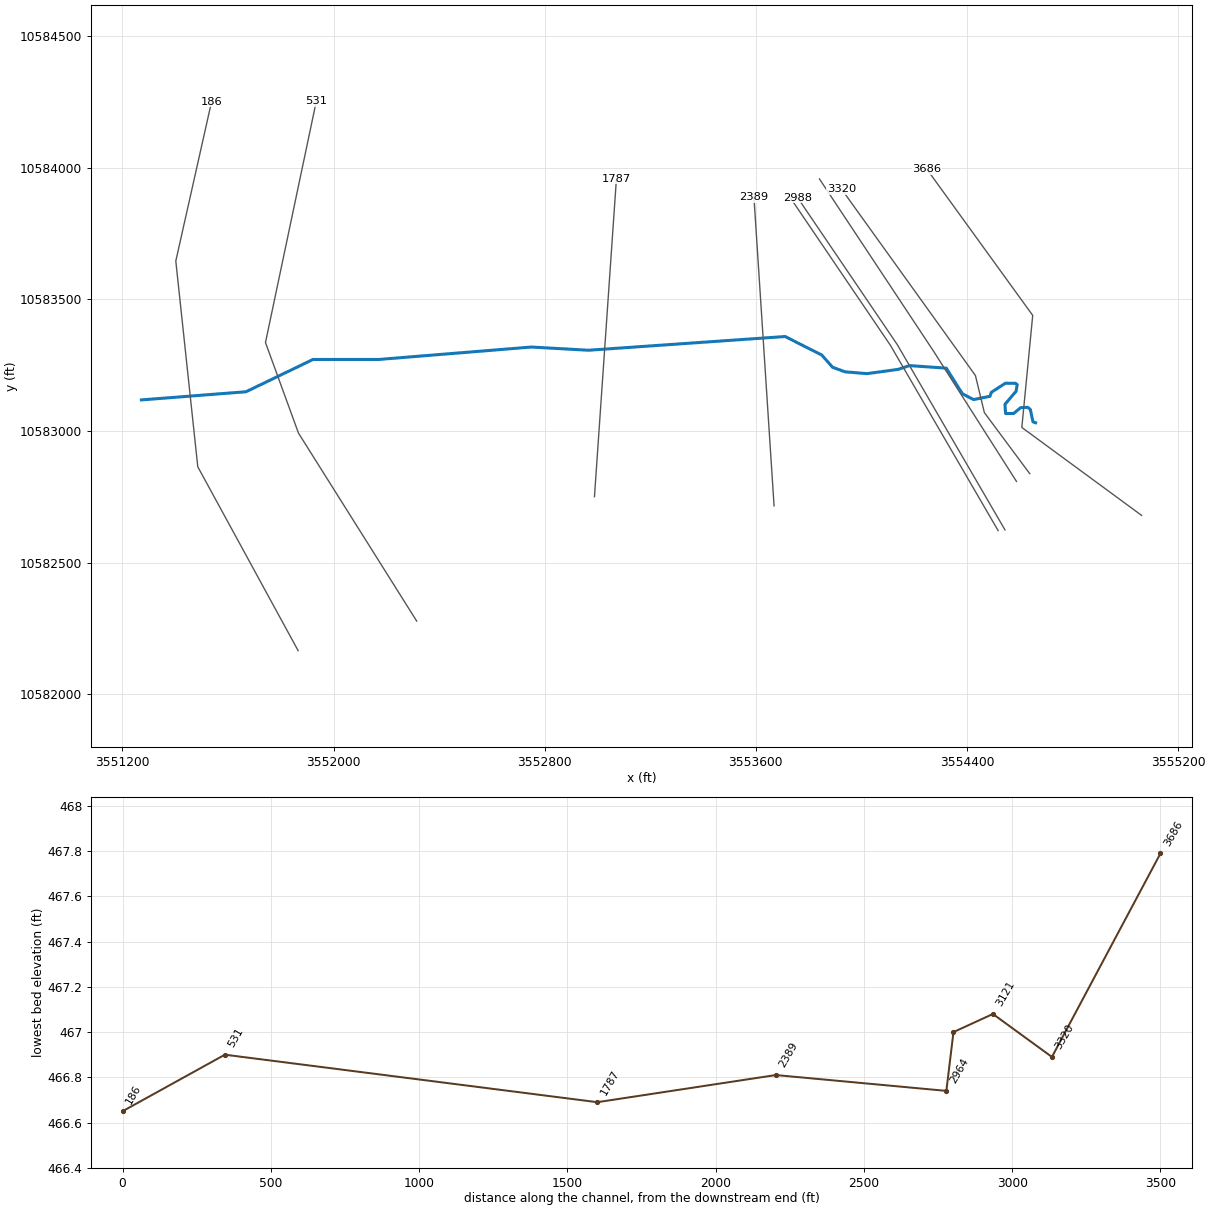
--- UNT0129 IN SAND CR.prj (project) ---

Proj Title=UNT0129 IN SAND CR Base Level Engineering
Current Plan=p01
Default Exp/Contr=0.3,0.1
English Units
Geom File=g01
Flow File=f01
Plan File=p01
BEGIN DESCRIPTION:
UNT0129 IN SAND CR
END DESCRIPTION:

--- UNT0129 IN SAND CR.p01 (plan) ---

Plan Title=Multiple Run
Short Identifier=Multiple
Geom File=g01
Flow File=f01
Subcritical Flow
K Sum by GR= 0
Std Step Tol= 0.01
Critical Tol= 0.01
Num of Std Step Trials= 20
Max Error Tol= 0.3
Flow Tol Ratio= 0.001
Split Flow NTrial= 30
Split Flow Tol= 0.02
Split Flow Ratio= 0.02
Log Output Level= 0
Friction Slope Method= 1
Unsteady Friction Slope Method= 2
Unsteady Bridges Friction Slope Method= 1
Parabolic Critical Depth
Global Vel Dist=  1 , 1 , 1
Global Log Level= 0
CheckData=True
Encroach Param= -1, 0, 0, 0
BEGIN DESCRIPTION:
Multiple Run
END DESCRIPTION:

--- UNT0129 IN SAND CR.f01 (steady flow) ---

Flow Title=Multiple
Number of Profiles=7
Profile Names=10-year,25-year,50-year,1pct_min,100-year,1pct_plu,500-year
River Rch & RM= UNT0129 IN SAND ,Reach-1,3686
     877    1187    1438    1272    1721    2327    2453
Boundary for River Rch & Prof#=UNT0129 IN SAND ,Reach-1,1
Up Type=0
Dn Type=3
Dn Slope=0.005
Boundary for River Rch & Prof#=UNT0129 IN SAND ,Reach-1,2
Up Type=0
Dn Type=3
Dn Slope=0.005
Boundary for River Rch & Prof#=UNT0129 IN SAND ,Reach-1,3
Up Type=0
Dn Type=3
Dn Slope=0.005
Boundary for River Rch & Prof#=UNT0129 IN SAND ,Reach-1,4
Up Type=0
Dn Type=3
Dn Slope=0.005
Boundary for River Rch & Prof#=UNT0129 IN SAND ,Reach-1,5
Up Type=0
Dn Type=3
Dn Slope=0.005
Boundary for River Rch & Prof#=UNT0129 IN SAND ,Reach-1,6
Up Type=0
Dn Type=3
Dn Slope=0.005
Boundary for River Rch & Prof#=UNT0129 IN SAND ,Reach-1,7
Up Type=0
Dn Type=3
Dn Slope=0.005

--- UNT0129 IN SAND CR.g01 (geometry) ---

Geom Title=Existing Conditions

River Reach=UNT0129 IN SAND ,Reach-1
Reach XY= 30
      3554660.10     10583031.11      3554650.17     10583034.94
      3554640.19     10583081.60      3554630.42     10583089.84
      3554603.51     10583088.76      3554577.04     10583066.62
      3554546.44     10583066.19      3554543.84     10583101.13
      3554585.94     10583150.82      3554590.49     10583175.56
      3554583.77     10583181.20      3554545.57     10583181.42
      3554492.59     10583146.95      3554487.20     10583131.94
      3554424.91     10583119.36      3554382.77     10583141.35
      3554321.66     10583238.57      3554181.80     10583248.33
      3554137.90     10583233.76      3554021.23     10583217.79
      3553937.90     10583224.73      3553890.68     10583242.09
      3553849.71     10583288.62      3553711.00     10583358.69
      3552966.21     10583306.61      3552749.20     10583318.76
      3552171.65     10583271.64      3551922.11     10583271.64
      3551668.18     10583149.05      3551271.88     10583118.05

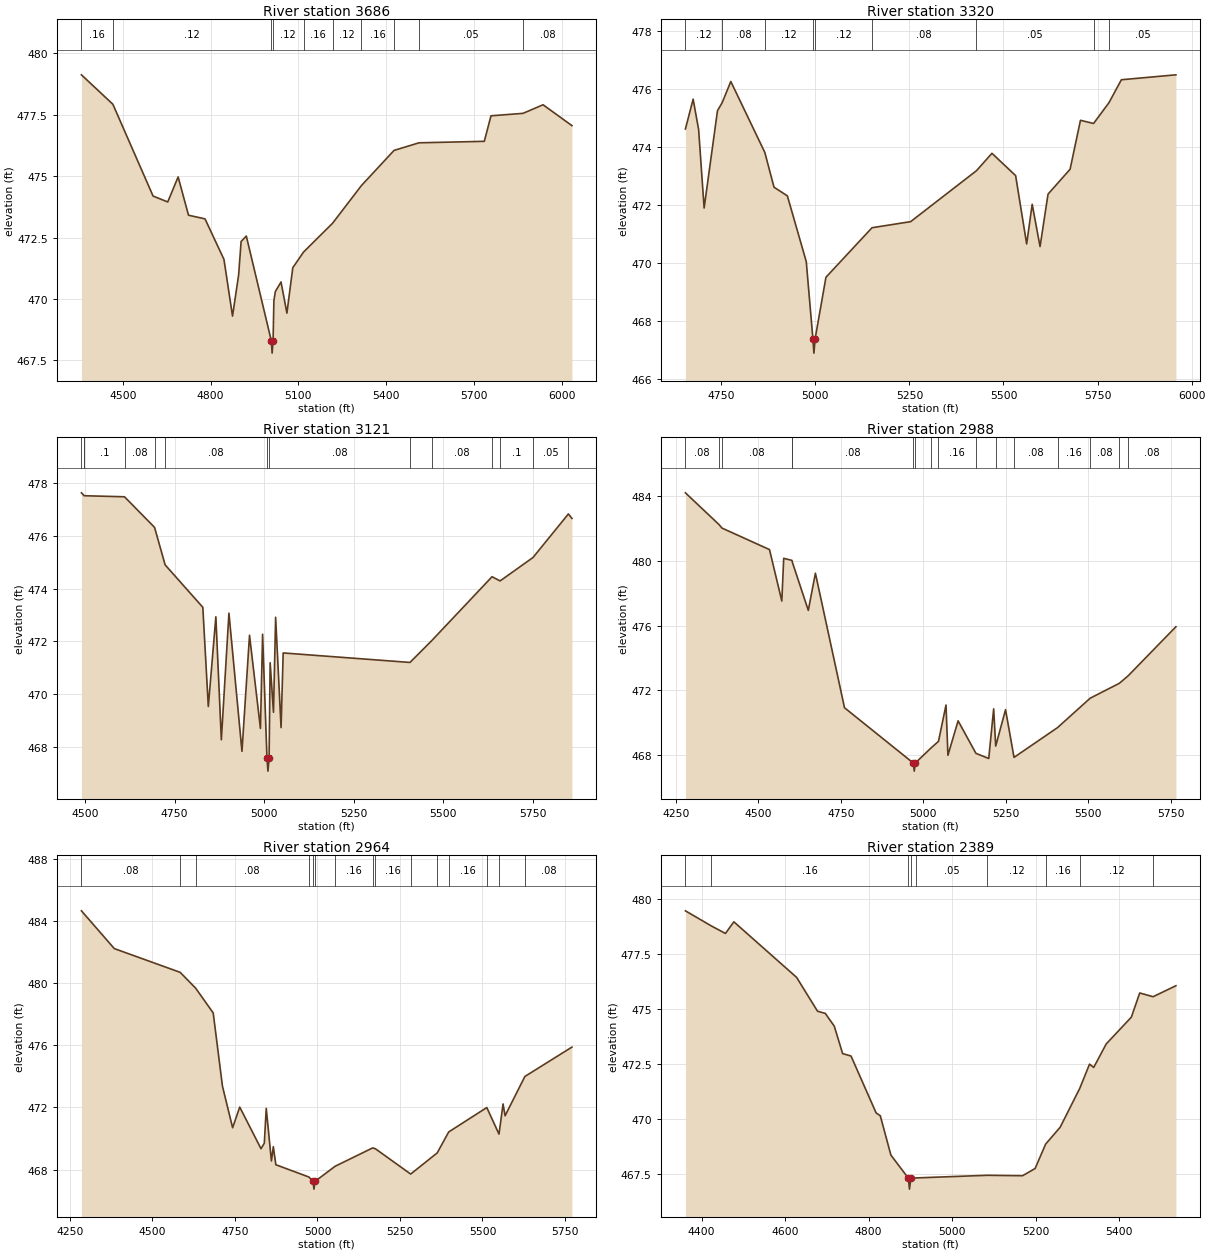
Type RM Length L Ch R = 1,3686,366,366,366
BEGIN DESCRIPTION:
UNT0129 IN SAND CR 3.2
END DESCRIPTION:
XS GIS Cut Line= 4
      3555061.75     10582679.75      3554607.94     10583013.54
      3554649.17     10583438.89      3554247.71     10583994.42
#Sta/Elev= 30
  4358.7  479.13  4466.2  477.93  4603.5  474.19  4653.6  473.95  4689.1  474.97
  4724.6  473.41  4781.0  473.26  4845.7  471.61  4875.0  469.30  4895.9  470.98
  4904.3  472.34  4922.1  472.56  5007.6  468.29  5010.3  467.79  5013.6  468.29
  5016.3  469.93  5021.4  470.30  5040.7  470.69  5060.8  469.42  5080.9  471.27
  5117.8  471.91  5216.7  473.08  5315.6  474.62  5426.9  476.05  5512.2  476.36
  5735.3  476.42  5758.2  477.46  5867.7  477.56  5936.1  477.91  6034.8  477.06
#Mann=10,-1,0
  4358.7    0.16       0  4466.2    0.12       0  5007.6    0.07       0
  5013.6    0.12       0  5117.8    0.16       0  5216.7    0.12       0
  5315.6    0.16       0  5426.9    0.12       0  5512.2    0.05       0
  5867.7    0.08       0
Bank Sta=5007.6,5013.6
Exp/Cntr=0.3,0.1

Type RM Length L Ch R = 1,3320,199,199,199
BEGIN DESCRIPTION:
UNT0129 IN SAND CR 3.1
END DESCRIPTION:
XS GIS Cut Line= 4
      3554637.82     10582838.21      3554465.96     10583069.96
      3554432.11     10583210.58      3553925.12     10583917.77
#Sta/Elev= 30
  4654.9  474.63  4675.4  475.66  4690.0  474.61  4704.6  471.90  4740.1  475.26
  4752.6  475.54  4775.5  476.27  4865.9  473.82  4890.3  472.62  4925.8  472.32
  4976.0  470.05  4993.6  467.39  4996.3  466.89  4999.6  467.39  5028.3  469.51
  5150.7  471.22  5253.3  471.43  5428.3  473.19  5469.4  473.79  5532.3  473.02
  5561.6  470.66  5576.3  472.03  5597.2  470.57  5618.4  472.38  5677.0  473.24
  5704.6  474.93  5739.4  474.82  5780.4  475.54  5813.3  476.33  5958.2  476.50
#Mann=9,-1,0
  4654.9    0.12       0  4752.6    0.08       0  4865.9    0.12       0
  4993.6    0.07       0  4999.6    0.12       0  5150.7    0.08       0
  5428.3    0.05       0  5739.4    0.08       0  5780.4    0.05       0
Bank Sta=4993.6,4999.6
Exp/Cntr=0.3,0.1

Type RM Length L Ch R = 1,3121,133,133,133
BEGIN DESCRIPTION:
UNT0129 IN SAND CR 3.0
END DESCRIPTION:
XS GIS Cut Line= 3
      3554587.70     10582808.52      3554272.82     10583303.90
      3553841.10     10583956.91
#Sta/Elev= 30
  4489.8  477.63  4496.7  477.53  4497.4  477.52  4610.1  477.48  4694.0  476.32
  4723.5  474.90  4828.8  473.29  4844.1  469.53  4865.2  472.93  4880.5  468.27
  4901.7  473.07  4938.1  467.83  4959.2  472.23  4989.7  468.70  4995.7  472.27
  5007.9  467.58  5010.6  467.08  5013.9  467.58  5016.8  471.19  5026.1  469.31
  5032.1  472.91  5047.3  468.73  5053.2  471.56  5407.3  471.20  5468.3  472.03
  5636.5  474.45  5659.0  474.29  5751.0  475.18  5849.7  476.83  5859.6  476.66
#Mann=14,-1,0
  4489.8    0.08       0  4496.7    0.12       0  4497.4     0.1       0
  4610.1    0.08       0  4694.0     0.1       0  4723.5    0.08       0
  5007.9    0.07       0  5013.9    0.08       0  5407.3    0.05       0
  5468.3    0.08       0  5636.5    0.05       0  5659.0     0.1       0
  5751.0    0.05       0  5849.7     0.1       0
Bank Sta=5007.9,5013.9
Exp/Cntr=0.3,0.1

Type RM Length L Ch R = 1,2988,24,24,24
BEGIN DESCRIPTION:
UNT0129 IN SAND CR 2.2
END DESCRIPTION:
XS GIS Cut Line= 3
      3554544.07     10582624.68      3554136.10     10583327.77
      3553758.50     10583885.49
#Sta/Elev= 30
  4279.0  484.21  4380.7  482.25  4389.8  482.03  4533.8  480.70  4571.1  477.52
  4576.9  480.16  4602.0  480.03  4602.9  479.93  4651.4  476.94  4672.9  479.24
  4761.1  470.92  4969.6  467.50  4972.4  467.00  4975.6  467.50  5024.2  468.45
  5045.9  468.84  5068.7  471.09  5074.5  467.98  5105.3  470.11  5159.4  468.10
  5198.2  467.78  5213.1  470.85  5219.3  468.55  5249.1  470.80  5274.8  467.85
  5406.6  469.69  5505.6  471.51  5593.9  472.43  5620.9  472.90  5765.4  475.93
#Mann=16,-1,0
  4279.0    0.08       0  4380.7     0.1       0  4389.8    0.08       0
  4602.0    0.05       0  4602.9    0.08       0  4969.6    0.07       0
  4975.6    0.08       0  5024.2    0.12       0  5045.9    0.16       0
  5159.4    0.08       0  5219.3    0.16       0  5274.8    0.08       0
  5406.6    0.16       0  5505.6    0.08       0  5593.9    0.16       0
  5620.9    0.08       0
Bank Sta=4969.6,4975.6
Exp/Cntr=0.3,0.1

Type RM Length L Ch R = 1,2964,575,575,575
BEGIN DESCRIPTION:
UNT0129 IN SAND CR 2.3
END DESCRIPTION:
XS GIS Cut Line= 3
      3554518.02     10582622.08      3554110.06     10583325.17
      3553732.46     10583882.89
#Sta/Elev= 30
  4284.7  484.65  4384.3  482.22  4584.0  480.69  4630.9  479.67  4684.0  478.08
  4712.0  473.37  4742.8  470.69  4764.4  472.02  4828.9  469.34  4838.9  469.70
  4844.7  471.94  4860.4  468.55  4866.2  469.47  4873.8  468.31  4974.0  467.52
  4986.6  467.24  4989.3  466.74  4992.6  467.24  5053.4  468.21  5167.0  469.39
  5175.4  469.34  5282.4  467.71  5362.8  469.07  5397.7  470.42  5513.1  471.99
  5550.1  470.28  5562.4  472.22  5568.5  471.46  5628.5  473.99  5771.1  475.88
#Mann=15,-1,0
  4284.7    0.08       0  4584.0    0.05       0  4630.9    0.08       0
  4974.0    0.12       0  4986.6    0.07       0  4992.6    0.12       0
  5053.4    0.16       0  5167.0    0.08       0  5175.4    0.16       0
  5282.4    0.08       0  5362.8    0.12       0  5397.7    0.16       0
  5513.1    0.08       0  5550.1    0.16       0  5628.5    0.08       0
Bank Sta=4986.6,4992.6
Exp/Cntr=0.3,0.1

Type RM Length L Ch R = 1,2389,602,602,602
BEGIN DESCRIPTION:
UNT0129 IN SAND CR 2.1
END DESCRIPTION:
XS GIS Cut Line= 2
      3553669.09     10582715.92      3553592.79     10583888.14
#Sta/Elev= 30
  4361.3  479.48  4423.6  478.79  4457.2  478.45  4477.3  478.98  4627.6  476.45
  4677.7  474.91  4696.3  474.81  4717.8  474.23  4737.8  472.98  4757.9  472.87
  4818.0  470.28  4828.0  470.15  4853.4  468.36  4895.2  467.31  4897.9  466.81
  4901.2  467.31  4913.8  467.32  5084.3  467.44  5168.7  467.42  5198.8  467.75
  5224.0  468.86  5258.9  469.63  5306.0  471.41  5329.1  472.50  5339.1  472.35
  5369.1  473.42  5429.3  474.64  5449.3  475.74  5481.3  475.57  5536.0  476.07
#Mann=9,-1,0
  4361.3    0.05       0  4423.6    0.16       0  4895.2   0.033       0
  4901.2    0.16       0  4913.8    0.05       0  5084.3    0.12       0
  5224.0    0.16       0  5306.0    0.12       0  5481.3    0.08       0
Bank Sta=4895.2,4901.2
Exp/Cntr=0.3,0.1

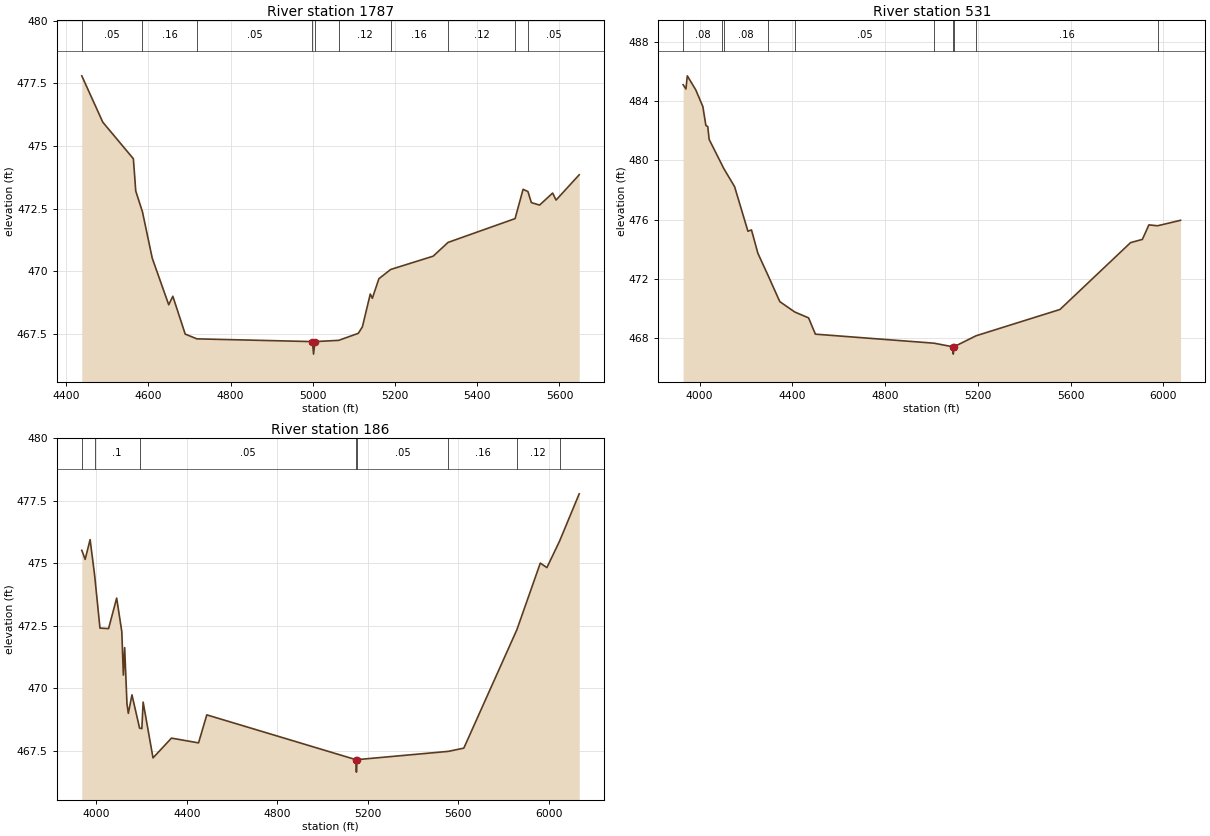
Type RM Length L Ch R = 1,1787,1256,1256,1256
BEGIN DESCRIPTION:
UNT0129 IN SAND CR 2.0
END DESCRIPTION:
XS GIS Cut Line= 2
      3552988.53     10582750.65      3553071.78     10583957.78
#Sta/Elev= 30
  4438.0  477.80  4489.1  475.95  4563.5  474.49  4569.3  473.20  4585.6  472.37
  4609.4  470.52  4649.5  468.66  4659.5  469.00  4689.6  467.49  4717.9  467.30
  4999.0  467.19  5001.8  466.69  5005.0  467.19  5062.8  467.24  5110.6  467.52
  5120.6  467.78  5139.8  469.09  5144.8  468.92  5160.7  469.70  5189.4  470.07
  5292.7  470.60  5329.0  471.15  5492.0  472.10  5511.5  473.27  5523.3  473.18
  5531.6  472.74  5551.6  472.64  5583.4  473.12  5591.7  472.84  5648.0  473.85
#Mann=10,-1,0
  4438.0    0.05       0  4585.6    0.16       0  4717.9    0.05       0
  4999.0   0.033       0  5005.0    0.05       0  5062.8    0.12       0
  5189.4    0.16       0  5329.0    0.12       0  5492.0    0.16       0
  5523.3    0.05       0
Bank Sta=4999,5005
Exp/Cntr=0.3,0.1

Type RM Length L Ch R = 1,531,345,345,345
BEGIN DESCRIPTION:
UNT0129 IN SAND CR 1.0
END DESCRIPTION:
XS GIS Cut Line= 4
      3552314.89     10582278.58      3551866.96     10582992.13
      3551741.96     10583335.88      3551934.68     10584252.58
#Sta/Elev= 30
  3928.6  485.12  3940.7  484.83  3946.6  485.72  3983.1  484.77  4013.7  483.64
  4026.7  482.36  4034.9  482.29  4040.8  481.42  4097.0  479.67  4103.9  479.45
  4150.4  478.23  4208.1  475.21  4223.4  475.30  4251.0  473.72  4295.5  472.20
  4345.5  470.45  4409.9  469.75  4469.7  469.35  4499.0  468.25  5010.3  467.64
  5090.8  467.40  5093.6  466.90  5096.8  467.40  5191.6  468.14  5553.7  469.92
  5858.1  474.44  5909.1  474.66  5937.1  475.64  5974.4  475.58  6073.6  475.95
#Mann=10,-1,0
  3928.6    0.08       0  4097.0    0.05       0  4103.9    0.08       0
  4295.5    0.16       0  4409.9    0.05       0  5010.3    0.12       0
  5090.8   0.033       0  5096.8    0.12       0  5191.6    0.16       0
  5974.4    0.05       0
Bank Sta=5090.8,5096.8
Exp/Cntr=0.3,0.1

Type RM Length L Ch R = 1,186,0,0,0
BEGIN DESCRIPTION:
UNT0129 IN SAND CR 1.1
END DESCRIPTION:
XS GIS Cut Line= 4
      3551865.68     10582166.19      3551485.47     10582864.11
      3551402.13     10583645.36      3551537.55     10584249.52
#Sta/Elev= 30
  3935.3  475.52  3950.2  475.16  3972.1  475.95  3991.7  474.56  4015.7  472.41
  4053.7  472.39  4089.5  473.61  4112.3  472.27  4119.2  470.53  4124.9  471.63
  4135.1  469.38  4141.1  469.00  4157.2  469.74  4190.9  468.41  4200.9  468.39
  4206.6  469.45  4250.3  467.22  4331.9  468.01  4451.6  467.82  4488.1  468.94
  5147.0  467.15  5149.7  466.65  5153.0  467.15  5556.0  467.48  5624.7  467.61
  5859.5  472.35  5962.9  475.01  5992.1  474.83  6048.1  475.89  6134.9  477.78
#Mann=8,-1,0
  3935.3    0.08       0  3991.7     0.1       0  4190.9    0.05       0
  5147.0   0.033       0  5153.0    0.05       0  5556.0    0.16       0
  5859.5    0.12       0  6048.1    0.05       0
Bank Sta=5147,5153
Exp/Cntr=0.3,0.1

Chan Stop Cuts=-1