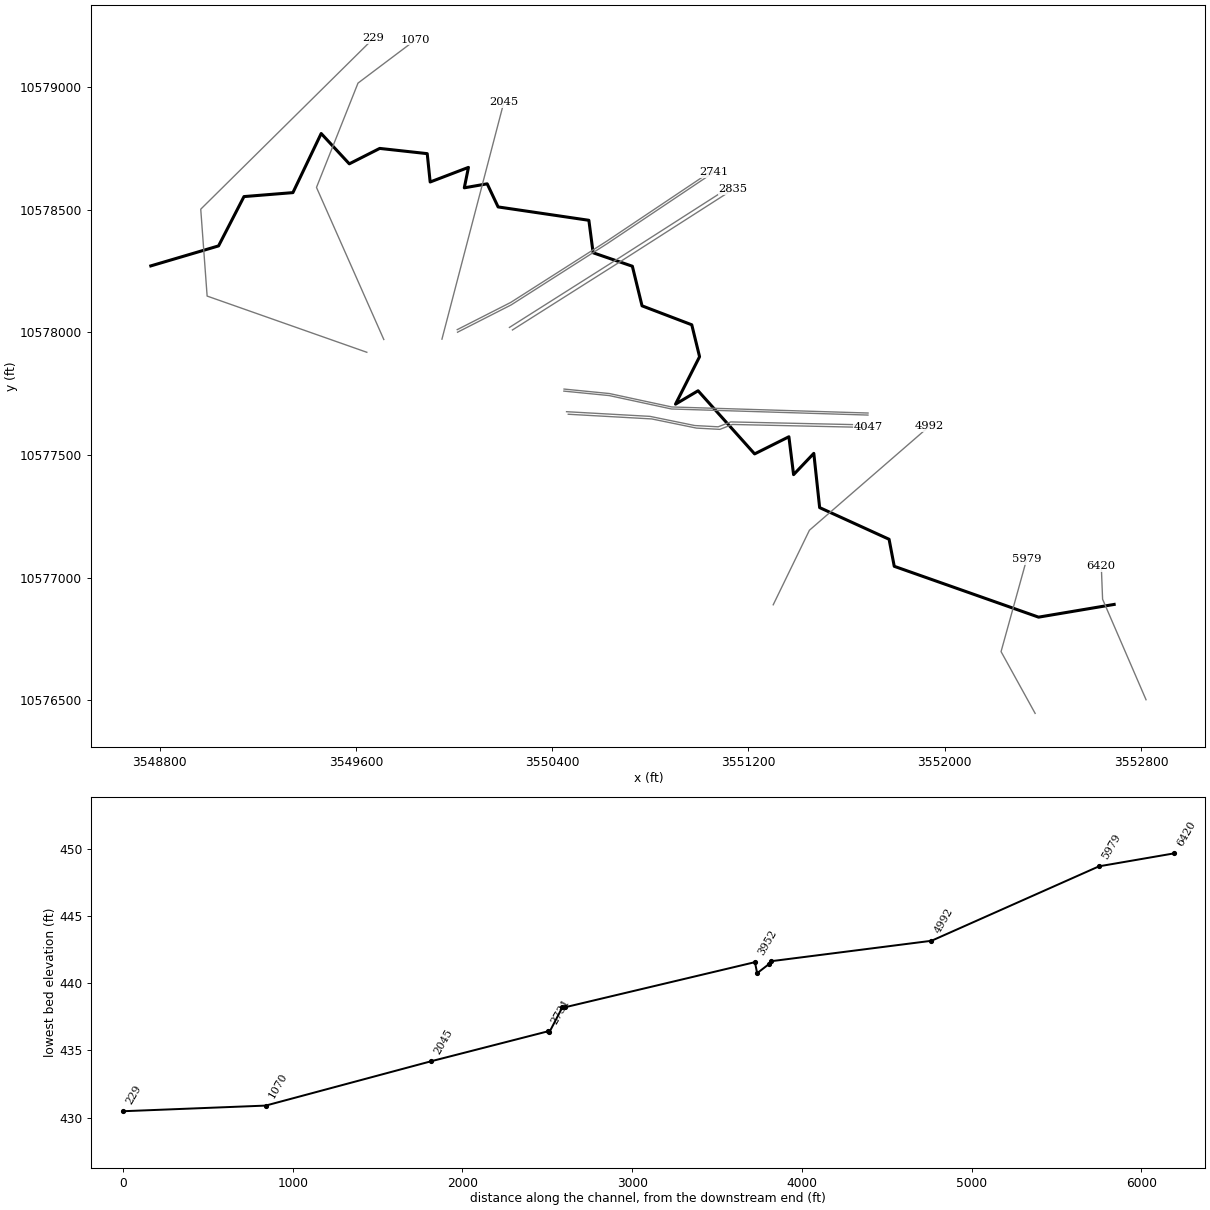
--- UNT0130 IN SAND CR.prj (project) ---

Proj Title=UNT0130 IN SAND CR Base Level Engineering
Current Plan=p01
Default Exp/Contr=0.3,0.1
English Units
Geom File=g01
Flow File=f01
Plan File=p01
Y Axis Title=Elevation
X Axis Title(PF)=Main Channel Distance
X Axis Title(XS)=Station
BEGIN DESCRIPTION:
UNT0130 IN SAND CR
END DESCRIPTION:
DSS Export Rating Curves= 0
DSS Export Rating Curve Sorted= 0
DSS Export Volume Flow Curves= 0
DXF OffsetX= 0
DXF OffsetY= 0
DXF ScaleX= 1
DXF ScaleY= 10

--- UNT0130 IN SAND CR.p01 (plan) ---

Plan Title=Multiple Run
Short Identifier=Multiple
Geom File=g01
Flow File=f01
Subcritical Flow
K Sum by GR= 0
Std Step Tol= 0.01
Critical Tol= 0.01
Num of Std Step Trials= 20
Max Error Tol= 0.3
Flow Tol Ratio= 0.001
Split Flow NTrial= 30
Split Flow Tol= 0.02
Split Flow Ratio= 0.02
Log Output Level= 0
Friction Slope Method= 1
Unsteady Friction Slope Method= 2
Unsteady Bridges Friction Slope Method= 1
Parabolic Critical Depth
Global Vel Dist=  1 , 1 , 1
Global Log Level= 0
CheckData=True
Encroach Param= -1, 0, 0, 0
BEGIN DESCRIPTION:
Multiple Run
END DESCRIPTION:

--- UNT0130 IN SAND CR.f01 (steady flow) ---

Flow Title=Multiple
Number of Profiles=7
Profile Names=10-year,25-year,50-year,1pct_min,100-year,1pct_plu,500-year
River Rch & RM= UNT0130 IN SAND ,Reach-1,6420
    1060    1444    1758    1559    2109    2852    3027
Boundary for River Rch & Prof#=UNT0130 IN SAND ,Reach-1,1
Up Type=0
Dn Type=3
Dn Slope=0.005
Boundary for River Rch & Prof#=UNT0130 IN SAND ,Reach-1,2
Up Type=0
Dn Type=3
Dn Slope=0.005
Boundary for River Rch & Prof#=UNT0130 IN SAND ,Reach-1,3
Up Type=0
Dn Type=3
Dn Slope=0.005
Boundary for River Rch & Prof#=UNT0130 IN SAND ,Reach-1,4
Up Type=0
Dn Type=3
Dn Slope=0.005
Boundary for River Rch & Prof#=UNT0130 IN SAND ,Reach-1,5
Up Type=0
Dn Type=3
Dn Slope=0.005
Boundary for River Rch & Prof#=UNT0130 IN SAND ,Reach-1,6
Up Type=0
Dn Type=3
Dn Slope=0.005
Boundary for River Rch & Prof#=UNT0130 IN SAND ,Reach-1,7
Up Type=0
Dn Type=3
Dn Slope=0.005

--- UNT0130 IN SAND CR.g01 (geometry) ---

Geom Title=Existing Conditions
Program Version=4.10

River Reach=UNT0130 IN SAND ,Reach-1
Reach XY= 30
      3552690.75     10576890.29      3552382.57     10576838.41
      3551794.19     10577045.65      3551773.16     10577155.85
      3551490.05     10577284.98      3551466.28     10577506.09
      3551383.81     10577419.28      3551364.72      10577573.8
      3551224.96     10577503.92      3550994.49      10577761.3
      3550902.48     10577706.61      3551000.57     10577900.19
      3550968.75     10578030.26      3550766.06     10578107.52
      3550726.56     10578268.98      3550566.62     10578323.88
      3550549.26     10578456.26      3550179.25     10578510.73
      3550134.76     10578604.91      3550041.45     10578588.64
      3550058.38     10578671.97      3549902.28     10578612.36
      3549890.29     10578727.96      3549696.66      10578749.3
      3549572.61     10578686.42      3549457.99     10578810.04
      3549342.75     10578569.06      3549143.27     10578552.92
      3549039.63     10578351.87      3548763.43     10578270.32

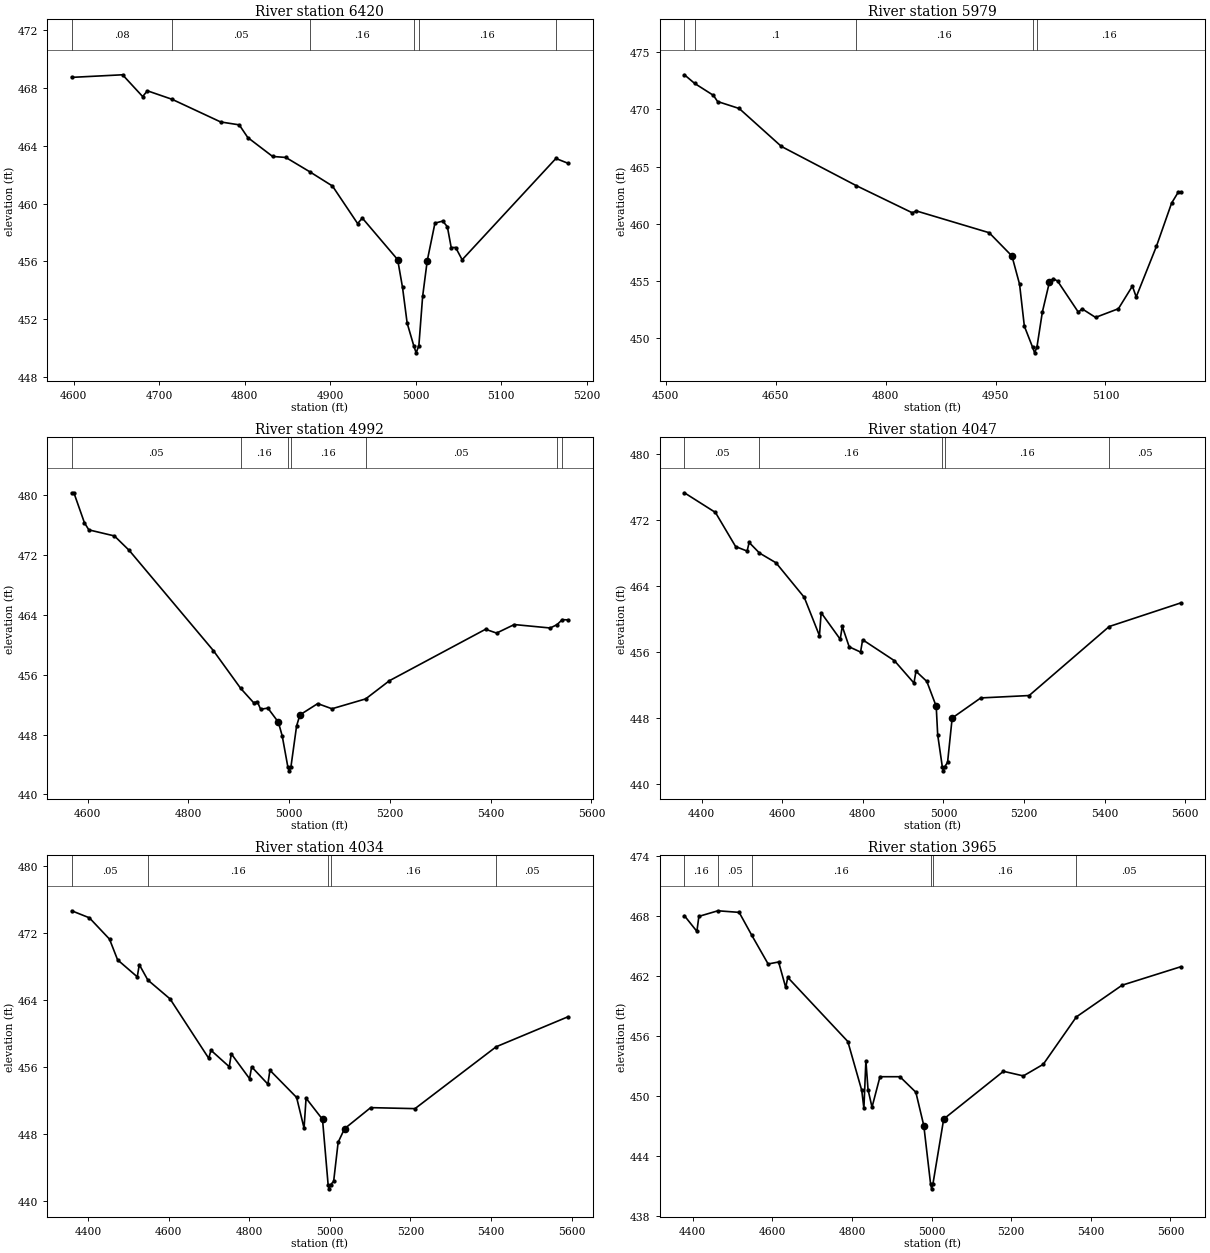
Type RM Length L Ch R = 1 ,6420    ,441,441,441
BEGIN DESCRIPTION:
UNT0130 IN SAND CR 9.1
END DESCRIPTION:
XS GIS Cut Line= 3
      3552820.62     10576501.78      3552643.55     10576911.46
      3552638.34     10577045.15
#Sta/Elev= 30
  4597.8  468.75  4657.3  468.93  4680.8  467.42  4686.3  467.82  4715.2  467.23
    4772  465.66  4793.7  465.46  4803.7  464.58  4832.7  463.27  4848.2   463.2
  4876.1  462.21  4902.7  461.22  4932.1  458.62  4937.6     459  4978.9  456.12
  4984.6  454.19    4990  451.72  4997.7  450.16  5000.5  449.66  5003.7  450.16
  5008.1  453.57  5013.5  456.05  5022.5  458.65  5031.6  458.79    5037   458.4
  5041.5  456.96  5046.7  456.96  5054.3  456.11  5163.9  463.13  5177.9   462.8
#Mann= 6 ,-1 , 0
  4597.8     .08       0  4715.2     .05       0  4876.1     .16       0
  4997.7     .07       0  5003.7     .16       0  5163.9     .05       0
Bank Sta=4978.9,5013.5
XS Rating Curve= 0 ,0
Exp/Cntr=0.3,0.1

Type RM Length L Ch R = 1 ,5979    ,987,987,987
BEGIN DESCRIPTION:
UNT0130 IN SAND CR 9.0
END DESCRIPTION:
XS GIS Cut Line= 3
      3552368.53     10576446.11      3552229.64     10576697.86
      3552333.73     10577073.48
#Sta/Elev= 30
  4525.3  473.03  4539.4  472.27  4564.9  471.23  4570.6  470.69  4600.1  470.08
  4657.7  466.76  4759.9  463.33  4836.5  460.95  4841.7  461.12  4941.3  459.21
  4972.4  457.17  4982.8   454.7  4989.3  451.04  5000.5   449.2  5003.3   448.7
  5006.5   449.2  5013.9  452.27  5023.6   454.9  5028.7  455.19  5034.7  454.98
    5063  452.26  5068.2  452.55  5086.5   451.8  5117.7  452.56  5136.8  454.54
    5142  453.59  5169.6  458.02  5190.3   461.8  5199.1  462.73  5202.6  462.73
#Mann= 5 ,-1 , 0
  4525.3     .08       0  4539.4      .1       0  4759.9     .16       0
  5000.5     .07       0  5006.5     .16       0
Bank Sta=4972.4,5023.6
XS Rating Curve= 0 ,0
Exp/Cntr=0.3,0.1

Type RM Length L Ch R = 1 ,4992    ,945,945,945
BEGIN DESCRIPTION:
UNT0130 IN SAND CR 7.0
END DESCRIPTION:
XS GIS Cut Line= 3
      3551300.81     10576888.81      3551448.39     10577192.65
      3551937.19     10577616.56
#Sta/Elev= 30
  4568.4  480.34  4572.8  480.34  4593.8  476.32  4602.5  475.38  4653.2  474.57
  4682.7  472.63  4849.5  459.25  4903.9  454.18  4929.3  452.29  4936.9  452.39
  4943.5  451.39  4957.8  451.55  4978.6  449.67  4986.3  447.82  4997.5  443.66
  5000.3  443.16  5003.5  443.66  5014.8  449.16  5021.4  450.64  5056.7  452.15
    5085  451.46  5151.9  452.78    5199  455.21  5389.8  462.09  5411.7  461.58
  5446.8  462.72  5518.1  462.26  5531.7  462.71  5542.1  463.38  5553.2  463.34
#Mann= 7 ,-1 , 0
  4568.4     .05       0  4903.9     .16       0  4997.5     .07       0
  5003.5     .16       0  5151.9     .05       0  5531.7     .16       0
  5542.1     .05       0
Bank Sta=4978.6,5021.4
XS Rating Curve= 0 ,0
Exp/Cntr=0.3,0.1

Type RM Length L Ch R = 1 ,4047    ,13,13,13
BEGIN DESCRIPTION:
UNT0130 IN SAND CR 5.3
END DESCRIPTION:
XS GIS Cut Line= 6
      3550465.25     10577665.56      3550805.54     10577646.46
      3550987.83     10577609.13      3551083.32     10577603.92
      3551134.53     10577623.89       3551687.7     10577611.75
#Sta/Elev= 30
  4357.5  475.28  4434.5   472.9  4484.6  468.77  4513.1  468.23  4518.1  469.27
  4543.7  467.99  4584.7  466.81  4654.8  462.63  4692.5  457.99  4696.7  460.77
    4744  457.56  4749.1  459.12  4766.3  456.64  4794.5  456.01  4799.6   457.5
  4878.6  454.96  4926.9  452.26  4931.9  453.69  4958.8  452.46  4982.1  449.45
  4985.8  445.99  4997.2  442.14  4999.9  441.64  5003.2  442.14  5010.3  442.67
  5021.7  448.03  5092.6  450.46  5212.6  450.75  5411.2   459.1  5588.3  461.95
#Mann= 5 ,-1 , 0
  4357.5     .05       0  4543.7     .16       0  4997.2     .07       0
  5003.2     .16       0  5411.2     .05       0
Bank Sta=4982.1,5021.7
XS Rating Curve= 0 ,0
Exp/Cntr=0.3,0.1

Type RM Length L Ch R = 1 ,4034    ,69,69,69
BEGIN DESCRIPTION:
UNT0130 IN SAND CR 5.2
END DESCRIPTION:
XS GIS Cut Line= 6
      3550458.31     10577675.97      3550798.59     10577656.87
      3550980.89     10577619.55      3551076.37     10577614.34
      3551127.59      10577634.3      3551681.37     10577622.15
#Sta/Elev= 30
  4359.4  474.67  4403.3  473.83  4453.3  471.28  4473.4   468.8  4522.2  466.77
  4527.2  468.23  4548.4  466.39  4603.6  464.13  4699.5  457.03  4705.1  457.99
  4750.5  456.02  4755.6  457.56  4800.9  454.59    4806  456.01  4846.3  453.94
  4851.4   455.6  4917.6  452.35  4936.1  448.68  4941.1  452.26  4981.9  449.73
  4995.8  441.92  4998.6  441.42  5001.8  441.92  5009.5   442.3  5020.7  446.99
  5036.6  448.61  5101.4  451.13  5211.4  451.01  5412.9  458.41  5590.8  461.99
#Mann= 5 ,-1 , 0
  4359.4     .05       0  4548.4     .16       0  4995.8     .07       0
  5001.8     .16       0  5412.9     .05       0
Bank Sta=4981.9,5036.6
XS Rating Curve= 0 ,0
Exp/Cntr=0.3,0.1

Type RM Length L Ch R = 1 ,3965    ,13,13,13
BEGIN DESCRIPTION:
UNT0130 IN SAND CR 5.0
END DESCRIPTION:
XS GIS Cut Line= 5
      3550447.41     10577759.87      3550632.35     10577741.64
      3550886.26     10577686.95      3551137.56     10577679.14
      3551687.01     10577662.21
#Sta/Elev= 30
    4379  468.06  4410.4  466.49  4415.4  467.99  4463.2  468.55  4516.6  468.39
  4548.3   466.1  4589.4  463.23  4615.7  463.43  4633.6  460.88  4638.7  461.89
  4789.6  455.48  4824.6  450.59    4830   448.8    4835  453.56  4840.4  450.67
  4850.4  448.91  4870.4  451.96  4920.5  451.96  4960.5  450.41  4980.5  447.07
  4997.5  441.25  5000.2  440.75  5003.5  441.25  5030.5  447.73  5180.6   452.5
  5230.6  452.04  5280.6   453.2  5363.8  457.94  5478.8  461.11  5625.7  462.95
#Mann= 6 ,-1 , 0
    4379     .16       0  4463.2     .05       0  4548.3     .16       0
  4997.5     .07       0  5003.5     .16       0  5363.8     .05       0
Bank Sta=4980.5,5030.5
XS Rating Curve= 0 ,0
Exp/Cntr=0.3,0.1

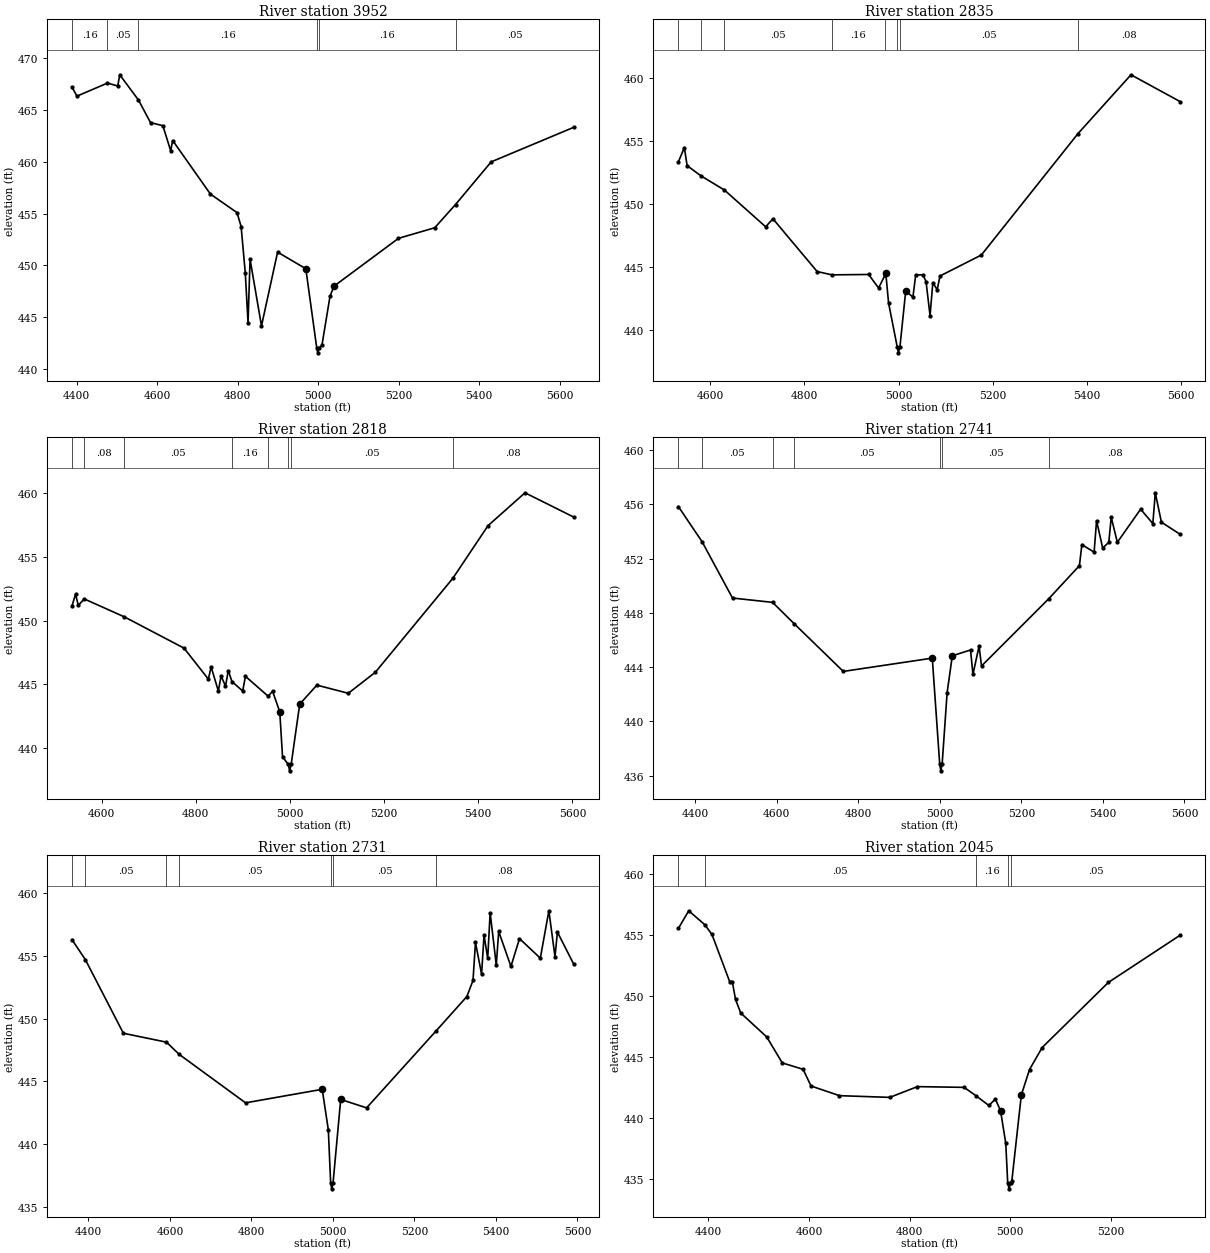
Type RM Length L Ch R = 1 ,3952    ,1117,1117,1117
BEGIN DESCRIPTION:
UNT0130 IN SAND CR 5.1
END DESCRIPTION:
XS GIS Cut Line= 5
      3550448.11     10577768.21      3550633.05     10577749.97
      3550886.95     10577695.29      3551138.26     10577687.47
      3551687.41     10577670.56
#Sta/Elev= 30
  4388.6  467.19  4401.1  466.32  4476.8  467.58  4502.3   467.3  4507.3  468.38
  4553.7  465.95  4583.7  463.77  4614.4  463.47  4633.7  461.06  4638.8  462.04
  4732.4  456.88  4798.5  455.09  4808.7  453.75    4819   449.3  4825.9  444.48
  4830.9  450.59  4859.3  444.17  4899.3  451.28  4969.4  449.68  4996.4  442.07
  4999.1  441.57  5002.4  442.07  5009.4  442.29  5029.4  447.02  5039.4     448
  5199.5  452.61  5289.5  453.63  5341.1  455.87  5429.6  459.98    5635  463.32
#Mann= 6 ,-1 , 0
  4388.6     .16       0  4476.8     .05       0  4553.7     .16       0
  4996.4     .07       0  5002.4     .16       0  5341.1     .05       0
Bank Sta=4969.4,5039.4
XS Rating Curve= 0 ,0
Exp/Cntr=0.3,0.1

Type RM Length L Ch R = 1 ,2835    ,17,17,17
BEGIN DESCRIPTION:
UNT0130 IN SAND CR 3.1
END DESCRIPTION:
XS GIS Cut Line= 3
      3550237.69     10578009.14      3550673.43     10578285.17
        3551137.     10578582.06
#Sta/Elev= 30
  4532.4  453.34    4545  454.46  4550.9  453.03    4580  452.23  4630.2   451.1
  4717.8  448.19  4733.1  448.83  4827.2  444.65  4858.7  444.39  4936.5  444.42
  4957.7  443.35  4970.9  444.34    4973  444.51  4978.9  442.16  4997.1  438.72
  4999.8  438.22  5003.1  438.72  5015.3  443.11  5030.6  442.63  5036.5  444.37
  5051.8   444.4  5058.5  443.86    5067  441.16  5072.9  443.77  5082.2  443.21
  5088.1   444.3    5176  445.96  5381.4  455.57  5493.9  460.22  5598.7  458.09
#Mann= 8 ,-1 , 0
  4532.4     .05       0    4580     .08       0  4630.2     .05       0
  4858.7     .16       0  4970.9     .05       0  4997.1     .04       0
  5003.1     .05       0  5381.4     .08       0
Bank Sta=4973,5015.3
XS Rating Curve= 0 ,0
Exp/Cntr=0.3,0.1

Type RM Length L Ch R = 1 ,2818    ,77,77,77
BEGIN DESCRIPTION:
UNT0130 IN SAND CR 3.0
END DESCRIPTION:
XS GIS Cut Line= 3
      3550225.49     10578019.53      3550661.28     10578295.59
       3551124.8     10578592.45
#Sta/Elev= 30
  4536.8  451.13  4544.4  452.07  4550.3  451.19  4562.8   451.7  4648.2  450.29
  4774.9  447.84  4826.6  445.41  4832.5  446.37  4847.8  444.48  4853.7  445.66
    4863  444.86    4869  446.08  4876.7  445.22  4899.5  444.48  4905.4  445.63
  4953.7  444.07    4963  444.46  4978.3  442.85  4984.2  439.32  4996.5  438.72
  4999.2  438.22  5002.5  438.72  5020.7  443.45  5057.1  444.94  5123.9   444.3
  5181.4  445.95  5346.1  453.32  5420.7  457.44  5499.3  460.02  5603.1  458.11
#Mann= 8 ,-1 , 0
  4536.8     .05       0  4562.8     .08       0  4648.2     .05       0
  4876.7     .16       0  4953.7     .05       0  4996.5     .04       0
  5002.5     .05       0  5346.1     .08       0
Bank Sta=4978.3,5020.7
XS Rating Curve= 0 ,0
Exp/Cntr=0.3,0.1

Type RM Length L Ch R = 1 ,2741    ,10,10,10
BEGIN DESCRIPTION:
UNT0130 IN SAND CR 2.1
END DESCRIPTION:
XS GIS Cut Line= 4
      3550013.88     10578000.01       3550232.2     10578111.13
      3550624.13     10578361.13       3551057.4     10578651.28
#Sta/Elev= 30
  4358.5  455.84  4416.4  453.26  4491.2   449.1  4589.5  448.78  4642.7   447.2
    4763  443.69  4981.3  444.67  4999.5  436.86  5002.2  436.36  5005.5  436.86
  5017.7  442.12  5030.4  444.84  5075.1  445.27  5081.1  443.47  5096.1  445.56
  5102.1  444.09  5267.1  449.05  5342.3  451.49  5348.3  453.04  5378.3  452.48
  5384.3   454.8  5399.3  452.79  5414.3   453.2  5420.3  455.05  5435.3  453.21
  5492.4  455.65  5522.4  454.59  5528.4  456.86  5543.4  454.69  5589.8  453.79
#Mann= 7 ,-1 , 0
  4358.5     .08       0  4416.4     .05       0  4589.5     .08       0
  4642.7     .05       0  4999.5     .04       0  5005.5     .05       0
  5267.1     .08       0
Bank Sta=4981.3,5030.4
XS Rating Curve= 0 ,0
Exp/Cntr=0.3,0.1

Type RM Length L Ch R = 1 ,2731    ,686,686,686
BEGIN DESCRIPTION:
UNT0130 IN SAND CR 2.2
END DESCRIPTION:
XS GIS Cut Line= 4
      3550012.61     10578010.45       3550230.9     10578121.54
      3550622.83     10578371.54      3551056.39     10578661.89
#Sta/Elev= 30
  4359.7   456.3  4392.5  454.71  4485.9  448.83  4591.6  448.12  4623.1  447.14
  4785.7  443.28  4973.8  444.36  4988.8  441.13  4994.5  436.92  4997.2  436.42
  5000.5  436.92  5019.2  443.55  5082.7  442.88  5253.9  449.04  5328.8  451.76
  5343.8  453.04  5349.9  456.07  5364.9  453.54  5370.9  456.66  5379.9   454.8
  5385.9  458.45  5400.9  454.27  5406.9  456.95  5436.9  454.16  5457.9  456.38
    5509  454.82    5530   458.6    5545  454.94    5551   456.9  5591.3  454.32
#Mann= 7 ,-1 , 0
  4359.7     .08       0  4392.5     .05       0  4591.6     .08       0
  4623.1     .05       0  4994.5     .04       0  5000.5     .05       0
  5253.9     .08       0
Bank Sta=4973.8,5019.2
XS Rating Curve= 0 ,0
Exp/Cntr=0.3,0.1

Type RM Length L Ch R = 1 ,2045    ,975,975,975
BEGIN DESCRIPTION:
UNT0130 IN SAND CR 2.0
END DESCRIPTION:
XS GIS Cut Line= 2
      3549950.33     10577971.76      3550202.72     10578937.53
#Sta/Elev= 30
  4340.2  455.53  4360.7  456.97  4392.4  455.84  4406.9  455.03  4442.2  451.16
  4447.3  451.17  4453.8  449.71  4464.1   448.6  4515.8  446.64  4546.8  444.51
  4588.1  443.99    4604  442.62  4660.5  441.83  4760.6  441.69  4815.5  442.57
  4908.5  442.51  4931.7  441.83  4957.6  441.03  4970.6  441.55  4980.9  440.59
  4991.2  437.94  4995.1   434.7  4997.8   434.2  5001.1   434.7  5003.3  434.85
  5022.2  441.89  5038.5  443.97  5063.6  445.77  5195.2   451.1  5338.4  454.98
#Mann= 5 ,-1 , 0
  4340.2     .08       0  4392.4     .05       0  4931.7     .16       0
  4995.1     .04       0  5001.1     .05       0
Bank Sta=4980.9,5022.2
XS Rating Curve= 0 ,0
Exp/Cntr=0.3,0.1

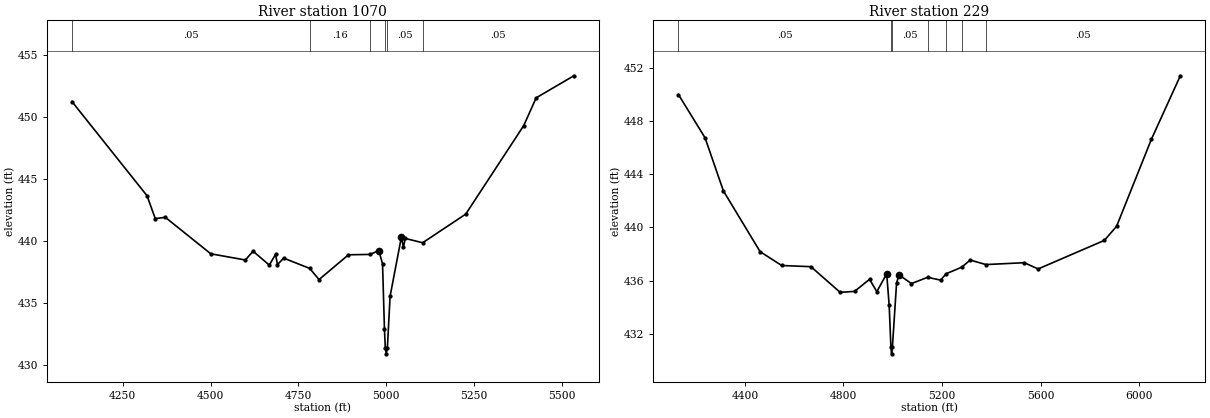
Type RM Length L Ch R = 1 ,1070    ,841,841,841
BEGIN DESCRIPTION:
UNT0130 IN SAND CR 1.0
END DESCRIPTION:
XS GIS Cut Line= 4
      3549713.28      10577970.3      3549438.84     10578590.22
      3549608.11     10579015.56      3549842.12     10579191.65
#Sta/Elev= 30
  4105.6  451.25  4319.4  443.65  4342.7  441.81  4371.4  441.91  4500.8  438.97
  4599.2  438.47  4621.1  439.18  4667.3  438.06  4685.1  438.92  4690.6   438.1
  4708.4  438.62  4782.4  437.79  4808.9  436.89  4892.7  438.89  4954.2  438.92
  4978.8  439.23  4989.6  438.18  4995.1   432.9  4997.5   431.4  5000.2   430.9
  5003.5   431.4  5011.1  435.54  5043.4  440.33    5049  439.51  5054.4  440.21
  5103.8  439.86  5226.4  442.17  5391.5  449.31  5426.9  451.55  5534.2  453.33
#Mann= 6 ,-1 , 0
  4105.6     .05       0  4782.4     .16       0  4954.2     .05       0
  4997.5     .07       0  5003.5     .05       0  5103.8     .05       0
Bank Sta=4978.8,5043.4
XS Rating Curve= 0 ,0
Exp/Cntr=0.3,0.1

Type RM Length L Ch R = 1 ,229     ,0,0,0
BEGIN DESCRIPTION:
UNT0130 IN SAND CR 1.1
END DESCRIPTION:
XS GIS Cut Line= 4
      3549644.08     10577918.18      3548993.02     10578147.35
      3548966.98     10578501.52       3549671.3     10579198.04
#Sta/Elev= 30
  4130.5     450  4238.6  446.74  4312.8  442.75  4461.9  438.17  4549.4  437.13
    4668  437.04  4786.5  435.11  4845.1  435.18  4905.8  436.09  4935.3  435.16
  4975.4  436.51  4985.4  434.13  4992.5  430.98  4995.2  430.48  4998.5  430.98
  5015.5  435.83  5025.6  436.42  5075.7  435.77  5141.4  436.24  5193.7  436.03
  5216.9  436.51  5279.5     437  5313.9  437.54  5377.7   437.2  5533.1  437.34
  5589.7  436.87  5858.3  439.02  5907.9  440.08  6049.3  446.64  6166.4  451.41
#Mann= 7 ,-1 , 0
  4130.5     .05       0  4992.5     .04       0  4998.5     .05       0
  5141.4     .08       0  5216.9     .05       0  5279.5     .08       0
  5377.7     .05       0
Bank Sta=4975.4,5025.6
XS Rating Curve= 0 ,0
Exp/Cntr=0.3,0.1

Chan Stop Cuts=-1
Use User Specified Reach Order=0
Composite Channel Slope=5