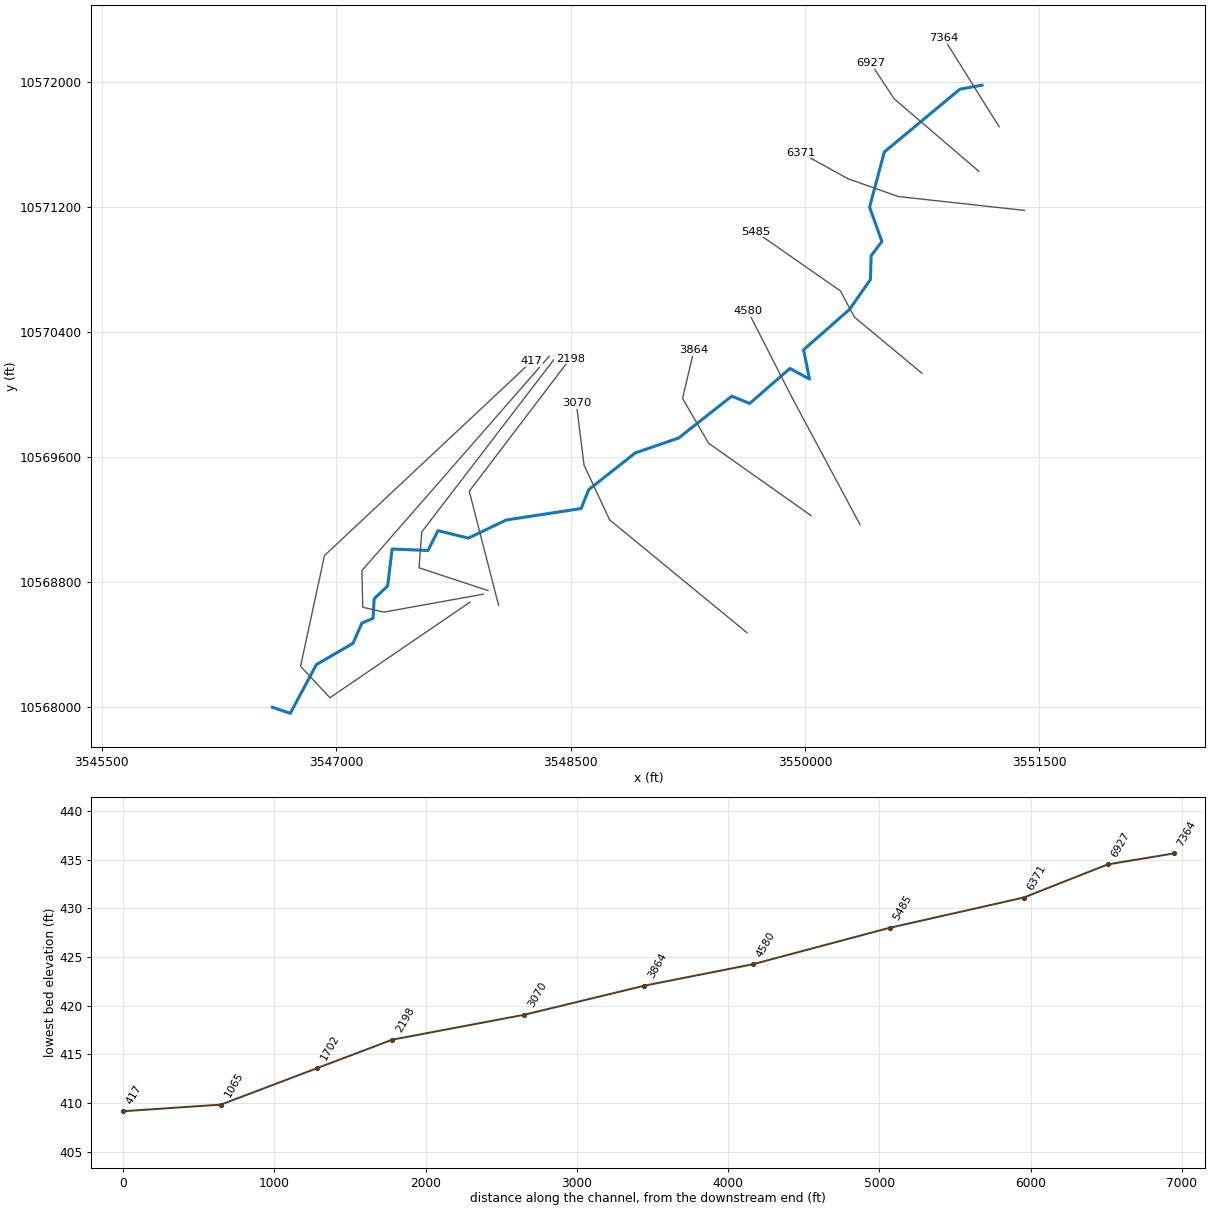
--- UNT0131 IN SAND CR.prj (project) ---

Proj Title=UNT0131 IN SAND CR Base Level Engineering
Current Plan=p01
Default Exp/Contr=0.3,0.1
English Units
Geom File=g01
Flow File=f01
Plan File=p01
Y Axis Title=Elevation
X Axis Title(PF)=Main Channel Distance
X Axis Title(XS)=Station
BEGIN DESCRIPTION:
UNT0131 IN SAND CR
END DESCRIPTION:
DSS Export Rating Curves= 0
DSS Export Rating Curve Sorted= 0
DSS Export Volume Flow Curves= 0
DXF OffsetX= 0
DXF OffsetY= 0
DXF ScaleX= 1
DXF ScaleY= 10

--- UNT0131 IN SAND CR.p01 (plan) ---

Plan Title=Multiple Run
Short Identifier=Multiple
Geom File=g01
Flow File=f01
Subcritical Flow
K Sum by GR= 0
Std Step Tol= 0.01
Critical Tol= 0.01
Num of Std Step Trials= 20
Max Error Tol= 0.3
Flow Tol Ratio= 0.001
Split Flow NTrial= 30
Split Flow Tol= 0.02
Split Flow Ratio= 0.02
Log Output Level= 0
Friction Slope Method= 1
Unsteady Friction Slope Method= 2
Unsteady Bridges Friction Slope Method= 1
Parabolic Critical Depth
Global Vel Dist=  1 , 1 , 1
Global Log Level= 0
CheckData=True
Encroach Param= -1, 0, 0, 0
BEGIN DESCRIPTION:
Multiple Run
END DESCRIPTION:

--- UNT0131 IN SAND CR.f01 (steady flow) ---

Flow Title=Multiple
Number of Profiles=7
Profile Names=10-year,25-year,50-year,1pct_min,100-year,1pct_plu,500-year
River Rch & RM= UNT0131 IN SAND ,Reach-1,7364
    1028    1408    1720    1533    2073    2803    3002
Boundary for River Rch & Prof#=UNT0131 IN SAND ,Reach-1,1
Up Type=0
Dn Type=3
Dn Slope=0.005
Boundary for River Rch & Prof#=UNT0131 IN SAND ,Reach-1,2
Up Type=0
Dn Type=3
Dn Slope=0.005
Boundary for River Rch & Prof#=UNT0131 IN SAND ,Reach-1,3
Up Type=0
Dn Type=3
Dn Slope=0.005
Boundary for River Rch & Prof#=UNT0131 IN SAND ,Reach-1,4
Up Type=0
Dn Type=3
Dn Slope=0.005
Boundary for River Rch & Prof#=UNT0131 IN SAND ,Reach-1,5
Up Type=0
Dn Type=3
Dn Slope=0.005
Boundary for River Rch & Prof#=UNT0131 IN SAND ,Reach-1,6
Up Type=0
Dn Type=3
Dn Slope=0.005
Boundary for River Rch & Prof#=UNT0131 IN SAND ,Reach-1,7
Up Type=0
Dn Type=3
Dn Slope=0.005

--- UNT0131 IN SAND CR.g01 (geometry) ---

Geom Title=Existing Conditions
Program Version=4.10

River Reach=UNT0131 IN SAND ,Reach-1
Reach XY= 30
      3551132.11     10571981.64      3550990.67     10571955.77
      3550507.41     10571554.26      3550412.97     10571201.08
      3550491.74     10570981.49      3550423.05     10570890.53
      3550418.36     10570738.45      3550285.03      10570547.3
      3549990.76     10570288.45      3550028.78     10570100.95
      3549903.26     10570169.17      3549645.96     10569945.22
      3549531.38     10569992.09      3549191.13     10569723.99
      3548914.09     10569628.77      3548615.93     10569393.81
      3548567.76     10569272.97      3548088.02     10569199.52
      3547846.36     10569083.58      3547651.89     10569131.46
      3547587.75     10569004.67      3547358.07     10569013.74
      3547329.69     10568777.38      3547243.44     10568695.68
      3547236.13     10568570.58      3547164.84     10568539.85
      3547107.95     10568410.48      3546873.35     10568274.23
      3546706.66     10567962.34      3546592.11     10568001.64

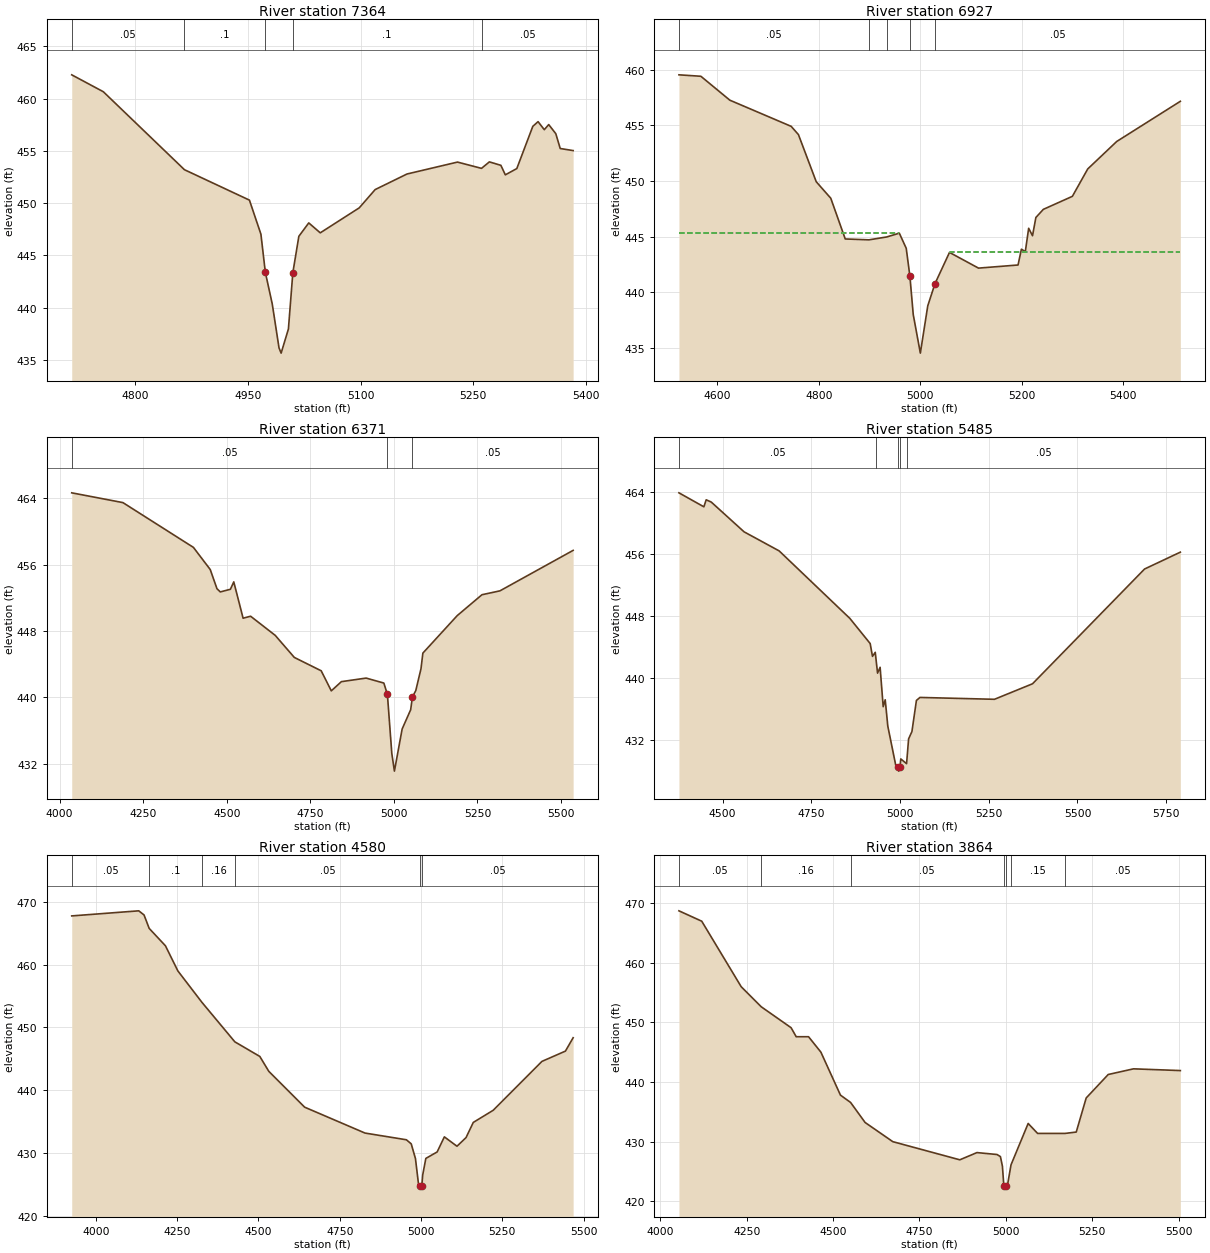
Type RM Length L Ch R = 1 ,7364    ,437,437,437
BEGIN DESCRIPTION:
UNT0131 IN SAND CR 11.1
END DESCRIPTION:
XS GIS Cut Line= 2
      3551242.13     10571715.31      3550887.99     10572281.24
#Sta/Elev= 30
  4715.4  462.28  4757.5  460.66  4865.5   453.2    4952  450.29  4967.3  447.03
  4973.2  443.37  4982.4  440.35  4991.4  436.15  4994.2  435.65  5003.9  437.96
  5009.8  443.35  5017.8  446.83    5031  448.11  5046.3  447.16  5098.2  449.55
  5119.4   451.3  5161.8  452.79    5229  453.93    5261  453.33  5271.5  453.95
  5286.8  453.62  5292.7  452.71    5308  453.31  5329.3  457.35  5336.3   457.8
  5344.6  457.03  5350.5  457.52  5359.9  456.65  5365.8  455.23    5383  455.03
#Mann= 5 ,-1 , 0
  4715.4     .05       0  4865.5      .1       0  4973.2     .05       0
  5009.8      .1       0    5261     .05       0
#XS Ineff= 2 , 0
                         5031.35          448.07
Permanent Ineff=
       F       F
Bank Sta=4973.2,5009.8
XS Rating Curve= 0 ,0
Exp/Cntr=0.3,0.1

Type RM Length L Ch R = 1 ,6927    ,556,556,556
BEGIN DESCRIPTION:
UNT0131 IN SAND CR 11.0
END DESCRIPTION:
XS GIS Cut Line= 3
      3551112.18     10571430.47      3550570.52       10571894.
      3550419.47     10572123.18
#Sta/Elev= 30
  4524.8  459.53    4568   459.4  4625.1  457.25  4745.8   454.9  4760.1  454.16
  4795.2  449.92  4823.8  448.44  4852.3  444.78    4899   444.7    4934  444.96
  4958.8   445.3  4972.4  443.94  4979.6  441.44  4986.2  437.99  5000.2  434.52
  5014.8  438.77    5029  440.76  5057.6  443.57  5114.7  442.16  5192.6  442.44
  5199.2  443.86  5206.9  443.64  5213.5  445.74  5221.1  445.07  5227.7  446.71
  5242.4  447.44  5299.6  448.61  5329.8  451.07  5386.9  453.54  5512.2  457.15
#Mann= 5 ,-1 , 0
  4524.8     .05       0    4899     .16       0    4934     .05       0
  4979.6     .03       0    5029     .05       0
#XS Ineff= 2 , 0
         4957.75  445.31 5058.42          443.64
Permanent Ineff=
       F       F
Bank Sta=4979.6,5029
XS Rating Curve= 0 ,0
Exp/Cntr=0.3,0.1

Type RM Length L Ch R = 1 ,6371    ,886,886,886
BEGIN DESCRIPTION:
UNT0131 IN SAND CR 10.0
END DESCRIPTION:
XS GIS Cut Line= 4
      3551403.89     10571180.46      3550596.56       10571269.
      3550273.64     10571383.59      3549971.58     10571550.24
#Sta/Elev= 30
  4036.3  464.67  4189.4  463.49  4400.3  458.09  4450.6  455.42  4470.7  453.11
  4480.7  452.72  4510.9  453.04    4521  453.93  4548.9  449.55  4571.3  449.79
    4645  447.48  4702.1  444.82  4782.5  443.21  4812.7  440.79  4842.9   441.9
  4916.9  442.33  4969.9  441.73  4980.5  440.37  4993.7  433.25  5001.5  431.11
  5024.6  436.19  5050.1  438.51  5055.4  440.06  5065.4  440.82    5081  443.46
  5086.6  445.34  5189.3  449.86  5263.3  452.38  5317.2  452.85  5536.1  457.73
#Mann= 3 , 0 , 0
  4036.3     .05       0  4980.5     .03       0  5055.4     .05       0
#XS Ineff= 2 , 0
         4921.98  442.27
Permanent Ineff=
       F       F
Bank Sta=4980.5,5055.4
XS Rating Curve= 0 ,0
Exp/Cntr=0.3,0.1

Type RM Length L Ch R = 1 ,5485    ,905,905,905
BEGIN DESCRIPTION:
UNT0131 IN SAND CR 8.0
END DESCRIPTION:
XS GIS Cut Line= 4
       3550747.6      10570138.8      3550315.31     10570498.17
      3550226.77     10570664.84      3549683.41     10571043.54
#Sta/Elev= 30
  4376.8  463.84  4447.1  462.04  4453.6  462.94  4467.9  462.65  4560.3  458.82
  4659.3  456.36  4858.5  447.67  4915.8  444.43  4922.3  442.78  4930.1   443.3
    4933   442.1  4936.6  440.62  4943.8  441.37  4952.5   436.3  4958.2  437.19
  4965.5  433.79  4988.2  428.68  4993.5   428.5  4996.2     428  4999.5   428.5
  5002.1  429.57  5018.4  428.96  5024.1  432.15  5033.5   433.1  5046.1   437.1
  5056.1  437.49  5266.1  437.25  5373.4  439.25  5689.2  454.03    5790   456.2
#Mann= 5 ,-1 , 0
  4376.8     .05       0    4933     .16       0  4993.5     .07       0
  4999.5     .16       0  5018.4     .05       0
Bank Sta=4993.5,4999.5
XS Rating Curve= 0 ,0
Exp/Cntr=0.3,0.1

Type RM Length L Ch R = 1 ,4580    ,716,716,716
BEGIN DESCRIPTION:
UNT0131 IN SAND CR 6.0
END DESCRIPTION:
XS GIS Cut Line= 3
      3550351.75     10569170.07      3549914.27     10569987.75
      3549634.97     10570535.16
#Sta/Elev= 30
  3925.9  467.76    4132  468.57  4148.3  467.91  4164.1  465.77  4214.1     463
  4252.3     459  4326.4  453.99  4427.4  447.71  4504.3  445.38  4531.9  443.01
  4642.2   437.3  4827.7  433.18    4955  432.11  4969.9  431.46  4982.9  429.12
  4992.3  425.05  4996.5  424.75  4999.2  424.25  5002.5  424.75  5005.1  426.48
  5014.8  429.14  5049.6  430.17  5071.8  432.57  5110.6  431.08  5138.5  432.46
  5160.7  434.87  5221.8   436.8  5371.8  444.59  5444.1  446.23  5467.8  448.36
#Mann= 6 ,-1 , 0
  3925.9     .05       0  4164.1      .1       0  4326.4     .16       0
  4427.4     .05       0  4996.5     .03       0  5002.5     .05       0
Bank Sta=4996.5,5002.5
XS Rating Curve= 0 ,0
Exp/Cntr=0.3,0.1

Type RM Length L Ch R = 1 ,3864    ,794,794,794
BEGIN DESCRIPTION:
UNT0131 IN SAND CR 5.0
END DESCRIPTION:
XS GIS Cut Line= 4
      3550039.25     10569227.35      3549383.02     10569690.88
      3549216.35     10569977.34      3549289.28     10570284.66
#Sta/Elev= 30
  4054.1  468.67  4120.1  466.93  4234.2  455.96  4291.9  452.61  4378.6  449.09
  4393.4  447.58  4429.1  447.58  4464.8     445  4521.4   437.8  4550.7  436.57
  4592.8  433.21  4672.9     430  4866.7  426.96  4916.3  428.17  4974.3  427.85
  4984.2   427.5    4990   425.9  4994.2  422.55    4997  422.05  5000.2  422.55
  5005.8   423.1  5014.9  426.12  5064.5  433.05  5091.8  431.38  5171.1  431.38
  5203.6  431.61  5232.4  437.32  5296.1  441.25  5369.3   442.2  5504.8  441.91
#Mann= 7 ,-1 , 0
  4054.1     .05       0  4291.9     .16       0  4550.7     .05       0
  4994.2     .03       0  5000.2     .05       0  5014.9     .15       0
  5171.1     .05       0
Bank Sta=4994.2,5000.2
XS Rating Curve= 0 ,0
Exp/Cntr=0.3,0.1

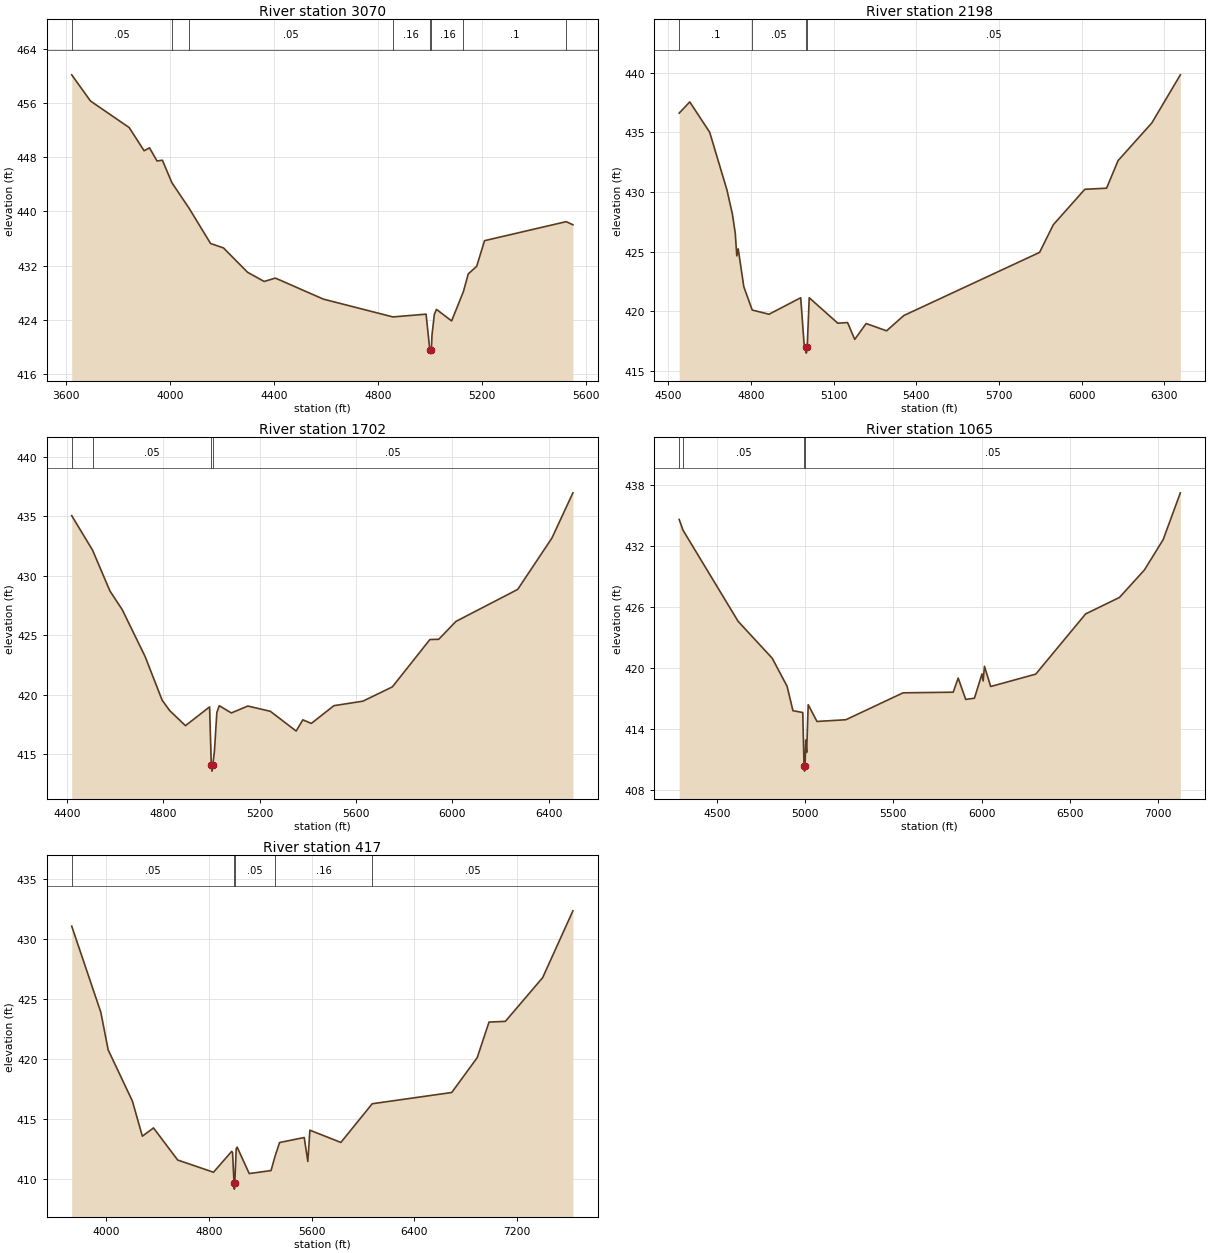
Type RM Length L Ch R = 1 ,3070    ,872,872,872
BEGIN DESCRIPTION:
UNT0131 IN SAND CR 3.0
END DESCRIPTION:
XS GIS Cut Line= 4
      3549629.21     10568477.87      3548749.89     10569200.47
      3548586.19     10569550.52      3548536.44     10569948.55
#Sta/Elev= 30
  3623.5  460.19  3695.6  456.32  3844.2   452.4  3901.6  448.97  3922.4   449.4
  3951.1  447.46  3971.9  447.57  4008.6  444.23  4074.3  440.48    4157  435.26
  4206.5  434.61  4299.1  431.01  4362.9  429.65    4406  430.15  4590.5  427.04
  4857.6  424.41    4985  424.82  4999.3  419.56    5002  419.06  5005.3  419.56
  5007.8  421.75  5016.8  424.81  5025.1  425.52  5083.1  423.82  5128.4  428.15
    5147  430.76  5179.4  431.89  5209.7  435.68  5523.3  438.49  5549.2  438.03
#Mann= 8 ,-1 , 0
  3623.5     .05       0  4008.6      .1       0  4074.3     .05       0
  4857.6     .16       0  4999.3     .07       0  5005.3     .16       0
  5128.4      .1       0  5523.3     .05       0
Bank Sta=4999.3,5005.3
XS Rating Curve= 0 ,0
Exp/Cntr=0.3,0.1

Type RM Length L Ch R = 1 ,2198    ,496,496,496
BEGIN DESCRIPTION:
UNT0131 IN SAND CR 1.0
END DESCRIPTION:
XS GIS Cut Line= 3
      3548039.28     10568654.37      3547851.77     10569383.59
      3548497.34     10570232.21
#Sta/Elev= 30
  4539.3  436.61  4577.8  437.55  4650.1  435.01  4712.9  430.16  4732.7  428.13
    4743  426.53  4748.5  424.65  4753.6  425.24    4774  422.06  4804.5  420.11
  4865.5  419.76  4980.5  421.14  4992.8  417.25  4998.1     417  5000.9   416.5
  5004.1     417  5011.4  421.14    5115  419.01  5150.6  419.06  5176.6  417.65
  5217.9  418.98  5292.2  418.37  5354.7  419.65  5847.5  424.94  5897.4  427.26
  6011.8  430.23  6090.7  430.32  6132.4  432.63    6255  435.79  6358.5  439.82
#Mann= 4 ,-1 , 0
  4539.3      .1       0  4804.5     .05       0  4998.1     .03       0
  5004.1     .05       0
Bank Sta=4998.1,5004.1
XS Rating Curve= 0 ,0
Exp/Cntr=0.3,0.1

Type RM Length L Ch R = 1 ,1702    ,637,637,637
BEGIN DESCRIPTION:
UNT0131 IN SAND CR 1.01
END DESCRIPTION:
XS GIS Cut Line= 4
      3547971.53     10568748.06      3547530.53      10568893.9
       3547547.9     10569123.06      3548391.65     10570223.77
#Sta/Elev= 30
  4419.7  435.05  4506.3  432.15  4578.4  428.72  4629.7  427.14  4724.5  423.21
  4795.2  419.54  4826.9  418.66    4892   417.4  4992.2  418.98  4999.3  414.08
    5002  413.58  5005.3  414.08  5012.3  415.25  5022.3   418.5  5032.4  419.08
  5082.5  418.47  5150.9  419.05  5244.4  418.61  5351.6  416.95  5379.4  417.89
  5414.7  417.59  5508.2  419.08  5628.8  419.46  5751.1  420.66    5907  424.64
  5943.8  424.66  6014.9  426.16  6271.4  428.85  6413.8  433.17  6500.9  436.97
#Mann= 4 ,-1 , 0
  4419.7      .1       0  4506.3     .05       0  4999.3     .03       0
  5005.3     .05       0
Bank Sta=4999.3,5005.3
XS Rating Curve= 0 ,0
Exp/Cntr=0.3,0.1

Type RM Length L Ch R = 1 ,1065    ,648,648,648
BEGIN DESCRIPTION:
UNT0131 IN SAND CR 1.02
END DESCRIPTION:
XS GIS Cut Line= 5
      3547940.94      10568724.8      3547305.53     10568610.22
      3547170.12     10568641.47      3547164.91     10568875.84
      3548363.22     10570247.32
#Sta/Elev= 30
  4286.4   434.6  4308.9  433.52  4620.5  424.57  4813.6  420.94  4897.9  418.18
  4931.3  415.77  4986.9  415.59  4994.1  410.32  4996.9  409.82  5000.1  410.32
  5003.7  412.88  5008.8  411.66  5017.7  416.36  5067.4  414.71  5231.2  414.88
  5555.4  417.53  5839.2  417.59  5867.7  418.98  5910.4  416.88  5959.8     417
  6002.5  419.39  6009.1   418.7  6016.7  420.14  6051.8  418.15  6307.2  419.37
    6590   425.3  6781.8  426.92  6923.2  429.63  7029.5  432.62  7126.7  437.22
#Mann= 4 ,-1 , 0
  4286.4      .1       0  4308.9     .05       0  4994.1     .03       0
  5000.1     .05       0
Bank Sta=4994.1,5000.1
XS Rating Curve= 0 ,0
Exp/Cntr=0.3,0.1

Type RM Length L Ch R = 1 ,417     ,0,0,0
BEGIN DESCRIPTION:
UNT0131 IN SAND CR 1.1
END DESCRIPTION:
XS GIS Cut Line= 5
      3547855.92     10568673.46      3546960.12     10568062.37
      3546772.62     10568263.76       3546925.4     10568972.09
      3548251.79     10570215.15
#Sta/Elev= 30
  3732.5   431.1  3959.3   423.9  4016.2  420.77  4204.6   416.5  4282.4  413.56
  4369.2  414.25  4557.5  411.57  4836.2  410.55  4977.9  412.29  4984.7   412.2
  4995.9  409.64  4998.6  409.14  5001.9  409.64    5013   412.5  5020.4  412.65
  5114.4  410.44  5284.2  410.69  5315.1  411.87  5350.6  413.03  5542.6  413.45
  5570.7  411.45  5586.8  414.06    5828  413.04    6072  416.27  6691.1  417.21
  6889.4  420.12  6981.3  423.09  7108.7  423.15  7398.9   426.8  7634.5  432.38
#Mann= 5 ,-1 , 0
  3732.5     .05       0  4995.9     .03       0  5001.9     .05       0
  5315.1     .16       0    6072     .05       0
Bank Sta=4995.9,5001.9
XS Rating Curve= 0 ,0
Exp/Cntr=0.3,0.1

Chan Stop Cuts=-1
Use User Specified Reach Order=0
Composite Channel Slope=5