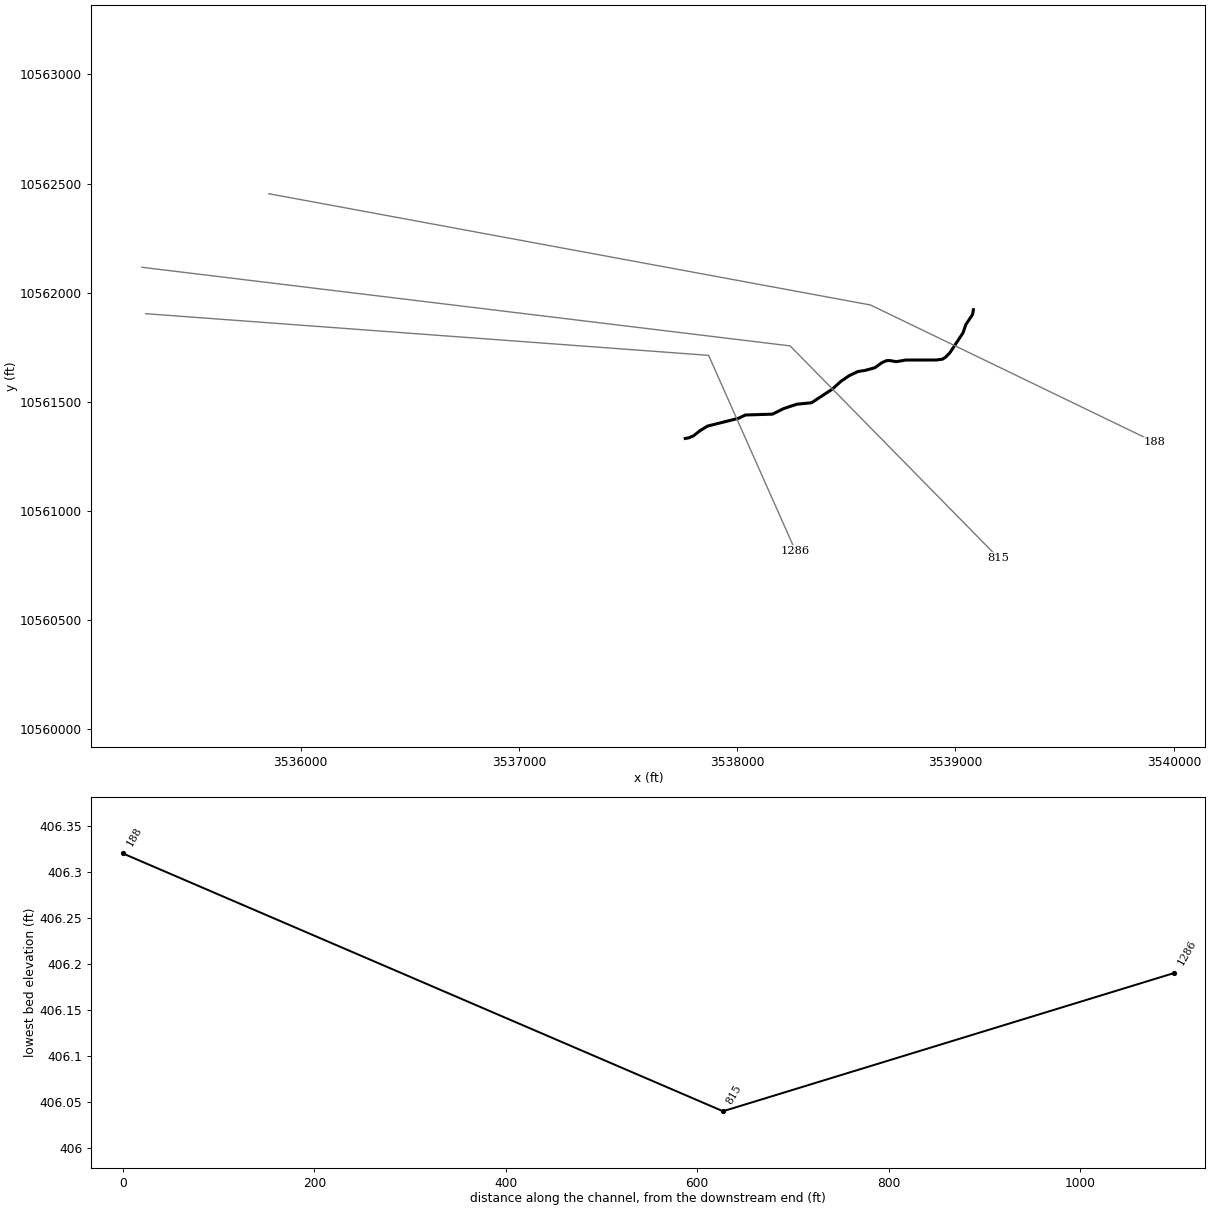
--- UNT0135 IN SAND CR.prj (project) ---

Proj Title=UNT0135 IN SAND CR Base Level Engineering
Current Plan=p01
Default Exp/Contr=0.3,0.1
English Units
Geom File=g01
Flow File=f01
Plan File=p01
BEGIN DESCRIPTION:
UNT0135 IN SAND CR
END DESCRIPTION:

--- UNT0135 IN SAND CR.p01 (plan) ---

Plan Title=Multiple Run
Short Identifier=Multiple
Geom File=g01
Flow File=f01
Subcritical Flow
K Sum by GR= 0
Std Step Tol= 0.01
Critical Tol= 0.01
Num of Std Step Trials= 20
Max Error Tol= 0.3
Flow Tol Ratio= 0.001
Split Flow NTrial= 30
Split Flow Tol= 0.02
Split Flow Ratio= 0.02
Log Output Level= 0
Friction Slope Method= 1
Unsteady Friction Slope Method= 2
Unsteady Bridges Friction Slope Method= 1
Parabolic Critical Depth
Global Vel Dist=  1 , 1 , 1
Global Log Level= 0
CheckData=True
Encroach Param= -1, 0, 0, 0
BEGIN DESCRIPTION:
Multiple Run
END DESCRIPTION:

--- UNT0135 IN SAND CR.f01 (steady flow) ---

Flow Title=Multiple
Number of Profiles=7
Profile Names=10-year,25-year,50-year,1pct_min,100-year,1pct_plu,500-year
River Rch & RM= UNT0135 IN SAND ,Reach-1,1286
    1353    1881    2321    2086    2821    3816    4159
Boundary for River Rch & Prof#=UNT0135 IN SAND ,Reach-1,1
Up Type=0
Dn Type=3
Dn Slope=0.005
Boundary for River Rch & Prof#=UNT0135 IN SAND ,Reach-1,2
Up Type=0
Dn Type=3
Dn Slope=0.005
Boundary for River Rch & Prof#=UNT0135 IN SAND ,Reach-1,3
Up Type=0
Dn Type=3
Dn Slope=0.005
Boundary for River Rch & Prof#=UNT0135 IN SAND ,Reach-1,4
Up Type=0
Dn Type=3
Dn Slope=0.005
Boundary for River Rch & Prof#=UNT0135 IN SAND ,Reach-1,5
Up Type=0
Dn Type=3
Dn Slope=0.005
Boundary for River Rch & Prof#=UNT0135 IN SAND ,Reach-1,6
Up Type=0
Dn Type=3
Dn Slope=0.005
Boundary for River Rch & Prof#=UNT0135 IN SAND ,Reach-1,7
Up Type=0
Dn Type=3
Dn Slope=0.005

--- UNT0135 IN SAND CR.g01 (geometry) ---

Geom Title=Existing Conditions

River Reach=UNT0135 IN SAND ,Reach-1
Reach XY= 30
      3537762.11     10561331.64      3537779.20     10561334.79
      3537800.46     10561344.16      3537829.34     10561366.93
      3537863.57     10561388.11      3538006.09     10561424.10
      3538037.94     10561439.20      3538161.87     10561443.04
      3538213.32     10561468.72      3538273.37     10561488.58
      3538340.59     10561495.29      3538434.68     10561556.82
      3538475.87     10561593.93      3538513.04     10561619.39
      3538553.41     10561638.50      3538586.80     10561643.73
      3538630.50     10561655.64      3538663.26     10561679.10
      3538683.23     10561688.05      3538696.50     10561689.03
      3538728.97     10561683.58      3538772.22     10561691.14
      3538912.34     10561691.19      3538940.78     10561695.12
      3538955.55     10561704.96      3538974.64     10561724.92
      3539034.27     10561815.48      3539047.80     10561854.08
      3539078.33     10561899.82      3539082.11     10561921.64

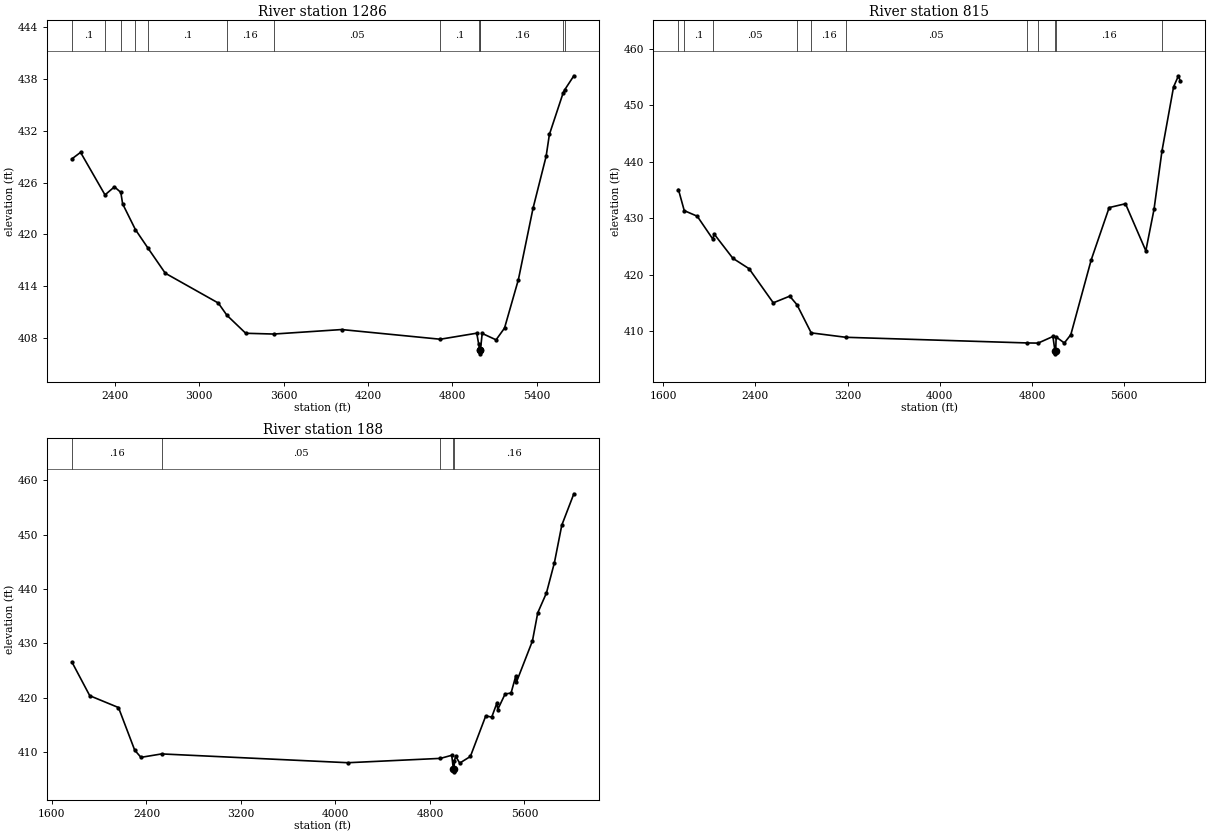
Type RM Length L Ch R = 1,1286,471,471,471
BEGIN DESCRIPTION:
UNT0135 IN SAND CK 1.0
END DESCRIPTION:
XS GIS Cut Line= 3
      3535291.11     10561903.47      3537869.19     10561712.50
      3538267.11     10560816.64
#Sta/Elev= 30
  2097.1  428.75  2158.3  429.50  2331.9  424.58  2398.9  425.51  2444.2  424.87
  2457.2  423.54  2548.0  420.56  2638.1  418.40  2759.9  415.52  3136.5  412.07
  3198.0  410.65  3331.5  408.57  3530.8  408.48  4013.3  409.00  4713.7  407.88
  4972.9  408.58  4986.5  407.31  4993.2  406.69  4995.9  406.19  4999.2  406.69
  5011.4  408.55  5109.9  407.81  5170.0  409.17  5268.5  414.78  5372.5  423.03
  5465.5  429.04  5488.7  431.57  5586.3  436.37  5597.6  436.74  5662.5  438.36
#Mann=13,-1,0
  2097.1     0.1       0  2331.9    0.16       0  2444.2     0.1       0
  2548.0    0.05       0  2638.1     0.1       0  3198.0    0.16       0
  3530.8    0.05       0  4713.7     0.1       0  4986.5    0.16       0
  4993.2    0.07       0  4999.2    0.16       0  5586.3     0.1       0
  5597.6    0.16       0
Bank Sta=4993.2,4999.2
Exp/Cntr=0.3,0.1

Type RM Length L Ch R = 1,815,627,627,627
BEGIN DESCRIPTION:
UNT0135 IN SAND CK 2.0
END DESCRIPTION:
XS GIS Cut Line= 3
      3535273.66     10562116.15      3538242.46     10561755.90
      3539197.19     10560783.81
#Sta/Elev= 30
  1732.6  435.13  1783.2  431.39  1895.9  430.40  2030.4  426.37  2043.3  427.23
  2204.5  422.96  2345.5  421.11  2555.3  415.07  2698.1  416.25  2760.6  414.74
  2884.4  409.75  3184.7  408.97  4753.9  407.97  4852.2  407.94  4980.6  409.11
  4998.7  406.54  5001.5  406.04  5004.7  406.54  5008.8  409.03  5079.6  407.96
  5136.0  409.43  5312.9  422.68  5468.5  431.93  5609.9  432.61  5786.6  424.28
  5857.4  431.59  5926.4  441.93  6027.1  453.29  6069.5  455.26  6085.7  454.26
#Mann=11,-1,0
  1732.6    0.05       0  1783.2     0.1       0  2030.4    0.05       0
  2760.6     0.1       0  2884.4    0.16       0  3184.7    0.05       0
  4753.9     0.1       0  4852.2    0.16       0  4998.7    0.07       0
  5004.7    0.16       0  5926.4     0.1       0
Bank Sta=4998.7,5004.7
Exp/Cntr=0.3,0.1

Type RM Length L Ch R = 1,188,0,0,0
BEGIN DESCRIPTION:
UNT0135 IN SAND CK 3.0
END DESCRIPTION:
XS GIS Cut Line= 3
      3535854.71     10562453.33      3538610.75     10561943.35
      3539912.81     10561314.02
#Sta/Elev= 30
  1769.4  426.53  1920.2  420.34  2163.4  418.16  2300.7  410.31  2353.6  408.99
  2528.9  409.62  4105.8  408.00  4889.4  408.80  4984.7  409.37  4998.3  406.82
  5001.1  406.32  5004.3  406.82  5006.9  408.36  5018.0  409.18  5052.1  407.93
  5142.4  409.15  5272.5  416.62  5323.2  416.40  5368.4  419.07  5374.0  417.80
  5436.2  420.65  5486.9  420.84  5526.6  423.96  5532.1  422.84  5667.7  430.42
  5712.9  435.62  5786.3  439.26  5854.0  444.86  5916.3  451.75  6018.4  457.53
#Mann=5,-1,0
  1769.4    0.16       0  2528.9    0.05       0  4889.4    0.16       0
  4998.3    0.07       0  5004.3    0.16       0
Bank Sta=4998.3,5004.3
Exp/Cntr=0.3,0.1

Chan Stop Cuts=-1