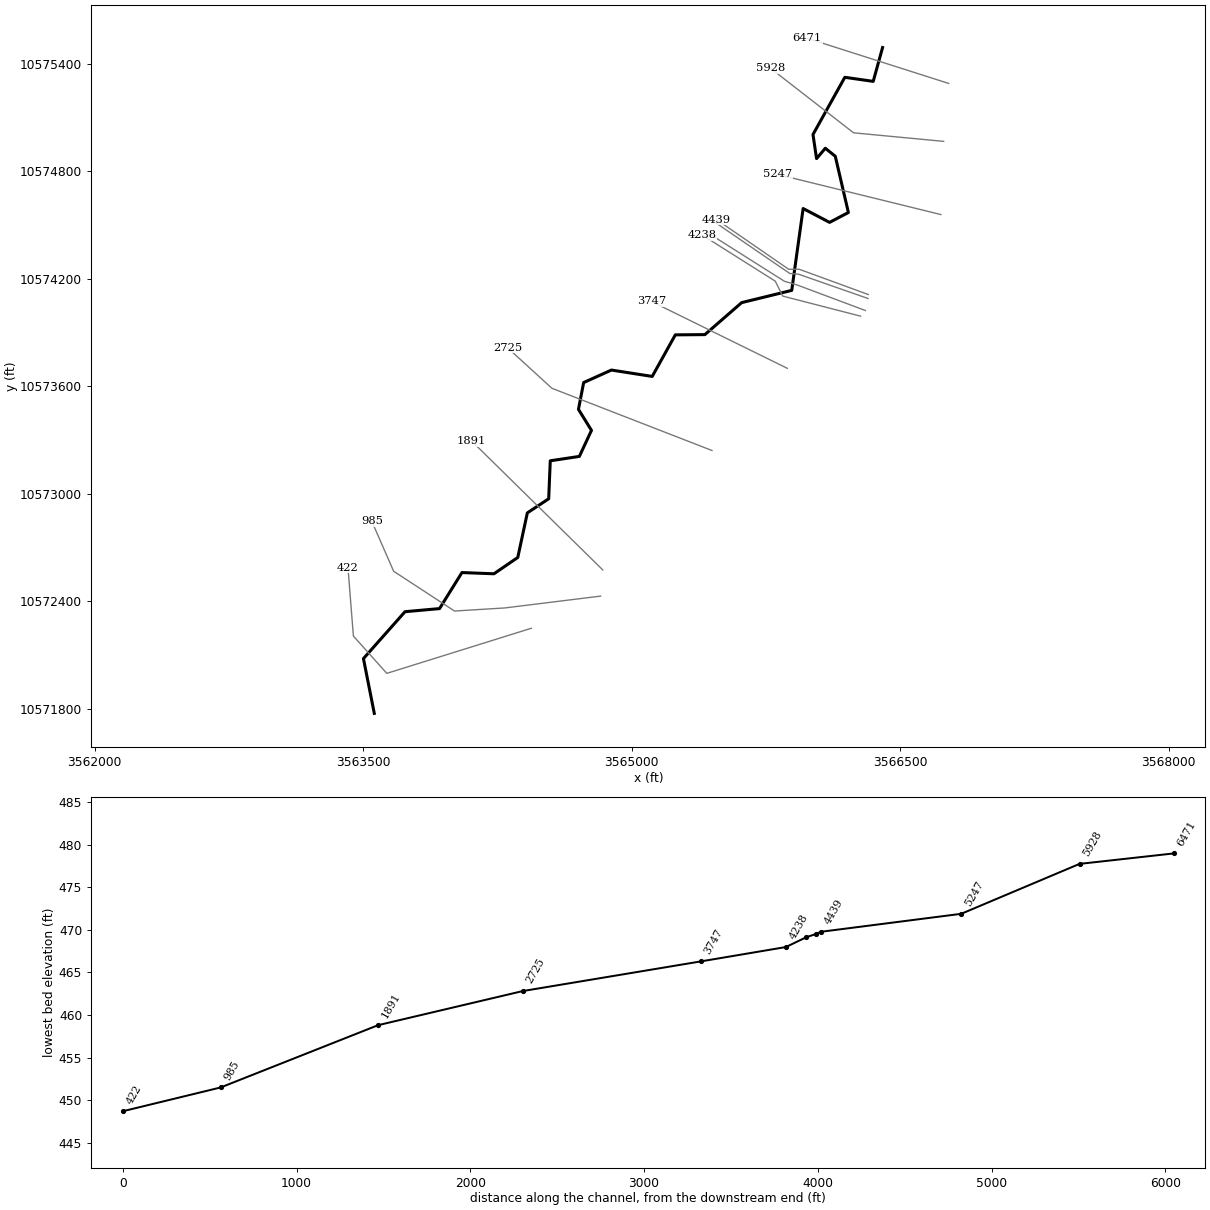
--- UNT0136 IN SAND CR.prj (project) ---

Proj Title=UNT0136 IN SAND CR Base Level Engineering
Current Plan=p01
Default Exp/Contr=0.3,0.1
English Units
Geom File=g01
Flow File=f01
Plan File=p01
Y Axis Title=Elevation
X Axis Title(PF)=Main Channel Distance
X Axis Title(XS)=Station
BEGIN DESCRIPTION:
UNT0136 IN SAND CR
END DESCRIPTION:
DSS Export Rating Curves= 0
DSS Export Rating Curve Sorted= 0
DSS Export Volume Flow Curves= 0
DXF OffsetX= 0
DXF OffsetY= 0
DXF ScaleX= 1
DXF ScaleY= 10

--- UNT0136 IN SAND CR.p01 (plan) ---

Plan Title=Multiple Run
Short Identifier=Multiple
Geom File=g01
Flow File=f01
Subcritical Flow
K Sum by GR= 0
Std Step Tol= 0.01
Critical Tol= 0.01
Num of Std Step Trials= 20
Max Error Tol= 0.3
Flow Tol Ratio= 0.001
Split Flow NTrial= 30
Split Flow Tol= 0.02
Split Flow Ratio= 0.02
Log Output Level= 0
Friction Slope Method= 1
Unsteady Friction Slope Method= 2
Unsteady Bridges Friction Slope Method= 1
Parabolic Critical Depth
Global Vel Dist=  1 , 1 , 1
Global Log Level= 0
CheckData=True
Encroach Param= -1, 0, 0, 0
BEGIN DESCRIPTION:
Multiple Run
END DESCRIPTION:

--- UNT0136 IN SAND CR.f01 (steady flow) ---

Flow Title=Multiple
Number of Profiles=7
Profile Names=10-year,25-year,50-year,1pct_min,100-year,1pct_plu,500-year
River Rch & RM= UNT0136 IN SAND ,Reach-1,6471
     495     647     766     664     898    1214    1227
River Rch & RM= UNT0136 IN SAND ,Reach-1,4238
    1028    1409    1723    1537    2079    2811    3016
River Rch & RM= UNT0136 IN SAND ,Reach-1,985
    1262    1745    2146    1923    2600    3517    3809
Boundary for River Rch & Prof#=UNT0136 IN SAND ,Reach-1,1
Up Type=0
Dn Type=3
Dn Slope=0.005
Boundary for River Rch & Prof#=UNT0136 IN SAND ,Reach-1,2
Up Type=0
Dn Type=3
Dn Slope=0.005
Boundary for River Rch & Prof#=UNT0136 IN SAND ,Reach-1,3
Up Type=0
Dn Type=3
Dn Slope=0.005
Boundary for River Rch & Prof#=UNT0136 IN SAND ,Reach-1,4
Up Type=0
Dn Type=3
Dn Slope=0.005
Boundary for River Rch & Prof#=UNT0136 IN SAND ,Reach-1,5
Up Type=0
Dn Type=3
Dn Slope=0.005
Boundary for River Rch & Prof#=UNT0136 IN SAND ,Reach-1,6
Up Type=0
Dn Type=3
Dn Slope=0.005
Boundary for River Rch & Prof#=UNT0136 IN SAND ,Reach-1,7
Up Type=0
Dn Type=3
Dn Slope=0.005

--- UNT0136 IN SAND CR.g01 (geometry) ---

Geom Title=Existing Conditions
Program Version=4.10

River Reach=UNT0136 IN SAND ,Reach-1
Reach XY= 30
      3566402.11     10575491.64      3566349.81     10575302.75
      3566191.21     10575325.48      3566013.31     10575006.14
      3566033.23     10574871.71      3566082.23     10574929.42
      3566137.85     10574884.85       3566211.1     10574570.82
      3566105.94     10574515.72      3565958.27     10574593.09
      3565894.59     10574136.13      3565614.89     10574067.86
      3565409.49     10573889.28      3565244.24     10573887.91
      3565115.15     10573655.83      3564887.24     10573691.48
      3564732.11     10573621.64       3564703.1     10573472.17
      3564775.85     10573354.76       3564708.1     10573209.44
       3564545.6       10573185.       3564536.8     10572972.95
      3564417.51     10572894.28      3564364.06     10572645.37
        3564231.     10572554.31      3564052.19     10572561.17
      3563926.97       10572360.      3563734.15     10572342.76
      3563501.86     10572080.96      3563562.47     10571775.17

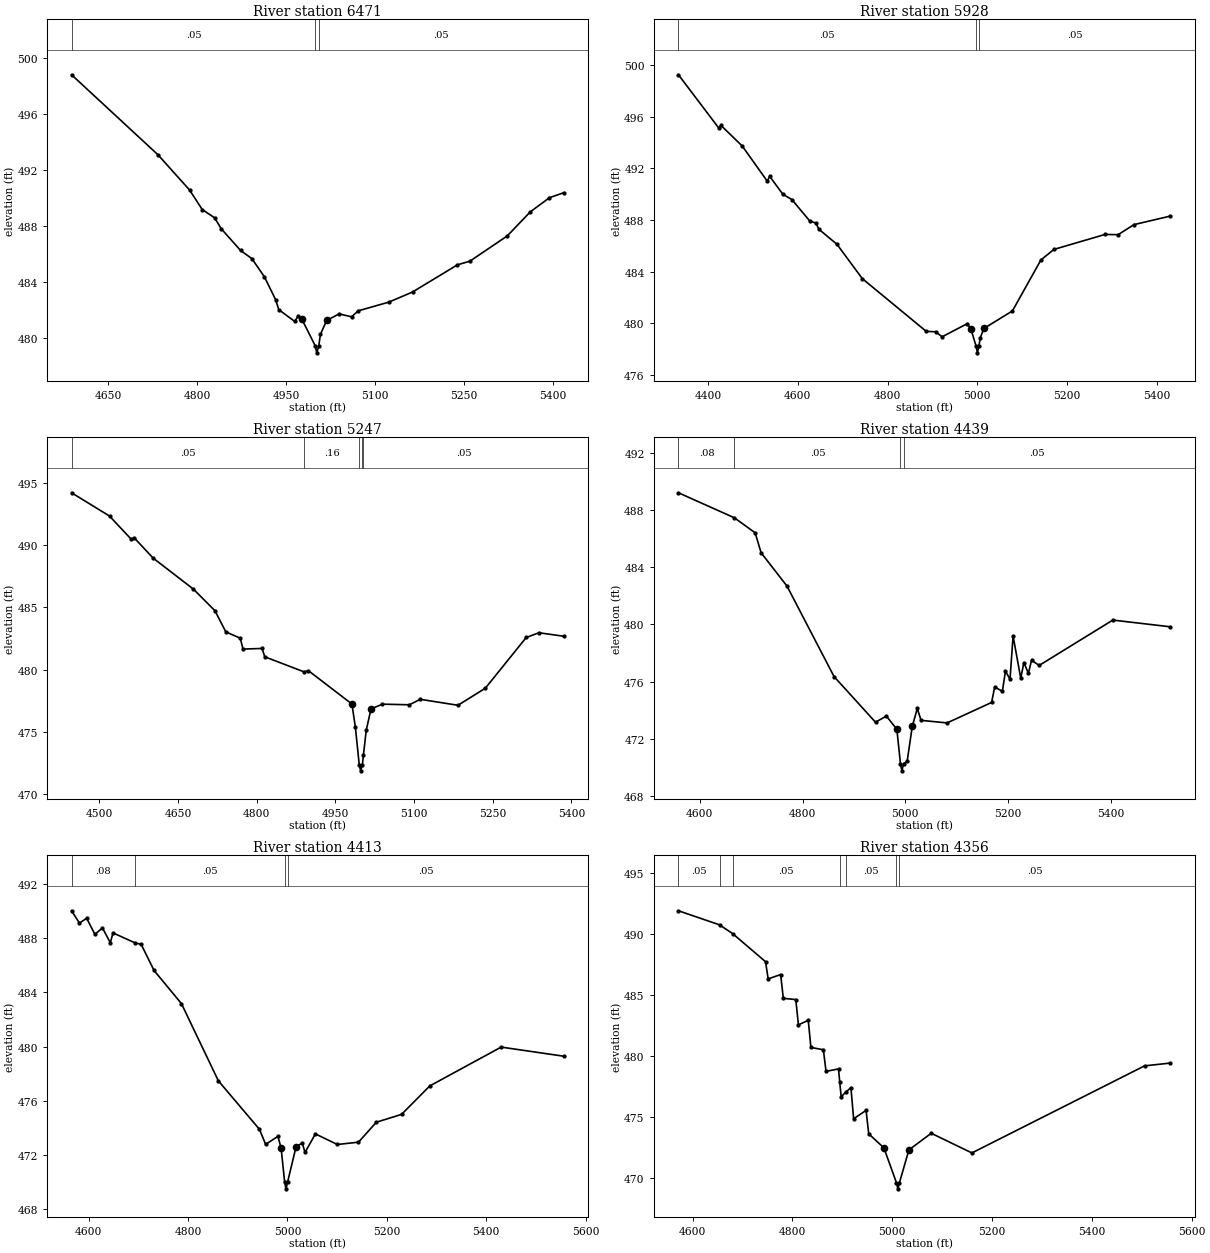
Type RM Length L Ch R = 1 ,6471    ,543,543,543
BEGIN DESCRIPTION:
UNT0136 IN SAND CR 8.0
END DESCRIPTION:
XS GIS Cut Line= 2
      3566771.67     10575291.23      3565981.71     10575542.97
#Sta/Elev= 30
  4588.3   498.8  4733.7   493.1  4787.3  490.57  4808.6  489.18  4829.2   488.6
  4840.8   487.8    4873  486.27  4892.2  485.68  4913.2  484.39  4932.2  482.75
  4937.5  482.04  4964.4   481.2  4969.7  481.56  4976.2  481.38  4998.9  479.46
  5001.6  478.96  5004.9  479.46  5007.7  480.28  5018.2  481.27  5039.3  481.74
  5060.1  481.53  5071.6  481.96  5123.1  482.58  5162.9   483.3  5238.6  485.24
  5259.6   485.5  5322.5   487.3  5361.4  489.02  5393.7  490.03  5417.4  490.38
#Mann= 3 ,-1 , 0
  4588.3     .05       0  4998.9     .04       0  5004.9     .05       0
Bank Sta=4976.2,5018.2
XS Rating Curve= 0 ,0
Exp/Cntr=0.3,0.1

Type RM Length L Ch R = 1 ,5928    ,681,681,681
BEGIN DESCRIPTION:
UNT0136 IN SAND CR 8.1
END DESCRIPTION:
XS GIS Cut Line= 3
      3566743.43     10574967.88      3566239.96     10575015.63
      3565774.27     10575377.35
#Sta/Elev= 30
  4334.4  499.24  4424.2  495.12  4429.2  495.32  4476.4  493.73  4532.4     491
  4537.4  491.39  4566.8     490  4586.9  489.59    4627  487.92  4640.6  487.77
  4647.1  487.29  4687.3  486.13  4743.8  483.47  4886.2  479.39    4907  479.36
  4921.5  478.97  4977.6  479.99  4985.8  479.55  4997.3  478.23    5000  477.73
  5003.3  478.23  5006.6  478.91  5014.7  479.62    5078  480.97  5141.4  484.91
  5170.4  485.73  5284.4  486.89  5313.4  486.87  5348.7  487.65  5429.8  488.31
#Mann= 3 ,-1 , 0
  4334.4     .05       0  4997.3     .03       0  5003.3     .05       0
Bank Sta=4985.8,5014.7
XS Rating Curve= 0 ,0
Exp/Cntr=0.3,0.1

Type RM Length L Ch R = 1 ,5247    ,808,808,808
BEGIN DESCRIPTION:
UNT0136 IN SAND CR 7.0
END DESCRIPTION:
XS GIS Cut Line= 2
      3566727.67     10574559.42      3565816.67     10574783.27
#Sta/Elev= 30
    4447  494.18  4519.4  492.31    4561  490.44  4566.1  490.58  4602.5  488.94
  4679.3  486.45  4720.5  484.71  4741.1  483.02  4768.7  482.51  4773.9  481.64
  4810.3  481.69  4815.4  481.02  4890.4  479.81  4898.5  479.91  4981.6  477.23
  4988.2  475.36  4995.5  472.37  4998.2  471.87  5001.5  472.37  5003.5  473.12
  5008.8  475.11    5018  476.84  5039.7  477.22  5091.2  477.17  5111.8  477.61
  5183.8  477.13    5236   478.5    5314  482.57  5338.3  482.95  5385.1  482.67
#Mann= 5 ,-1 , 0
    4447     .05       0  4890.4     .16       0  4995.5     .07       0
  5001.5     .16       0  5003.5     .05       0
Bank Sta=4981.6,5018
XS Rating Curve= 0 ,0
Exp/Cntr=0.3,0.1

Type RM Length L Ch R = 1 ,4439    ,26,26,26
BEGIN DESCRIPTION:
UNT0136 IN SAND CR 6.1
END DESCRIPTION:
XS GIS Cut Line= 4
      3566322.48     10574113.01      3565936.22     10574254.06
      3565877.63     10574254.06      3565475.54     10574530.76
#Sta/Elev= 30
  4558.3   489.2  4667.3  487.45  4707.7   486.4  4719.2  485.01  4769.6  482.68
  4861.3  476.35    4942  473.16  4963.2  473.59  4983.6  472.66  4990.6  470.26
  4993.4  469.76  4996.6  470.26  5003.6  470.42  5013.6  472.87  5023.4  474.12
  5030.7  473.29  5081.4  473.11    5168  474.54  5174.1  475.62    5189  475.32
  5195.1  476.73  5203.9  476.16  5209.9  479.19  5224.8  476.23  5230.9  477.33
  5239.7  476.58  5245.8  477.49  5260.7  477.13  5404.1   480.3  5516.2  479.83
#Mann= 4 ,-1 , 0
  4558.3     .08       0  4667.3     .05       0  4990.6     .03       0
  4996.6     .05       0
Bank Sta=4983.6,5013.6
XS Rating Curve= 0 ,0
Exp/Cntr=0.3,0.1

Type RM Length L Ch R = 1 ,4413    ,57,57,57
BEGIN DESCRIPTION:
UNT0136 IN SAND CR 6.0
END DESCRIPTION:
XS GIS Cut Line= 4
      3566320.75     10574090.89      3565932.79     10574226.41
      3565883.49     10574230.57       3565446.5     10574529.54
#Sta/Elev= 30
  4565.7  490.01  4581.6   489.1    4596  489.46  4612.7  488.27  4627.8  488.75
  4643.7  487.65    4649  488.38  4692.4  487.66  4705.8  487.53  4731.6  485.61
  4786.7  483.17  4861.1  477.47  4943.7   473.9  4956.2  472.79  4980.9  473.38
  4987.4   472.5  4994.4  470.01  4997.2  469.51  5000.4  470.01  5017.5  472.63
    5030  472.88  5035.4  472.19  5056.3  473.56  5100.5  472.78    5143  472.95
  5178.9  474.42  5229.7     475  5286.6   477.1  5430.1  479.96  5555.6  479.29
#Mann= 4 ,-1 , 0
  4565.7     .08       0  4692.4     .05       0  4994.4     .04       0
  5000.4     .05       0
Bank Sta=4987.4,5017.5
XS Rating Curve= 0 ,0
Exp/Cntr=0.3,0.1

Type RM Length L Ch R = 1 ,4356    ,118,118,118
BEGIN DESCRIPTION:
UNT0136 IN SAND CR 5.1
END DESCRIPTION:
XS GIS Cut Line= 4
      3566305.98     10574023.86      3565924.93     10574166.21
      3565853.75     10574187.04      3565426.98     10574456.59
#Sta/Elev= 30
  4571.7   491.9    4654  490.75  4680.6  490.02  4746.2  487.73  4751.5  486.32
  4776.5  486.68  4781.8  484.73  4806.8  484.63  4812.1  482.56  4831.8  482.93
  4837.1  480.71  4862.1  480.52  4867.4  478.75  4892.4  478.95  4894.9  477.87
  4897.7  476.67  4907.6  477.07  4917.3  477.42  4922.7  474.87  4947.6  475.55
    4953  473.63  4983.3  472.49  5008.5  469.63  5011.3  469.13  5014.5  469.63
  5033.5  472.32  5078.2  473.68  5159.7  472.07  5505.6   479.2  5557.4  479.43
#Mann= 7 ,-1 , 0
  4571.7     .05       0    4654     .08       0  4680.6     .05       0
  4894.9     .16       0  4907.6     .05       0  5008.5     .04       0
  5014.5     .05       0
Bank Sta=4983.3,5033.5
XS Rating Curve= 0 ,0
Exp/Cntr=0.3,0.1

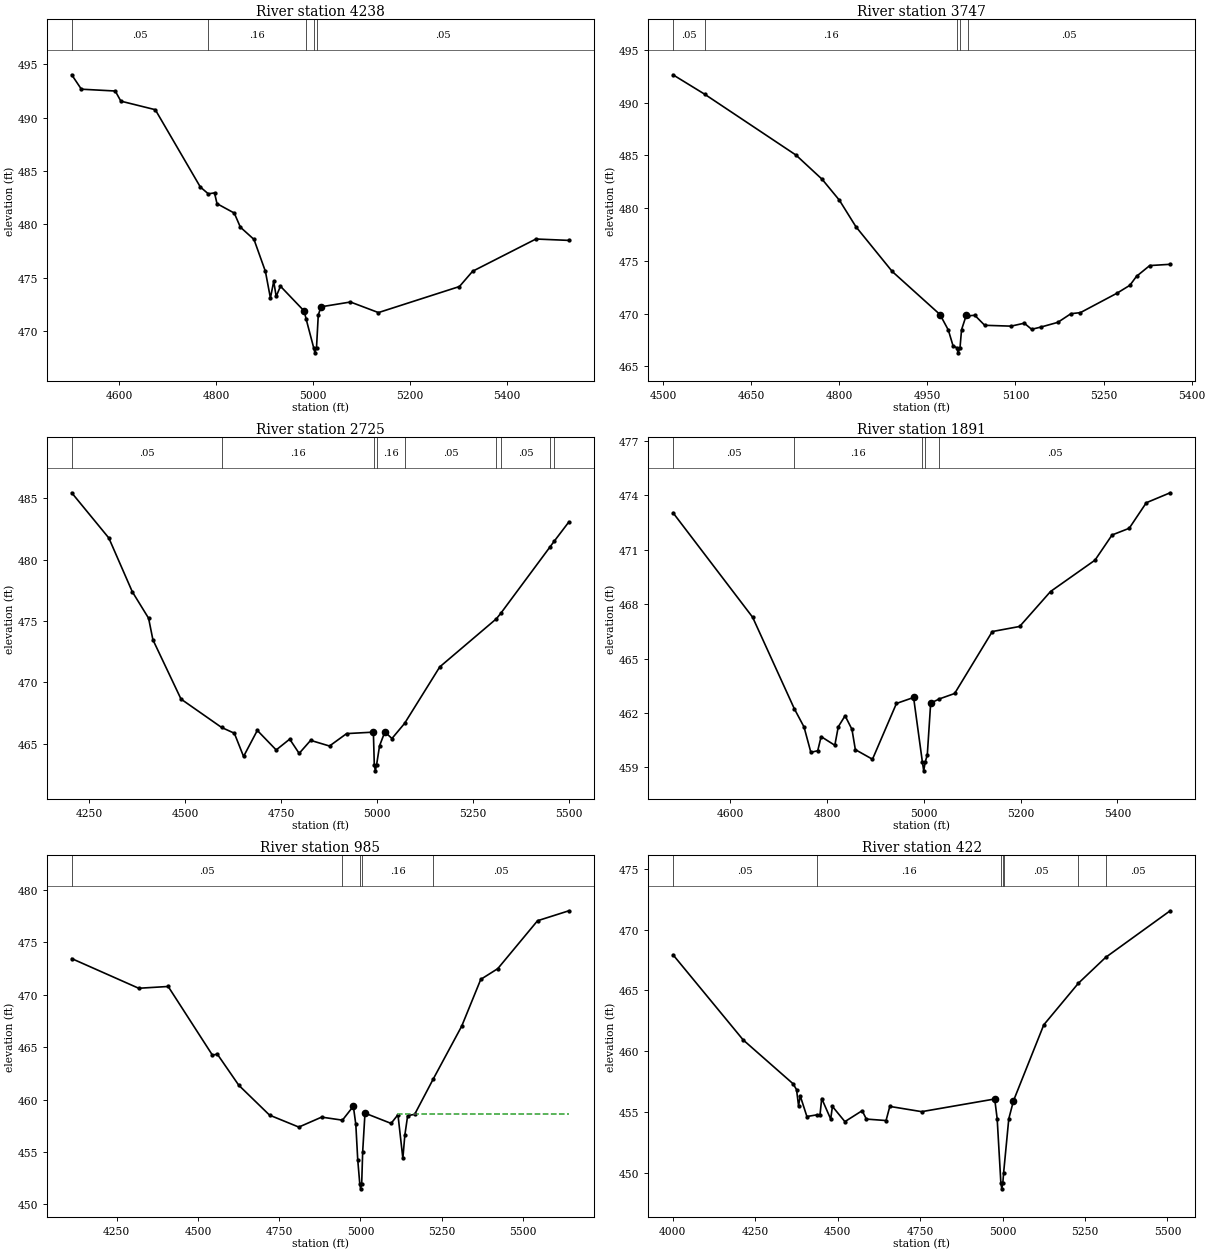
Type RM Length L Ch R = 1 ,4238    ,491,491,491
BEGIN DESCRIPTION:
UNT0136 IN SAND CR 5.0
END DESCRIPTION:
XS GIS Cut Line= 4
      3566279.06     10573992.35       3565844.2     10574104.32
      3565802.54     10574187.65      3565393.65     10574445.48
#Sta/Elev= 30
  4501.7  494.01  4521.6  492.66  4591.5  492.49  4603.1  491.54  4674.1  490.74
    4767   483.5  4783.5  482.86  4796.3  482.95  4801.4  481.94    4837  481.06
  4849.6  479.74  4877.7  478.59  4901.3  475.59  4911.6   473.1  4918.4  474.67
  4923.5  473.25  4932.3  474.21  4981.3  471.88    4985  471.18  5000.7  468.47
  5003.4  467.97  5006.7  468.47  5010.3   471.5  5015.9  472.28  5076.7  472.73
  5134.4  471.74  5301.5  474.18  5328.7  475.61  5459.3  478.63  5527.3   478.5
#Mann= 5 ,-1 , 0
  4501.7     .05       0  4783.5     .16       0    4985     .05       0
  5000.7     .03       0  5006.7     .05       0
Bank Sta=4981.3,5015.9
XS Rating Curve= 0 ,0
Exp/Cntr=0.3,0.1

Type RM Length L Ch R = 1 ,3747    ,1022,1022,1022
BEGIN DESCRIPTION:
UNT0136 IN SAND CR 4.0
END DESCRIPTION:
XS GIS Cut Line= 2
      3565870.04     10573701.03       3565110.5     10574074.29
#Sta/Elev= 30
    4517  492.63  4570.9  490.79  4726.4  485.02    4771  482.72  4800.3  480.74
  4828.4  478.23  4890.2  473.99  4971.5  469.91  4985.7  468.44  4993.8  466.93
  4999.6  466.78  5002.4  466.28  5005.6  466.78  5008.2  468.47  5016.1  469.82
    5020  469.79  5030.7  469.84  5047.6  468.89  5092.5  468.81    5115  469.09
  5127.5  468.51  5143.1  468.72  5172.1  469.17  5194.4  469.99  5210.5  470.09
  5272.4  471.92  5294.7  472.68    5306  473.53  5328.5  474.55  5363.3  474.67
#Mann= 5 ,-1 , 0
    4517     .05       0  4570.9     .16       0  4999.6     .07       0
  5005.6     .16       0    5020     .05       0
Bank Sta=4971.5,5016.1
XS Rating Curve= 0 ,0
Exp/Cntr=0.3,0.1

Type RM Length L Ch R = 1 ,2725    ,834,834,834
BEGIN DESCRIPTION:
UNT0136 IN SAND CR 3.0
END DESCRIPTION:
XS GIS Cut Line= 3
      3565449.06      10573242.4      3564554.93     10573589.63
      3564307.51     10573815.35
#Sta/Elev= 30
  4204.8  485.44  4301.4  481.76  4362.4  477.39  4404.9  475.23  4416.1  473.48
  4489.3  468.65    4595  466.34  4628.1  465.87  4652.1  463.98  4687.9   466.1
    4737  464.51  4772.2  465.39  4796.8  464.23  4826.7  465.29  4875.8  464.83
  4920.3  465.84    4990  465.96  4992.4  463.31  4995.1  462.81  4998.4  463.31
  5006.1  464.85  5019.9  465.98  5038.3  465.44  5071.2  466.67  5162.8  471.27
  5310.3  475.19  5322.1  475.65  5449.9  481.04    5461  481.51  5498.9  483.07
#Mann= 9 ,-1 , 0
  4204.8     .05       0    4595     .16       0  4992.4     .07       0
  4998.4     .16       0  5071.2     .05       0  5310.3      .1       0
  5322.1     .05       0  5449.9      .1       0    5461     .05       0
Bank Sta=4990,5019.9
XS Rating Curve= 0 ,0
Exp/Cntr=0.3,0.1

Type RM Length L Ch R = 1 ,1891    ,906,906,906
BEGIN DESCRIPTION:
UNT0136 IN SAND CR 1.0
END DESCRIPTION:
XS GIS Cut Line= 2
      3564838.98     10572575.76      3564106.31     10573295.43
#Sta/Elev= 30
  4481.9  473.05  4646.4  467.28  4732.5  462.23  4752.6  461.22  4766.7  459.82
  4780.9  459.91  4787.9  460.69  4816.2  460.21  4823.3  461.23  4837.4  461.84
  4851.6  461.09  4858.6  459.97    4894  459.44  4943.5  462.52  4978.9  462.85
    4997   459.3  4999.8   458.8    5003   459.3  5007.2  459.67  5014.2  462.54
  5032.1  462.77  5063.7  463.07  5141.5  466.49    5198  466.77  5261.8   468.7
  5353.6  470.43  5388.9  471.82  5424.3  472.19  5459.6   473.6  5508.9  474.15
#Mann= 5 ,-1 , 0
  4481.9     .05       0  4732.5     .16       0    4997     .07       0
    5003     .16       0  5032.1     .05       0
Bank Sta=4978.9,5014.2
XS Rating Curve= 0 ,0
Exp/Cntr=0.3,0.1

Type RM Length L Ch R = 1 ,985     ,563,563,563
BEGIN DESCRIPTION:
UNT0136 IN SAND CR 1.1
END DESCRIPTION:
XS GIS Cut Line= 5
      3564826.79     10572429.69      3564292.04     10572363.72
      3564010.79     10572346.36      3563670.51     10572568.58
      3563548.99     10572846.36
#Sta/Elev= 30
  4111.3  473.45  4317.5  470.62  4408.2  470.79  4544.4  464.24  4559.4  464.34
  4625.5  461.37  4720.2  458.52  4810.3  457.38  4880.5  458.33  4944.5  458.04
  4978.1  459.37  4985.7  457.63  4991.6  454.27  4997.8  451.99  5000.5  451.49
  5003.8  451.99  5006.8  455.01  5013.9  458.71  5094.3  457.73  5115.4  458.56
  5130.5  454.39  5136.5  456.59  5145.3  458.48  5166.7  458.59  5224.6     462
  5311.5     467  5370.3  471.47  5422.6  472.49    5545  477.06  5641.5  478.01
#Mann= 5 ,-1 , 0
  4111.3     .05       0  4944.5     .16       0  4997.8     .07       0
  5003.8     .16       0  5224.6     .05       0
#XS Ineff= 2 , 0
                         5114.77          458.67
Permanent Ineff=
       F       F
Bank Sta=4978.1,5013.9
XS Rating Curve= 0 ,0
Exp/Cntr=0.3,0.1

Type RM Length L Ch R = 1 ,422     ,0,0,0
BEGIN DESCRIPTION:
UNT0136 IN SAND CR 1.2
END DESCRIPTION:
XS GIS Cut Line= 4
       3564439.7     10572250.22       3563632.4     10571998.49
      3563445.77     10572206.82      3563415.47     10572587.67
#Sta/Elev= 30
  4000.8  467.93  4213.7  460.93  4364.9  457.33  4375.4  456.85  4381.5  455.53
  4386.7  456.33  4406.8  454.64  4437.6  454.78  4446.5  454.76  4451.7  456.12
    4479  454.43  4484.2  455.47    4522  454.22  4574.4  455.12    4587  454.43
  4646.8  454.31  4658.2  455.47  4754.8  455.04  4976.2  456.08  4983.7  454.46
  4994.9   449.2  4997.7   448.7  5000.9   449.2  5003.2     450  5018.9  454.45
  5033.1  455.93    5125  462.17    5230  465.59  5312.5  467.71  5508.2  471.54
#Mann= 7 ,-1 , 0
  4000.8     .05       0  4437.6     .16       0  4994.9     .07       0
  5000.9     .16       0  5003.2     .05       0    5230     .08       0
  5312.5     .05       0
Bank Sta=4976.2,5033.1
XS Rating Curve= 0 ,0
Exp/Cntr=0.3,0.1

Chan Stop Cuts=-1
Use User Specified Reach Order=0
Composite Channel Slope=5