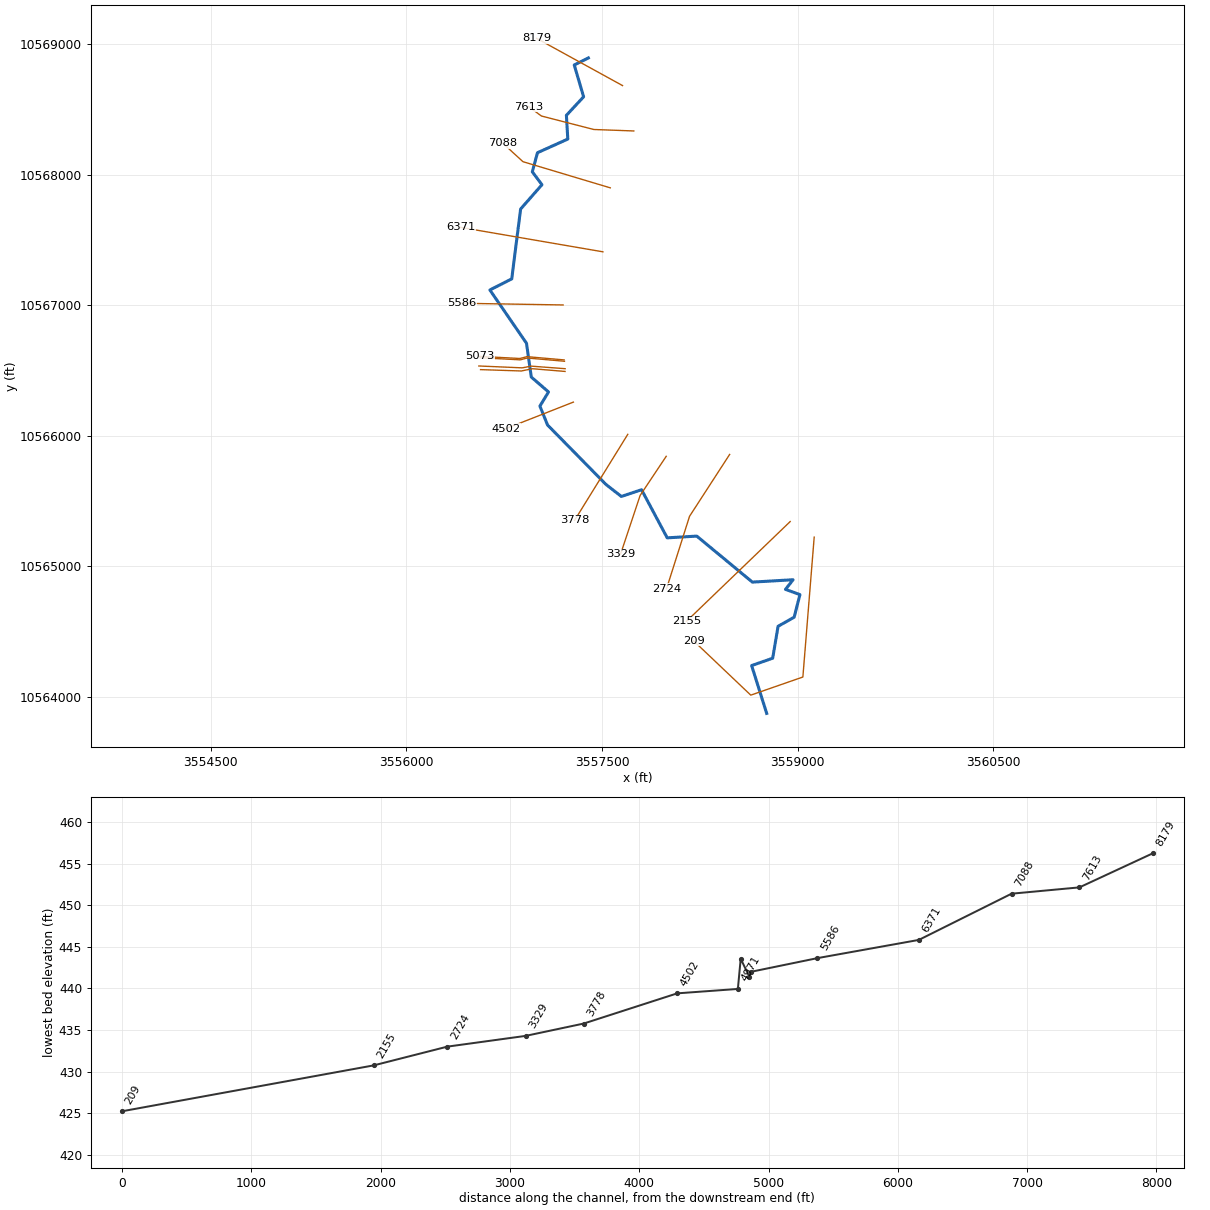
--- UNT0139 IN SAND CR.prj (project) ---

Proj Title=UNT0139 IN SAND CR Base Level Engineering
Current Plan=p01
Default Exp/Contr=0.3,0.1
English Units
Geom File=g01
Flow File=f01
Plan File=p01
Y Axis Title=Elevation
X Axis Title(PF)=Main Channel Distance
X Axis Title(XS)=Station
BEGIN DESCRIPTION:
UNT0139 IN SAND CR
END DESCRIPTION:
DSS Export Rating Curves= 0
DSS Export Rating Curve Sorted= 0
DSS Export Volume Flow Curves= 0
DXF OffsetX= 0
DXF OffsetY= 0
DXF ScaleX= 1
DXF ScaleY= 10

--- UNT0139 IN SAND CR.p01 (plan) ---

Plan Title=Multiple Run
Short Identifier=Multiple
Geom File=g01
Flow File=f01
Subcritical Flow
K Sum by GR= 0
Std Step Tol= 0.01
Critical Tol= 0.01
Num of Std Step Trials= 20
Max Error Tol= 0.3
Flow Tol Ratio= 0.001
Split Flow NTrial= 30
Split Flow Tol= 0.02
Split Flow Ratio= 0.02
Log Output Level= 0
Friction Slope Method= 1
Unsteady Friction Slope Method= 2
Unsteady Bridges Friction Slope Method= 1
Parabolic Critical Depth
Global Vel Dist=  1 , 1 , 1
Global Log Level= 0
CheckData=True
Encroach Param= -1, 0, 0, 0
BEGIN DESCRIPTION:
Multiple Run
END DESCRIPTION:

--- UNT0139 IN SAND CR.f01 (steady flow) ---

Flow Title=Multiple
Number of Profiles=7
Profile Names=10-year,25-year,50-year,1pct_min,100-year,1pct_plu,500-year
River Rch & RM= UNT0139 IN SAND ,Reach-1,8179
     411     531     624     536     725     981     975
River Rch & RM= UNT0139 IN SAND ,Reach-1,6371
     840    1132    1367    1205    1629    2203    2307
Boundary for River Rch & Prof#=UNT0139 IN SAND ,Reach-1,1
Up Type=0
Dn Type=3
Dn Slope=0.005
Boundary for River Rch & Prof#=UNT0139 IN SAND ,Reach-1,2
Up Type=0
Dn Type=3
Dn Slope=0.005
Boundary for River Rch & Prof#=UNT0139 IN SAND ,Reach-1,3
Up Type=0
Dn Type=3
Dn Slope=0.005
Boundary for River Rch & Prof#=UNT0139 IN SAND ,Reach-1,4
Up Type=0
Dn Type=3
Dn Slope=0.005
Boundary for River Rch & Prof#=UNT0139 IN SAND ,Reach-1,5
Up Type=0
Dn Type=3
Dn Slope=0.005
Boundary for River Rch & Prof#=UNT0139 IN SAND ,Reach-1,6
Up Type=0
Dn Type=3
Dn Slope=0.005
Boundary for River Rch & Prof#=UNT0139 IN SAND ,Reach-1,7
Up Type=0
Dn Type=3
Dn Slope=0.005

--- UNT0139 IN SAND CR.g01 (geometry) ---

Geom Title=Existing Conditions
Program Version=4.10

River Reach=UNT0139 IN SAND ,Reach-1
Reach XY= 30
      3557395.69     10568895.02      3557287.16     10568840.85
      3557359.05     10568597.07      3557227.04     10568454.92
      3557237.87     10568273.04      3557005.45     10568168.64
      3556965.81     10568022.14      3557039.78     10567923.24
      3556876.18     10567736.91      3556808.14     10567201.47
      3556640.69     10567116.58      3556921.42     10566707.98
      3556957.94     10566449.31      3557090.05     10566334.97
      3557024.11     10566226.64      3557082.65     10566081.64
      3557530.33     10565626.05      3557647.99     10565534.14
      3557803.15      10565585.4      3557999.67     10565216.87
      3558226.16     10565230.31      3558652.25     10564877.72
      3558964.23     10564895.68      3558906.15     10564821.98
      3559016.83     10564781.88      3558972.82     10564608.96
      3558849.38     10564538.91      3558807.98     10564294.38
      3558646.72       10564238.      3558762.11     10563871.64

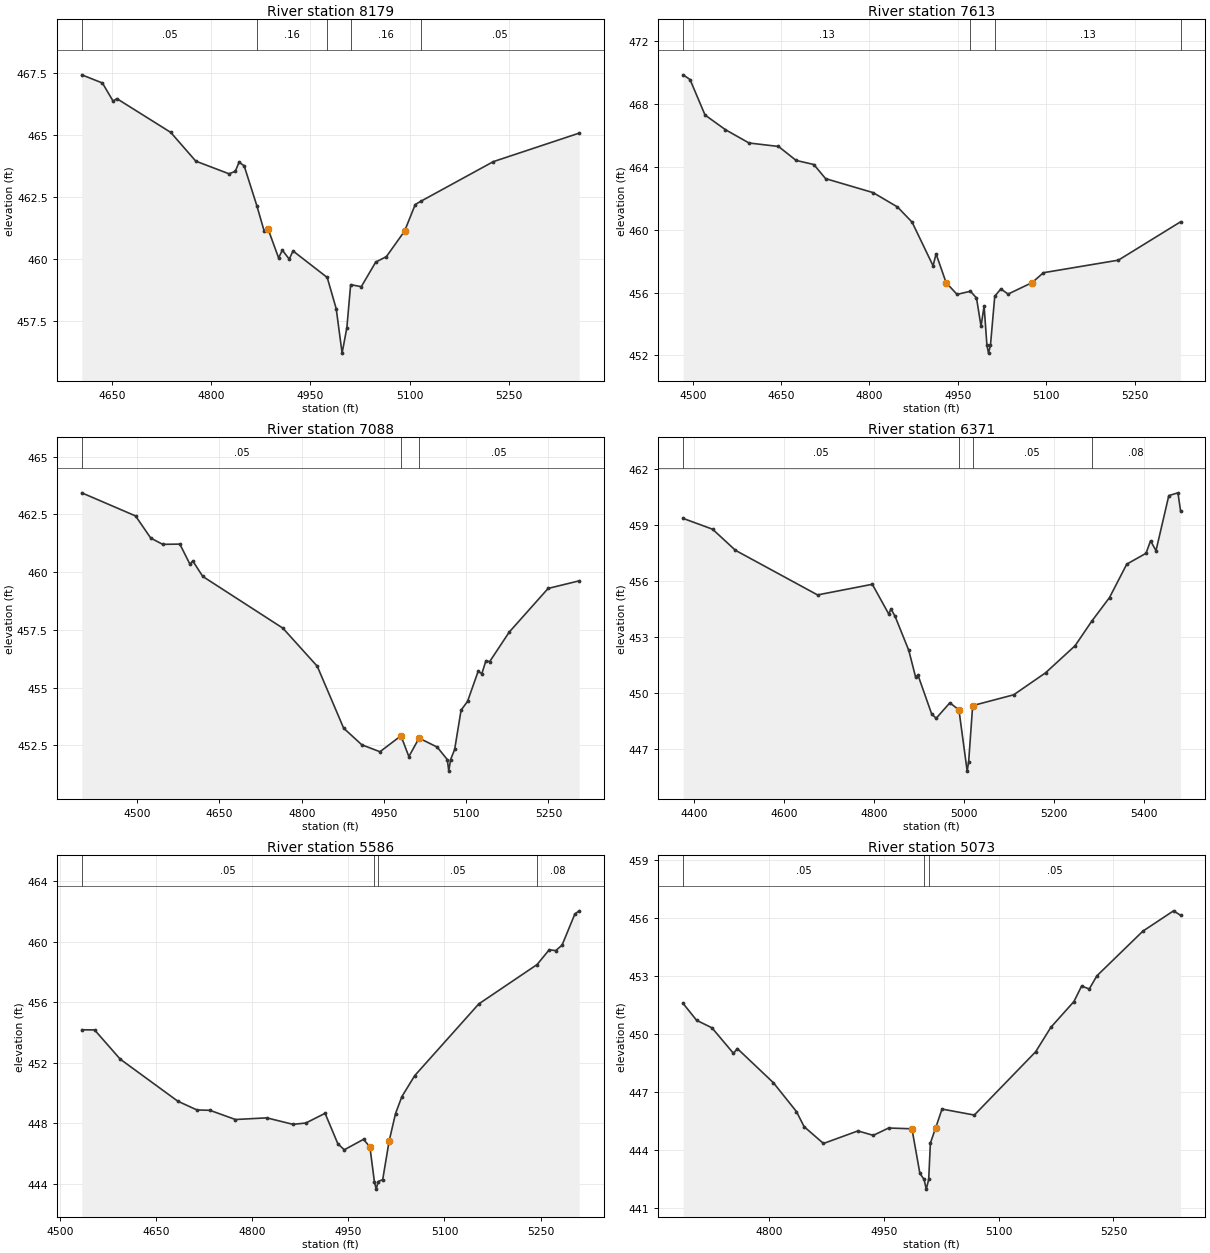
Type RM Length L Ch R = 1 ,8179    ,566,566,566
BEGIN DESCRIPTION:
UNT01637 IN SAND CR 3.0
END DESCRIPTION:
XS GIS Cut Line= 2
      3557657.14     10568683.13      3556998.33     10569045.09
#Sta/Elev= 30
  4604.5  467.44  4635.7  467.11  4651.8  466.38  4657.5  466.48  4738.9  465.12
  4776.8  463.96    4827  463.45  4836.5  463.55  4842.2  463.92  4849.9  463.77
  4869.1  462.16  4880.1  461.14  4885.8  461.24  4901.9  460.06  4907.6  460.37
    4918  460.01  4923.7  460.34  4975.4  459.27    4989  458.01  4997.9  456.22
  5005.1  457.25  5010.8  458.98  5026.9   458.9  5048.7  459.89  5064.8  460.11
  5092.3  461.14  5108.4  462.21  5116.7  462.34  5226.4  463.94  5356.2  465.09
#Mann= 5 ,-1 , 0
  4604.5     .05       0  4869.1     .16       0  4975.4     .07       0
  5010.8     .16       0  5116.7     .05       0
Bank Sta=4885.8,5092.3
XS Rating Curve= 0 ,0
Exp/Cntr=0.3,0.1

Type RM Length L Ch R = 1 ,7613    ,525,525,525
BEGIN DESCRIPTION:
UNT01637 IN SAND CR 2.0
END DESCRIPTION:
XS GIS Cut Line= 4
      3557743.79     10568335.27       3557437.3     10568346.44
       3557035.5     10568449.85      3556936.79     10568522.59
#Sta/Elev= 30
  4483.7  469.86  4495.4  469.56  4520.9   467.3  4555.4  466.37  4595.5  465.52
  4645.5   465.3  4675.5  464.41  4705.5  464.15  4725.5  463.25  4806.1  462.36
  4847.4  461.45  4872.3  460.48  4907.9   457.7    4913  458.46    4930  456.63
  4948.6  455.88  4971.3  456.08  4981.6  455.65  4989.3  453.85  4994.5  455.14
  4999.3  452.64    5002  452.14  5005.3  452.64  5012.6  455.76  5022.9  456.23
  5035.2   455.9  5075.9  456.63  5095.2  457.26  5222.4  458.06  5327.9   460.5
#Mann= 4 ,-1 , 0
  4483.7     .13       0  4971.3     .05       0  5012.6     .13       0
  5327.9     .05       0
Bank Sta=4930,5075.9
XS Rating Curve= 0 ,0
Exp/Cntr=0.3,0.1

Type RM Length L Ch R = 1 ,7088    ,717,717,717
BEGIN DESCRIPTION:
UNT01637 IN SAND CR 1.0
END DESCRIPTION:
XS GIS Cut Line= 3
      3557563.41     10567899.27      3556894.13     10568099.79
      3556740.45     10568240.44
#Sta/Elev= 30
    4399  463.43    4497  462.43  4524.8  461.47  4546.5   461.2  4577.8  461.21
  4596.2  460.34  4601.4  460.48  4619.6  459.81  4765.7  457.57  4828.4  455.92
  4876.5  453.24  4909.6  452.52  4942.7  452.22    4981  452.91  4995.4  452.01
    5014  452.81  5047.1  452.42  5065.5  451.88  5068.2  451.38  5071.5  451.88
  5078.9  452.32  5090.6  454.02  5102.4   454.4  5121.7   455.7  5128.5   455.6
  5135.9  456.16  5142.7  456.12  5178.4   457.4  5249.3  459.29    5306  459.62
#Mann= 3 , 0 , 0
    4399     .05       0    4981     .03       0    5014     .05       0
Bank Sta=4981,5014
XS Rating Curve= 0 ,0
Exp/Cntr=0.3,0.1

Type RM Length L Ch R = 1 ,6371    ,785,785,785
BEGIN DESCRIPTION:
UNT0139 IN SAND CR 10.0
END DESCRIPTION:
XS GIS Cut Line= 2
      3557506.79     10567409.03      3556416.37     10567596.41
#Sta/Elev= 30
    4376  459.37  4441.6  458.79  4492.4  457.66    4675  455.27  4796.8  455.84
  4833.3  454.25  4838.3  454.52  4847.5  454.12  4877.9   452.3  4893.2  450.86
  4898.3  450.98  4928.7   448.9  4938.8  448.66  4969.3  449.49  4989.5  449.11
  5007.8  445.83  5011.1  446.33    5020  449.34  5111.3  449.92  5182.3   451.1
  5247.9  452.55  5284.8  453.86  5324.4  455.13  5362.8  456.92  5405.6   457.5
  5415.7  458.17  5427.8  457.64  5456.3  460.59  5476.6  460.74  5482.4  459.78
#Mann= 4 ,-1 , 0
    4376     .05       0  4989.5     .03       0    5020     .05       0
  5284.8     .08       0
Bank Sta=4989.5,5020
XS Rating Curve= 0 ,0
Exp/Cntr=0.3,0.1

Type RM Length L Ch R = 1 ,5586    ,513,513,513
BEGIN DESCRIPTION:
UNT0139 IN SAND CR 9.0
END DESCRIPTION:
XS GIS Cut Line= 2
      3557202.08     10567001.75      3556425.29     10567014.74
#Sta/Elev= 30
  4533.5  454.17  4553.5  454.16  4593.5  452.23  4683.5  449.45  4713.5  448.87
  4733.5  448.85  4773.5  448.24  4822.4  448.35  4863.5  447.92  4883.5  448.01
  4913.5  448.65  4933.5  446.63  4943.5  446.24  4973.5  446.93  4983.5  446.43
  4990.5  444.14  4993.3  443.64  4996.5  444.14  5003.5  444.27  5013.5  446.81
  5023.5  448.63  5033.5  449.76  5053.5  451.14  5153.6  455.88  5244.6  458.48
  5263.6  459.46  5273.6   459.4  5283.6  459.76  5303.6  461.82  5310.4  462.03
#Mann= 4 ,-1 , 0
  4533.5     .05       0  4990.5     .03       0  4996.5     .05       0
  5244.6     .08       0
Bank Sta=4983.5,5013.5
XS Rating Curve= 0 ,0
Exp/Cntr=0.3,0.1

Type RM Length L Ch R = 1 ,5073    ,12,12,12
BEGIN DESCRIPTION:
UNT0139 IN SAND CR 7.2
END DESCRIPTION:
XS GIS Cut Line= 4
      3557209.63     10566580.64       3556924.3      10566605.6
      3556871.13     10566591.49      3556562.98     10566607.77
#Sta/Elev= 30
  4687.7   451.6  4705.3  450.73  4725.4  450.34  4753.5  449.02  4758.5  449.27
  4805.7   447.5  4835.8  446.01  4845.8  445.23  4871.1  444.36  4916.1  445.01
  4936.2  444.78  4956.2  445.16  4986.7  445.12  4997.1  442.81  5002.6   442.5
  5005.4     442  5008.6   442.5  5010.8  444.38  5017.8  445.18    5026  446.14
  5068.2  445.83  5148.3   449.1  5168.3  450.37  5198.4   451.7  5208.4   452.5
  5218.4  452.35  5228.4  453.03  5288.5  455.34  5328.6  456.39  5337.7  456.16
#Mann= 3 ,-1 , 0
  4687.7     .05       0  5002.6     .03       0  5008.6     .05       0
Bank Sta=4986.7,5017.8
XS Rating Curve= 0 ,0
Exp/Cntr=0.3,0.1

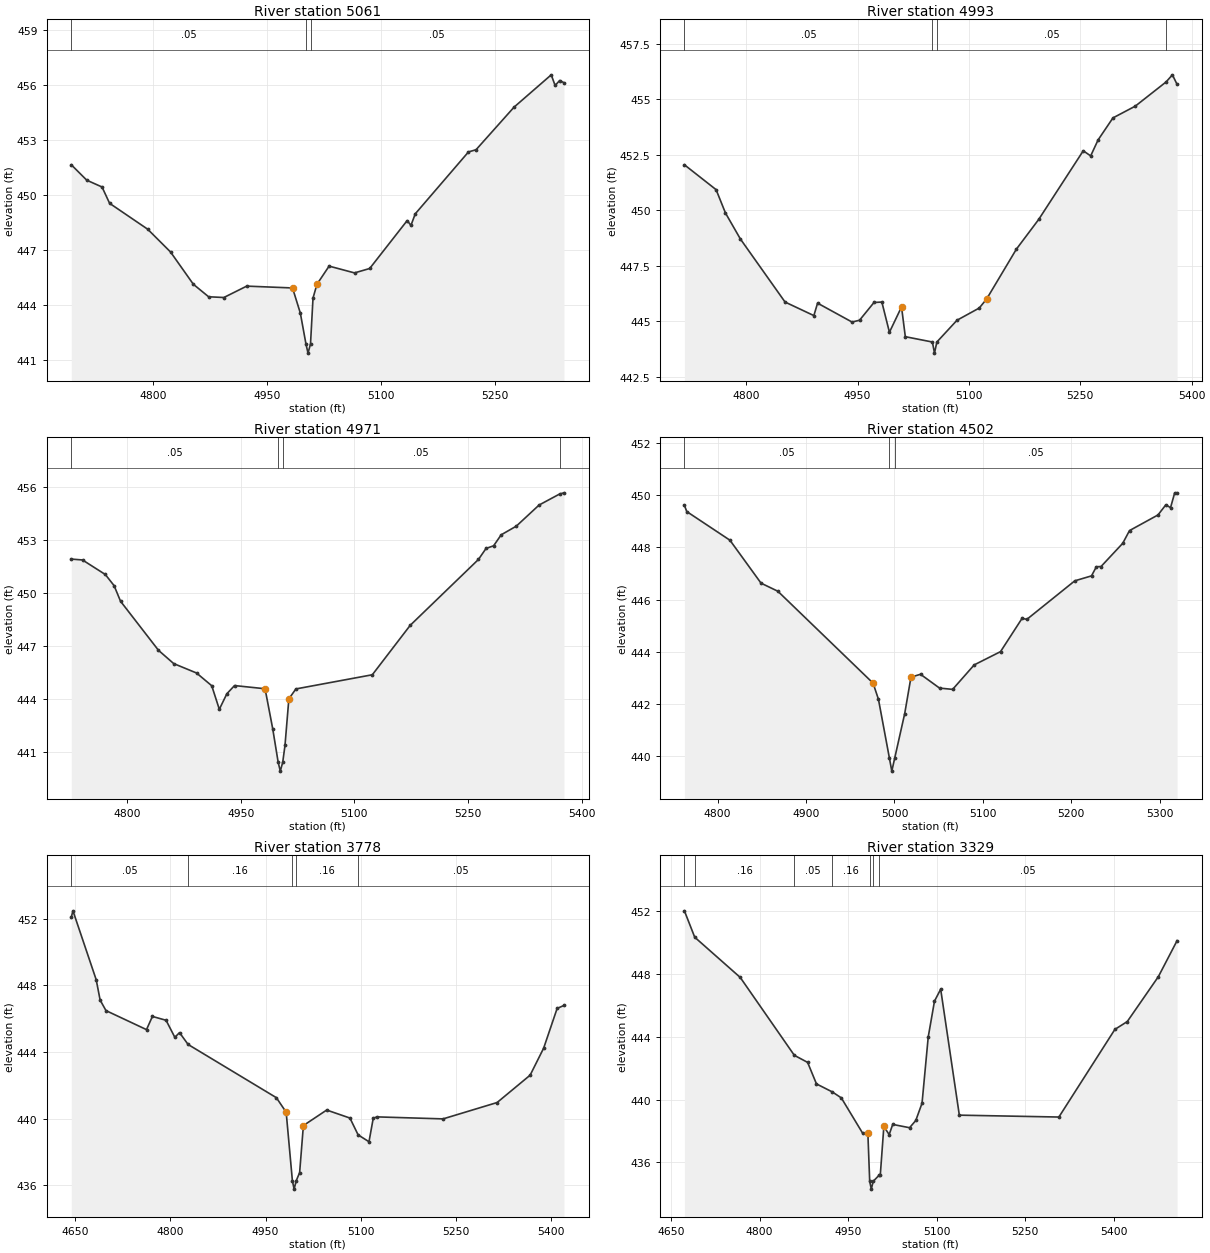
Type RM Length L Ch R = 1 ,5061    ,68,68,68
BEGIN DESCRIPTION:
UNT0139 IN SAND CR 7.3
END DESCRIPTION:
XS GIS Cut Line= 4
      3557212.44     10566570.22      3556927.08     10566595.18
      3556873.91     10566581.07       3556566.4     10566597.32
#Sta/Elev= 30
    4692  451.64  4712.4   450.8  4732.5  450.43  4742.5  449.54  4792.7  448.13
  4822.8  446.89  4852.9  445.13    4873  444.45  4893.1  444.41  4923.2  445.03
  4983.6  444.93  4993.9  443.56  5001.3  441.88    5004  441.38  5007.3  441.88
  5010.6  444.38  5015.8  445.13  5031.8  446.12  5065.3  445.75  5085.3  445.99
  5134.7   448.6  5139.7  448.34  5145.4  448.97  5215.5  452.34  5225.5  452.46
  5275.6  454.78  5324.6  456.54  5329.7  455.96  5335.7  456.23  5341.4  456.11
#Mann= 3 ,-1 , 0
    4692     .05       0  5001.3     .03       0  5007.3     .05       0
Bank Sta=4983.6,5015.8
XS Rating Curve= 0 ,0
Exp/Cntr=0.3,0.1

Type RM Length L Ch R = 1 ,4993    ,22,22,22
BEGIN DESCRIPTION:
UNT0139 IN SAND CR 7.1
END DESCRIPTION:
XS GIS Cut Line= 4
       3557217.3     10566513.25      3556958.18     10566532.78
      3556887.87     10566519.76      3556555.83     10566534.03
#Sta/Elev= 30
  4716.7  452.04  4759.4  450.92    4772  449.87  4792.1   448.7  4852.3  445.86
  4891.1  445.25  4896.1  445.81  4942.5  444.96  4952.6  445.04  4972.1  445.84
  4982.7  445.86  4992.9   444.5  5009.2  445.64  5014.3   444.3  5050.8  444.06
  5053.6  443.56  5056.8  444.06  5083.9  445.04  5113.9  445.59  5123.9     446
  5163.9  448.24    5194  449.58    5254  452.67    5264  452.44    5274  453.16
    5294  454.15  5324.1  454.68  5365.6  455.77  5374.1  456.09  5380.4  455.66
#Mann= 4 ,-1 , 0
  4716.7     .05       0  5050.8     .03       0  5056.8     .05       0
  5365.6     .08       0
Bank Sta=5009.2,5123.9
XS Rating Curve= 0 ,0
Exp/Cntr=0.3,0.1

Type RM Length L Ch R = 1 ,4971    ,469,469,469
BEGIN DESCRIPTION:
UNT0139 IN SAND CR 7.0
END DESCRIPTION:
XS GIS Cut Line= 4
      3557216.83     10566492.24      3556966.83     10566513.08
      3556881.76     10566495.72      3556569.23     10566506.13
#Sta/Elev= 30
  4726.4  451.91  4741.2  451.86  4771.3  451.04  4782.9  450.41  4791.4  449.53
  4841.5  446.76  4861.6  446.01  4891.7  445.48  4911.8  444.76  4921.8  443.43
  4931.8  444.31  4941.9  444.77  4982.2  444.59  4992.3  442.33  4999.5  440.44
  5002.3  439.94  5005.5  440.44  5008.5  441.39  5013.6  444.02  5022.9  444.58
  5123.8  445.38  5173.8  448.17  5263.9  451.89  5273.9  452.51  5283.9  452.66
  5293.9  453.28  5313.9  453.77  5343.9  454.96  5370.9  455.58  5376.8  455.65
#Mann= 4 ,-1 , 0
  4726.4     .05       0  4999.5     .03       0  5005.5     .05       0
  5370.9     .08       0
Bank Sta=4982.2,5013.6
XS Rating Curve= 0 ,0
Exp/Cntr=0.3,0.1

Type RM Length L Ch R = 1 ,4502    ,724,724,724
BEGIN DESCRIPTION:
UNT0139 IN SAND CR 6.0
END DESCRIPTION:
XS GIS Cut Line= 2
      3557280.67     10566257.23      3556762.04     10566053.25
#Sta/Elev= 30
  4762.4  449.62  4765.1  449.38  4813.9  448.28  4849.1  446.63  4868.1  446.32
  4975.8  442.79  4981.9  442.17  4994.3  439.91    4997  439.41  5000.3  439.91
  5011.6  441.62  5018.7  443.02  5029.5  443.13    5051   442.6  5065.8  442.55
  5090.2  443.49    5120     444  5144.4  445.28  5149.8  445.24    5204  446.72
  5222.9  446.91  5228.4  447.26  5233.7  447.27  5258.2  448.16  5265.9  448.65
  5298.1  449.25    5307  449.64  5312.3  449.53    5317   450.1  5319.7   450.1
#Mann= 3 ,-1 , 0
  4762.4     .05       0  4994.3     .03       0  5000.3     .05       0
Bank Sta=4975.8,5018.7
XS Rating Curve= 0 ,0
Exp/Cntr=0.3,0.1

Type RM Length L Ch R = 1 ,3778    ,449,449,449
BEGIN DESCRIPTION:
UNT0139 IN SAND CR 6.1
END DESCRIPTION:
XS GIS Cut Line= 2
      3557697.58     10566010.24      3557289.58      10565350.5
#Sta/Elev= 30
  4644.2  452.08  4646.8  452.46  4683.4  448.33  4689.6  447.11  4698.8  446.48
  4762.6  445.34  4771.9  446.13  4793.4   445.9  4807.2  444.88  4814.6  445.16
  4828.1  444.45  4967.1  441.26  4982.5  440.39  4992.3  436.28    4995  435.78
  4998.3  436.28  5003.7  436.77  5009.6  439.59  5046.3  440.52  5082.9  440.04
  5095.8  439.03  5112.9  438.62  5119.6  440.03  5125.5  440.11  5229.5  439.99
  5314.6  440.97  5366.6  442.61  5387.9  444.23  5409.1  446.61  5419.9  446.79
#Mann= 5 ,-1 , 0
  4644.2     .05       0  4828.1     .16       0  4992.3     .07       0
  4998.3     .16       0  5095.8     .05       0
Bank Sta=4982.5,5009.6
XS Rating Curve= 0 ,0
Exp/Cntr=0.3,0.1

Type RM Length L Ch R = 1 ,3329    ,605,605,605
BEGIN DESCRIPTION:
UNT0139 IN SAND CR 4.0
END DESCRIPTION:
XS GIS Cut Line= 3
      3557992.09     10565841.61      3557792.11     10565541.64
      3557642.09     10565091.61
#Sta/Elev= 30
  4672.7  452.02  4690.2  450.34  4767.3  447.78    4859  442.82  4881.5  442.37
  4896.5     441  4923.3  440.49  4938.6  440.11  4974.6  437.87  4983.6  437.87
  4986.7   434.8  4989.4   434.3  4992.7   434.8  5003.3  435.21  5004.7  435.22
  5010.7  438.29  5019.7  437.77  5025.7  438.42  5054.3  438.21  5064.8  438.67
  5075.4  439.77  5085.9  443.99  5096.5  446.27    5107  447.03  5138.6  439.01
  5307.3  438.89  5402.2  444.47  5423.2  444.97  5475.9  447.83  5507.6  450.12
#Mann= 7 ,-1 , 0
  4672.7     .05       0  4690.2     .16       0    4859     .05       0
  4923.3     .16       0  4986.7     .07       0  4992.7     .16       0
  5003.3     .05       0
Bank Sta=4983.6,5010.7
XS Rating Curve= 0 ,0
Exp/Cntr=0.3,0.1

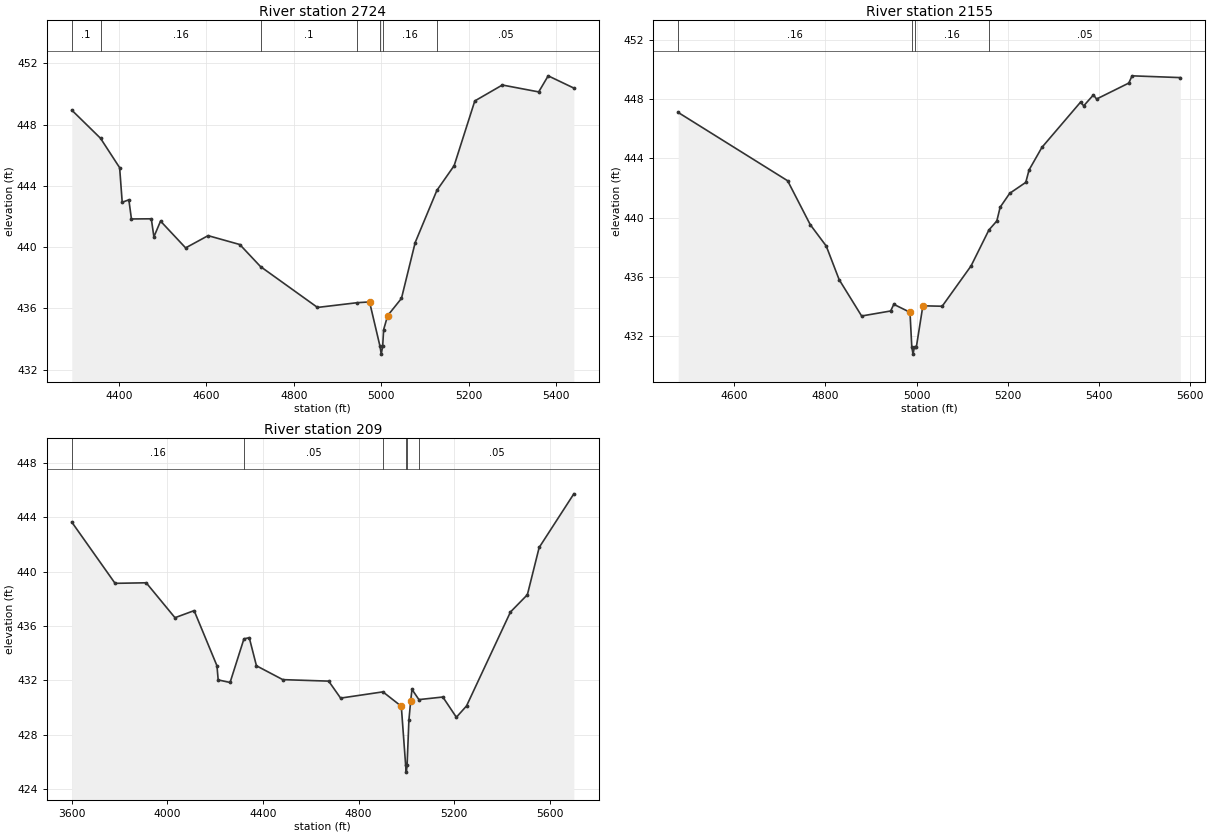
Type RM Length L Ch R = 1 ,2724    ,569,569,569
BEGIN DESCRIPTION:
UNT0139 IN SAND CR 3.0
END DESCRIPTION:
XS GIS Cut Line= 3
      3558478.21      10565856.1      3558170.92     10565382.14
      3557994.11     10564825.72
#Sta/Elev= 30
  4292.2  448.95    4358  447.11  4401.7  445.19  4407.6  442.93  4422.8  443.09
  4428.7  441.84  4474.2  441.85  4480.1  440.67  4495.3   441.7  4552.7  439.95
  4604.1  440.75  4676.6  440.17    4724  438.73  4854.4  436.06  4945.3  436.37
  4973.5  436.42  4997.5  433.51  5000.2  433.01  5003.5  433.51  5005.7  434.61
    5015  435.53  5046.5  436.65  5077.9   440.3  5127.6  443.71    5167  445.32
  5214.3  449.55  5277.3  450.59  5360.5  450.14  5382.2  451.19  5440.9  450.39
#Mann= 7 ,-1 , 0
  4292.2      .1       0    4358     .16       0    4724      .1       0
  4945.3     .16       0  4997.5     .07       0  5003.5     .16       0
  5127.6     .05       0
Bank Sta=4973.5,5015
XS Rating Curve= 0 ,0
Exp/Cntr=0.3,0.1

Type RM Length L Ch R = 1 ,2155    ,1946,1946,1946
BEGIN DESCRIPTION:
UNT0139 IN SAND CR 1.0
END DESCRIPTION:
XS GIS Cut Line= 2
       3558942.1     10565341.64      3558146.92     10564576.81
#Sta/Elev= 30
  4476.4  447.11  4716.8  442.49  4766.5  439.52  4801.7  438.07    4830   435.8
  4879.4  433.34  4943.2  433.68  4950.1  434.13  4985.7  433.59  4989.6  431.26
  4992.3  430.76  4995.6  431.26  4999.8  431.27    5014  434.03  5056.4     434
  5119.9  436.73  5159.1  439.16  5176.5  439.77  5183.8   440.7  5204.8  441.64
  5240.1  442.38  5247.3  443.22  5275.6  444.75  5360.5  447.81  5367.4  447.56
  5388.8   448.3  5395.7  448.02  5466.5   449.1  5473.7  449.59  5579.7  449.47
#Mann= 4 ,-1 , 0
  4476.4     .16       0  4989.6     .07       0  4995.6     .16       0
  5159.1     .05       0
Bank Sta=4985.7,5014
XS Rating Curve= 0 ,0
Exp/Cntr=0.3,0.1

Type RM Length L Ch R = 1 ,209     ,0,0,0
BEGIN DESCRIPTION:
UNT0139 IN SAND CR 1.1
END DESCRIPTION:
XS GIS Cut Line= 4
      3559126.19      10565222.3      3559039.39     10564150.24
      3558640.08     10564011.35      3558202.47      10564427.3
#Sta/Elev= 30
  3599.3  443.66  3780.6  439.15    3911  439.19  4031.4  436.62  4111.6  437.14
  4207.2  433.08  4212.3  432.04  4262.1  431.85  4320.1  435.06  4342.4  435.15
  4372.5  433.08  4482.8  432.06  4674.9  431.95  4724.9   430.7    4902  431.16
    4979   430.1  4997.2  425.75    5000  425.25  5003.2  425.75  5010.8  429.07
  5018.4  430.52  5023.7  431.34  5052.7  430.59  5152.9  430.78  5209.5  429.29
    5252  430.12    5436  437.04  5506.8  438.31  5556.2  441.79  5701.4  445.74
#Mann= 6 ,-1 , 0
  3599.3     .16       0  4320.1     .05       0    4902     .16       0
  4997.2     .07       0  5003.2     .16       0  5052.7     .05       0
Bank Sta=4979,5018.4
XS Rating Curve= 0 ,0
Exp/Cntr=0.3,0.1

Chan Stop Cuts=-1
Use User Specified Reach Order=0
Composite Channel Slope=5