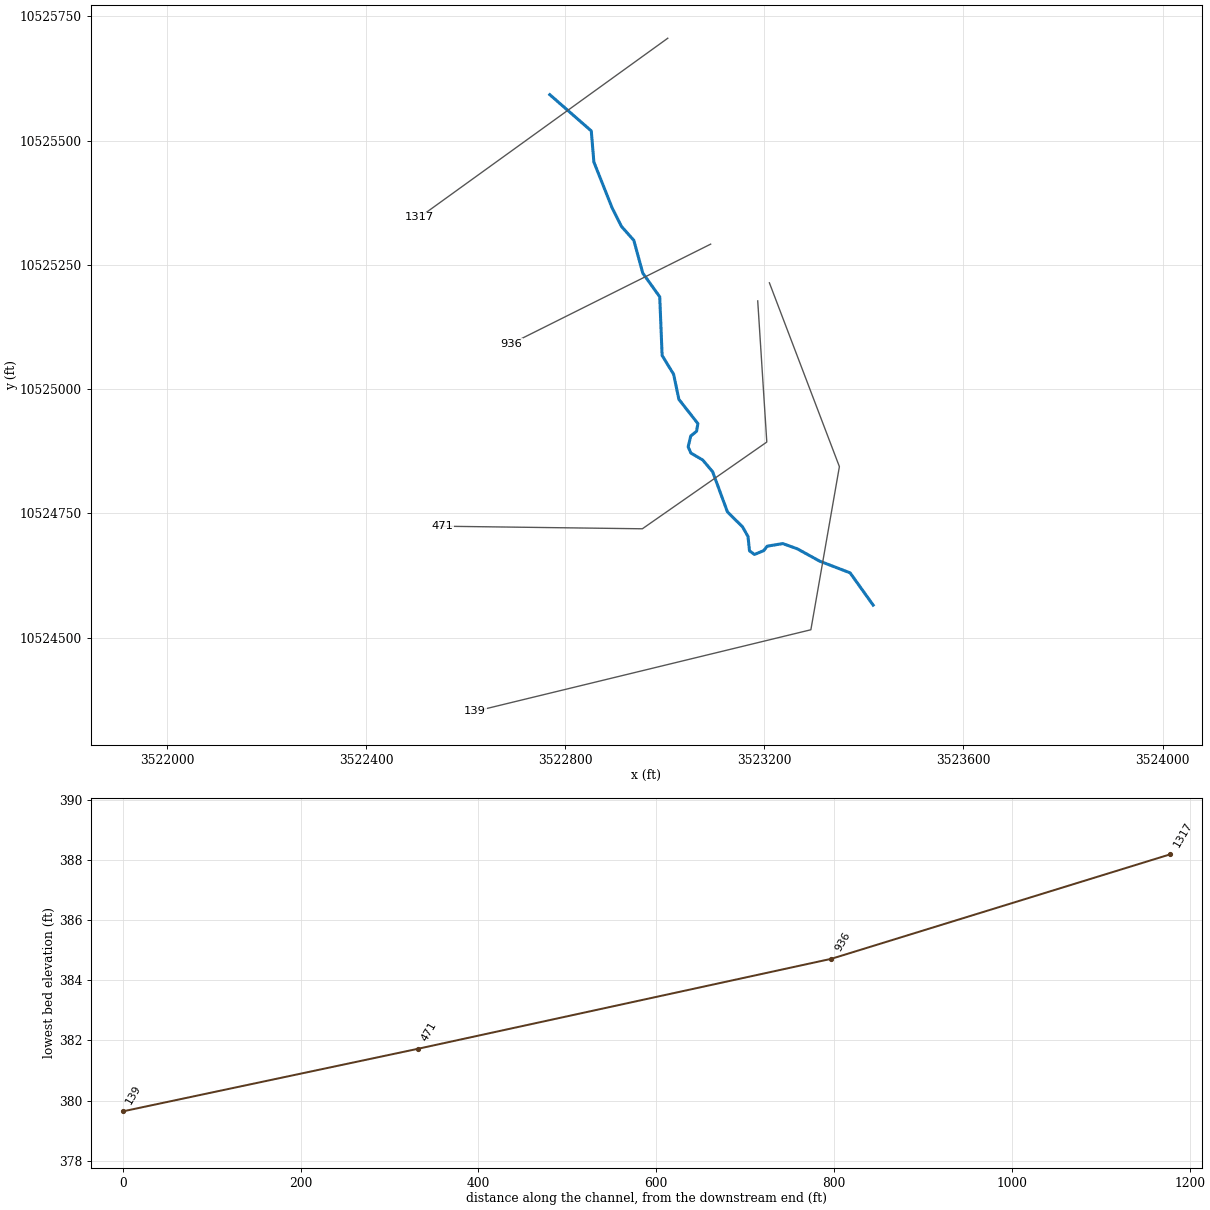
--- UNT01393 IN SAND CR.prj (project) ---

Proj Title=UNT01393 IN SAND CR Base Level Engineering
Current Plan=p01
Default Exp/Contr=0.3,0.1
English Units
Geom File=g01
Flow File=f01
Plan File=p01
BEGIN DESCRIPTION:
UNT01393 IN SAND CR
END DESCRIPTION:

--- UNT01393 IN SAND CR.p01 (plan) ---

Plan Title=Multiple Run
Short Identifier=Multiple
Geom File=g01
Flow File=f01
Subcritical Flow
K Sum by GR= 0
Std Step Tol= 0.01
Critical Tol= 0.01
Num of Std Step Trials= 20
Max Error Tol= 0.3
Flow Tol Ratio= 0.001
Split Flow NTrial= 30
Split Flow Tol= 0.02
Split Flow Ratio= 0.02
Log Output Level= 0
Friction Slope Method= 1
Unsteady Friction Slope Method= 2
Unsteady Bridges Friction Slope Method= 1
Parabolic Critical Depth
Global Vel Dist=  1 , 1 , 1
Global Log Level= 0
CheckData=True
Encroach Param= -1, 0, 0, 0
BEGIN DESCRIPTION:
Multiple Run
END DESCRIPTION:

--- UNT01393 IN SAND CR.f01 (steady flow) ---

Flow Title=Multiple
Number of Profiles=7
Profile Names=10-year,25-year,50-year,1pct_min,100-year,1pct_plu,500-year
River Rch & RM= UNT01393 IN SAND,Reach-1,1317
     332     429     505     436     590     798     800
Boundary for River Rch & Prof#=UNT01393 IN SAND,Reach-1,1
Up Type=0
Dn Type=3
Dn Slope=0.005
Boundary for River Rch & Prof#=UNT01393 IN SAND,Reach-1,2
Up Type=0
Dn Type=3
Dn Slope=0.005
Boundary for River Rch & Prof#=UNT01393 IN SAND,Reach-1,3
Up Type=0
Dn Type=3
Dn Slope=0.005
Boundary for River Rch & Prof#=UNT01393 IN SAND,Reach-1,4
Up Type=0
Dn Type=3
Dn Slope=0.005
Boundary for River Rch & Prof#=UNT01393 IN SAND,Reach-1,5
Up Type=0
Dn Type=3
Dn Slope=0.005
Boundary for River Rch & Prof#=UNT01393 IN SAND,Reach-1,6
Up Type=0
Dn Type=3
Dn Slope=0.005
Boundary for River Rch & Prof#=UNT01393 IN SAND,Reach-1,7
Up Type=0
Dn Type=3
Dn Slope=0.005

--- UNT01393 IN SAND CR.g01 (geometry) ---

Geom Title=Existing Conditions

River Reach=UNT01393 IN SAND,Reach-1
Reach XY= 30
      3522768.90     10525592.31      3522852.24     10525519.39
      3522857.45     10525456.89      3522894.11     10525364.55
      3522912.85     10525327.31      3522937.74     10525299.22
      3522955.78     10525233.20      3522989.79     10525185.68
      3522994.56     10525067.66      3523017.68     10525029.80
      3523028.27     10524979.37      3523066.46     10524930.59
      3523063.77     10524915.20      3523052.09     10524905.78
      3523046.88     10524883.90      3523052.43     10524871.40
      3523076.05     10524857.46      3523096.02     10524833.90
      3523125.72     10524753.18      3523156.30     10524722.69
      3523167.05     10524703.64      3523170.14     10524674.70
      3523180.04     10524667.41      3523198.79     10524675.22
      3523205.56     10524684.08      3523236.81     10524689.29
      3523265.98     10524678.87      3523311.29     10524653.87
      3523372.23     10524630.43      3523418.53     10524565.52

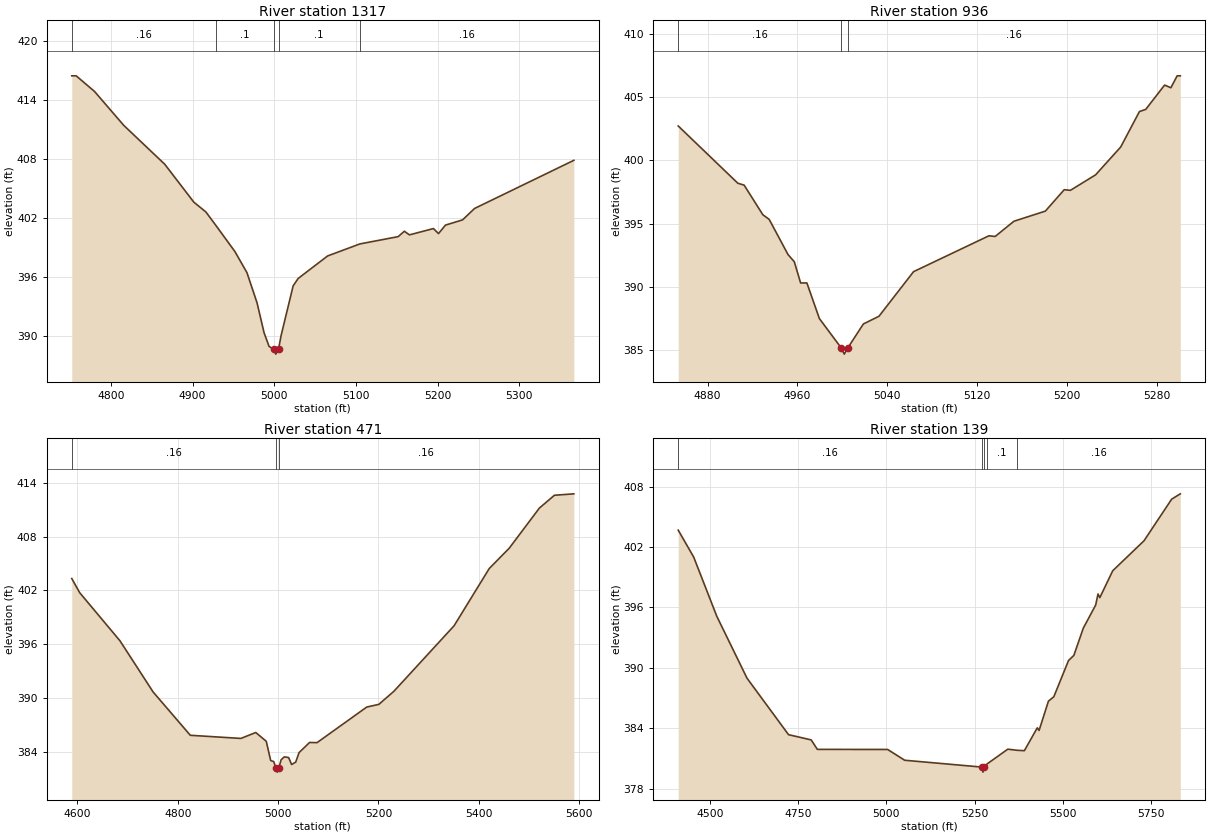
Type RM Length L Ch R = 1,1317,381,381,381
BEGIN DESCRIPTION:
UNT01393 IN SAND CR 2.1
END DESCRIPTION:
XS GIS Cut Line= 2
      3523005.91     10525705.79      3522507.83     10525346.06
#Sta/Elev= 30
  4752.2  416.44  4757.6  416.44  4780.1  414.85  4815.7  411.42  4866.0  407.46
  4901.6  403.61  4916.3  402.62  4928.3  401.28  4951.9  398.59  4966.6  396.45
  4978.9  393.40  4987.5  390.36  4993.6  388.97  4999.2  388.68  5001.9  388.18
  5005.2  388.68  5008.4  390.08  5023.1  395.11  5029.2  395.86  5065.3  398.15
  5104.8  399.37  5151.6  400.11  5159.2  400.66  5165.4  400.29  5194.8  400.93
  5201.0  400.42  5209.5  401.28  5230.4  401.81  5245.1  402.97  5366.6  407.86
#Mann=5,-1,0
  4752.2    0.16       0  4928.3     0.1       0  4999.2    0.07       0
  5005.2     0.1       0  5104.8    0.16       0
Bank Sta=4999.2,5005.2
Exp/Cntr=0.3,0.1

Type RM Length L Ch R = 1,936,465,465,465
BEGIN DESCRIPTION:
UNT01393 IN SAND CR 2.0
END DESCRIPTION:
XS GIS Cut Line= 3
      3523092.07     10525291.63      3522992.11     10525241.64
      3522692.08     10525091.63
#Sta/Elev= 30
  4853.8  402.72  4906.9  398.20  4912.5  398.05  4929.2  395.71  4934.8  395.35
  4951.6  392.57  4957.2  392.00  4962.8  390.33  4968.4  390.33  4979.5  387.52
  4998.9  385.21  5001.7  384.71  5004.9  385.21  5018.7  387.09  5032.6  387.70
  5063.4  391.22  5130.5  394.05  5136.1  394.00  5152.8  395.20  5180.8  396.00
  5197.6  397.69  5203.1  397.64  5225.5  398.86  5247.9  401.06  5264.6  403.86
  5270.2  404.03  5287.0  405.95  5292.6  405.74  5298.2  406.68  5301.0  406.68
#Mann=3,-1,0
  4853.8    0.16       0  4998.9    0.07       0  5004.9    0.16       0
Bank Sta=4998.9,5004.9
Exp/Cntr=0.3,0.1

Type RM Length L Ch R = 1,471,332,332,332
BEGIN DESCRIPTION:
UNT01393 IN SAND CR 1.0
END DESCRIPTION:
XS GIS Cut Line= 5
      3523186.64     10525177.45      3523204.87     10524893.55
      3522954.87     10524719.07      3522548.62     10524724.28
      3522553.79     10524724.28
#Sta/Elev= 30
  4588.6  403.32  4604.4  401.74  4684.6  396.38  4750.8  390.66  4824.9  385.83
  4925.7  385.48  4955.4  386.14  4976.3  385.16  4985.1  383.01  4991.1  382.90
  4995.4  382.22  4998.2  381.72  5001.4  382.22  5006.0  383.10  5012.1  383.42
  5020.8  383.35  5026.9  382.57  5035.0  382.84  5041.7  383.90  5062.7  385.03
  5077.5  385.01  5176.6  388.98  5200.7  389.28  5230.7  390.74  5350.7  398.05
  5420.7  404.43  5460.7  406.71  5520.7  411.18  5550.7  412.61  5589.4  412.77
#Mann=3,-1,0
  4588.6    0.16       0  4995.4    0.07       0  5001.4    0.16       0
Bank Sta=4995.4,5001.4
Exp/Cntr=0.3,0.1

Type RM Length L Ch R = 1,139,0,0,0
BEGIN DESCRIPTION:
UNT01393 IN SAND CR 1.1
END DESCRIPTION:
XS GIS Cut Line= 4
      3523210.09     10525213.85      3523350.70     10524844.07
      3523293.41     10524515.95      3522618.98     10524351.90
#Sta/Elev= 30
  4410.4  403.67  4454.2  401.00  4519.8  395.11  4605.3  388.97  4723.0  383.36
  4787.2  382.84  4804.6  381.90  5003.9  381.89  5052.1  380.82  5271.2  380.14
  5274.0  379.64  5277.2  380.14  5285.9  380.46  5344.4  381.92  5370.5  381.81
  5391.3  381.77  5427.9  384.04  5433.0  383.78  5459.5  386.69  5474.8  387.13
  5516.5  390.73  5531.5  391.23  5558.3  393.94  5593.3  396.23  5600.0  397.33
  5605.1  396.97  5641.7  399.64  5730.4  402.62  5808.7  406.75  5833.2  407.28
#Mann=5,-1,0
  4410.4    0.16       0  5271.2    0.07       0  5277.2    0.16       0
  5285.9     0.1       0  5370.5    0.16       0
Bank Sta=5271.2,5277.2
Exp/Cntr=0.3,0.1

Chan Stop Cuts=-1