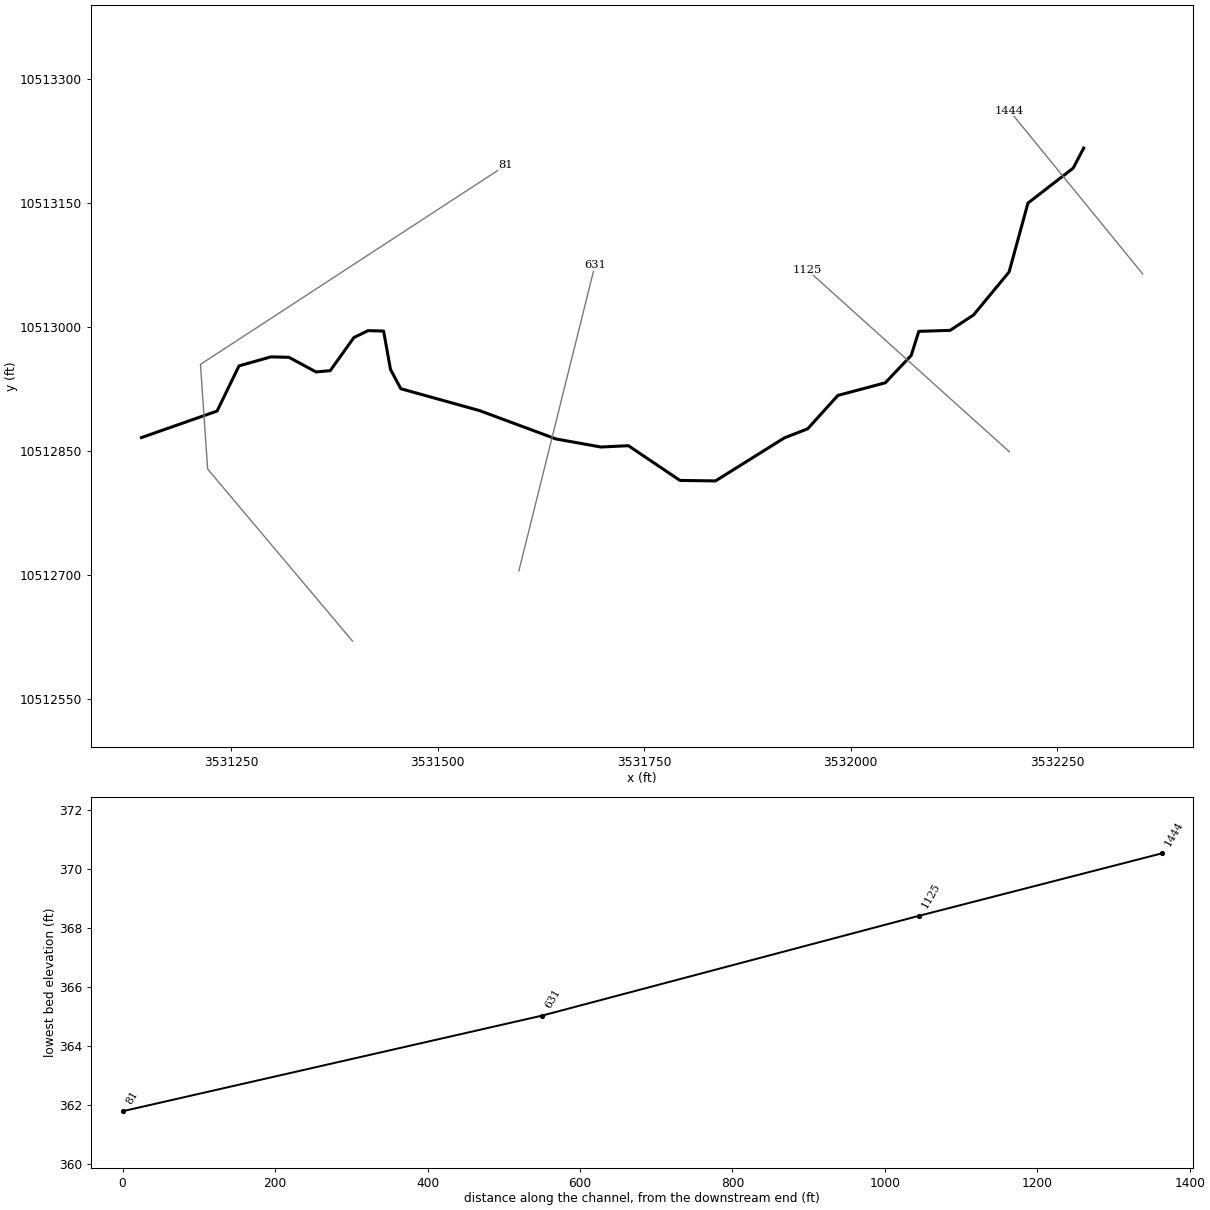
--- UNT01418 IN SAND CR.prj (project) ---

Proj Title=UNT01418 IN SAND CR Base Level Engineering
Current Plan=p01
Default Exp/Contr=0.3,0.1
English Units
Geom File=g01
Flow File=f01
Plan File=p01
BEGIN DESCRIPTION:
UNT01418 IN SAND CR
END DESCRIPTION:

--- UNT01418 IN SAND CR.p01 (plan) ---

Plan Title=Multiple Run
Short Identifier=Multiple
Geom File=g01
Flow File=f01
Subcritical Flow
K Sum by GR= 0
Std Step Tol= 0.01
Critical Tol= 0.01
Num of Std Step Trials= 20
Max Error Tol= 0.3
Flow Tol Ratio= 0.001
Split Flow NTrial= 30
Split Flow Tol= 0.02
Split Flow Ratio= 0.02
Log Output Level= 0
Friction Slope Method= 1
Unsteady Friction Slope Method= 2
Unsteady Bridges Friction Slope Method= 1
Parabolic Critical Depth
Global Vel Dist=  1 , 1 , 1
Global Log Level= 0
CheckData=True
Encroach Param= -1, 0, 0, 0
BEGIN DESCRIPTION:
Multiple Run
END DESCRIPTION:

--- UNT01418 IN SAND CR.f01 (steady flow) ---

Flow Title=Multiple
Number of Profiles=7
Profile Names=10-year,25-year,50-year,1pct_min,100-year,1pct_plu,500-year
River Rch & RM= UNT01418 IN SAND,Reach-1,1444
     223     278     318     268     363     491     468
Boundary for River Rch & Prof#=UNT01418 IN SAND,Reach-1,1
Up Type=0
Dn Type=3
Dn Slope=0.005
Boundary for River Rch & Prof#=UNT01418 IN SAND,Reach-1,2
Up Type=0
Dn Type=3
Dn Slope=0.005
Boundary for River Rch & Prof#=UNT01418 IN SAND,Reach-1,3
Up Type=0
Dn Type=3
Dn Slope=0.005
Boundary for River Rch & Prof#=UNT01418 IN SAND,Reach-1,4
Up Type=0
Dn Type=3
Dn Slope=0.005
Boundary for River Rch & Prof#=UNT01418 IN SAND,Reach-1,5
Up Type=0
Dn Type=3
Dn Slope=0.005
Boundary for River Rch & Prof#=UNT01418 IN SAND,Reach-1,6
Up Type=0
Dn Type=3
Dn Slope=0.005
Boundary for River Rch & Prof#=UNT01418 IN SAND,Reach-1,7
Up Type=0
Dn Type=3
Dn Slope=0.005

--- UNT01418 IN SAND CR.g01 (geometry) ---

Geom Title=Existing Conditions

River Reach=UNT01418 IN SAND,Reach-1
Reach XY= 30
      3532282.11     10513216.64      3532269.32     10513192.37
      3532214.66     10513150.11      3532191.83     10513066.67
      3532148.76     10513014.62      3532120.43     10512995.99
      3532082.55     10512994.79      3532073.36     10512965.66
      3532042.01     10512932.51      3531984.52     10512917.17
      3531947.98     10512876.73      3531919.87     10512865.81
      3531836.43     10512813.66      3531793.47     10512814.26
      3531731.01     10512856.34      3531697.73     10512854.73
      3531643.36     10512864.49      3531550.93     10512898.80
      3531455.53     10512925.33      3531443.03     10512948.77
      3531434.70     10512995.13      3531415.95     10512995.65
      3531398.76     10512987.31      3531370.11     10512947.21
      3531352.92     10512945.65      3531320.11     10512963.36
      3531298.24     10512963.88      3531259.70     10512952.94
      3531233.13     10512898.25      3531141.64     10512866.18

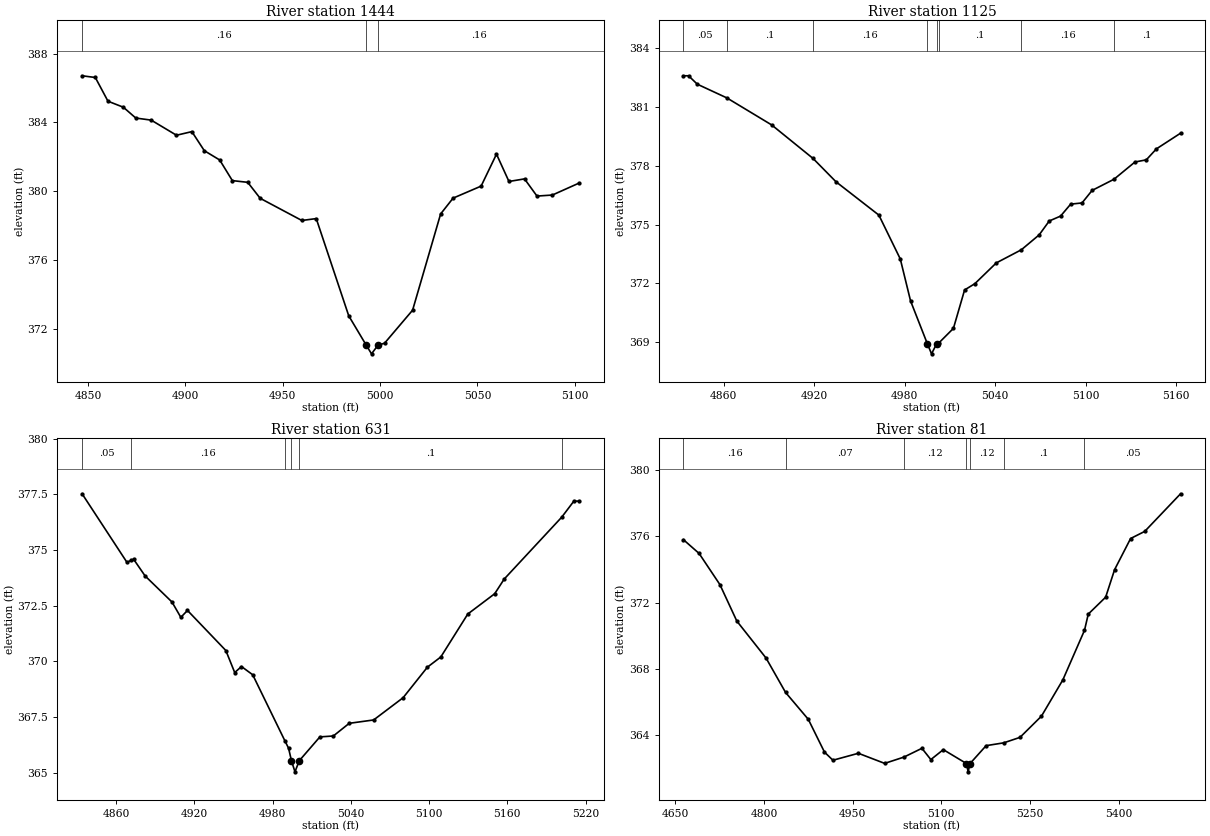
Type RM Length L Ch R = 1,1444,319,319,319
BEGIN DESCRIPTION:
UNT01418 IN SAND CR 2.1
END DESCRIPTION:
XS GIS Cut Line= 2
      3532353.69     10513064.14      3532192.24     10513262.04
#Sta/Elev= 30
  4846.9  386.71  4853.7  386.61  4860.2  385.23  4868.1  384.88  4874.5  384.25
  4882.4  384.13  4895.4  383.25  4903.3  383.46  4909.7  382.35  4917.6  381.81
  4924.1  380.61  4932.0  380.51  4938.4  379.58  4959.8  378.29  4967.2  378.40
  4983.9  372.74  4992.9  371.03  4995.6  370.53  4998.9  371.03  5002.3  371.15
  5016.7  373.07  5031.1  378.67  5037.5  379.59  5051.9  380.29  5059.8  382.15
  5066.2  380.56  5074.2  380.71  5080.6  379.71  5088.5  379.77  5102.3  380.47
#Mann=3,-1,0
  4846.9    0.16       0  4992.9    0.07       0  4998.9    0.16       0
Bank Sta=4992.9,4998.9
Exp/Cntr=0.3,0.1

Type RM Length L Ch R = 1,1125,494,494,494
BEGIN DESCRIPTION:
UNT01418 IN SAND CR 2.0
END DESCRIPTION:
XS GIS Cut Line= 2
      3532192.18     10512848.91      3531947.43     10513069.36
#Sta/Elev= 30
  4833.4  382.60  4836.8  382.60  4842.6  382.17  4862.2  381.47  4891.9  380.09
  4919.3  378.38  4934.5  377.19  4962.9  375.49  4977.1  373.25  4983.9  371.11
  4995.1  368.91  4997.8  368.41  5001.1  368.91  5002.7  368.97  5012.3  369.71
  5019.7  371.67  5026.5  371.99  5040.7  373.05  5057.3  373.72  5069.1  374.48
  5075.8  375.19  5083.3  375.44  5090.0  376.05  5097.5  376.11  5104.2  376.75
  5118.7  377.32  5132.6  378.20  5140.1  378.31  5146.8  378.87  5162.8  379.67
#Mann=8,-1,0
  4833.4    0.05       0  4862.2     0.1       0  4919.3    0.16       0
  4995.1    0.07       0  5001.1    0.16       0  5002.7     0.1       0
  5057.3    0.16       0  5118.7     0.1       0
Bank Sta=4995.1,5001.1
Exp/Cntr=0.3,0.1

Type RM Length L Ch R = 1,631,550,550,550
BEGIN DESCRIPTION:
UNT01418 IN SAND CR 1.0
END DESCRIPTION:
XS GIS Cut Line= 2
      3531598.45     10512704.74      3531690.47     10513074.56
#Sta/Elev= 30
  4834.0  377.52  4868.4  374.44  4871.6  374.53  4873.5  374.58  4882.3  373.83
  4902.9  372.66  4909.7  371.97  4914.8  372.28  4944.2  370.48  4951.0  369.49
  4956.2  369.76  4964.8  369.39  4989.5  366.42  4992.3  366.09  4994.5  365.53
  4997.2  365.03  5000.5  365.53  5016.3  366.60  5026.6  366.64  5038.8  367.21
  5057.5  367.36  5080.1  368.36  5098.7  369.73  5109.0  370.19  5129.7  372.12
  5150.3  373.03  5157.6  373.69  5201.7  376.47  5211.0  377.19  5215.1  377.19
#Mann=6,-1,0
  4834.0    0.05       0  4871.6    0.16       0  4989.5     0.1       0
  4994.5    0.07       0  5000.5     0.1       0  5201.7    0.05       0
Bank Sta=4994.5,5000.5
Exp/Cntr=0.3,0.1

Type RM Length L Ch R = 1,81,0,0,0
BEGIN DESCRIPTION:
UNT01418 IN SAND CR 1.1
END DESCRIPTION:
XS GIS Cut Line= 4
      3531397.04     10512619.75      3531221.73     10512828.05
      3531213.04     10512954.78      3531582.87     10513196.13
#Sta/Elev= 30
  4663.7  375.80  4690.2  374.97  4725.4  373.09  4754.0  370.89  4803.4  368.66
  4836.5  366.58  4874.9  364.96  4902.3  362.98  4916.6  362.49  4959.6  362.91
  5004.1  362.30  5036.7  362.68  5067.1  363.21  5082.2  362.53  5103.3  363.13
  5142.5  362.29  5145.3  361.79  5148.5  362.29  5175.7  363.37  5205.5  363.54
  5233.0  363.87  5269.3  365.15  5305.5  367.34  5342.1  370.33  5348.5  371.31
  5377.9  372.33  5393.0  373.99  5420.1  375.87  5444.0  376.30  5504.6  378.57
#Mann=7,-1,0
  4663.7    0.16       0  4836.5    0.07       0  5036.7    0.12       0
  5142.5    0.07       0  5148.5    0.12       0  5205.5     0.1       0
  5342.1    0.05       0
Bank Sta=5142.5,5148.5
Exp/Cntr=0.3,0.1

Chan Stop Cuts=-1