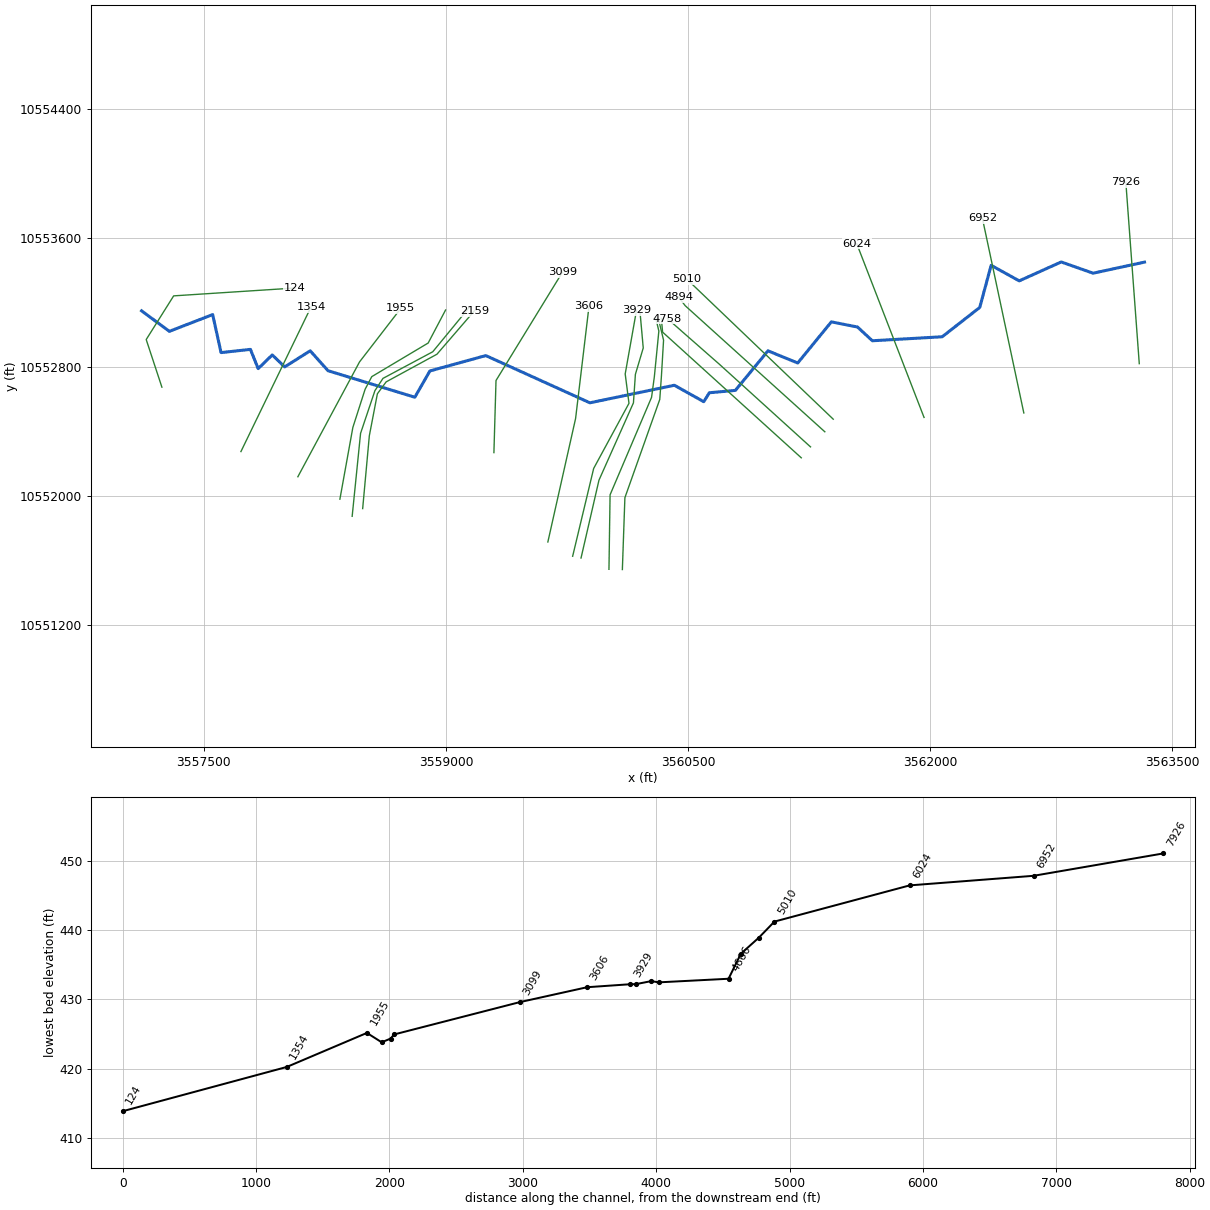
--- UNT0142 IN SAND CR.prj (project) ---

Proj Title=UNT0142 IN SAND CR Base Level Engineering
Current Plan=p01
Default Exp/Contr=0.3,0.1
English Units
Geom File=g01
Flow File=f01
Plan File=p01
BEGIN DESCRIPTION:
UNT0142 IN SAND CR
END DESCRIPTION:

--- UNT0142 IN SAND CR.p01 (plan) ---

Plan Title=Multiple Run
Short Identifier=Multiple
Geom File=g01
Flow File=f01
Subcritical Flow
K Sum by GR= 0
Std Step Tol= 0.01
Critical Tol= 0.01
Num of Std Step Trials= 20
Max Error Tol= 0.3
Flow Tol Ratio= 0.001
Split Flow NTrial= 30
Split Flow Tol= 0.02
Split Flow Ratio= 0.02
Log Output Level= 0
Friction Slope Method= 1
Unsteady Friction Slope Method= 2
Unsteady Bridges Friction Slope Method= 1
Parabolic Critical Depth
Global Vel Dist=  1 , 1 , 1
Global Log Level= 0
CheckData=True
Encroach Param= -1, 0, 0, 0
BEGIN DESCRIPTION:
Multiple Run
END DESCRIPTION:

--- UNT0142 IN SAND CR.f01 (steady flow) ---

Flow Title=Multiple
Number of Profiles=7
Profile Names=10-year,25-year,50-year,1pct_min,100-year,1pct_plu,500-year
River Rch & RM= UNT0142 IN SAND ,Reach-1,7926
    1123    1547    1898    1697    2296    3105    3349
River Rch & RM= UNT0142 IN SAND ,Reach-1,3971
    1247    1729    2130    1913    2587    3499    3805
Boundary for River Rch & Prof#=UNT0142 IN SAND ,Reach-1,1
Up Type=0
Dn Type=3
Dn Slope=0.005
Boundary for River Rch & Prof#=UNT0142 IN SAND ,Reach-1,2
Up Type=0
Dn Type=3
Dn Slope=0.005
Boundary for River Rch & Prof#=UNT0142 IN SAND ,Reach-1,3
Up Type=0
Dn Type=3
Dn Slope=0.005
Boundary for River Rch & Prof#=UNT0142 IN SAND ,Reach-1,4
Up Type=0
Dn Type=3
Dn Slope=0.005
Boundary for River Rch & Prof#=UNT0142 IN SAND ,Reach-1,5
Up Type=0
Dn Type=3
Dn Slope=0.005
Boundary for River Rch & Prof#=UNT0142 IN SAND ,Reach-1,6
Up Type=0
Dn Type=3
Dn Slope=0.005
Boundary for River Rch & Prof#=UNT0142 IN SAND ,Reach-1,7
Up Type=0
Dn Type=3
Dn Slope=0.005

--- UNT0142 IN SAND CR.g01 (geometry) ---

Geom Title=Existing Conditions

River Reach=UNT0142 IN SAND ,Reach-1
Reach XY= 30
      3563327.88     10553450.00      3563009.37     10553381.38
      3562811.79     10553451.00      3562551.90     10553333.80
      3562377.73     10553430.10      3562307.15     10553168.98
      3562074.57     10552987.24      3561641.90     10552962.55
      3561549.96     10553047.66      3561387.93     10553079.71
      3561179.61     10552824.62      3560995.23     10552900.14
      3560793.24     10552654.83      3560632.13     10552640.24
      3560597.40     10552584.69      3560415.46     10552686.77
      3559892.07     10552577.90      3559247.24     10552870.63
      3558900.86     10552775.31      3558807.58     10552612.42
      3558269.85     10552776.84      3558159.44     10552900.28
      3558001.10     10552800.28      3557924.54     10552874.76
      3557837.04     10552789.86      3557789.12     10552909.13
      3557607.11     10552889.14      3557555.16     10553124.77
      3557287.00     10553020.97      3557114.70     10553148.04

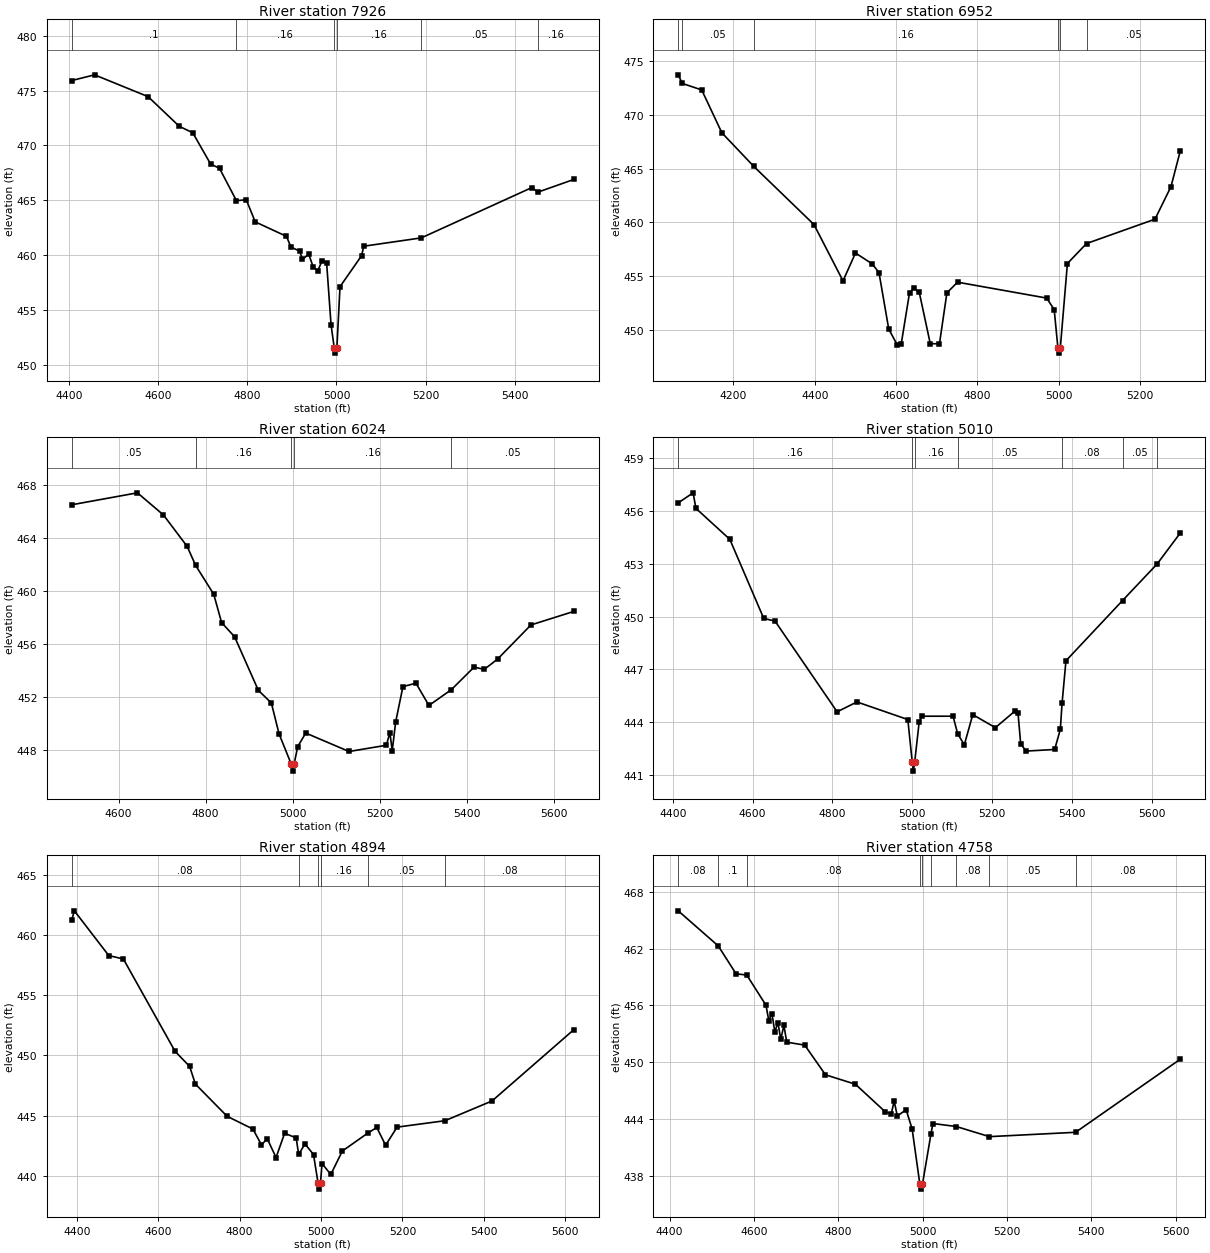
Type RM Length L Ch R = 1,7926,974,974,974
BEGIN DESCRIPTION:
UNT0142 IN SAND CR 15.0
END DESCRIPTION:
XS GIS Cut Line= 2
      3563295.44     10552820.59      3563212.11     10553945.61
#Sta/Elev= 30
  4405.2  475.91  4456.4  476.43  4576.7  474.44  4646.9  471.73  4677.0  471.15
  4717.1  468.30  4737.2  467.90  4775.2  464.95  4797.3  465.04  4817.4  463.02
  4887.6  461.70  4897.6  460.73  4917.6  460.34  4923.4  459.60  4937.7  460.08
  4947.7  458.89  4957.8  458.56  4967.8  459.47  4977.8  459.30  4987.8  453.62
  4994.9  451.55  4997.6  451.05  5000.9  451.55  5007.9  457.11  5056.3  459.93
  5061.3  460.80  5190.6  461.56  5439.1  466.15  5452.5  465.73  5533.3  466.89
#Mann=6,-1,0
  4405.2     0.1       0  4775.2    0.16       0  4994.9    0.07       0
  5000.9    0.16       0  5190.6    0.05       0  5452.5    0.16       0
Bank Sta=4994.9,5000.9
Exp/Cntr=0.3,0.1

Type RM Length L Ch R = 1,6952,928,928,928
BEGIN DESCRIPTION:
UNT0142 IN SAND CR 13.0
END DESCRIPTION:
XS GIS Cut Line= 2
      3562580.16     10552515.06      3562323.23     10553723.34
#Sta/Elev= 30
  4064.2  473.75  4074.1  472.95  4122.0  472.34  4171.5  468.35  4250.3  465.21
  4398.1  459.80  4469.6  454.55  4500.3  457.15  4541.2  456.14  4558.1  455.33
  4582.1  450.06  4602.6  448.62  4612.8  448.67  4633.2  453.43  4643.5  453.88
  4657.3  453.47  4684.3  448.70  4706.9  448.69  4725.2  453.43  4751.4  454.43
  4970.6  452.95  4989.2  451.88  4998.3  448.32  5001.0  447.82  5004.3  448.32
  5021.7  456.17  5068.7  458.03  5237.2  460.30  5276.5  463.33  5299.5  466.67
#Mann=6,-1,0
  4064.2     0.1       0  4074.1    0.05       0  4250.3    0.16       0
  4998.3    0.07       0  5004.3    0.16       0  5068.7    0.05       0
Bank Sta=4998.3,5004.3
Exp/Cntr=0.3,0.1

Type RM Length L Ch R = 1,6024,1014,1014,1014
BEGIN DESCRIPTION:
UNT0142 IN SAND CR 11.0
END DESCRIPTION:
XS GIS Cut Line= 2
      3561962.12     10552487.23      3561545.46     10553563.60
#Sta/Elev= 30
  4492.5  466.52  4643.4  467.42  4703.3  465.75  4757.8  463.38  4777.2  461.95
  4818.9  459.77  4836.9  457.64  4866.8  456.57  4921.4  452.53  4951.3  451.58
  4969.0  449.25  4997.4  446.94  5000.2  446.44  5003.4  446.94  5011.9  448.29
  5030.4  449.31  5129.9  447.92  5215.7  448.39  5223.8  449.34  5229.2  447.98
  5237.1  450.15  5253.8  452.81  5283.7  453.07  5313.6  451.39  5365.4  452.59
  5417.3  454.28  5440.9  454.11  5471.8  454.90  5548.1  457.46  5646.7  458.48
#Mann=5,-1,0
  4492.5    0.05       0  4777.2    0.16       0  4997.4    0.07       0
  5003.4    0.16       0  5365.4    0.05       0
Bank Sta=4997.4,5003.4
Exp/Cntr=0.3,0.1

Type RM Length L Ch R = 1,5010,116,116,116
BEGIN DESCRIPTION:
UNT0142 IN SAND CR 9.1
END DESCRIPTION:
XS GIS Cut Line= 2
      3561399.48     10552476.47      3560491.43     10553345.67
#Sta/Elev= 30
  4413.8  456.46  4451.1  457.03  4458.0  456.15  4542.9  454.39  4627.8  449.90
  4656.2  449.74  4811.6  444.59  4861.2  445.15  4988.6  444.15  4999.7  441.72
  5002.5  441.22  5005.7  441.72  5016.9  443.99  5023.8  444.34  5101.8  444.34
  5113.3  443.35  5130.0  442.71  5151.2  444.43  5207.8  443.69  5257.2  444.64
  5264.4  444.53  5271.3  442.74  5285.5  442.36  5356.2  442.45  5370.4  443.59
  5374.8  445.09  5384.5  447.49  5526.1  450.91  5612.8  452.99  5670.8  454.75
#Mann=7,-1,0
  4413.8    0.16       0  4999.7    0.07       0  5005.7    0.16       0
  5113.3    0.05       0  5374.8    0.08       0  5526.1    0.05       0
  5612.8    0.08       0
Bank Sta=4999.7,5005.7
Exp/Cntr=0.3,0.1

Type RM Length L Ch R = 1,4894,136,136,136
BEGIN DESCRIPTION:
UNT0142 IN SAND CR 9.0
END DESCRIPTION:
XS GIS Cut Line= 3
      3561347.40     10552398.34      3560482.78     10553179.62
      3560441.35     10553233.52
#Sta/Elev= 30
  4387.7  461.24  4394.1  461.99  4478.6  458.28  4514.4  458.00  4641.5  450.34
  4677.3  449.09  4691.3  447.63  4769.2  444.96  4832.7  443.90  4853.7  442.59
  4867.9  443.10  4889.5  441.54  4910.5  443.55  4938.9  443.17  4945.0  441.80
  4960.5  442.67  4981.5  441.79  4992.7  439.42  4995.4  438.92  4998.7  439.42
  5002.4  441.04  5024.0  440.14  5052.4  442.08  5115.1  443.57  5136.9  444.03
  5158.6  442.56  5186.9  444.06  5304.3  444.59  5420.1  446.23  5621.0  452.14
#Mann=6,-1,0
  4387.7    0.08       0  4945.0    0.16       0  4992.7    0.07       0
  4998.7    0.16       0  5115.1    0.05       0  5304.3    0.08       0
Bank Sta=4992.7,4998.7
Exp/Cntr=0.3,0.1

Type RM Length L Ch R = 1,4758,92,92,92
BEGIN DESCRIPTION:
UNT0142 IN SAND CR 8.0
END DESCRIPTION:
XS GIS Cut Line= 3
      3561258.80     10552304.64      3560696.32     10552815.04
      3560372.23     10553099.72
#Sta/Elev= 30
  4420.5  466.01  4515.4  462.30  4557.6  459.35  4583.0  459.22  4628.6  456.03
  4635.3  454.41  4642.8  455.15  4649.5  453.22  4657.0  454.17  4663.7  452.43
  4671.2  453.89  4677.9  452.12  4720.5  451.81  4769.8  448.67  4840.8  447.67
  4911.7  444.75  4925.9  444.56  4932.7  445.89  4940.1  444.32  4961.1  444.97
  4975.3  442.94  4993.7  437.08  4996.4  436.58  4999.7  437.08  5020.1  442.45
  5024.6  443.52  5080.1  443.20  5158.6  442.13  5363.0  442.59  5611.4  450.32
#Mann=9,-1,0
  4420.5    0.08       0  4515.4     0.1       0  4583.0    0.08       0
  4993.7    0.07       0  4999.7    0.08       0  5020.1    0.05       0
  5080.1    0.08       0  5158.6    0.05       0  5363.0    0.08       0
Bank Sta=4993.7,4999.7
Exp/Cntr=0.3,0.1

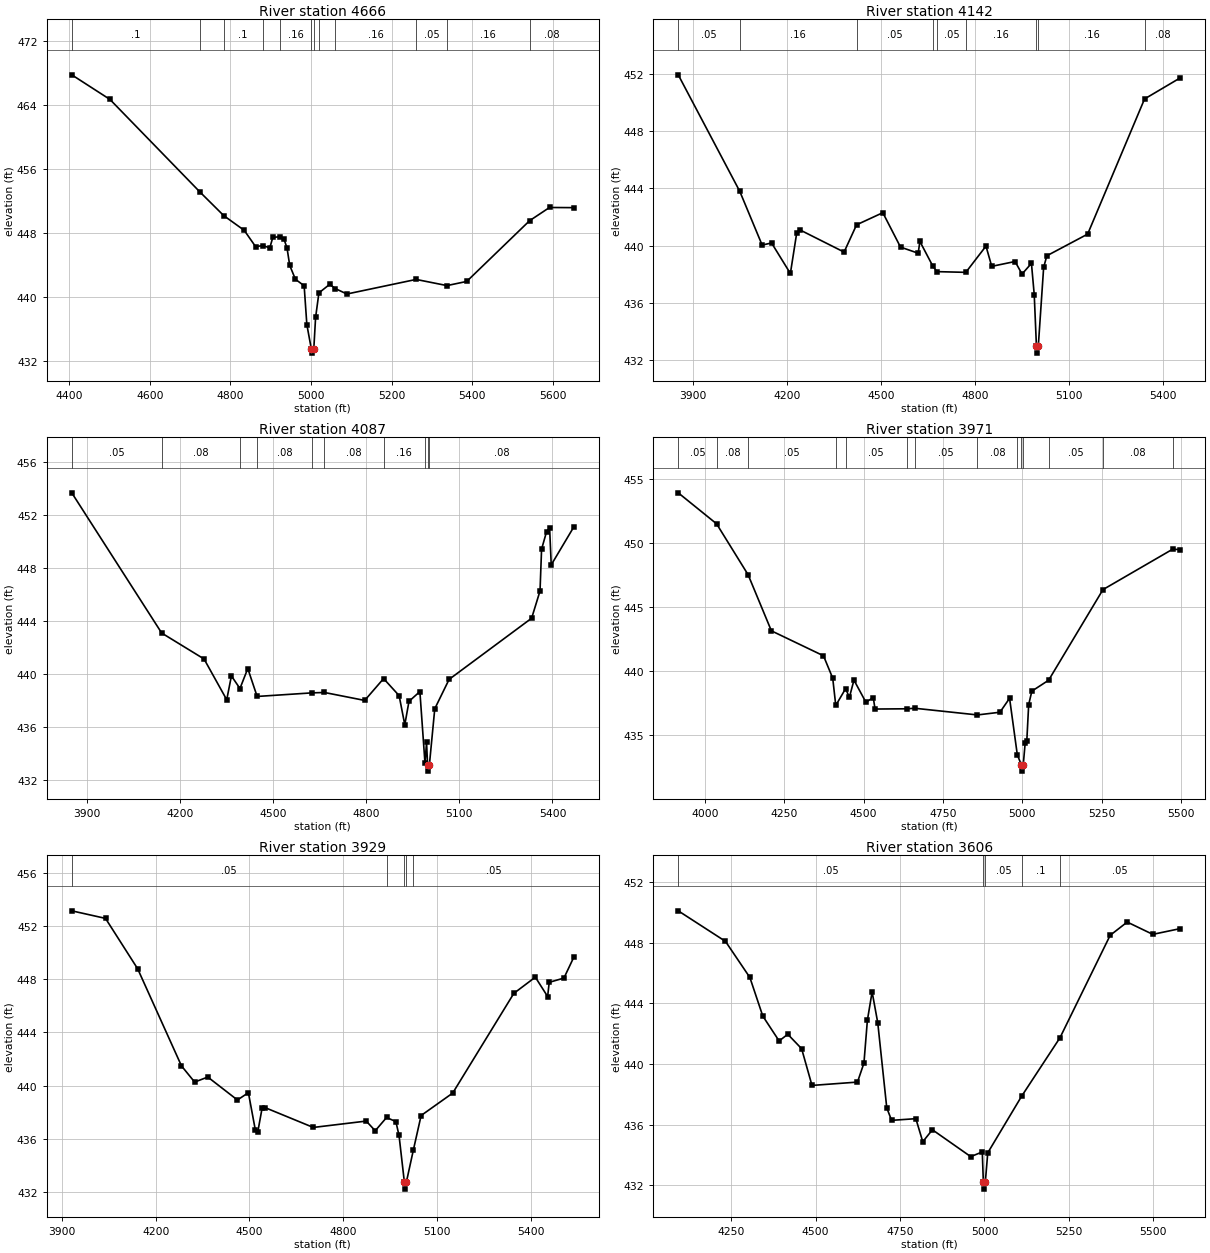
Type RM Length L Ch R = 1,4666,524,524,524
BEGIN DESCRIPTION:
UNT0142 IN SAND CR 7.0
END DESCRIPTION:
XS GIS Cut Line= 3
      3561201.56     10552236.89      3560342.53     10553016.12
      3560334.47     10553101.75
#Sta/Elev= 30
  4406.4  467.72  4501.1  464.65  4724.5  453.09  4783.6  450.14  4834.3  448.31
  4862.7  446.26  4879.7  446.41  4897.8  446.13  4905.2  447.42  4922.0  447.51
  4933.0  447.19  4940.4  446.14  4947.2  443.93  4961.3  442.20  4983.0  441.39
  4989.7  436.54  5000.9  433.48  5003.7  432.98  5006.9  433.48  5011.4  437.43
  5019.6  440.50  5046.5  441.57  5060.5  441.03  5089.1  440.36  5260.8  442.18
  5337.4  441.41  5386.4  441.93  5542.4  449.51  5591.8  451.16  5652.2  451.14
#Mann=12,-1,0
  4406.4     0.1       0  4724.5    0.08       0  4783.6     0.1       0
  4879.7    0.08       0  4922.0    0.16       0  5000.9    0.07       0
  5006.9    0.16       0  5019.6    0.05       0  5060.5    0.16       0
  5260.8    0.05       0  5337.4    0.16       0  5542.4    0.08       0
Bank Sta=5000.9,5006.9
Exp/Cntr=0.3,0.1

Type RM Length L Ch R = 1,4142,55,55,55
BEGIN DESCRIPTION:
UNT0142 IN SAND CR 6.2
END DESCRIPTION:
XS GIS Cut Line= 6
      3560093.24     10551544.35      3560108.86     10551989.67
      3560325.01     10552599.04      3560335.43     10552747.48
      3560348.45     10552966.23      3560315.64     10553102.84
#Sta/Elev= 30
  3854.0  451.96  4050.3  443.79  4121.5  440.03  4151.5  440.18  4211.5  438.04
  4231.5  440.85  4241.5  441.10  4382.7  439.54  4422.5  441.45  4506.2  442.30
  4562.6  439.89  4619.0  439.46  4624.3  440.29  4665.3  438.57  4678.7  438.17
  4770.8  438.12  4835.1  439.96  4853.4  438.54  4927.8  438.88  4950.0  438.00
  4980.0  438.75  4988.9  436.56  4995.9  432.96  4998.6  432.46  5001.9  432.96
  5018.9  438.46  5029.0  439.28  5159.2  440.80  5340.6  450.27  5454.6  451.75
#Mann=9,-1,0
  3854.0    0.05       0  4050.3    0.16       0  4422.5    0.05       0
  4665.3    0.08       0  4678.7    0.05       0  4770.8    0.16       0
  4995.9    0.07       0  5001.9    0.16       0  5340.6    0.08       0
Bank Sta=4995.9,5001.9
Exp/Cntr=0.3,0.1

Type RM Length L Ch R = 1,4087,116,116,116
BEGIN DESCRIPTION:
UNT0142 IN SAND CR 6.1
END DESCRIPTION:
XS GIS Cut Line= 6
      3560010.18     10551545.79      3560017.12     10552007.57
      3560274.07     10552611.74      3560291.43     10552740.21
      3560319.28     10553022.55      3560299.74     10553105.05
#Sta/Elev= 30
  3852.4  453.66  4141.9  443.07  4278.3  441.11  4351.3  438.03  4366.4  439.83
  4393.9  438.88  4419.1  440.39  4449.2  438.28  4625.2  438.55  4666.0  438.58
  4795.5  437.98  4856.4  439.63  4906.4  438.34  4924.6  436.14  4938.1  437.91
  4973.2  438.65  4989.6  433.25  4994.7  434.81  4997.9  433.14  5000.7  432.64
  5003.9  433.14  5021.1  437.35  5067.3  439.57  5333.0  444.19  5360.0  446.25
  5365.0  449.40  5381.1  450.73  5390.9  451.00  5396.1  448.22  5468.9  451.09
#Mann=10,-1,0
  3852.4    0.05       0  4141.9    0.08       0  4393.9    0.16       0
  4449.2    0.08       0  4625.2    0.05       0  4666.0    0.08       0
  4856.4    0.16       0  4989.6    0.08       0  4997.9    0.07       0
  5003.9    0.08       0
Bank Sta=4997.9,5003.9
Exp/Cntr=0.3,0.1

Type RM Length L Ch R = 1,3971,42,42,42
BEGIN DESCRIPTION:
UNT0142 IN SAND CR 6.0
END DESCRIPTION:
XS GIS Cut Line= 6
      3559837.14     10551615.61      3559948.26     10552098.28
      3560161.80     10552577.45      3560173.95     10552754.53
      3560222.56     10552917.73      3560203.46     10553131.30
#Sta/Elev= 30
  3916.2  453.94  4037.0  451.52  4136.4  447.54  4209.7  443.16  4373.9  441.21
  4403.0  439.46  4412.6  437.33  4443.5  438.64  4455.6  437.97  4469.9  439.31
  4507.6  437.58  4530.8  437.95  4536.3  437.05  4635.8  437.07  4662.1  437.11
  4859.0  436.59  4929.9  436.80  4960.3  437.89  4984.7  433.47  4997.4  432.70
  5000.2  432.20  5003.4  432.70  5009.5  434.42  5014.5  434.52  5020.5  437.40
  5030.5  438.45  5083.3  439.30  5254.6  446.38  5473.7  449.53  5498.3  449.51
#Mann=14,-1,0
  3916.2    0.05       0  4037.0    0.08       0  4136.4    0.05       0
  4412.6    0.08       0  4443.5    0.05       0  4635.8    0.08       0
  4662.1    0.05       0  4859.0    0.08       0  4984.7    0.16       0
  4997.4    0.07       0  5003.4    0.16       0  5083.3    0.05       0
  5254.6    0.08       0  5473.7    0.05       0
Bank Sta=4997.4,5003.4
Exp/Cntr=0.3,0.1

Type RM Length L Ch R = 1,3929,323,323,323
BEGIN DESCRIPTION:
UNT0142 IN SAND CR 6.3
END DESCRIPTION:
XS GIS Cut Line= 5
      3559785.24     10551626.79      3559915.46     10552171.09
      3560134.21     10552574.74      3560110.77     10552757.03
      3560181.09     10553152.87
#Sta/Elev= 30
  3932.0  453.17  4039.8  452.60  4142.6  448.80  4282.6  441.48  4324.7  440.26
  4366.7  440.64  4461.4  438.91  4496.5  439.46  4518.4  436.68  4526.4  436.49
  4540.3  438.30  4549.2  438.34  4703.9  436.84  4873.1  437.32  4901.8  436.59
  4938.1  437.59  4967.8  437.28  4977.9  436.24  4995.1  432.69  4997.8  432.19
  5001.1  432.69  5024.0  435.17  5048.5  437.74  5149.4  439.43  5344.9  446.95
  5413.5  448.17  5452.8  446.71  5457.9  447.78  5504.9  448.10  5536.6  449.68
#Mann=5,-1,0
  3932.0    0.05       0  4938.1    0.08       0  4995.1    0.07       0
  5001.1    0.08       0  5024.0    0.05       0
Bank Sta=4995.1,5001.1
Exp/Cntr=0.3,0.1

Type RM Length L Ch R = 1,3606,507,507,507
BEGIN DESCRIPTION:
UNT0142 IN SAND CR 5.0
END DESCRIPTION:
XS GIS Cut Line= 3
      3559631.66     10551715.24      3559803.54     10552480.90
      3559886.74     10553177.74
#Sta/Elev= 30
  4093.4  450.09  4233.2  448.08  4305.5  445.70  4343.7  443.16  4392.1  441.52
  4417.7  441.96  4458.7  441.01  4489.4  438.59  4624.1  438.81  4643.2  440.06
  4653.4  442.88  4667.4  444.75  4684.1  442.72  4710.8  437.11  4725.1  436.29
  4796.9  436.40  4817.4  434.88  4845.9  435.67  4959.4  433.90  4993.6  434.21
  4996.7  432.26  4999.5  431.76  5002.7  432.26  5009.8  434.15  5109.8  437.87
  5223.6  441.73  5372.3  448.48  5422.7  449.35  5498.4  448.54  5579.9  448.92
#Mann=5,-1,0
  4093.4    0.05       0  4996.7    0.03       0  5002.7    0.05       0
  5109.8     0.1       0  5223.6    0.05       0
Bank Sta=4996.7,5002.7
Exp/Cntr=0.3,0.1

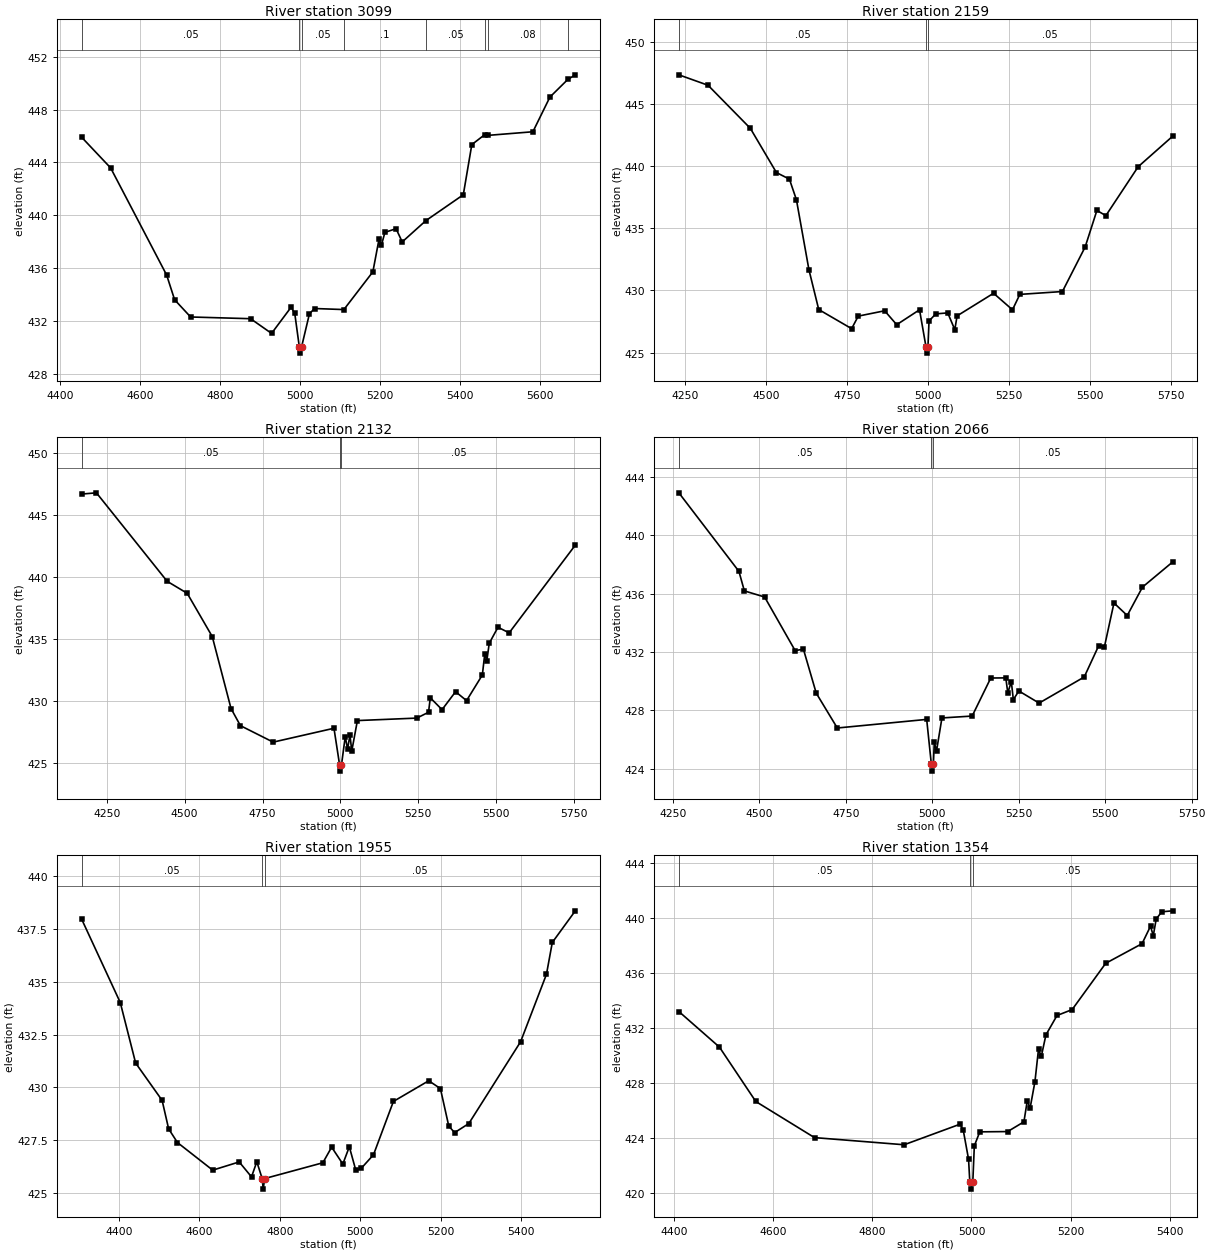
Type RM Length L Ch R = 1,3099,940,940,940
BEGIN DESCRIPTION:
UNT0142 IN SAND CR 4.2
END DESCRIPTION:
XS GIS Cut Line= 3
      3559297.46     10552269.08      3559310.48     10552716.15
      3559722.13     10553387.78
#Sta/Elev= 30
  4453.2  445.91  4525.8  443.59  4665.9  435.50  4685.9  433.63  4725.9  432.33
  4875.9  432.20  4928.4  431.09  4977.3  433.07  4986.4  432.60  4997.7  430.10
  5000.5  429.60  5003.7  430.10  5023.1  432.57  5035.9  432.97  5109.3  432.89
  5181.8  435.74  5197.2  438.21  5203.1  437.74  5211.9  438.72  5239.8  439.00
  5255.2  438.00  5314.5  439.61  5408.0  441.56  5429.3  445.35  5462.0  446.11
  5470.8  446.05  5582.1  446.32  5624.7  448.94  5669.4  450.27  5688.2  450.62
#Mann=8,-1,0
  4453.2    0.05       0  4997.7    0.03       0  5003.7    0.05       0
  5109.3     0.1       0  5314.5    0.05       0  5462.0     0.1       0
  5470.8    0.08       0  5669.4    0.05       0
Bank Sta=4997.7,5003.7
Exp/Cntr=0.3,0.1

Type RM Length L Ch R = 1,2159,27,27,27
BEGIN DESCRIPTION:
UNT0142 IN SAND CR 4.1
END DESCRIPTION:
XS GIS Cut Line= 6
      3558484.44     10551922.03      3558525.67     10552373.44
      3558575.59     10552633.85      3558629.84     10552707.64
      3558944.51     10552879.08      3559176.06     10553147.42
#Sta/Elev= 30
  4232.1  447.36  4322.1  446.52  4452.6  443.05  4533.0  439.49  4573.1  438.96
  4594.7  437.30  4633.4  431.65  4663.5  428.46  4765.0  426.92  4785.4  427.93
  4866.8  428.36  4904.0  427.24  4974.4  428.44  4994.4  425.45  4997.2  424.95
  5000.4  425.45  5003.7  427.54  5024.6  428.11  5061.4  428.19  5083.2  426.84
  5090.3  427.95  5202.8  429.77  5261.1  428.44  5283.8  429.68  5415.1  429.91
  5485.3  433.50  5521.5  436.44  5549.1  436.02  5648.8  439.96  5754.9  442.41
#Mann=3,-1,0
  4232.1    0.05       0  4994.4   0.035       0  5000.4    0.05       0
Bank Sta=4994.4,5000.4
Exp/Cntr=0.3,0.1

Type RM Length L Ch R = 1,2132,66,66,66
BEGIN DESCRIPTION:
UNT0142 IN SAND CR 4.0
END DESCRIPTION:
XS GIS Cut Line= 6
      3558419.34     10551874.29      3558471.42     10552388.63
      3558560.40     10552653.38      3558610.31     10552729.34
      3558918.47     10552894.27      3559139.83     10553163.38
#Sta/Elev= 30
  4169.1  446.71  4216.7  446.81  4443.8  439.67  4508.2  438.70  4588.6  435.21
  4648.9  429.40  4679.0  428.02  4784.2  426.69  4979.4  427.81  4997.5  424.85
  5000.2  424.35  5003.5  424.85  5015.6  427.13  5023.1  426.13  5030.7  427.26
  5036.6  425.98  5054.6  428.43  5245.3  428.63  5283.0  429.10  5288.7  430.27
  5326.4  429.31  5369.8  430.76  5405.1  430.04  5455.8  432.11  5463.7  433.84
  5470.2  433.27  5478.0  434.67  5506.0  435.96  5541.9  435.51  5754.3  442.59
#Mann=3,-1,0
  4169.1    0.05       0  4997.5   0.035       0  5003.5    0.05       0
Bank Sta=4997.5,5003.5
Exp/Cntr=0.3,0.1

Type RM Length L Ch R = 1,2066,111,111,111
BEGIN DESCRIPTION:
UNT0142 IN SAND CR 3.0
END DESCRIPTION:
XS GIS Cut Line= 6
      3558343.39     10551980.66      3558423.68     10552425.52
      3558499.63     10552662.06      3558540.87     10552740.19
      3558890.26     10552948.52      3558997.93     10553153.11
#Sta/Elev= 30
  4267.0  442.92  4440.7  437.53  4456.4  436.19  4515.0  435.77  4603.3  432.09
  4627.2  432.19  4664.3  429.17  4725.2  426.78  4983.7  427.37  4997.1  424.32
  4999.8  423.82  5003.1  424.32  5005.7  425.80  5012.2  425.21  5027.8  427.47
  5115.2  427.60  5169.0  430.21  5212.5  430.22  5218.2  429.20  5228.5  429.95
  5234.3  428.73  5250.3  429.32  5308.8  428.49  5439.3  430.28  5481.2  432.43
  5497.6  432.34  5525.3  435.36  5563.7  434.50  5607.8  436.45  5694.8  438.17
#Mann=3,-1,0
  4267.0    0.05       0  4997.1   0.035       0  5003.1    0.05       0
Bank Sta=4997.1,5003.1
Exp/Cntr=0.3,0.1

Type RM Length L Ch R = 1,1955,601,601,601
BEGIN DESCRIPTION:
UNT0142 IN SAND CR 3.1
END DESCRIPTION:
XS GIS Cut Line= 3
      3558082.96     10552119.52      3558464.91     10552831.33
      3558720.97     10553163.34
#Sta/Elev= 30
  4307.5  437.98  4403.6  434.02  4441.8  431.15  4507.6  429.38  4523.8  428.03
  4545.7  427.38  4633.4  426.07  4699.2  426.46  4729.8  425.75  4743.0  426.47
  4756.3  425.67  4759.0  425.17  4762.3  425.67  4907.1  426.42  4929.0  427.16
  4956.8  426.36  4972.9  427.18  4989.1  426.06  5002.2  426.15  5033.0  426.80
  5082.5  429.33  5170.3  430.31  5199.3  429.94  5220.1  428.16  5234.6  427.85
  5269.9  428.28  5398.6  432.16  5462.9  435.36  5477.4  436.87  5534.6  438.37
#Mann=3,-1,0
  4307.5    0.05       0  4756.3    0.03       0  4762.3    0.05       0
Bank Sta=4756.3,4762.3
Exp/Cntr=0.3,0.1

Type RM Length L Ch R = 1,1354,1230,1230,1230
BEGIN DESCRIPTION:
UNT0142 IN SAND CR 3.2
END DESCRIPTION:
XS GIS Cut Line= 2
      3557730.23     10552275.55      3558164.24     10553171.35
#Sta/Elev= 30
  4410.1  433.19  4491.9  430.60  4565.2  426.64  4683.6  424.01  4864.3  423.49
  4977.2  424.99  4983.6  424.53  4994.2  422.43  4996.7  420.76  4999.5  420.26
  5002.7  420.76  5005.8  423.41  5016.8  424.43  5073.0  424.45  5105.8  425.16
  5112.6  426.71  5118.2  426.15  5128.0  428.08  5135.2  430.45  5140.8  429.92
  5150.2  431.49  5172.5  432.90  5203.0  433.33  5270.7  436.70  5344.0  438.13
  5361.0  439.40  5366.6  438.71  5372.5  439.92  5383.6  440.45  5405.5  440.52
#Mann=3,-1,0
  4410.1    0.05       0  4996.7    0.03       0  5002.7    0.05       0
Bank Sta=4996.7,5002.7
Exp/Cntr=0.3,0.1

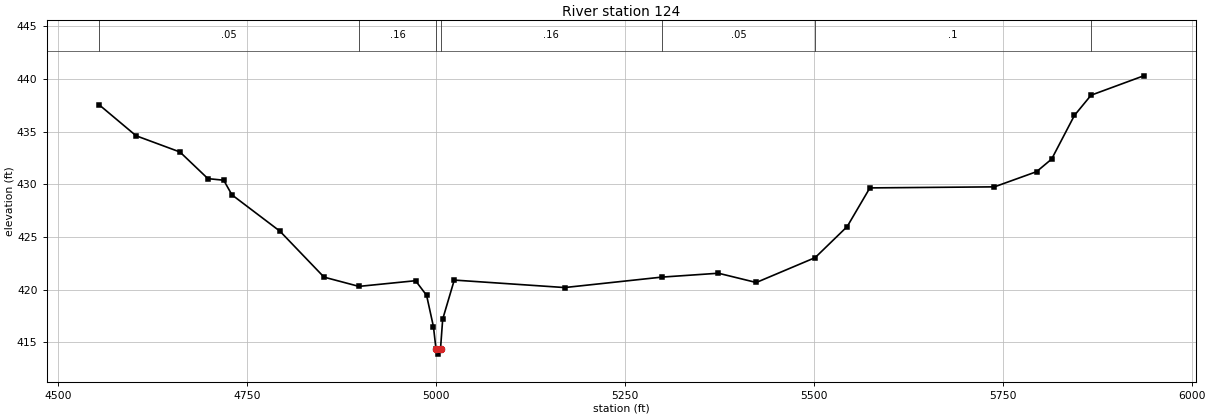
Type RM Length L Ch R = 1,124,0,0,0
BEGIN DESCRIPTION:
UNT0142 IN SAND CR 1.0
END DESCRIPTION:
XS GIS Cut Line= 4
      3557240.65     10552674.88      3557143.43     10552970.01
      3557313.57     10553240.84      3558063.52     10553289.45
#Sta/Elev= 30
  4554.4  437.57  4603.6  434.61  4661.6  433.07  4698.6  430.54  4719.5  430.39
  4730.4  429.00  4793.9  425.55  4852.2  421.19  4898.4  420.31  4973.3  420.85
  4987.9  419.46  4997.0  416.47  5000.3  414.38  5003.0  413.88  5006.3  414.38
  5009.2  417.20  5024.5  420.91  5170.5  420.20  5298.9  421.19  5373.9  421.56
  5424.0  420.68  5501.9  423.04  5544.3  425.99  5574.3  429.66  5739.1  429.76
  5794.8  431.20  5814.8  432.40  5844.9  436.54  5866.9  438.46  5936.5  440.30
#Mann=7,-1,0
  4554.4    0.05       0  4898.4    0.16       0  5000.3    0.07       0
  5006.3    0.16       0  5298.9    0.05       0  5501.9     0.1       0
  5866.9    0.05       0
Bank Sta=5000.3,5006.3
Exp/Cntr=0.3,0.1

Chan Stop Cuts=-1