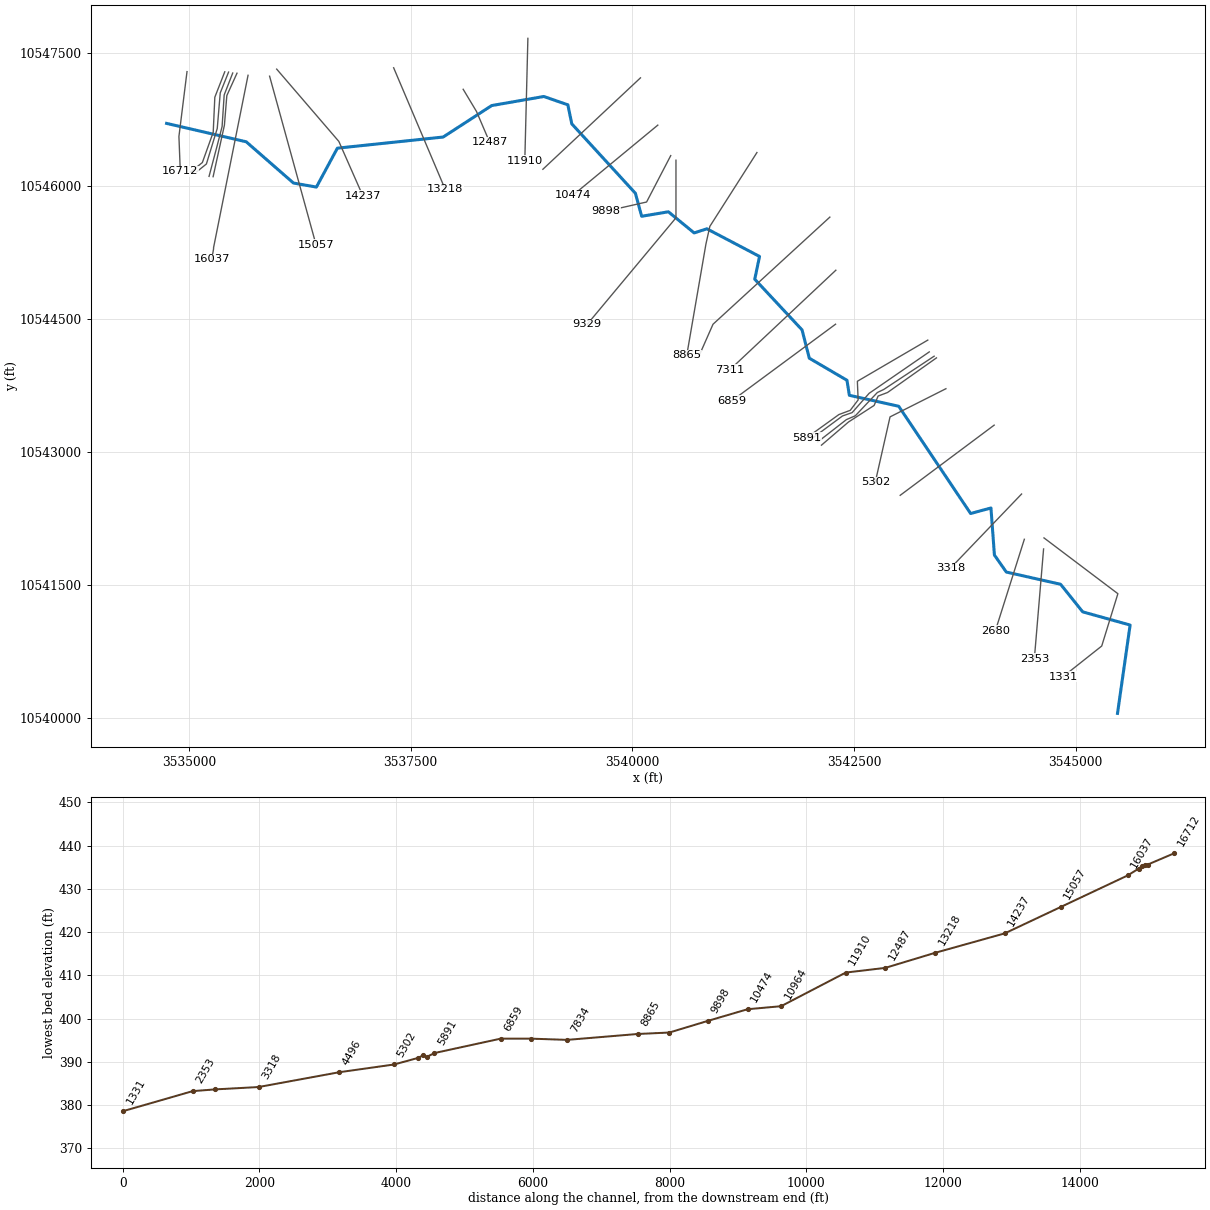
--- UNT0143 IN SAND CR.prj (project) ---

Proj Title=UNT0143 IN SAND CR Base Level Engineering
Current Plan=p01
Default Exp/Contr=0.3,0.1
English Units
Geom File=g01
Flow File=f01
Plan File=p01
Y Axis Title=Elevation
X Axis Title(PF)=Main Channel Distance
X Axis Title(XS)=Station
BEGIN DESCRIPTION:
UNT0143 IN SAND CR
END DESCRIPTION:
DSS Export Rating Curves= 0
DSS Export Rating Curve Sorted= 0
DSS Export Volume Flow Curves= 0
DXF OffsetX= 0
DXF OffsetY= 0
DXF ScaleX= 1
DXF ScaleY= 10

--- UNT0143 IN SAND CR.p01 (plan) ---

Plan Title=Multiple Run
Short Identifier=Multiple
Geom File=g01
Flow File=f01
Subcritical Flow
K Sum by GR= 0
Std Step Tol= 0.01
Critical Tol= 0.01
Num of Std Step Trials= 20
Max Error Tol= 0.3
Flow Tol Ratio= 0.001
Split Flow NTrial= 30
Split Flow Tol= 0.02
Split Flow Ratio= 0.02
Log Output Level= 0
Friction Slope Method= 1
Unsteady Friction Slope Method= 2
Unsteady Bridges Friction Slope Method= 1
Parabolic Critical Depth
Global Vel Dist=  1 , 1 , 1
Global Log Level= 0
CheckData=True
Encroach Param= -1, 0, 0, 0
BEGIN DESCRIPTION:
Multiple Run
END DESCRIPTION:

--- UNT0143 IN SAND CR.f01 (steady flow) ---

Flow Title=Multiple
Program Version=4.10
Number of Profiles= 7
Profile Names=10-year,25-year,50-year,1pct_min,100-year,1pct_plu,500-year
River Rch & RM=UNT0143 IN SAND,Reach-1         ,16712
     892    1215    1477    1312    1774    2399    2549
River Rch & RM=UNT0143 IN SAND,Reach-1         ,12487
    1087    1494    1829    1633    2209    2987    3211
River Rch & RM=UNT0143 IN SAND,Reach-1         ,9329
    1706    2397    2977    2692    3641    4924    5434
River Rch & RM=UNT0143 IN SAND,Reach-1         ,5891
    1882    2649    3295    2982    4033    5454    6029
Boundary for River Rch & Prof#=UNT0143 IN SAND,Reach-1         , 1
Up Type= 0
Dn Type= 3
Dn Slope=0.005
Boundary for River Rch & Prof#=UNT0143 IN SAND,Reach-1         , 2
Up Type= 0
Dn Type= 3
Dn Slope=0.005
Boundary for River Rch & Prof#=UNT0143 IN SAND,Reach-1         , 3
Up Type= 0
Dn Type= 3
Dn Slope=0.005
Boundary for River Rch & Prof#=UNT0143 IN SAND,Reach-1         , 4
Up Type= 0
Dn Type= 3
Dn Slope=0.005
Boundary for River Rch & Prof#=UNT0143 IN SAND,Reach-1         , 5
Up Type= 0
Dn Type= 3
Dn Slope=0.005
Boundary for River Rch & Prof#=UNT0143 IN SAND,Reach-1         , 6
Up Type= 0
Dn Type= 3
Dn Slope=0.005
Boundary for River Rch & Prof#=UNT0143 IN SAND,Reach-1         , 7
Up Type= 0
Dn Type= 3
Dn Slope=0.005
DSS Import GetInterval= 0
DSS Import GetPeak= 0
DSS Import FillOption= 0

--- UNT0143 IN SAND CR.g01 (geometry) ---

Geom Title=Existing Conditions
Program Version=4.10

River Reach=UNT0143 IN SAND ,Reach-1
Reach XY= 30
        3534747.     10546706.83      3535645.16     10546499.34
      3536177.71     10546034.07      3536436.53     10545988.48
      3536673.25     10546427.43      3537866.59     10546553.05
      3538413.62     10546907.98      3539001.81     10547010.31
      3539272.71     10546916.38      3539317.05     10546701.75
       3540034.8     10545918.17      3540105.07     10545659.33
      3540406.63     10545709.78      3540697.31     10545471.35
      3540840.64     10545517.92      3541434.85     10545205.93
      3541380.55     10544949.42      3541914.04     10544377.65
      3541996.12     10544058.03      3542420.76     10543809.17
      3542447.67      10543639.9      3543004.56     10543515.87
      3543815.26     10542306.44      3544044.74      10542368.2
      3544083.94     10541837.43      3544217.93     10541645.84
      3544830.45     10541507.79      3545079.38     10541196.95
      3545614.27      10541048.1      3545472.11     10540051.64

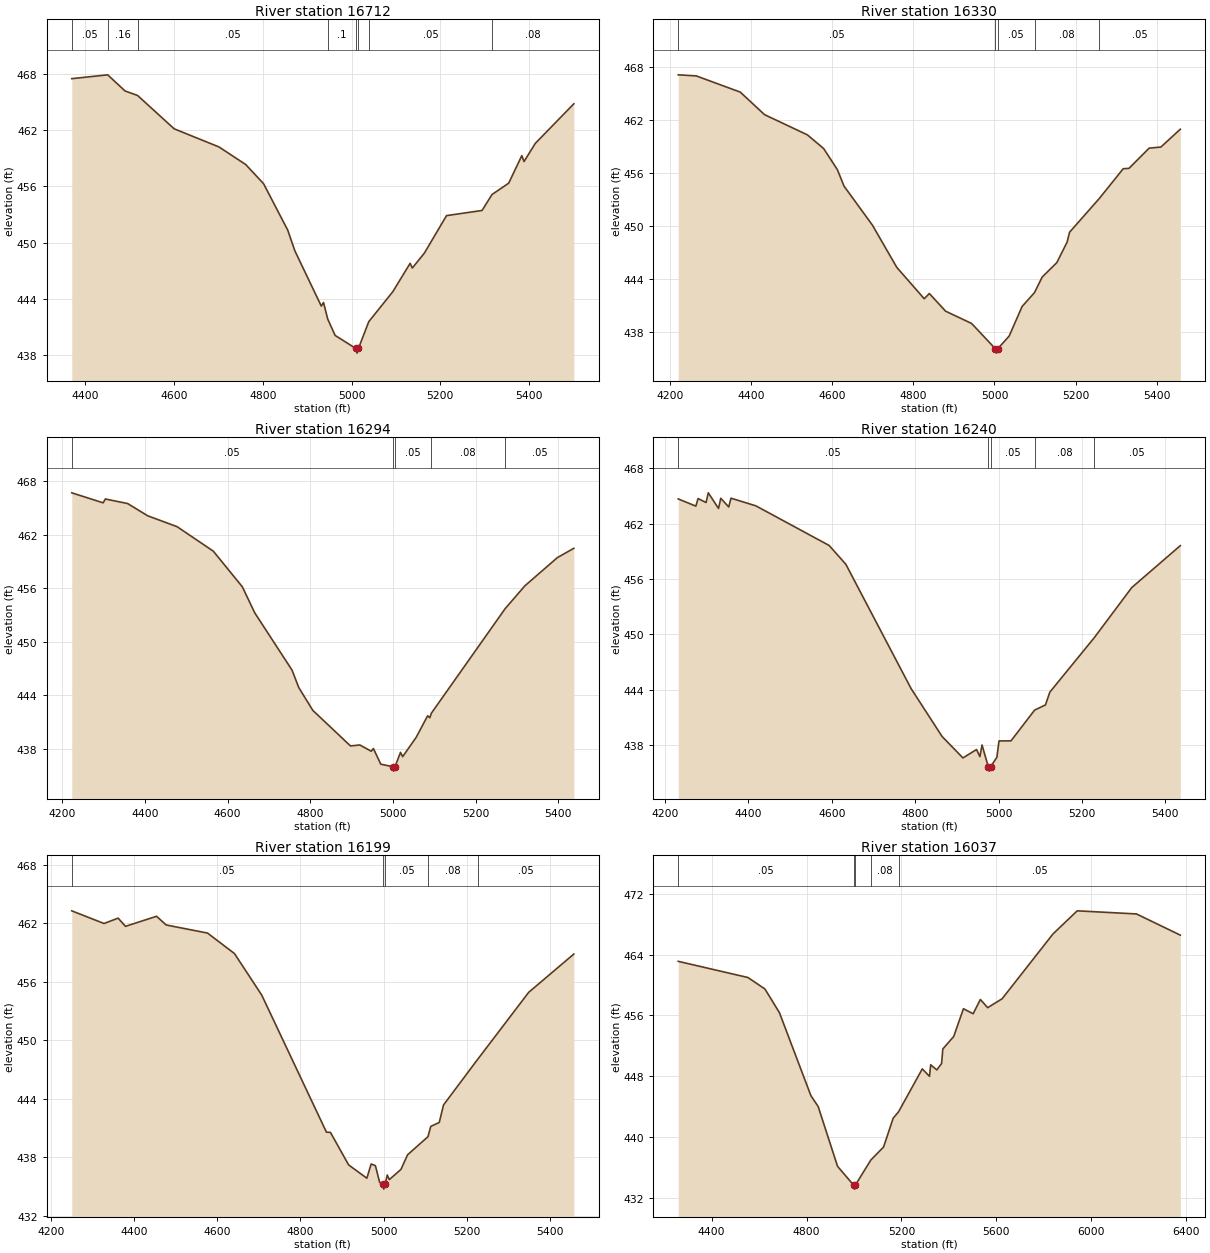
Type RM Length L Ch R = 1 ,16712   ,382,382,382
BEGIN DESCRIPTION:
UNT0143 IN SAND CR 33.0
END DESCRIPTION:
XS GIS Cut Line= 3
      3534977.14     10547290.81      3534885.99     10546559.02
      3534901.55     10546164.87
#Sta/Elev= 30
  4369.2  467.49  4450.2   467.9  4489.3  466.18  4517.5   465.7  4600.1  462.14
  4700.9  460.21  4761.4  458.33  4801.7  456.28    4856  451.34  4872.2  449.12
  4931.7  443.23  4936.8  443.61  4946.3  441.84  4962.9   440.1  5009.5  438.71
  5012.2  438.21  5015.5  438.71  5038.7  441.56  5093.2  444.78    5132  447.79
    5137  447.29  5164.1  448.88  5214.1  452.88  5294.2  453.43  5316.6  455.13
  5354.2  456.34  5383.8  459.28  5388.8  458.65  5414.3  460.59  5501.1  464.81
#Mann= 8 ,-1 , 0
  4369.2     .05       0  4450.2     .16       0  4517.5     .05       0
  4946.3      .1       0  5009.5     .07       0  5015.5      .1       0
  5038.7     .05       0  5316.6     .08       0
Bank Sta=5009.5,5015.5
XS Rating Curve= 0 ,0
Exp/Cntr=0.3,0.1

Type RM Length L Ch R = 1 ,16330   ,36,36,36
BEGIN DESCRIPTION:
UNT0143 IN SAND CR 33.3
END DESCRIPTION:
XS GIS Cut Line= 5
      3535402.92     10547288.71      3535290.94     10547002.25
      3535272.71     10546606.42      3535150.31     10546265.27
      3535017.48     10546158.48
#Sta/Elev= 30
    4221  467.15  4265.3  467.03  4373.9  465.19  4433.6  462.64  4539.2  460.35
  4579.2   458.8  4613.1   456.4  4629.3  454.55  4699.4  450.12  4759.4  445.34
  4826.9  441.79  4839.5  442.38  4879.6  440.38  4943.6  438.99  5002.1  436.13
  5004.9  435.63  5008.1  436.13  5036.1  437.56    5068  440.91  5098.6  442.49
  5117.5  444.25  5153.5  445.88  5178.9  448.21  5184.9  449.32  5258.1  453.14
    5317  456.51  5331.4  456.56    5381  458.85  5409.8  458.97  5457.7  460.99
#Mann= 5 ,-1 , 0
    4221     .05       0  5002.1    .035       0  5008.1     .05       0
  5098.6     .08       0  5258.1     .05       0
Bank Sta=5002.1,5008.1
XS Rating Curve= 0 ,0
Exp/Cntr=0.3,0.1

Type RM Length L Ch R = 1 ,16294   ,54,54,54
BEGIN DESCRIPTION:
UNT0143 IN SAND CR 33.1
END DESCRIPTION:
XS GIS Cut Line= 5
       3535445.9     10547285.63      3535352.14     10547051.21
      3535318.28     10546650.17      3535195.89     10546249.12
       3535086.8     10546160.81
#Sta/Elev= 30
  4223.2  466.69  4299.1  465.57  4304.5     466  4358.4  465.49  4406.8  464.12
    4478   462.9  4565.6  460.16  4635.8  456.17  4665.9  453.25  4756.2  446.83
  4772.3  444.89  4806.4  442.33  4897.5  438.35    4920  438.46  4947.6  437.76
  4952.9  438.06  4970.7  436.31  4999.1  436.03  5001.8  435.53  5005.1  436.03
  5018.5  437.63  5023.7  437.15  5056.5  439.32  5084.1  441.73  5089.3   441.5
  5093.2  442.02  5271.6  453.72  5319.4  456.28  5397.8  459.43  5437.8  460.48
#Mann= 5 ,-1 , 0
  4223.2     .05       0  4999.1    .035       0  5005.1     .05       0
  5093.2     .08       0  5271.6     .05       0
Bank Sta=4999.1,5005.1
XS Rating Curve= 0 ,0
Exp/Cntr=0.3,0.1

Type RM Length L Ch R = 1 ,16240   ,41,41,41
BEGIN DESCRIPTION:
UNT0143 IN SAND CR 33.2
END DESCRIPTION:
XS GIS Cut Line= 5
      3535492.75     10547275.14      3535396.41     10547027.77
      3535372.97     10546671.65      3535316.98      10546454.2
      3535225.83     10546109.14
#Sta/Elev= 30
  4231.9  464.68  4274.1   463.9  4279.5  464.72  4298.6  464.29    4304  465.34
  4328.5  463.65  4333.9  464.75    4353  463.81  4358.4  464.76  4418.1  463.93
  4593.7  459.64  4633.8   457.6  4790.2  444.14  4864.6  438.95  4914.5  436.63
  4947.2  437.54  4955.2  436.77  4960.3  438.03  4975.2   435.7  4977.9   435.2
  4981.2   435.7  4995.9   436.7    5001  438.47  5029.8  438.48  5086.4  441.81
  5112.4  442.37  5122.8  443.75    5229  449.63  5319.3  455.08  5435.7  459.62
#Mann= 5 ,-1 , 0
  4231.9     .05       0  4975.2    .035       0  4981.2     .05       0
  5086.4     .08       0    5229     .05       0
Bank Sta=4975.2,4981.2
XS Rating Curve= 0 ,0
Exp/Cntr=0.3,0.1

Type RM Length L Ch R = 1 ,16199   ,162,162,162
BEGIN DESCRIPTION:
UNT0143 IN SAND CR 33.4
END DESCRIPTION:
XS GIS Cut Line= 4
      3535540.96     10547273.12      3535426.35     10547020.48
      3535399.01     10546686.49      3535271.64     10546105.51
#Sta/Elev= 30
    4250  463.25  4327.5  461.95  4361.5   462.5  4379.1  461.66  4453.9  462.69
    4477   461.8  4576.4  460.97  4641.2  458.87  4706.9   454.6  4862.4  440.55
    4872  440.53  4915.8  437.19  4959.6  435.83  4969.9  437.29  4980.1  437.12
  4990.3  435.41  4997.6  435.21  5000.3  434.71  5003.6  435.21  5008.6  436.16
  5013.7  435.69  5041.5  436.73  5057.5  438.23  5106.6  440.09  5113.2  441.14
  5133.7  441.55  5143.9  443.34  5225.7     448  5348.7  454.89  5457.3  458.82
#Mann= 5 ,-1 , 0
    4250     .05       0  4997.6    .035       0  5003.6     .05       0
  5106.6     .08       0  5225.7     .05       0
Bank Sta=4997.6,5003.6
XS Rating Curve= 0 ,0
Exp/Cntr=0.3,0.1

Type RM Length L Ch R = 1 ,16037   ,980,980,980
BEGIN DESCRIPTION:
UNT0143 IN SAND CR 32.0
END DESCRIPTION:
XS GIS Cut Line= 4
      3535665.64     10547249.77      3535276.75     10545305.29
      3535276.75      10545291.4       3535256.2     10545174.98
#Sta/Elev= 30
  4259.6  463.11  4553.2  460.98  4624.8  459.47    4686  456.35  4818.6  445.42
  4849.2  443.99  4930.8  436.12  4999.2  433.62  5001.9  433.12  5005.2  433.62
  5070.7  436.94  5124.5  438.66  5165.1  442.46  5187.9  443.31  5287.7  448.95
  5318.1  447.97  5323.2  449.49  5348.9  448.81  5369.1  449.67  5374.2  451.57
    5420  453.21  5461.1  456.87  5501.9  456.21  5532.5  458.09    5563  457.01
    5624  458.18  5838.4  466.72  5940.4  469.76    6190  469.35  6374.7  466.56
#Mann= 5 ,-1 , 0
  4259.6     .05       0  4999.2    .035       0  5005.2     .05       0
  5070.7     .08       0  5187.9     .05       0
Bank Sta=4999.2,5005.2
XS Rating Curve= 0 ,0
Exp/Cntr=0.3,0.1

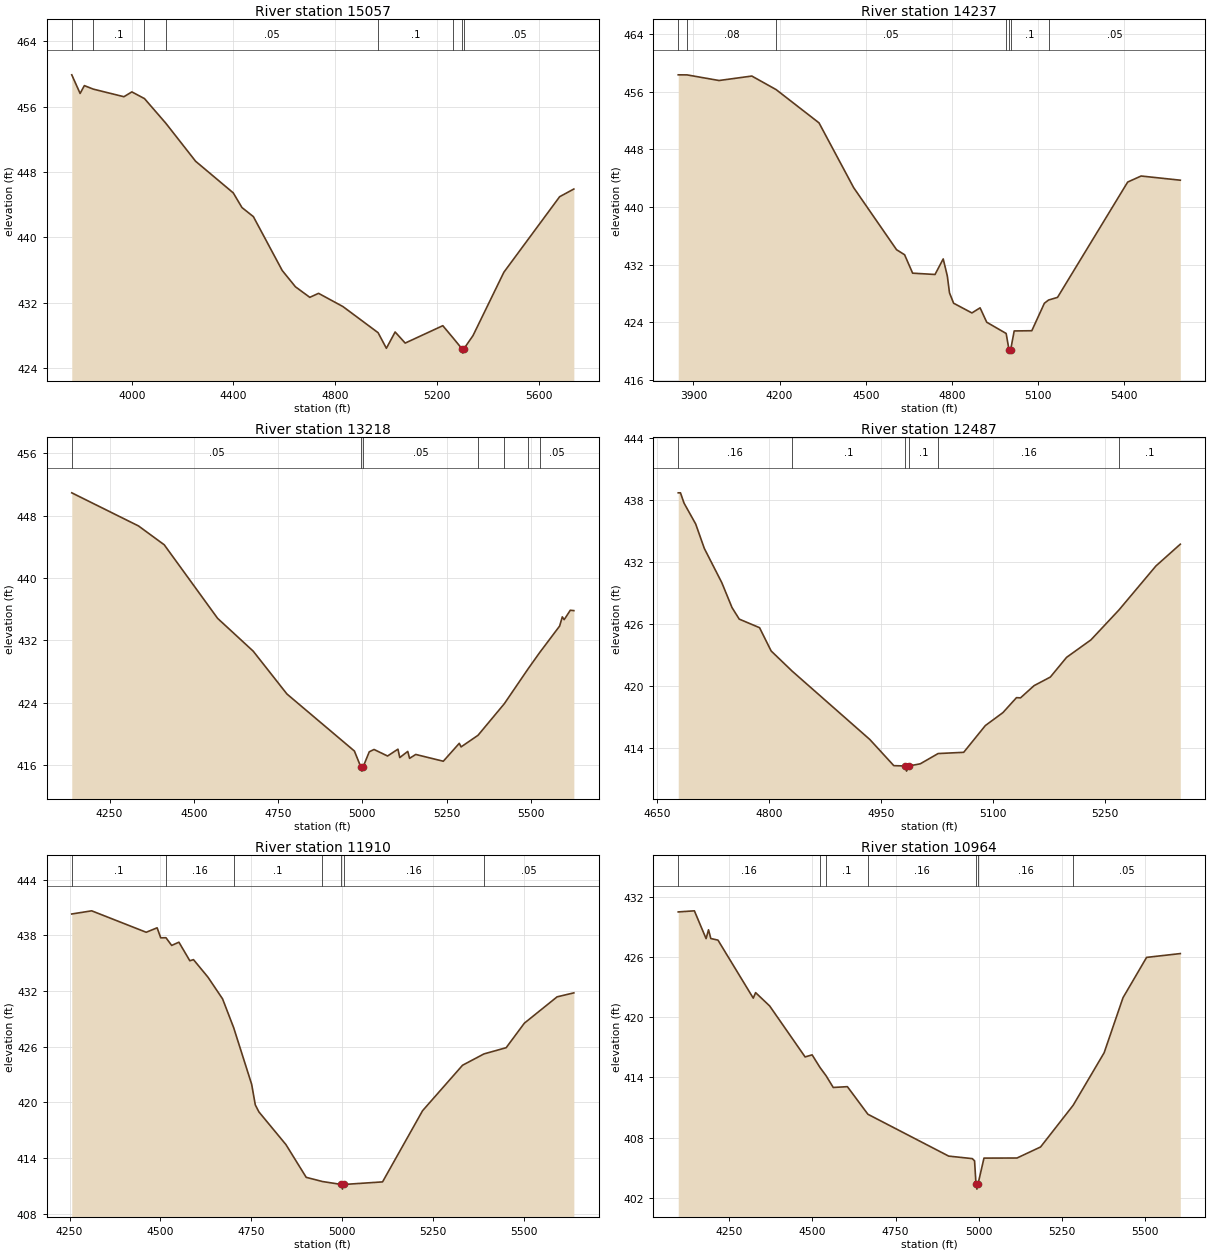
Type RM Length L Ch R = 1 ,15057   ,820,820,820
BEGIN DESCRIPTION:
UNT0143 IN SAND CR 30.0
END DESCRIPTION:
XS GIS Cut Line= 2
      3535908.69     10547239.32      3536432.97     10545336.63
#Sta/Elev= 30
  3764.3  459.89  3797.1  457.61  3813.8  458.57  3848.8  458.14  3969.3  457.21
  4000.5   457.8  4050.1  456.98  4134.1  453.96  4251.1  449.31    4399  445.44
  4433.4  443.64  4478.2  442.53  4591.7  435.93  4643.6  433.94    4700  432.65
  4734.4  433.14  4830.3  431.52  4968.5  428.32    5001  426.41  5035.4  428.41
    5075  427.05  5222.8  429.18  5263.5  427.67    5299  426.32  5301.7  425.82
    5305  426.32  5341.6  427.97    5463  435.73  5682.1  444.97  5737.9  445.91
#Mann= 8 ,-1 , 0
  3764.3     .05       0  3848.8      .1       0  4050.1     .08       0
  4134.1     .05       0  4968.5      .1       0  5263.5     .05       0
    5299     .07       0    5305     .05       0
Bank Sta=5299,5305
XS Rating Curve= 0 ,0
Exp/Cntr=0.3,0.1

Type RM Length L Ch R = 1 ,14237   ,1019,1019,1019
BEGIN DESCRIPTION:
UNT0143 IN SAND CR 28.0
END DESCRIPTION:
XS GIS Cut Line= 3
      3535988.56     10547319.17      3536689.94     10546503.21
      3536960.78     10545888.62
#Sta/Elev= 30
  3847.2  458.35  3878.1  458.34  3989.3  457.56  4103.4  458.18  4187.9   456.3
  4337.2  451.68  4457.9  442.68  4607.1  434.07  4635.1  433.37  4663.1  430.81
    4741  430.63  4769.5  432.79  4783.8  430.43  4791.4  428.08  4805.7  426.64
  4869.4  425.29  4897.9     426    4921     424  4988.6  422.44  4998.4  420.21
  5001.1  419.71  5004.4  420.21  5016.6  422.79  5077.9  422.82  5121.6  426.63
  5136.1  427.08  5167.4  427.45  5411.6  443.46  5458.3   444.3  5594.8  443.72
#Mann= 7 ,-1 , 0
  3847.2     .05       0  3878.1     .08       0  4187.9     .05       0
  4988.6      .1       0  4998.4     .07       0  5004.4      .1       0
  5136.1     .05       0
Bank Sta=4998.4,5004.4
XS Rating Curve= 0 ,0
Exp/Cntr=0.3,0.1

Type RM Length L Ch R = 1 ,13218   ,731,731,731
BEGIN DESCRIPTION:
UNT0143 IN SAND CR 26.0
END DESCRIPTION:
XS GIS Cut Line= 2
      3537307.88     10547334.32      3537889.46     10545962.84
#Sta/Elev= 30
  4137.7  450.93  4335.7  446.68  4412.1  444.26  4570.4  434.82    4676  430.61
  4776.1  425.11  4976.3  417.79  4995.7  415.71  4998.5  415.21  5001.7  415.71
  5020.4  417.69  5034.5  417.99  5074.7  417.15  5105.5  418.03  5110.9  416.95
  5134.6  417.74    5140  416.85  5158.3  417.35  5240.1  416.48  5287.5  418.78
  5292.9  418.32  5343.1  419.81  5420.9  423.85  5491.7  428.34  5525.7  430.41
  5585.2  433.83  5593.2  435.01  5598.7  434.65  5616.9  435.86  5627.4  435.81
#Mann= 7 ,-1 , 0
  4137.7     .05       0  4995.7     .03       0  5001.7     .05       0
  5343.1      .1       0  5420.9     .16       0  5491.7      .1       0
  5525.7     .05       0
Bank Sta=4995.7,5001.7
XS Rating Curve= 0 ,0
Exp/Cntr=0.3,0.1

Type RM Length L Ch R = 1 ,12487   ,577,577,577
BEGIN DESCRIPTION:
UNT0143 IN SAND CR 24.0
END DESCRIPTION:
XS GIS Cut Line= 3
      3538092.08     10547091.68      3538242.11     10546841.64
      3538392.11     10546491.62
#Sta/Elev= 30
  4678.4  438.65  4681.4  438.65  4686.2  437.65  4701.8  435.63  4713.4  433.26
  4736.8  429.95  4750.4  427.55  4760.1  426.43  4787.3   425.6  4802.8  423.35
  4830.9   421.4    4935  414.78  4967.1  412.25  4981.5  412.22  4984.2  411.72
  4987.5  412.22  5002.6  412.43  5026.4  413.42  5060.7  413.54  5089.7  416.13
  5113.2  417.38  5131.4  418.83  5136.8  418.81  5154.9  419.99  5176.7  420.82
  5198.5  422.73  5231.1  424.42  5268.7  427.32  5318.1  431.57  5350.8  433.68
#Mann= 6 ,-1 , 0
  4678.4     .16       0  4830.9      .1       0  4981.5     .07       0
  4987.5      .1       0  5026.4     .16       0  5268.7      .1       0
Bank Sta=4981.5,4987.5
XS Rating Curve= 0 ,0
Exp/Cntr=0.3,0.1

Type RM Length L Ch R = 1 ,11910   ,946,946,946
BEGIN DESCRIPTION:
UNT0143 IN SAND CR 23.0
END DESCRIPTION:
XS GIS Cut Line= 2
      3538821.89     10547666.39      3538787.19     10546285.53
#Sta/Elev= 30
    4256  440.29  4310.8  440.63  4460.8  438.32  4490.8   438.8  4500.8  437.72
  4515.2  437.73  4530.8   436.9  4550.8  437.25  4580.8  435.25  4590.9  435.37
  4630.9  433.47  4670.9  431.14  4701.4  428.04  4750.9  421.94  4760.9  419.72
  4770.9  418.96  4845.2  415.44    4901  411.91  4945.6  411.46    4998  411.14
  5000.7  410.64    5004  411.14    5111  411.42  5221.1  419.09  5331.1  423.99
    5390  425.21  5451.1  425.88  5501.1  428.52  5591.2  431.36  5637.3  431.79
#Mann= 7 ,-1 , 0
    4256      .1       0  4515.2     .16       0  4701.4      .1       0
  4945.6     .16       0    4998     .07       0    5004     .16       0
    5390     .05       0
Bank Sta=4998,5004
XS Rating Curve= 0 ,0
Exp/Cntr=0.3,0.1

Type RM Length L Ch R = 1 ,10964   ,490,490,490
BEGIN DESCRIPTION:
UNT0143 IN SAND CR 21.0
END DESCRIPTION:
XS GIS Cut Line= 2
      3540091.69     10547220.61      3538991.01     10546189.37
#Sta/Elev= 30
  4097.2  430.48  4145.7  430.59  4180.9  427.82  4188.2   428.7  4195.1  427.83
  4216.6  427.67  4322.6  421.89  4329.6  422.44  4371.9  421.11  4478.4  416.03
  4499.4  416.24  4522.9  414.99  4541.3  414.16  4562.9  412.99  4605.4  413.07
    4667  410.32  4909.7  406.15  4980.5   405.9  4987.4  405.68  4991.7  403.36
  4994.4  402.86  4997.7  403.36  5015.7  405.95  5114.9  405.96  5185.7  407.06
  5283.5  411.21  5376.7  416.45  5433.3  421.93  5504.2  425.95  5605.5  426.33
#Mann= 7 ,-1 , 0
  4097.2     .16       0  4522.9     .08       0  4541.3      .1       0
    4667     .16       0  4991.7     .07       0  4997.7     .16       0
  5283.5     .05       0
Bank Sta=4991.7,4997.7
XS Rating Curve= 0 ,0
Exp/Cntr=0.3,0.1

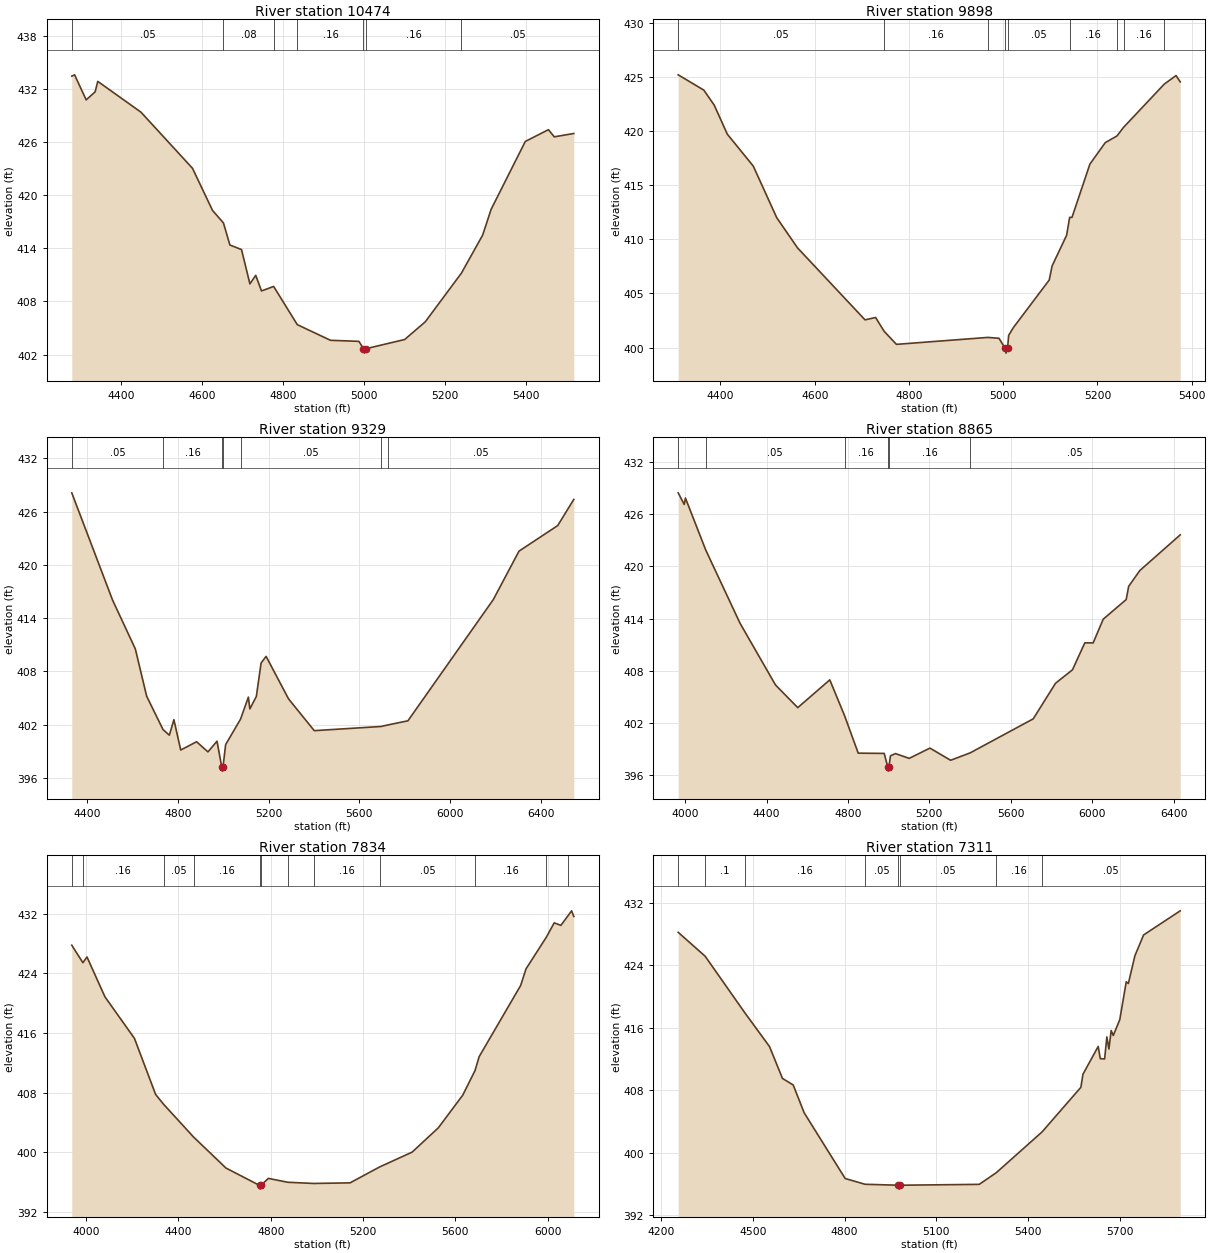
Type RM Length L Ch R = 1 ,10474   ,576,576,576
BEGIN DESCRIPTION:
UNT0143 IN SAND CR 20.0
END DESCRIPTION:
XS GIS Cut Line= 2
      3540287.17     10546687.24      3539329.49     10545896.11
#Sta/Elev= 30
  4277.1  433.47  4284.1  433.62  4312.8  430.79    4335   431.7  4341.4  432.88
  4448.3   429.4  4575.9  423.05  4625.4  418.29  4652.4  416.88  4668.4  414.38
  4697.1  413.87  4717.9  409.99  4732.3  410.95  4746.6  409.19  4776.6   409.7
  4835.1  405.38  4917.3  403.61  4987.6  403.49  4998.9  402.66  5001.7  402.16
  5004.9  402.66  5100.9   403.7  5151.8   405.7  5241.3  411.21  5293.8   415.5
  5314.6   418.4  5399.3  426.09  5456.6  427.42  5470.9  426.61  5519.3  426.99
#Mann= 7 ,-1 , 0
  4277.1     .05       0  4652.4     .08       0  4776.6     .05       0
  4835.1     .16       0  4998.9     .07       0  5004.9     .16       0
  5241.3     .05       0
Bank Sta=4998.9,5004.9
XS Rating Curve= 0 ,0
Exp/Cntr=0.3,0.1

Type RM Length L Ch R = 1 ,9898    ,569,569,569
BEGIN DESCRIPTION:
UNT0143 IN SAND CR 18.0
END DESCRIPTION:
XS GIS Cut Line= 3
      3540432.99     10546343.47       3540160.7     10545820.03
      3539696.96     10545715.03
#Sta/Elev= 30
  4310.3  425.18  4364.7  423.77  4386.8  422.38  4414.6   419.7  4469.6  416.76
  4519.5  411.99  4563.7   409.2  4706.9  402.56  4729.3  402.78  4747.3  401.51
  4773.5   400.3  4967.4  400.94  4991.2  400.86  5003.4  399.99  5006.1  399.49
  5009.4  399.99  5011.7  401.13  5021.9  401.86  5097.8  406.24  5103.9  407.54
  5134.7  410.37  5141.1  412.02  5146.1  412.02  5184.1  416.94  5216.7  418.92
  5241.6  419.54  5255.5  420.33  5342.1  424.33  5366.9  425.11  5375.8  424.53
#Mann= 9 ,-1 , 0
  4310.3     .05       0  4747.3     .16       0  4967.4     .05       0
  5003.4     .03       0  5009.4     .05       0  5141.1     .16       0
  5241.6      .1       0  5255.5     .16       0  5342.1      .1       0
Bank Sta=5003.4,5009.4
XS Rating Curve= 0 ,0
Exp/Cntr=0.3,0.1

Type RM Length L Ch R = 1 ,9329    ,464,464,464
BEGIN DESCRIPTION:
UNT0143 IN SAND CR 17.0
END DESCRIPTION:
XS GIS Cut Line= 3
      3540492.11     10546291.62      3540492.11     10545641.64
      3539492.12     10544441.66
#Sta/Elev= 30
  4332.9  428.13  4512.9  416.03  4612.9  410.55  4662.9  405.21  4735.1  401.45
  4762.9  400.82  4782.9  402.57  4812.9  399.15  4882.9  400.08  4932.9  398.94
  4972.9  400.14  4993.5  397.27  4996.3  396.77  4999.5  397.27  5010.9  399.76
  5076.4  402.62  5111.1  405.11  5117.6  403.78  5146.2  405.19  5167.1  408.96
  5189.2   409.7  5288.1  404.91  5401.4  401.33  5695.6   401.8    5725  401.97
    5814  402.44  6190.2   416.1  6303.5  421.56    6474  424.44  6544.9  427.39
#Mann= 7 ,-1 , 0
  4332.9     .05       0  4735.1     .16       0  4993.5     .07       0
  4999.5     .16       0  5076.4     .05       0  5695.6     .16       0
    5725     .05       0
Bank Sta=4993.5,4999.5
XS Rating Curve= 0 ,0
Exp/Cntr=0.3,0.1

Type RM Length L Ch R = 1 ,8865    ,1031,1031,1031
BEGIN DESCRIPTION:
UNT0143 IN SAND CR 16.0
END DESCRIPTION:
XS GIS Cut Line= 4
      3541405.23     10546378.23      3540873.97     10545544.87
      3540829.85     10545344.56      3540613.55     10544089.97
#Sta/Elev= 30
    3966  428.48  3995.7  427.14  4001.6  427.88  4101.6  421.88  4270.3  413.44
  4444.2  406.35  4553.4  403.74  4710.8  406.94  4783.4  402.82  4850.5   398.5
  4978.1  398.47  4995.6  396.93  4998.3  396.43  5001.6  396.93  5008.8  398.19
  5033.5  398.45    5101   397.9    5203  399.08  5304.4  397.68  5400.4  398.53
  5710.3  402.45  5819.9  406.55  5903.1   408.1    5964  411.21  6004.6  411.19
  6054.3  413.93    6167  416.19  6179.2  417.71    6234  419.53  6432.5  423.64
#Mann= 6 ,-1 , 0
    3966     .16       0  4101.6     .05       0  4783.4     .16       0
  4995.6     .07       0  5001.6     .16       0  5400.4     .05       0
Bank Sta=4995.6,5001.6
XS Rating Curve= 0 ,0
Exp/Cntr=0.3,0.1

Type RM Length L Ch R = 1 ,7834    ,523,523,523
BEGIN DESCRIPTION:
UNT0143 IN SAND CR 14.0
END DESCRIPTION:
XS GIS Cut Line= 3
      3542227.63     10545649.69      3540909.92     10544441.35
      3540753.65     10544087.15
#Sta/Elev= 30
  3938.2  427.76  3986.4  425.42  4004.3  426.18    4082  420.84  4209.7  415.28
  4301.5  407.76    4337  406.41  4465.7  402.06  4606.1   397.9  4751.7  395.57
  4754.5  395.07  4757.7  395.57  4789.9  396.51  4874.2  395.99  4985.5  395.83
  5143.8  395.91  5271.8  398.04  5412.7  400.03  5526.1  403.28  5632.2  407.67
  5685.3  410.96  5703.1  412.82    5883  422.37  5906.3   424.6  5994.1  428.83
  6028.3  430.76  6057.1  430.42  6086.7  431.65  6103.7  432.37  6113.2  431.62
#Mann= 12 ,-1 , 0
  3938.2     .05       0  3986.4     .16       0    4337     .05       0
  4465.7     .16       0  4751.7     .07       0  4757.7     .16       0
  4874.2     .05       0  4985.5     .16       0  5271.8     .05       0
  5685.3     .16       0  5994.1     .05       0  6086.7     .16       0
Bank Sta=4751.7,4757.7
XS Rating Curve= 0 ,0
Exp/Cntr=0.3,0.1

Type RM Length L Ch R = 1 ,7311    ,452,452,452
BEGIN DESCRIPTION:
UNT0143 IN SAND CR 13.0
END DESCRIPTION:
XS GIS Cut Line= 2
      3542295.34     10545050.74      3541097.91     10543926.19
#Sta/Elev= 30
  4255.8  428.22    4344  425.16  4474.8  417.87  4554.6   413.6    4597  409.52
  4632.2  408.68  4667.9  405.13  4802.2  396.71  4867.2  395.97    4976  395.85
  4978.8  395.35    4982  395.85  5240.8  395.96  5296.8  397.46  5446.4  402.67
  5573.4  408.38  5580.3  410.06  5630.1  413.61  5636.9  412.05  5651.1  412.01
  5658.4  414.83  5665.2  413.29  5672.6  415.65  5679.4  415.01  5700.7  417.04
  5721.9  421.88  5728.8  421.67  5750.2  425.22  5778.6  427.88  5898.5  430.97
#Mann= 8 ,-1 , 0
  4255.8     .05       0    4344      .1       0  4474.8     .16       0
  4867.2     .05       0    4976    .033       0    4982     .05       0
  5296.8     .16       0  5446.4     .05       0
Bank Sta=4976,4982
XS Rating Curve= 0 ,0
Exp/Cntr=0.3,0.1

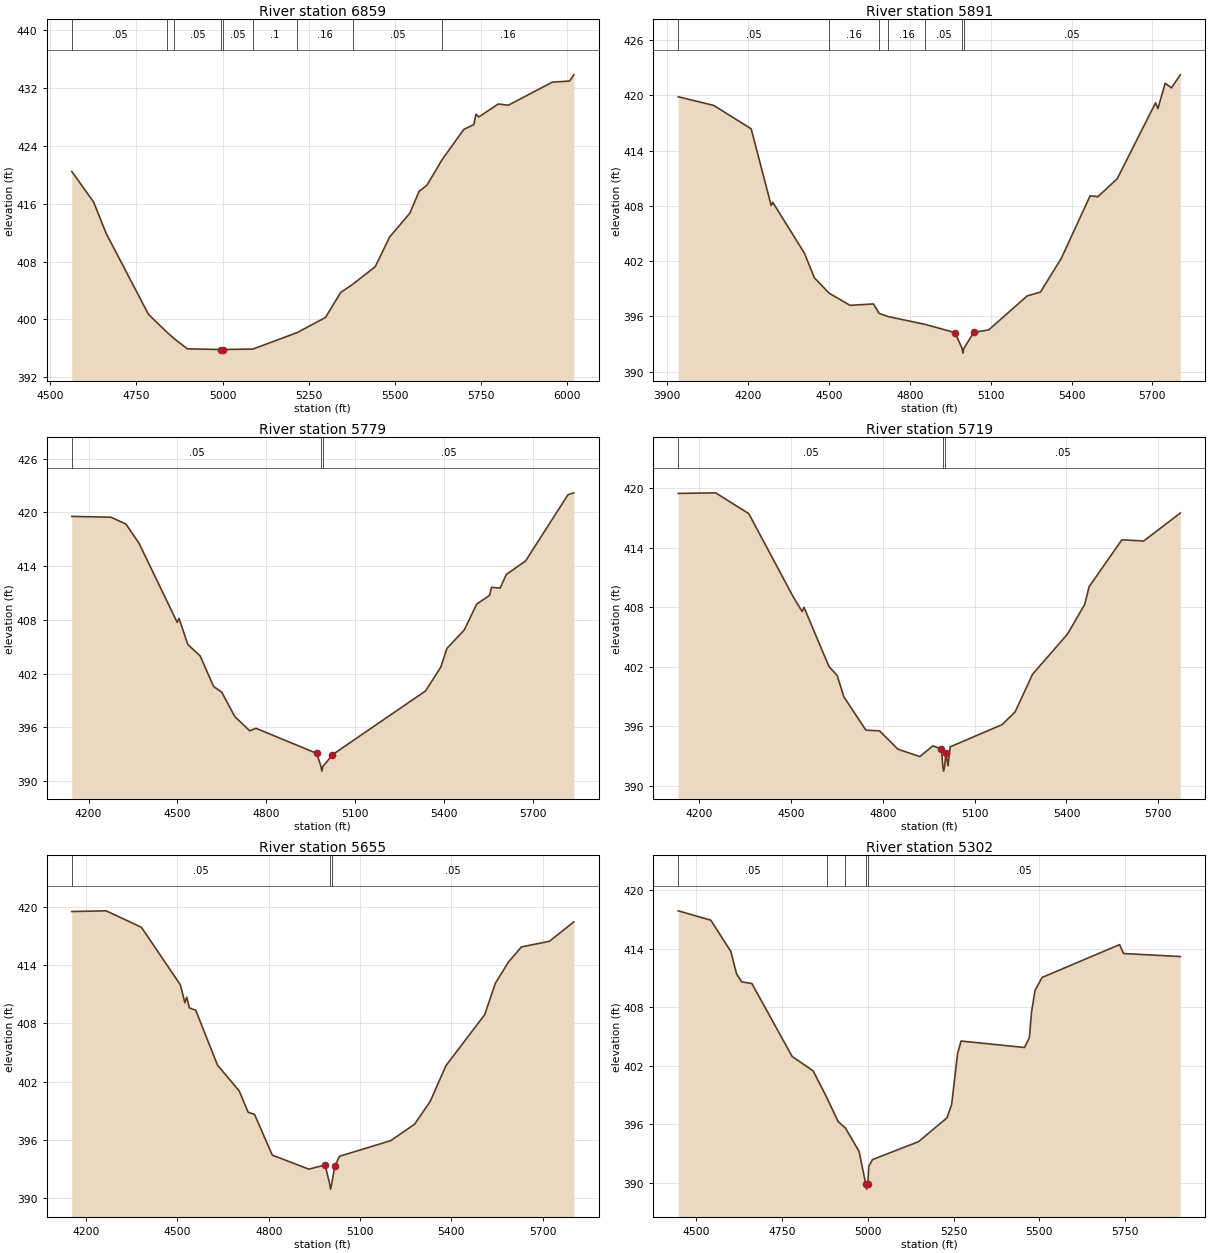
Type RM Length L Ch R = 1 ,6859    ,968,968,968
BEGIN DESCRIPTION:
UNT0143 IN SAND CR 12.0
END DESCRIPTION:
XS GIS Cut Line= 2
      3542292.14     10544441.66      3541120.88     10543576.41
#Sta/Elev= 30
  4562.3  420.45    4626  416.19  4661.8  411.91  4784.7  400.71  4838.7  398.22
  4859.8  397.33    4898  395.94  4994.6  395.85  4997.3  395.35  5000.6  395.85
  5087.7  395.91  5216.7   398.2  5298.3  400.28  5342.2  403.73  5377.1  404.86
  5442.4  407.29  5484.1  411.38  5542.6  414.66  5569.7  417.69  5592.7  418.56
  5636.2  422.06  5699.1  426.24  5728.4  426.92  5734.6  428.35    5743  427.98
  5799.4  429.76  5828.6  429.59  5955.9  432.78    6006  432.93  6018.5  433.79
#Mann= 9 ,-1 , 0
  4562.3     .05       0  4838.7     .16       0  4859.8     .05       0
  4994.6    .033       0  5000.6     .05       0  5087.7      .1       0
  5216.7     .16       0  5377.1     .05       0  5636.2     .16       0
Bank Sta=4994.6,5000.6
XS Rating Curve= 0 ,0
Exp/Cntr=0.3,0.1

Type RM Length L Ch R = 1 ,5891    ,112,112,112
BEGIN DESCRIPTION:
UNT0143 IN SAND CR 10.0
END DESCRIPTION:
XS GIS Cut Line= 6
      3543332.34     10544262.24      3542538.07     10543797.83
      3542546.75     10543587.33      3542457.78     10543470.14
      3542329.74      10543422.4      3541966.17     10543160.54
#Sta/Elev= 30
  3940.9  419.85  4072.6  418.91  4211.5  416.37  4285.8  408.04  4291.6  408.39
    4409  402.87  4446.2  400.19  4500.8  398.52  4578.3  397.21  4665.2  397.36
    4686  396.34  4718.1     396    4857  395.14  4967.3  394.25  4994.3  392.52
    4997  392.02  5000.3  392.52  5037.3  394.28  5092.6  394.54  5235.5  398.23
  5284.8  398.65    5362  402.31  5468.8  409.09  5498.2  409.01  5569.4  410.95
  5711.8   419.2  5720.3  418.55  5747.4  421.31  5770.7  420.82  5803.5  422.23
#Mann= 7 ,-1 , 0
  3940.9     .05       0  4500.8     .16       0    4686     .05       0
  4718.1     .16       0    4857     .05       0  4994.3     .03       0
  5000.3     .05       0
Bank Sta=4967.3,5037.3
XS Rating Curve= 0 ,0
Exp/Cntr=0.3,0.1

Type RM Length L Ch R = 1 ,5779    ,60,60,60
BEGIN DESCRIPTION:
UNT0143 IN SAND CR 10.1
END DESCRIPTION:
XS GIS Cut Line= 5
      3543349.17     10544129.21      3542670.45     10543661.73
      3542479.48     10543444.71       3542370.1     10543406.52
      3541996.11     10543129.48
#Sta/Elev= 30
  4143.2  419.55  4275.2  419.46  4325.9   418.7  4370.3  416.55  4499.1  407.72
  4505.2  408.17  4534.9  405.26  4576.8  403.97  4621.5  400.59  4649.6  399.93
  4693.2  397.22  4743.9  395.63  4764.9  395.91  4969.9  393.11  4984.5  391.63
  4987.2  391.13  4990.5  391.63  5022.6  392.95  5337.3  400.08  5388.7  402.74
  5409.5  404.83    5468  406.88  5509.7  409.76  5553.5  410.75  5559.8  411.64
    5589  411.55  5609.9  413.08  5674.6  414.57  5817.8  421.96  5837.7  422.18
#Mann= 3 ,-1 , 0
  4143.2     .05       0  4984.5     .03       0  4990.5     .05       0
Bank Sta=4969.9,5022.6
XS Rating Curve= 0 ,0
Exp/Cntr=0.3,0.1

Type RM Length L Ch R = 1 ,5719    ,64,64,64
BEGIN DESCRIPTION:
UNT0143 IN SAND CR 9.1
END DESCRIPTION:
XS GIS Cut Line= 6
      3543404.01     10544080.79      3542836.29     10543705.78
      3542763.37     10543671.06      3542515.11      10543408.9
      3542414.41      10543365.5      3542091.51     10543113.77
#Sta/Elev= 30
  4130.8  419.49  4253.1  419.55  4361.4  417.45  4505.9   409.1    4536  407.56
    4542     408  4623.3  402.04  4650.4  401.12  4672.4  398.96  4744.3   395.6
  4788.9  395.54  4849.1  393.68  4920.6  392.94  4963.1  394.02  4991.4  393.71
  4995.7  391.97  4998.4  391.47  5001.7  391.97  5005.6  393.33  5012.8  392.01
  5019.7  393.92  5189.6  396.16  5232.1  397.45  5289.2  401.25  5403.4   405.3
  5459.5  408.29    5474  410.08  5581.1  414.81  5652.2  414.69  5772.1  417.51
#Mann= 3 ,-1 , 0
  4130.8     .05       0  4995.7     .03       0  5001.7     .05       0
Bank Sta=4991.4,5005.6
XS Rating Curve= 0 ,0
Exp/Cntr=0.3,0.1

Type RM Length L Ch R = 1 ,5655    ,353,353,353
BEGIN DESCRIPTION:
UNT0143 IN SAND CR 9.2
END DESCRIPTION:
XS GIS Cut Line= 6
      3543430.05     10544061.69      3542877.95     10543671.06
      3542772.05     10543631.13      3542726.91     10543525.22
      3542436.98     10543337.72      3542133.13     10543077.28
#Sta/Elev= 30
  4152.7  419.54  4265.9  419.61  4381.7  417.91  4509.6  411.98  4524.4  410.14
  4530.5  410.71  4539.2   409.6  4560.1  409.36  4631.5  403.71  4702.9  401.04
  4732.4  398.84  4753.3  398.63  4811.7  394.42  4931.7  392.97  4985.4   393.4
  5000.6  391.41  5003.4  390.91  5006.6  391.41  5017.7  393.32  5032.7   394.3
    5201  395.91  5279.5  397.61    5331  399.97  5382.4  403.64  5509.8   408.9
  5544.9  412.14  5587.7  414.32  5630.5  415.89  5722.7  416.47  5802.8  418.47
#Mann= 3 ,-1 , 0
  4152.7     .05       0  5000.6     .03       0  5006.6     .05       0
Bank Sta=4985.4,5017.7
XS Rating Curve= 0 ,0
Exp/Cntr=0.3,0.1

Type RM Length L Ch R = 1 ,5302    ,806,806,806
BEGIN DESCRIPTION:
UNT0143 IN SAND CR 9.0
END DESCRIPTION:
XS GIS Cut Line= 3
      3543536.82     10543713.95       3542906.6     10543396.23
      3542739.93     10542659.22
#Sta/Elev= 30
  4448.7  417.87  4543.6  416.91  4601.7  413.72  4618.4  411.43  4633.2   410.6
    4663  410.43  4780.1  402.97  4841.5  401.48  4880.5   398.8    4914   396.3
  4935.2  395.64  4975.3  393.23  4994.6  389.88  4997.3  389.38  5000.6  389.88
  5003.2  391.69  5013.9   392.4  5148.1  394.24    5231  396.68  5244.6  398.06
  5261.7  403.24    5272  404.54  5456.5  403.88  5470.7  404.89    5477  407.49
  5487.3  409.74  5507.8  411.05  5733.3  414.41  5745.1   413.5  5910.1  413.19
#Mann= 5 ,-1 , 0
  4448.7     .05       0  4880.5     .16       0  4935.2     .05       0
  4994.6     .03       0  5000.6     .05       0
Bank Sta=4994.6,5000.6
XS Rating Curve= 0 ,0
Exp/Cntr=0.3,0.1

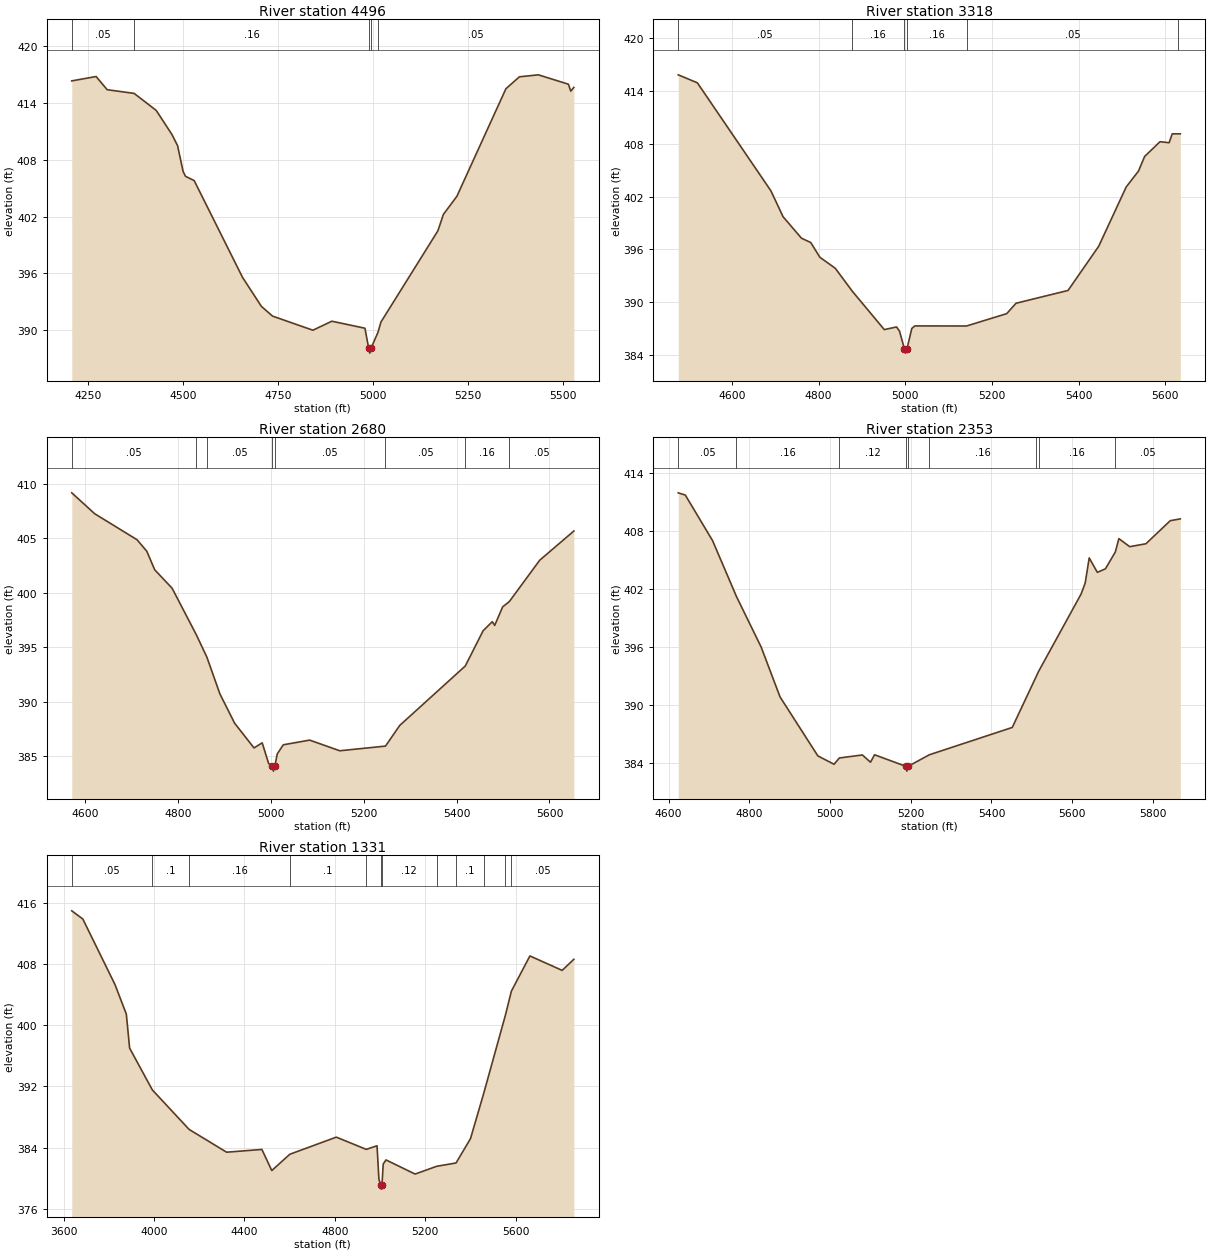
Type RM Length L Ch R = 1 ,4496    ,1178,1178,1178
BEGIN DESCRIPTION:
UNT0143 IN SAND CR 8.0
END DESCRIPTION:
XS GIS Cut Line= 2
      3544081.04      10543303.1      3543021.16     10542511.45
#Sta/Elev= 30
  4206.8  416.33  4270.9  416.79  4300.1   415.4  4371.1  415.01  4429.4  413.21
    4471  410.65  4485.6  409.49  4500.2  406.76  4506.5  406.25  4529.4   405.8
  4656.6  395.59  4706.6  392.51  4735.8  391.49  4842.1     390  4892.1  390.95
  4979.3  390.21  4989.2  388.08  4991.9  387.58  4995.2  388.08  5013.9  389.81
  5021.4  390.86  5171.4  400.49    5186  402.23  5221.5  404.14  5350.7   415.5
  5386.2  416.76  5436.2  416.97  5515.4  415.98  5521.6  415.25  5529.7  415.64
#Mann= 5 ,-1 , 0
  4206.8     .05       0  4371.1     .16       0  4989.2     .07       0
  4995.2     .16       0  5013.9     .05       0
Bank Sta=4989.2,4995.2
XS Rating Curve= 0 ,0
Exp/Cntr=0.3,0.1

Type RM Length L Ch R = 1 ,3318    ,638,638,638
BEGIN DESCRIPTION:
UNT0143 IN SAND CR 6.0
END DESCRIPTION:
XS GIS Cut Line= 2
      3544390.11     10542526.05      3543588.05     10541689.27
#Sta/Elev= 30
  4475.8  415.86    4520  414.95  4689.7  402.65  4717.8   399.7  4760.3  397.25
  4781.7  396.76  4802.8  395.08  4838.3  393.83  4877.5  391.22  4951.5  386.84
  4979.8  387.14  4986.7  386.66  4997.9  384.66  5000.6  384.16  5003.9  384.66
    5015  386.97  5022.1  387.26  5141.3  387.25  5234.2  388.66  5255.6  389.84
  5375.7   391.3  5446.5  396.33    5510  403.09  5538.3  404.89  5552.5  406.56
    5588  408.24  5609.1  408.13  5616.3  409.14  5630.1  409.14  5634.9  409.14
#Mann= 6 ,-1 , 0
  4475.8     .05       0  4877.5     .16       0  4997.9     .07       0
  5003.9     .16       0  5141.3     .05       0  5630.1     .16       0
Bank Sta=4997.9,5003.9
XS Rating Curve= 0 ,0
Exp/Cntr=0.3,0.1

Type RM Length L Ch R = 1 ,2680    ,327,327,327
BEGIN DESCRIPTION:
UNT0143 IN SAND CR 4.0
END DESCRIPTION:
XS GIS Cut Line= 2
      3544421.34     10542015.59      3544095.33     10540985.54
#Sta/Elev= 30
    4572  409.18  4621.3  407.26  4712.5  404.87  4733.5  403.81  4750.5  402.11
    4788  400.41    4840  396.14  4862.7  394.09  4890.8   390.7  4922.5  388.01
  4964.2  385.74  4981.8  386.21  4995.7   384.3  5003.2  384.11  5005.9  383.61
  5009.2  384.11  5014.1  385.19  5027.2  386.03    5084  386.46  5148.6  385.48
  5247.1  385.91  5277.8  387.81  5418.8  393.27  5457.2  396.51  5476.9  397.34
  5482.1     397  5499.2   398.7  5513.6  399.19    5579  402.99  5652.4  405.67
#Mann= 8 ,-1 , 0
    4572     .05       0    4840     .16       0  4862.7     .05       0
  5003.2     .03       0  5009.2     .05       0  5247.1     .05       0
  5418.8     .16       0  5513.6     .05       0
Bank Sta=5003.2,5009.2
XS Rating Curve= 0 ,0
Exp/Cntr=0.3,0.1

Type RM Length L Ch R = 1 ,2353    ,1022,1022,1022
BEGIN DESCRIPTION:
UNT0143 IN SAND CR 2.0
END DESCRIPTION:
XS GIS Cut Line= 2
      3544638.37     10541906.38       3544534.2     10540666.75
#Sta/Elev= 30
  4623.9  411.95  4641.4  411.72  4708.9  407.02  4768.2  401.24  4829.4  396.02
  4876.2  390.87  4969.9  384.78    5010  383.92  5023.2  384.57  5080.2  384.88
  5100.3  384.13  5110.3   384.9  5187.6  383.71  5190.4  383.21  5193.6  383.71
  5246.2   384.9  5451.5  387.72  5509.4  392.85  5516.8  393.51  5622.1   401.5
  5632.2  402.63  5642.2  405.23  5662.3  403.74  5682.4   404.1    5707  405.85
  5715.6  407.22  5742.6  406.39  5782.7  406.69  5842.9  409.07  5867.9  409.26
#Mann= 9 ,-1 , 0
  4623.9     .05       0  4768.2     .16       0  5023.2     .12       0
  5187.6     .07       0  5193.6     .12       0  5246.2     .16       0
  5509.4     .05       0  5516.8     .16       0    5707     .05       0
Bank Sta=5187.6,5193.6
XS Rating Curve= 0 ,0
Exp/Cntr=0.3,0.1

Type RM Length L Ch R = 1 ,1331    ,0,0,0
BEGIN DESCRIPTION:
UNT0143 IN SAND CR 1.0
END DESCRIPTION:
XS GIS Cut Line= 4
      3544643.06     10542030.99       3545476.4     10541401.65
      3545294.11     10540811.37      3544856.44      10540464.7
#Sta/Elev= 30
  3636.5  414.96  3685.4  413.89  3827.9   405.3  3877.8  401.45  3892.4     397
    3993  391.53  4155.5  386.37  4321.2  383.39  4477.3  383.75    4521  380.99
  4600.8  383.12  4806.4  385.36  4938.9  383.76  4986.5  384.23  4994.8   379.9
  5002.2  379.06    5005  378.56  5008.2  379.06  5013.9  381.85  5026.2  382.38
  5154.9  380.53  5250.7  381.55  5335.9  381.98  5399.8  385.16  5458.2  391.07
  5554.5  401.34  5580.6  404.45  5662.6  409.06  5805.2  407.17  5856.9  408.62
#Mann= 12 ,-1 , 0
  3636.5     .05       0    3993      .1       0  4155.5     .16       0
  4600.8      .1       0  4938.9     .12       0  5002.2     .07       0
  5008.2     .12       0  5250.7     .16       0  5335.9      .1       0
  5458.2     .05       0  5554.5      .1       0  5580.6     .05       0
Bank Sta=5002.2,5008.2
XS Rating Curve= 0 ,0
Exp/Cntr=0.3,0.1

Chan Stop Cuts=-1
Use User Specified Reach Order=0
Composite Channel Slope=5