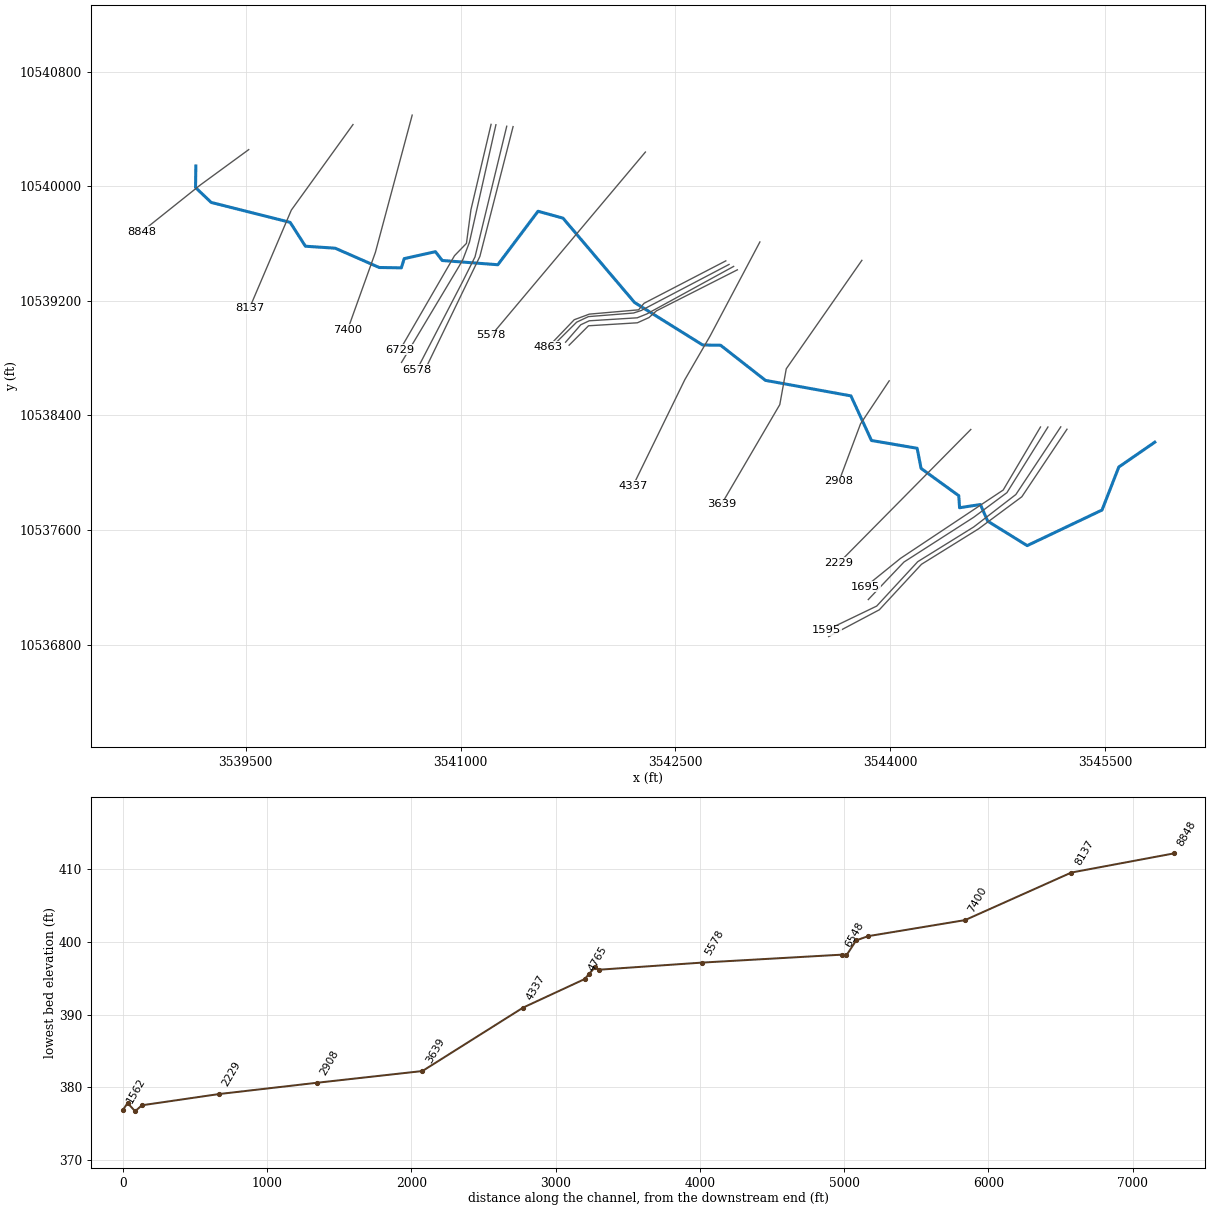
--- UNT0144 IN SAND CR.prj (project) ---

Proj Title=UNT0144 IN SAND CR Base Level Engineering
Current Plan=p01
Default Exp/Contr=0.3,0.1
English Units
Geom File=g01
Flow File=f01
Plan File=p01
Y Axis Title=Elevation
X Axis Title(PF)=Main Channel Distance
X Axis Title(XS)=Station
BEGIN DESCRIPTION:
UNT0144 IN SAND CR
END DESCRIPTION:
DSS Export Rating Curves= 0
DSS Export Rating Curve Sorted= 0
DSS Export Volume Flow Curves= 0
DXF OffsetX= 0
DXF OffsetY= 0
DXF ScaleX= 1
DXF ScaleY= 10

--- UNT0144 IN SAND CR.p01 (plan) ---

Plan Title=Multiple Run
Short Identifier=Multiple
Geom File=g01
Flow File=f01
Subcritical Flow
K Sum by GR= 0
Std Step Tol= 0.01
Critical Tol= 0.01
Num of Std Step Trials= 20
Max Error Tol= 0.3
Flow Tol Ratio= 0.001
Split Flow NTrial= 30
Split Flow Tol= 0.02
Split Flow Ratio= 0.02
Log Output Level= 0
Friction Slope Method= 1
Unsteady Friction Slope Method= 2
Unsteady Bridges Friction Slope Method= 1
Parabolic Critical Depth
Global Vel Dist=  1 , 1 , 1
Global Log Level= 0
CheckData=True
Encroach Param= -1, 0, 0, 0
BEGIN DESCRIPTION:
Multiple Run
END DESCRIPTION:

--- UNT0144 IN SAND CR.f01 (steady flow) ---

Flow Title=Multiple
Number of Profiles=7
Profile Names=10-year,25-year,50-year,1pct_min,100-year,1pct_plu,500-year
River Rch & RM= UNT0144 IN SAND ,Reach-1,8848
     922    1260    1538    1370    1853    2506    2682
River Rch & RM= UNT0144 IN SAND ,Reach-1,5578
    1237    1715    2112    1896    2564    3468    3770
Boundary for River Rch & Prof#=UNT0144 IN SAND ,Reach-1,1
Up Type=0
Dn Type=3
Dn Slope=0.005
Boundary for River Rch & Prof#=UNT0144 IN SAND ,Reach-1,2
Up Type=0
Dn Type=3
Dn Slope=0.005
Boundary for River Rch & Prof#=UNT0144 IN SAND ,Reach-1,3
Up Type=0
Dn Type=3
Dn Slope=0.005
Boundary for River Rch & Prof#=UNT0144 IN SAND ,Reach-1,4
Up Type=0
Dn Type=3
Dn Slope=0.005
Boundary for River Rch & Prof#=UNT0144 IN SAND ,Reach-1,5
Up Type=0
Dn Type=3
Dn Slope=0.005
Boundary for River Rch & Prof#=UNT0144 IN SAND ,Reach-1,6
Up Type=0
Dn Type=3
Dn Slope=0.005
Boundary for River Rch & Prof#=UNT0144 IN SAND ,Reach-1,7
Up Type=0
Dn Type=3
Dn Slope=0.005

--- UNT0144 IN SAND CR.g01 (geometry) ---

Geom Title=Existing Conditions
Program Version=4.10

River Reach=UNT0144 IN SAND ,Reach-1
Reach XY= 30
      3539152.11     10540141.64      3539150.16     10539990.82
       3539259.6     10539886.82      3539810.63     10539747.91
      3539917.01     10539581.27      3540125.06     10539567.49
      3540432.24     10539432.74      3540586.75     10539430.38
      3540606.71     10539494.62       3540824.6     10539543.23
      3540872.14     10539481.56      3541260.36     10539452.08
      3541540.74     10539825.35      3541715.02     10539777.31
      3542214.42      10539188.7      3542690.12     10538891.83
      3542815.12     10538890.09      3543128.21     10538644.95
      3543724.96     10538536.56      3543868.36     10538225.13
      3544187.06     10538170.99      3544214.67     10538030.36
      3544477.69     10537839.74      3544483.42     10537755.88
      3544628.73     10537778.28      3544679.77     10537662.13
      3544955.29      10537491.3      3545477.77     10537739.74
      3545594.73     10538039.91      3545845.92     10538213.41

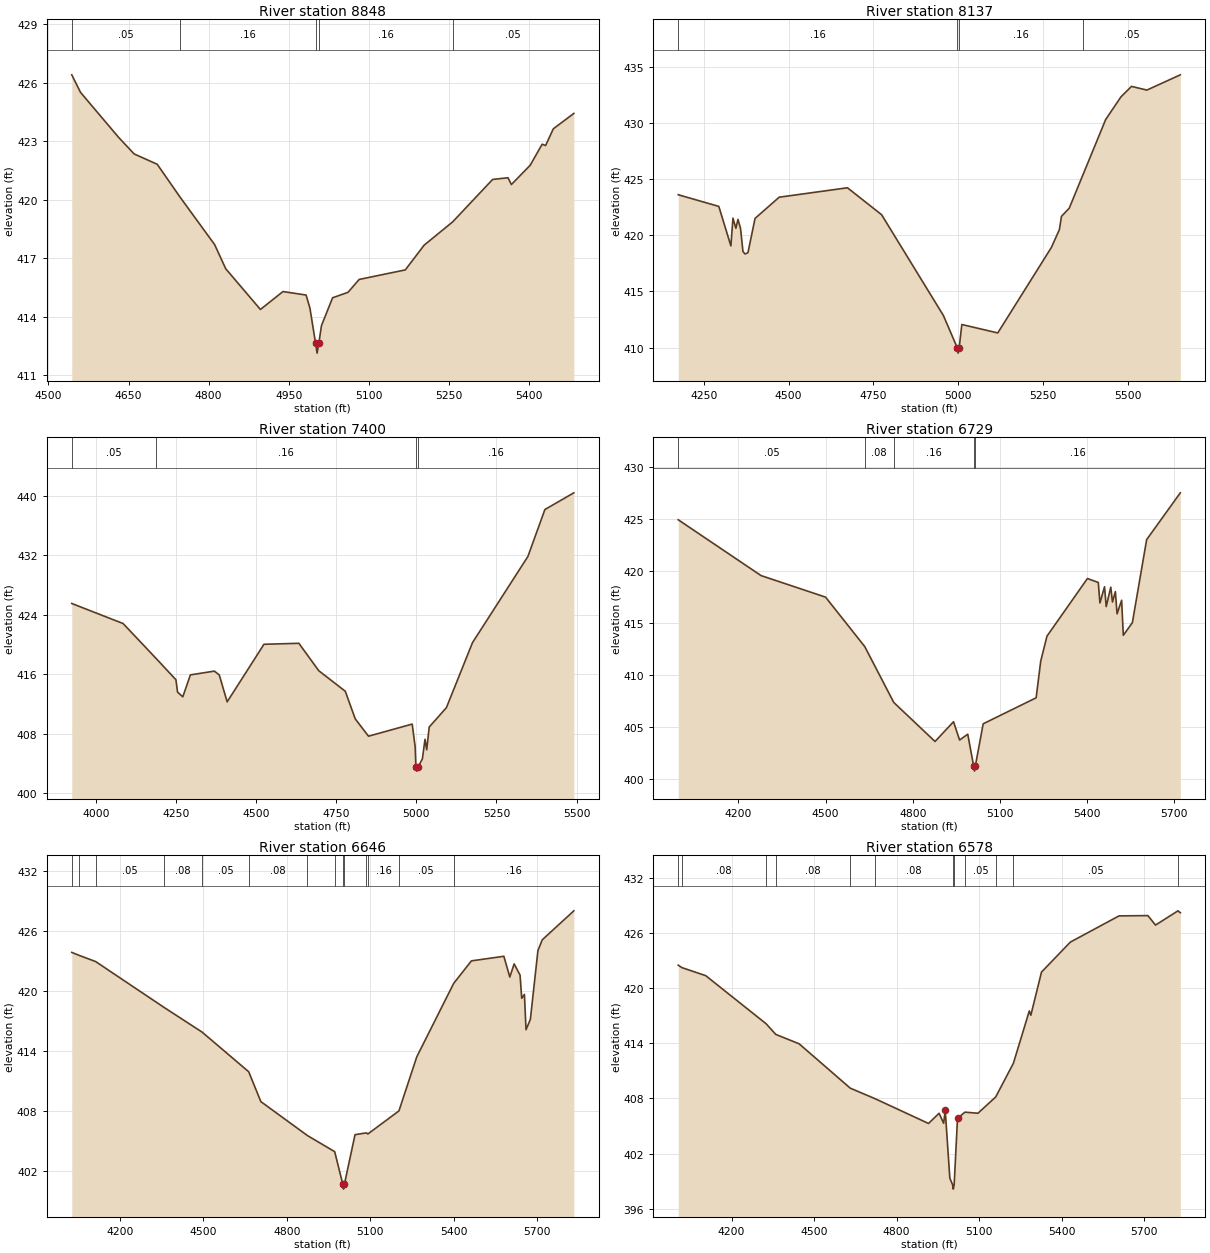
Type RM Length L Ch R = 1 ,8848    ,711,711,711
BEGIN DESCRIPTION:
UNT0144 IN SAND CR 16.0
END DESCRIPTION:
XS GIS Cut Line= 3
      3539521.32     10540255.59      3539182.76     10540008.18
      3538775.92     10539683.57
#Sta/Elev= 30
  4543.8  426.41  4560.2  425.51  4631.2  423.21  4660.6  422.35  4703.8  421.82
  4746.9  420.12  4811.2   417.7    4832  416.46  4896.9  414.37  4939.2  415.29
  4982.4  415.11  4989.6  414.44  5000.2  412.63    5003  412.13  5006.2  412.63
  5011.2  413.54    5032  414.97  5060.9  415.25  5081.7  415.91  5168.1   416.4
  5203.4  417.67  5256.6  418.86  5331.5  421.04  5360.3  421.13  5366.7  420.78
  5401.9  421.77  5424.3  422.85  5430.7  422.78  5445.2  423.64  5483.6  424.43
#Mann= 5 ,-1 , 0
  4543.8     .05       0  4746.9     .16       0  5000.2     .07       0
  5006.2     .16       0  5256.6     .05       0
Bank Sta=5000.2,5006.2
XS Rating Curve= 0 ,0
Exp/Cntr=0.3,0.1

Type RM Length L Ch R = 1 ,8137    ,737,737,737
BEGIN DESCRIPTION:
UNT0144 IN SAND CR 15.0
END DESCRIPTION:
XS GIS Cut Line= 3
      3540249.26     10540430.58       3539818.7     10539833.36
      3539527.06     10539149.38
#Sta/Elev= 30
  4174.5  423.62  4294.1  422.58  4329.7  419.06  4335.8  421.53  4344.4  420.63
  4350.6  421.42  4358.1  420.62  4365.3  418.55  4371.4  418.34    4380  418.45
  4400.9  421.51    4472   423.4  4673.3  424.24  4773.9  421.84  4956.1  412.85
  4996.6     410  4999.3   409.5  5002.6     410  5010.4  412.05  5116.3   411.3
  5274.3  418.92  5297.9  420.51    5304  421.69  5326.9  422.42  5368.5  425.48
  5434.4  430.33  5479.5  432.35  5510.5  433.28  5555.8  432.95  5654.3  434.31
#Mann= 4 ,-1 , 0
  4174.5     .16       0  4996.6     .07       0  5002.6     .16       0
  5368.5     .05       0
Bank Sta=4996.6,5002.6
XS Rating Curve= 0 ,0
Exp/Cntr=0.3,0.1

Type RM Length L Ch R = 1 ,7400    ,671,671,671
BEGIN DESCRIPTION:
UNT0144 IN SAND CR 13.0
END DESCRIPTION:
XS GIS Cut Line= 3
      3540662.44     10540496.51      3540405.51     10539538.22
      3540211.08      10538996.6
#Sta/Elev= 30
  3924.1  425.53  4084.4  422.83  4188.1   418.1  4249.3  415.27  4254.4   413.6
  4270.8  412.97  4294.5  415.92  4369.3  416.43  4384.7  415.91  4409.3  412.29
  4524.2  420.04  4633.2  420.17  4695.3  416.48  4778.1  413.72  4809.2     410
  4850.6  407.67    4987   409.3  4996.3  406.24  4998.6  403.47  5001.4  402.97
  5004.6  403.47  5018.8  404.62    5027  407.25  5032.3  405.84  5040.1   408.9
  5093.8  411.51  5175.4  420.27  5348.2  431.85  5401.3  438.17  5491.7  440.42
#Mann= 4 ,-1 , 0
  3924.1     .05       0  4188.1     .16       0  4998.6     .07       0
  5004.6     .16       0
Bank Sta=4998.6,5004.6
XS Rating Curve= 0 ,0
Exp/Cntr=0.3,0.1

Type RM Length L Ch R = 1 ,6729    ,83,83,83
BEGIN DESCRIPTION:
UNT0144 IN SAND CR 12.1
END DESCRIPTION:
XS GIS Cut Line= 5
      3541213.02      10540431.9      3541072.39     10539835.51
      3541041.14     10539601.13       3540957.8      10539515.2
      3540577.62     10538858.98
#Sta/Elev= 30
  3993.2  424.94  4278.2  419.57  4500.1   417.5  4634.8  412.75  4734.8  407.37
  4876.7  403.62  4940.3  405.52  4961.1  403.76  4989.3  404.32  5009.4  401.27
  5012.2  400.77  5015.4  401.27  5042.3  405.32  5224.5  407.82  5240.3  411.35
  5261.8  413.75    5401  419.29  5438.3  418.91    5444  416.94  5459.8   418.5
  5465.6  416.59  5481.3  418.46  5487.1  417.03  5497.1  418.03  5502.9  415.89
  5518.6   417.2  5524.4  413.83  5555.6  415.05  5604.7  423.03  5720.5  427.53
#Mann= 5 ,-1 , 0
  3993.2     .05       0  4634.8     .08       0  4734.8     .16       0
  5009.4     .07       0  5015.4     .16       0
Bank Sta=5009.4,5015.4
XS Rating Curve= 0 ,0
Exp/Cntr=0.3,0.1

Type RM Length L Ch R = 1 ,6646    ,68,68,68
BEGIN DESCRIPTION:
UNT0144 IN SAND CR 12.0
END DESCRIPTION:
XS GIS Cut Line= 5
      3541246.86     10540429.23      3541061.97     10539608.95
       3541017.7     10539491.76      3540991.66     10539444.88
      3540588.01      10538770.4
#Sta/Elev= 30
  4026.9  423.89  4054.5  423.58  4112.9  422.97  4358.9  418.38  4495.6  415.91
  4663.3  411.94    4707  408.95  4874.7  405.55  4972.6  403.94  5001.6  400.69
  5004.4  400.19  5007.6  400.69  5045.7  405.64  5086.5  405.82  5091.9  405.71
  5203.6  408.02  5267.9  413.44  5400.4  420.78  5464.3  423.04    5581   423.5
  5602.4  421.42    5618  422.74  5639.3  421.61  5645.2   419.3  5654.9  419.68
  5660.7  416.15  5676.3  417.18  5703.5  424.06  5719.1  425.15  5832.7  428.05
#Mann= 14 ,-1 , 0
  4026.9     .05       0  4054.5     .08       0  4112.9     .05       0
  4358.9     .08       0  4495.6     .05       0  4663.3     .08       0
  4874.7     .16       0  4972.6     .08       0  5001.6     .07       0
  5007.6     .08       0  5086.5     .05       0  5091.9     .16       0
  5203.6     .05       0  5400.4     .16       0
Bank Sta=5001.6,5007.6
XS Rating Curve= 0 ,0
Exp/Cntr=0.3,0.1

Type RM Length L Ch R = 1 ,6578    ,30,30,30
BEGIN DESCRIPTION:
UNT0144 IN SAND CR 12.2
END DESCRIPTION:
XS GIS Cut Line= 4
      3541322.39     10540418.85      3541101.03     10539507.38
      3541015.09     10539335.51      3540694.77      10538718.3
#Sta/Elev= 30
  4006.3  422.48  4020.1  422.21  4106.3  421.34  4325.9  416.11  4361.1  414.95
  4445.9  413.93  4631.7  409.11  4721.4  407.97  4916.3  405.27  4954.7  406.38
  4971.4  405.29    4977  406.72  4993.8  399.33  5003.6  398.63  5006.3  398.13
  5009.6  398.63  5021.7  405.83  5048.7   406.5    5096  406.38  5160.8  408.16
    5225  411.82  5282.8  417.51  5288.4  417.04  5327.1  421.73    5432  424.99
    5609  427.84    5714  427.87  5741.7  426.84  5823.4  428.39  5831.8  428.18
#Mann= 12 ,-1 , 0
  4006.3     .05       0  4020.1     .08       0  4325.9     .05       0
  4361.1     .08       0  4631.7     .05       0  4721.4     .08       0
  5003.6     .07       0  5009.6     .08       0  5048.7     .05       0
  5160.8     .16       0    5225     .05       0  5823.4     .16       0
Bank Sta=4977,5021.7
XS Rating Curve= 0 ,0
Exp/Cntr=0.3,0.1

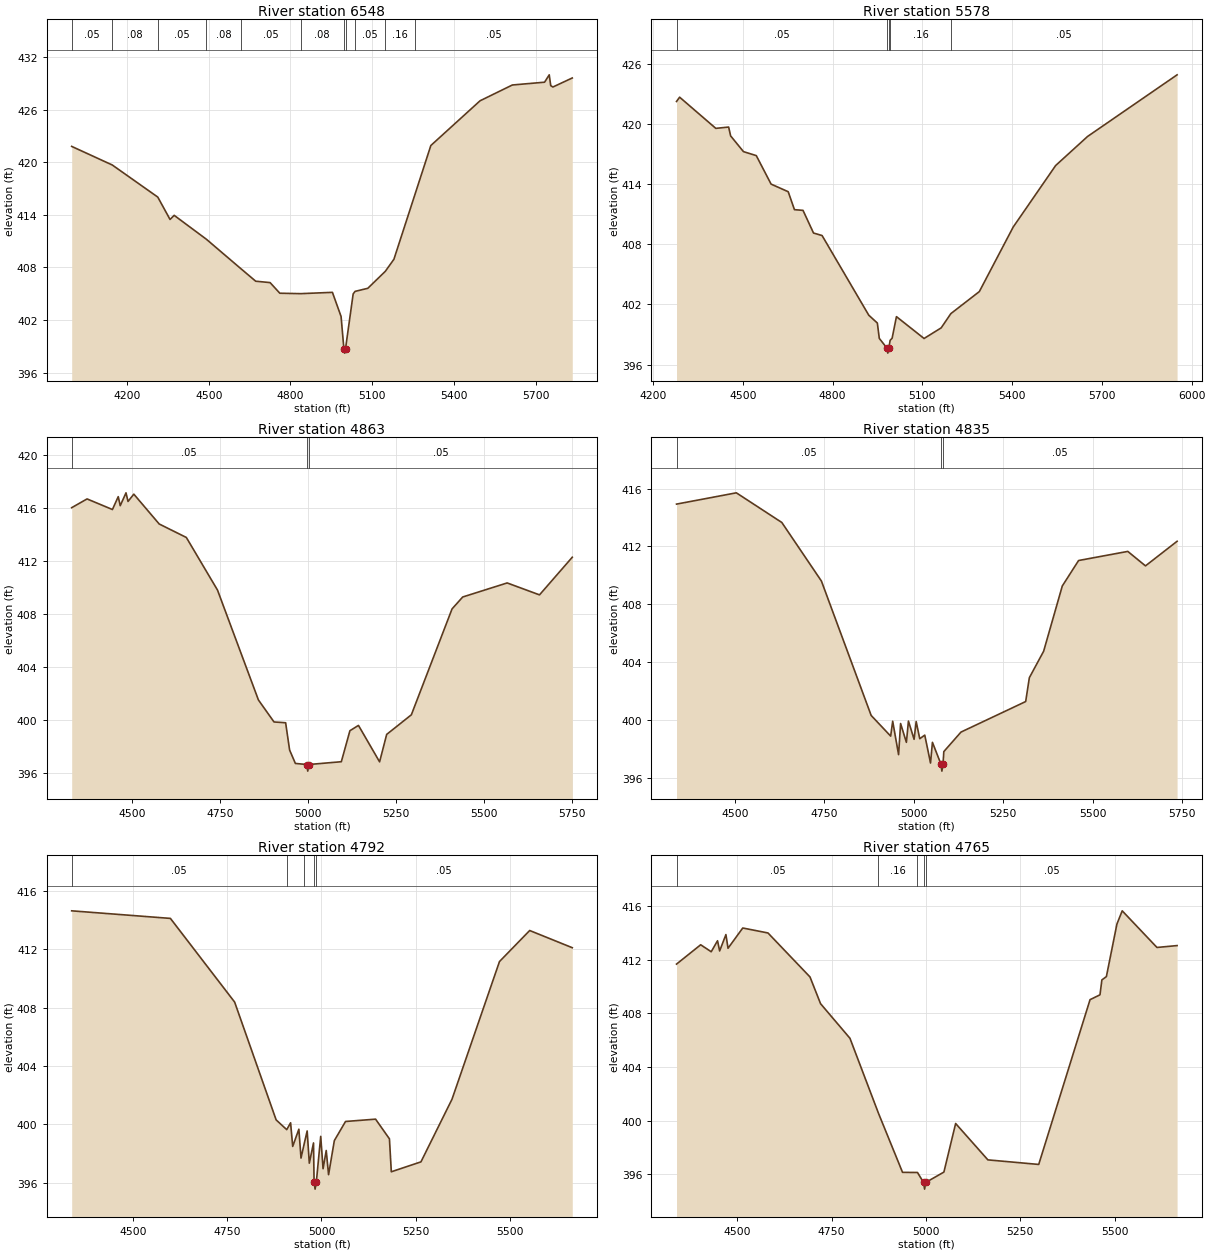
Type RM Length L Ch R = 1 ,6548    ,970,970,970
BEGIN DESCRIPTION:
UNT0144 IN SAND CR 12.3
END DESCRIPTION:
XS GIS Cut Line= 3
      3541366.65      10540416.2      3541134.89     10539509.99
      3540741.67     10538697.51
#Sta/Elev= 30
  3996.9   421.8  4145.9  419.68    4313  416.02    4358  413.47  4373.2  413.94
  4491.6  411.21  4619.9  407.81  4672.5  406.43  4725.4  406.27  4761.1  405.06
  4837.2  405.01  4954.2  405.16    4986  402.41  4996.3  398.73  4999.1  398.23
  5002.3  398.73  5030.4  404.98  5037.4  405.27  5084.1  405.62  5148.5  407.56
    5180  408.93  5258.4  416.43  5315.6   421.9  5496.3     427  5614.8   428.8
  5733.2  429.12  5750.3  429.96  5755.8  428.73  5763.7  428.57  5834.9   429.6
#Mann= 11 ,-1 , 0
  3996.9     .05       0  4145.9     .08       0    4313     .05       0
  4491.6     .08       0  4619.9     .05       0  4837.2     .08       0
  4996.3     .07       0  5002.3     .08       0  5037.4     .05       0
  5148.5     .16       0  5258.4     .05       0
Bank Sta=4996.3,5002.3
XS Rating Curve= 0 ,0
Exp/Cntr=0.3,0.1

Type RM Length L Ch R = 1 ,5578    ,715,715,715
BEGIN DESCRIPTION:
UNT0144 IN SAND CR 10.0
END DESCRIPTION:
XS GIS Cut Line= 2
      3542290.35     10540238.69      3541213.97     10538958.33
#Sta/Elev= 30
  4278.7  422.24  4289.1  422.67    4410  419.56  4452.9  419.69  4459.5  418.81
  4502.4  417.24  4545.3  416.84  4594.7     414  4651.9  413.24  4672.8  411.45
  4701.4  411.38  4736.5  409.12  4765.1  408.87  4921.2  400.92  4949.8  400.14
  4956.3  398.61  4981.9  397.64  4984.7  397.14  4987.9  397.64  4992.6  398.42
  4999.2  398.63  5013.6  400.78  5105.9   398.6  5163.1  399.66  5195.4  401.08
  5290.6  403.28  5403.8  409.72  5545.5  415.85  5652.2  418.75  5951.4   424.9
#Mann= 5 ,-1 , 0
  4278.7     .05       0  4981.9     .07       0  4987.9     .05       0
  4992.6     .16       0  5195.4     .05       0
Bank Sta=4981.9,4987.9
XS Rating Curve= 0 ,0
Exp/Cntr=0.3,0.1

Type RM Length L Ch R = 1 ,4863    ,28,28,28
BEGIN DESCRIPTION:
UNT0144 IN SAND CR 9.3
END DESCRIPTION:
XS GIS Cut Line= 6
      3542851.55     10539479.05      3542280.61     10539182.84
      3542242.85     10539137.27       3541899.1     10539107.32
      3541793.63     10539068.26      3541612.67     10538879.48
#Sta/Elev= 30
  4328.8  416.04  4372.5   416.7  4444.5   415.9    4461  416.87  4466.7  416.19
  4483.1  417.16  4488.8  416.51  4505.3  417.06  4577.3  414.81  4654.5  413.79
    4743  409.82  4859.2  401.53  4903.5  399.87  4936.5  399.81  4947.8  397.75
  4964.2  396.74  4996.6  396.66  4999.3  396.16  5002.6  396.66  5094.7  396.87
  5119.1  399.21  5143.4  399.61  5203.4  396.86  5223.5  398.93  5293.6  400.41
  5409.2   408.4  5439.5   409.3  5565.8  410.36  5657.6  409.46  5750.7   412.3
#Mann= 3 ,-1 , 0
  4328.8     .05       0  4996.6     .03       0  5002.6     .05       0
Bank Sta=4996.6,5002.6
XS Rating Curve= 0 ,0
Exp/Cntr=0.3,0.1

Type RM Length L Ch R = 1 ,4835    ,43,43,43
BEGIN DESCRIPTION:
UNT0144 IN SAND CR 9.0
END DESCRIPTION:
XS GIS Cut Line= 6
      3542874.41     10539454.21      3542260.43      10539132.3
      3542207.26     10539114.94      3541892.59     10539089.98
      3541810.12     10539050.92      3541638.65     10538880.53
#Sta/Elev= 30
  4337.3  414.93  4504.4  415.71  4631.4  413.66    4742  409.61  4880.9  400.32
  4935.4  398.89    4941  399.92  4957.5  397.61  4963.1  399.76  4979.3  398.46
    4985  399.93  5000.8  398.67  5006.6   399.9  5016.6  398.71  5030.6  398.96
  5046.7  397.03    5052  398.46  5075.6  396.97  5078.4  396.47  5081.6  396.97
  5083.8  397.82  5131.8  399.17  5312.4  401.28  5322.7  402.93  5362.6  404.76
  5414.7  409.27  5460.2  411.03  5597.6  411.66    5647  410.66  5735.3  412.36
#Mann= 3 ,-1 , 0
  4337.3     .05       0  5075.6     .03       0  5081.6     .05       0
Bank Sta=5075.6,5081.6
XS Rating Curve= 0 ,0
Exp/Cntr=0.3,0.1

Type RM Length L Ch R = 1 ,4792    ,27,27,27
BEGIN DESCRIPTION:
UNT0144 IN SAND CR 9.1
END DESCRIPTION:
XS GIS Cut Line= 6
      3542906.22     10539440.33      3542300.01     10539108.49
      3542233.17     10539081.58       3541898.1     10539060.75
      3541839.07     10539032.97      3541733.15     10538911.43
#Sta/Elev= 30
  4338.4  414.65  4599.9  414.13    4770  408.39  4879.9  400.31    4908  399.64
  4918.2  400.11  4923.8  398.49  4940.1  399.67  4945.8  397.69  4953.8  398.62
  4962.1  399.55  4967.8  397.34  4978.9  398.73  4980.4  396.06  4983.1  395.56
  4986.4  396.06    4998  399.18  5004.2  396.96  5012.6  398.21  5018.8  396.55
  5034.1  398.89  5063.7   400.2  5143.3  400.36    5180  399.01    5185  396.75
  5263.5  397.43  5345.8  401.73  5471.5  411.17  5551.5   413.3  5664.3  412.12
#Mann= 5 ,-1 , 0
  4338.4     .05       0    4908     .16       0  4953.8     .05       0
  4980.4    .035       0  4986.4     .05       0
Bank Sta=4980.4,4986.4
XS Rating Curve= 0 ,0
Exp/Cntr=0.3,0.1

Type RM Length L Ch R = 1 ,4765    ,428,428,428
BEGIN DESCRIPTION:
UNT0144 IN SAND CR 9.2
END DESCRIPTION:
XS GIS Cut Line= 6
      3542932.29     10539416.56       3542367.2     10539130.11
      3542315.11     10539083.23      3542234.38     10539046.77
      3541893.24     10539025.94      3541757.81     10538890.51
#Sta/Elev= 30
  4339.6  411.66  4403.6   413.1  4431.5  412.58  4448.2   413.4  4453.8  412.64
  4470.4  413.86    4476  412.84    4515  414.35  4581.8  413.98  4693.1   410.7
    4721  408.71  4798.9  406.13    4874  400.57  4938.1  396.14  4977.7  396.13
  4993.7  395.39  4996.5  394.89  4999.7  395.39  5047.6  396.16  5078.7  399.78
  5164.1  397.07  5298.7  396.73  5434.6  409.01  5460.9  409.37  5465.9  410.48
  5477.9  410.73  5505.7  414.64  5519.8  415.63  5611.8   412.9  5665.1  413.04
#Mann= 5 ,-1 , 0
  4339.6     .05       0    4874     .16       0  4977.7     .05       0
  4993.7    .035       0  4999.7     .05       0
Bank Sta=4993.7,4999.7
XS Rating Curve= 0 ,0
Exp/Cntr=0.3,0.1

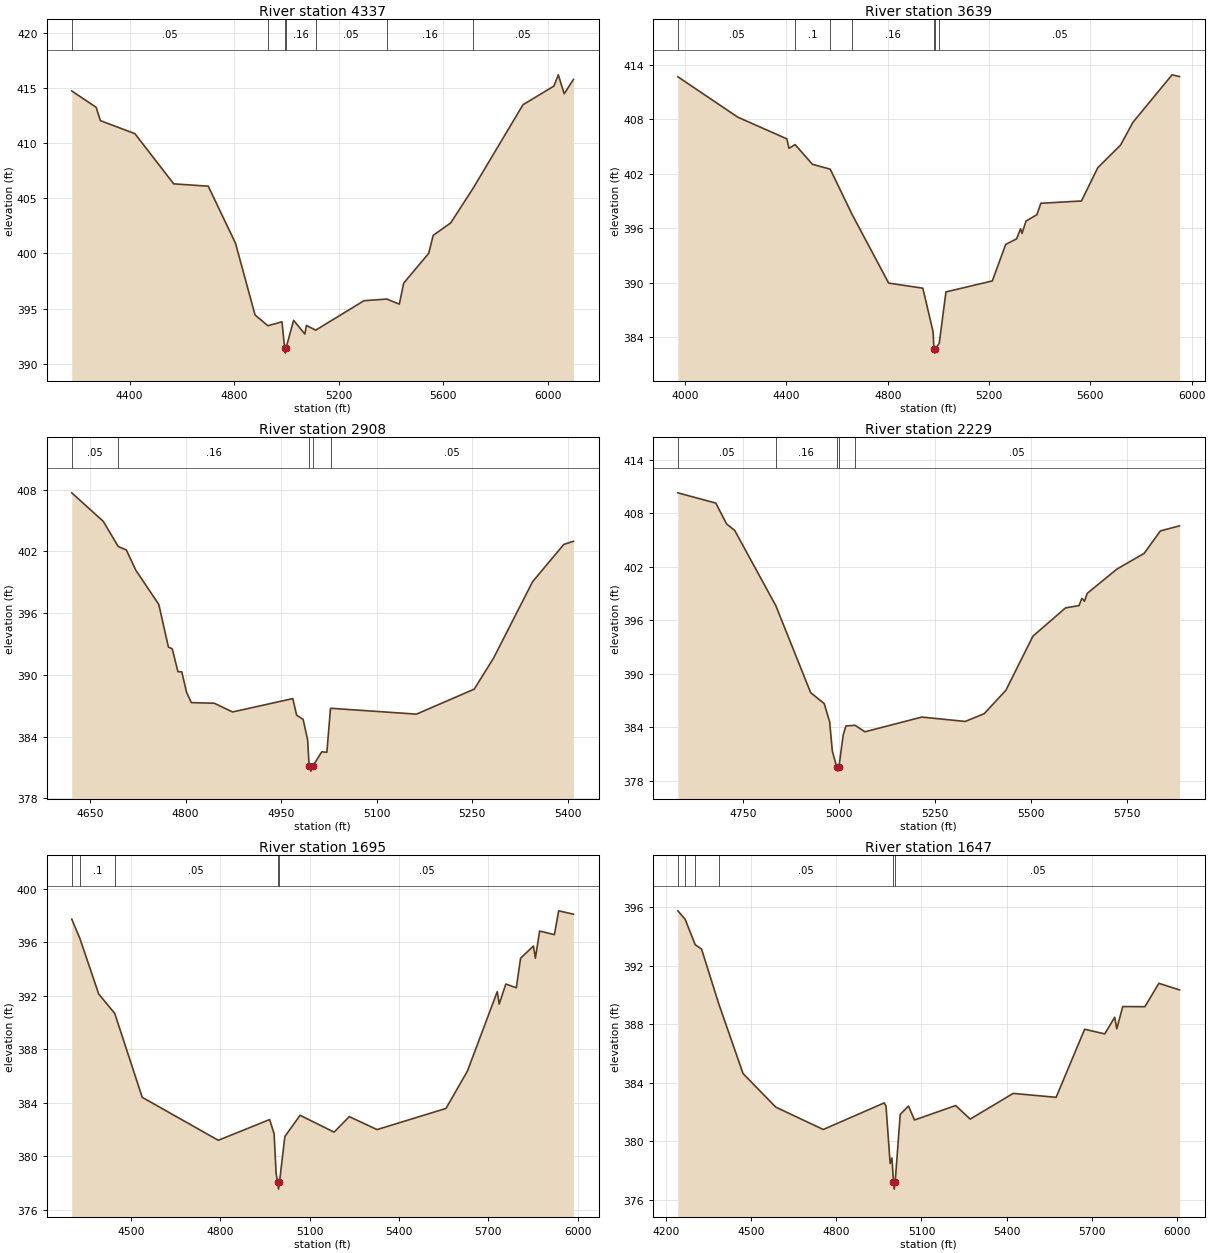
Type RM Length L Ch R = 1 ,4337    ,698,698,698
BEGIN DESCRIPTION:
UNT0144 IN SAND CR 7.0
END DESCRIPTION:
XS GIS Cut Line= 4
      3543089.55     10539611.17      3542742.11     10538954.89
      3542565.23     10538649.33      3542204.11     10537909.72
#Sta/Elev= 30
  4178.9  414.72  4272.1  413.24  4288.4  412.03  4420.4  410.85  4568.8   406.3
  4700.8  406.09  4805.1  400.92  4879.9  394.42    4929  393.44    4983   393.8
  4992.8  391.46  4995.6  390.96  4998.8  391.46  5027.4  393.93  5070.4  392.69
  5076.2  393.47  5111.9  393.04  5296.4  395.71  5383.7  395.86  5431.6   395.4
  5448.5  397.31  5544.2  400.01  5561.1  401.63  5628.1  402.76  5713.6  405.89
  5904.6  413.47  6022.8  415.16  6039.7  416.18  6062.1  414.46  6097.6  415.76
#Mann= 7 ,-1 , 0
  4178.9     .05       0    4929     .16       0  4992.8     .07       0
  4998.8     .16       0  5111.9     .05       0  5383.7     .16       0
  5713.6     .05       0
Bank Sta=4992.8,4998.8
XS Rating Curve= 0 ,0
Exp/Cntr=0.3,0.1

Type RM Length L Ch R = 1 ,3639    ,731,731,731
BEGIN DESCRIPTION:
UNT0144 IN SAND CR 5.0
END DESCRIPTION:
XS GIS Cut Line= 4
      3543801.34     10539482.67      3543273.56     10538725.72
      3543228.43     10538475.72      3542822.16     10537781.24
#Sta/Elev= 30
  3970.8  412.68  4207.6  408.23  4401.3  405.84  4410.1   404.8    4434  405.21
  4502.5  403.04  4572.8   402.5  4658.9  397.53  4803.5  389.96  4938.4   389.4
    4979  384.59  4982.2  382.75  4984.9  382.25  4988.2  382.75  5003.2  383.33
  5029.8  388.99  5212.9   390.2  5265.7  394.22  5308.7  394.83  5324.4  395.95
  5330.2  395.43  5345.9  396.79  5388.9  397.49  5404.6  398.75  5564.9     399
  5629.3  402.66  5719.4  405.16  5768.2  407.66  5922.7  412.89  5952.2   412.7
#Mann= 7 ,-1 , 0
  3970.8     .05       0    4434      .1       0  4572.8     .05       0
  4658.9     .16       0  4982.2     .07       0  4988.2     .16       0
  5003.2     .05       0
Bank Sta=4982.2,4988.2
XS Rating Curve= 0 ,0
Exp/Cntr=0.3,0.1

Type RM Length L Ch R = 1 ,2908    ,679,679,679
BEGIN DESCRIPTION:
UNT0144 IN SAND CR 4.0
END DESCRIPTION:
XS GIS Cut Line= 3
      3543992.12     10538641.67      3543792.11     10538341.64
       3543642.1     10537941.63
#Sta/Elev= 30
  4621.2  407.69  4670.8  404.91  4694.2  402.47  4706.9  402.14  4721.9  400.16
  4757.9  396.84    4773   392.7    4779  392.53    4788   390.3    4794  390.29
  4801.5   388.3    4809   387.3  4845.1  387.24  4873.6  386.39  4968.3  387.69
  4974.3  386.08  4984.5  385.67  4991.6  383.68  4993.9  381.14  4996.7  380.64
  4999.9  381.14  5013.8  382.52  5021.8  382.47  5027.5  386.75  5162.5  386.18
  5253.2  388.61  5283.5  391.62  5344.9  399.06  5393.9  402.68    5409  402.98
#Mann= 5 ,-1 , 0
  4621.2     .05       0  4694.2     .16       0  4993.9     .07       0
  4999.9     .16       0  5027.5     .05       0
Bank Sta=4993.9,4999.9
XS Rating Curve= 0 ,0
Exp/Cntr=0.3,0.1

Type RM Length L Ch R = 1 ,2229    ,534,534,534
BEGIN DESCRIPTION:
UNT0144 IN SAND CR 2.0
END DESCRIPTION:
XS GIS Cut Line= 2
      3544561.73     10538302.08      3543641.63     10537371.57
#Sta/Elev= 30
  4578.7  410.29  4677.8  409.14    4706   406.8  4727.2  406.07  4834.5  397.62
  4925.2  387.89  4960.6  386.66  4974.7  384.62  4981.8  381.32    4993  379.59
  4995.7  379.09    4999  379.59  5010.1  383.15  5017.1  384.15    5041  384.23
  5066.7   383.5  5215.1  385.15  5328.3  384.66  5377.8  385.53  5434.4  388.15
  5505.1  394.23    5590  397.39  5625.3  397.65  5632.4  398.46  5639.4  398.14
  5646.5  399.02  5724.3  401.75    5795   403.5  5837.4  406.02  5887.3  406.59
#Mann= 5 ,-1 , 0
  4578.7     .05       0  4834.5     .16       0    4993     .07       0
    4999     .16       0    5041     .05       0
Bank Sta=4993,4999
XS Rating Curve= 0 ,0
Exp/Cntr=0.3,0.1

Type RM Length L Ch R = 1 ,1695    ,48,48,48
BEGIN DESCRIPTION:
UNT0144 IN SAND CR 1.3
END DESCRIPTION:
XS GIS Cut Line= 4
      3545048.18     10538319.44      3544787.77     10537879.35
      3544071.62     10537402.78      3543828.06     10537205.86
#Sta/Elev= 30
  4300.9  397.73  4328.5  396.27  4391.3  392.14  4445.3  390.68  4537.6  384.41
    4793   381.2  4965.4  382.75  4980.4  381.69  4987.2  378.73  4992.4  378.05
  4995.2  377.55  4998.4  378.05  5016.5  381.48  5067.6  383.07  5181.8  381.81
  5232.9  382.97  5326.1     382  5557.5  383.58  5629.6  386.37  5729.8  392.31
  5736.3  391.38  5758.6  392.88  5793.8   392.6  5808.2  394.81  5851.3  395.72
  5857.8  394.81  5872.1  396.84  5921.7  396.57  5936.1  398.35  5985.7   398.1
#Mann= 5 ,-1 , 0
  4300.9     .16       0  4328.5      .1       0  4445.3     .05       0
  4992.4     .03       0  4998.4     .05       0
Bank Sta=4992.4,4998.4
XS Rating Curve= 0 ,0
Exp/Cntr=0.3,0.1

Type RM Length L Ch R = 1 ,1647    ,52,52,52
BEGIN DESCRIPTION:
UNT0144 IN SAND CR 1.2
END DESCRIPTION:
XS GIS Cut Line= 5
      3545100.27     10538319.44      3544813.81     10537861.12
      3544582.04     10537689.24      3544095.06     10537376.74
      3543846.11     10537114.83
#Sta/Elev= 30
  4240.9  395.77  4266.5   395.2  4302.3  393.45  4324.5  393.16  4385.1  389.42
  4470.8  384.64  4586.3  382.34  4753.8  380.81  4968.8  382.63    4975   382.4
  4989.6  378.48  4995.9  378.86  5001.3  377.23    5004  376.73  5007.3  377.23
  5025.1  381.84  5054.3  382.42  5075.3  381.46  5220.6  382.45  5271.8  381.52
  5423.5  383.28  5574.8  383.01  5675.4  387.67  5746.2  387.35  5781.4  388.49
  5788.7   387.7  5809.7  389.22  5887.8  389.21  5937.1  390.81  6009.9  390.36
#Mann= 6 ,-1 , 0
  4240.9     .16       0  4266.5     .05       0  4302.3      .1       0
  4385.1     .05       0  5001.3     .03       0  5007.3     .05       0
Bank Sta=5001.3,5007.3
XS Rating Curve= 0 ,0
Exp/Cntr=0.3,0.1

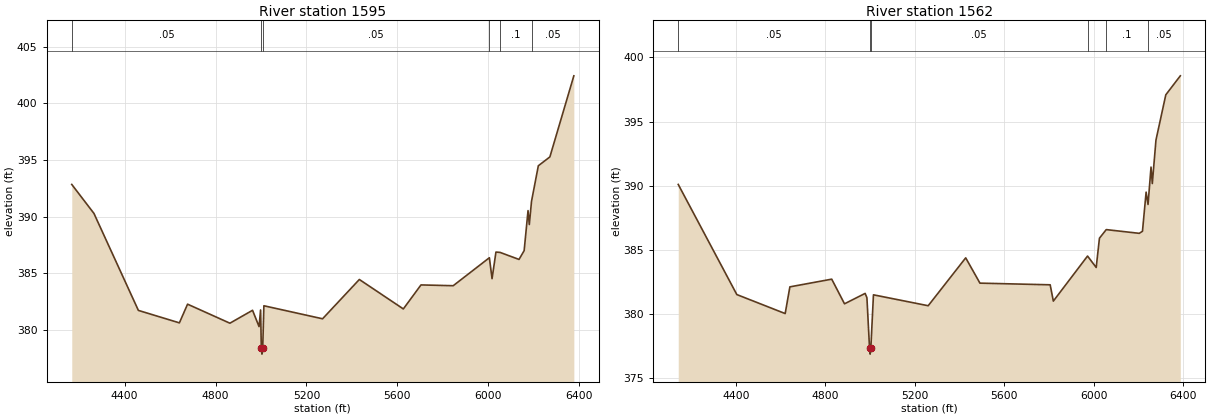
Type RM Length L Ch R = 1 ,1595    ,33,33,33
BEGIN DESCRIPTION:
UNT0144 IN SAND CR 1.0
END DESCRIPTION:
XS GIS Cut Line= 6
      3545189.67     10538320.31      3544876.31      10537848.1
      3544582.04     10537621.53      3544191.42     10537379.35
      3543904.96     10537069.45      3543553.41     10536900.19
#Sta/Elev= 30
  4167.2  392.84  4264.9  390.28  4460.4  381.72  4640.9  380.62  4676.9  382.27
  4863.3  380.59  4962.9  381.73  4991.6  380.29  4998.3  381.76  5001.6  378.36
  5004.3  377.86  5007.6  378.36  5012.8  382.13  5271.1  380.98    5433  384.45
  5626.6  381.85  5704.3  383.97  5846.1   383.9  6005.3  386.37  6017.1  384.52
  6034.2  386.87  6052.4  386.84  6135.8  386.22  6158.4     387  6175.5  390.53
  6181.1   389.3  6190.8  391.35  6220.8  394.49  6271.6  395.27  6377.1  402.43
#Mann= 6 ,-1 , 0
  4167.2     .05       0  5001.6     .03       0  5007.6     .05       0
  6005.3     .08       0  6052.4      .1       0  6190.8     .05       0
Bank Sta=5001.6,5007.6
XS Rating Curve= 0 ,0
Exp/Cntr=0.3,0.1

Type RM Length L Ch R = 1 ,1562    ,0,0,0
BEGIN DESCRIPTION:
UNT0144 IN SAND CR 1.1
END DESCRIPTION:
XS GIS Cut Line= 6
      3545233.08     10538303.83      3544917.98     10537832.47
      3544615.89     10537608.51      3544217.46     10537361.12
      3543923.19     10537043.41      3543569.74     10536856.29
#Sta/Elev= 30
  4141.9   390.1  4403.9  381.52  4620.1  380.04  4641.1  382.12  4828.2  382.72
  4885.4   380.8  4977.6  381.61  4985.6  381.27  4997.2  377.38  4999.9  376.88
  5003.2  377.38  5014.8   381.5  5259.6  380.65  5427.3  384.38    5491  382.41
    5805  382.28  5819.2  381.01  5972.1  384.52  6010.8  383.63  6025.3  385.91
  6055.8  386.58  6203.2  386.29  6217.7  386.45    6234   389.5  6242.6  388.54
    6256  391.45  6261.7  390.17    6278  393.55    6322  397.08  6386.9  398.56
#Mann= 6 ,-1 , 0
  4141.9     .05       0  4997.2     .03       0  5003.2     .05       0
  5972.1     .08       0  6055.8      .1       0  6242.6     .05       0
Bank Sta=4997.2,5003.2
XS Rating Curve= 0 ,0
Exp/Cntr=0.3,0.1

Chan Stop Cuts=-1
Use User Specified Reach Order=0
Composite Channel Slope=5