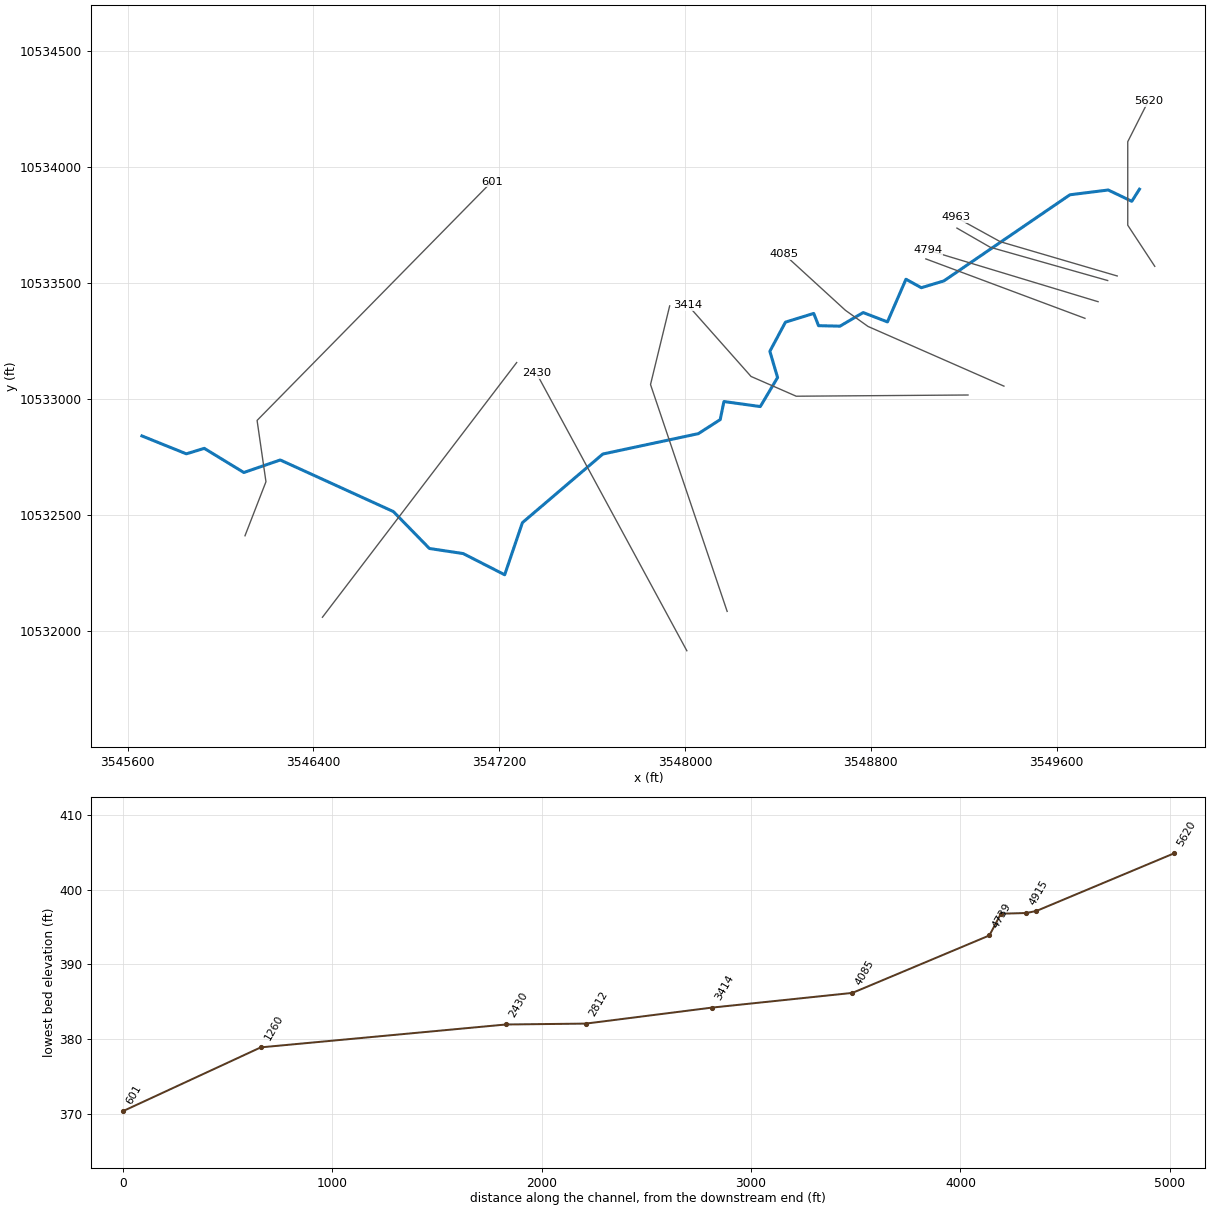
--- UNT0146 IN SAND CR.prj (project) ---

Proj Title=UNT0146 IN SAND CR Base Level Engineering
Current Plan=p01
Default Exp/Contr=0.3,0.1
English Units
Geom File=g01
Flow File=f01
Plan File=p01
Y Axis Title=Elevation
X Axis Title(PF)=Main Channel Distance
X Axis Title(XS)=Station
BEGIN DESCRIPTION:
UNT0146 IN SAND CR
END DESCRIPTION:
DSS Export Rating Curves= 0
DSS Export Rating Curve Sorted= 0
DSS Export Volume Flow Curves= 0
DXF OffsetX= 0
DXF OffsetY= 0
DXF ScaleX= 1
DXF ScaleY= 10

--- UNT0146 IN SAND CR.p01 (plan) ---

Plan Title=Multiple Run
Short Identifier=Multiple
Geom File=g01
Flow File=f01
Subcritical Flow
K Sum by GR= 0
Std Step Tol= 0.01
Critical Tol= 0.01
Num of Std Step Trials= 20
Max Error Tol= 0.3
Flow Tol Ratio= 0.001
Split Flow NTrial= 30
Split Flow Tol= 0.02
Split Flow Ratio= 0.02
Log Output Level= 0
Friction Slope Method= 1
Unsteady Friction Slope Method= 2
Unsteady Bridges Friction Slope Method= 1
Parabolic Critical Depth
Global Vel Dist=  1 , 1 , 1
Global Log Level= 0
CheckData=True
Encroach Param= -1, 0, 0, 0
BEGIN DESCRIPTION:
Multiple Run
END DESCRIPTION:

--- UNT0146 IN SAND CR.f01 (steady flow) ---

Flow Title=Multiple
Number of Profiles=7
Profile Names=10-year,25-year,50-year,1pct_min,100-year,1pct_plu,500-year
River Rch & RM= UNT0146 IN SAND ,Reach-1,5620
     469     616     732     638     863    1167    1192
River Rch & RM= UNT0146 IN SAND ,Reach-1,4085
     656     879    1058     931    1259    1703    1777
River Rch & RM= UNT0146 IN SAND ,Reach-1,2812
     982    1347    1649    1474    1993    2695    2901
Boundary for River Rch & Prof#=UNT0146 IN SAND ,Reach-1,1
Up Type=0
Dn Type=3
Dn Slope=0.005
Boundary for River Rch & Prof#=UNT0146 IN SAND ,Reach-1,2
Up Type=0
Dn Type=3
Dn Slope=0.005
Boundary for River Rch & Prof#=UNT0146 IN SAND ,Reach-1,3
Up Type=0
Dn Type=3
Dn Slope=0.005
Boundary for River Rch & Prof#=UNT0146 IN SAND ,Reach-1,4
Up Type=0
Dn Type=3
Dn Slope=0.005
Boundary for River Rch & Prof#=UNT0146 IN SAND ,Reach-1,5
Up Type=0
Dn Type=3
Dn Slope=0.005
Boundary for River Rch & Prof#=UNT0146 IN SAND ,Reach-1,6
Up Type=0
Dn Type=3
Dn Slope=0.005
Boundary for River Rch & Prof#=UNT0146 IN SAND ,Reach-1,7
Up Type=0
Dn Type=3
Dn Slope=0.005

--- UNT0146 IN SAND CR.g01 (geometry) ---

Geom Title=Existing Conditions

River Reach=UNT0146 IN SAND ,Reach-1
Reach XY= 30
      3549955.89     10533903.67      3549922.93     10533851.68
      3549821.64     10533900.21      3549656.62     10533879.67
      3549113.91     10533508.84      3549017.04     10533479.67
      3548950.89     10533516.13      3548871.14     10533332.54
      3548766.57     10533372.65      3548666.71     10533314.12
      3548574.58     10533316.22      3548553.81     10533369.02
      3548432.14     10533331.39      3548364.93     10533205.96
      3548398.24     10533093.05      3548323.87     10532968.07
      3548167.24     10532989.71      3548151.28     10532911.91
      3548057.19     10532851.49      3547645.96     10532763.72
      3547299.86     10532468.31      3547223.52     10532244.09
      3547044.80     10532335.30      3546899.55     10532357.15
      3546744.45     10532516.04      3546257.56     10532738.12
      3546100.72     10532684.26      3545930.49     10532788.13
      3545853.10     10532764.60      3545662.11     10532841.64

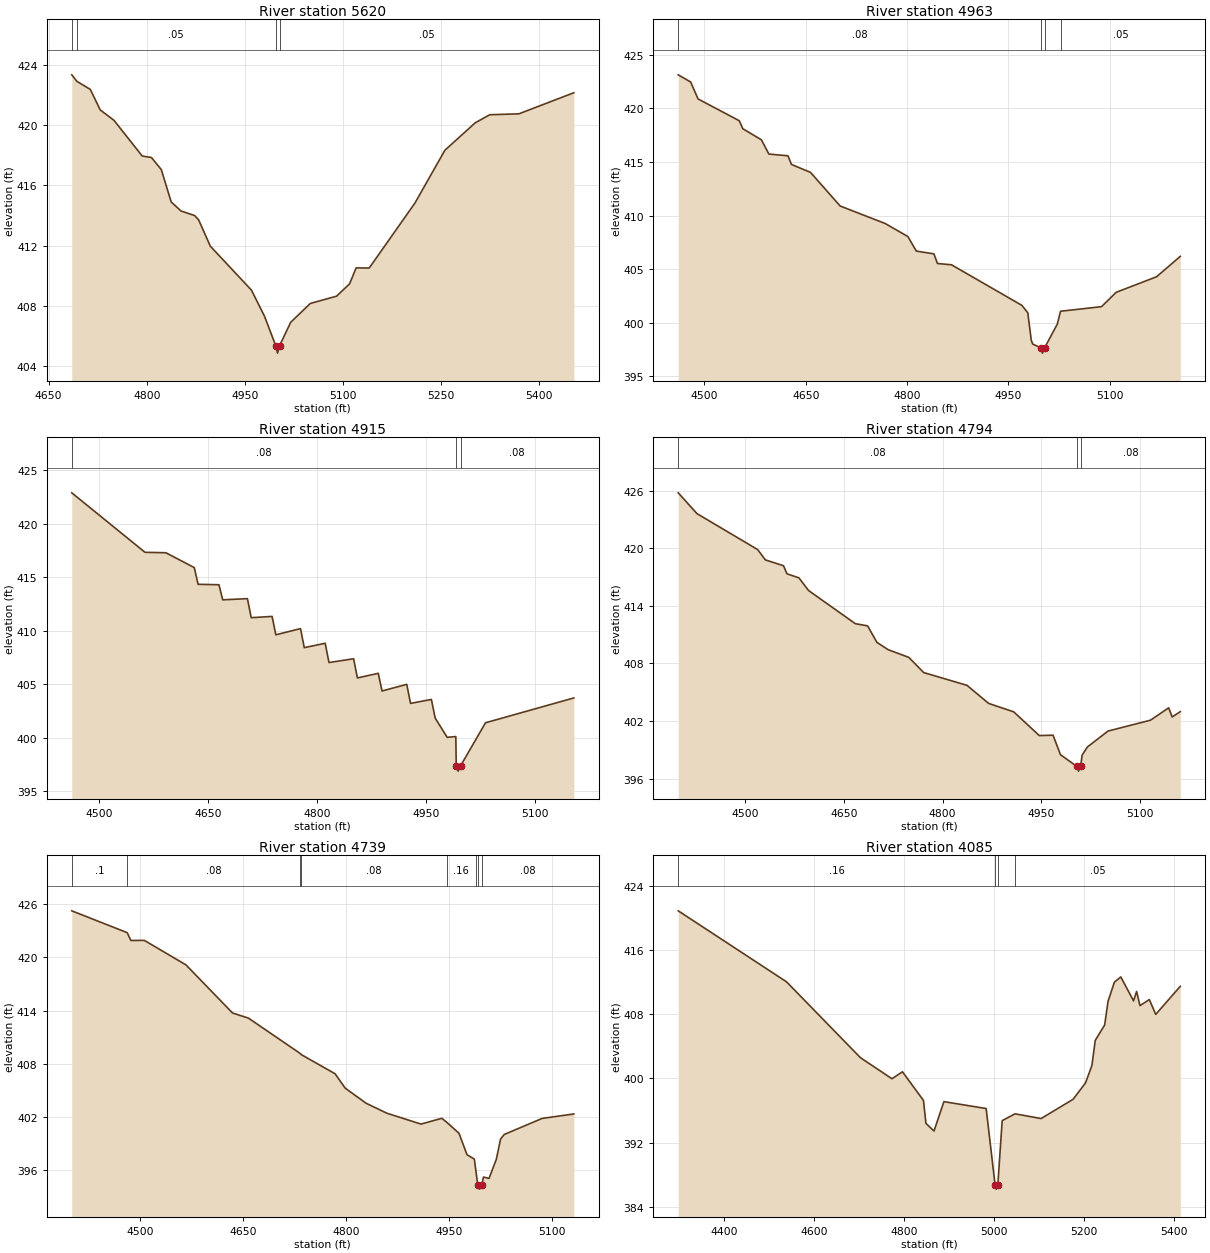
Type RM Length L Ch R = 1,5620,657,657,657
BEGIN DESCRIPTION:
UNT01732 IN SAND CR 3.0
END DESCRIPTION:
XS GIS Cut Line= 4
      3550021.84     10533571.62      3549905.51     10533748.72
      3549905.51     10534108.10      3549994.05     10534283.44
#Sta/Elev= 30
  4685.4  423.34  4693.2  422.91  4713.8  422.37  4728.9  421.01  4749.9  420.32
  4793.1  417.95  4807.2  417.85  4822.3  417.05  4837.4  414.90  4852.4  414.30
  4873.5  413.99  4879.5  413.70  4897.3  411.96  4960.2  409.04  4980.2  407.30
  4997.2  405.36  5000.0  404.86  5003.2  405.36  5020.2  406.91  5050.2  408.16
  5090.2  408.64  5110.2  409.46  5120.2  410.52  5140.2  410.51  5210.2  414.83
  5255.9  418.33  5302.2  420.15  5324.5  420.69  5369.1  420.75  5453.1  422.15
#Mann=4,-1,0
  4685.4    0.08       0  4693.2    0.05       0  4997.2    0.03       0
  5003.2    0.05       0
Bank Sta=4997.2,5003.2
Exp/Cntr=0.3,0.1

Type RM Length L Ch R = 1,4963,48,48,48
BEGIN DESCRIPTION:
UNT01732 IN SAND CR 2.0
END DESCRIPTION:
XS GIS Cut Line= 3
      3549860.26     10533530.16      3549356.79     10533677.73
      3549165.34     10533783.13
#Sta/Elev= 30
  4461.2  423.14  4479.6  422.47  4490.5  420.89  4551.6  418.85  4556.8  418.11
  4584.3  417.07  4595.4  415.74  4623.6  415.58  4628.8  414.77  4657.0  414.03
  4700.9  410.89  4767.7  409.25  4801.1  408.04  4813.6  406.68  4839.7  406.42
  4844.9  405.52  4865.7  405.40  4969.9  401.61  4978.6  400.92  4983.8  398.35
  4985.9  398.00  4997.6  397.65  5000.4  397.15  5003.6  397.65  5022.4  399.87
  5027.1  401.06  5087.8  401.49  5109.5  402.83  5169.2  404.28  5204.4  406.19
#Mann=4,-1,0
  4461.2    0.08       0  4997.6    0.07       0  5003.6    0.08       0
  5027.1    0.05       0
Bank Sta=4997.6,5003.6
Exp/Cntr=0.3,0.1

Type RM Length L Ch R = 1,4915,121,121,121
BEGIN DESCRIPTION:
UNT01732 IN SAND CR 2.1
END DESCRIPTION:
XS GIS Cut Line= 3
      3549819.07     10533510.62      3549313.39     10533653.86
      3549170.20     10533736.30
#Sta/Elev= 30
  4462.2  422.89  4563.0  417.33  4591.7  417.29  4630.8  415.90  4636.0  414.34
  4664.7  414.30  4669.9  412.89  4703.9  413.00  4709.1  411.22  4737.8  411.34
  4743.0  409.62  4776.9  410.20  4782.1  408.42  4810.9  408.83  4816.1  407.03
  4850.0  407.38  4855.2  405.59  4883.9  406.02  4889.1  404.37  4923.1  404.99
  4928.3  403.21  4957.0  403.58  4962.2  401.84  4978.7  400.04  4990.6  400.11
  4991.2  397.38  4993.9  396.88  4997.2  397.38  5031.5  401.40  5153.0  403.72
#Mann=3,-1,0
  4462.2    0.08       0  4991.2    0.07       0  4997.2    0.08       0
Bank Sta=4991.2,4997.2
Exp/Cntr=0.3,0.1

Type RM Length L Ch R = 1,4794,55,55,55
BEGIN DESCRIPTION:
UNT01732 IN SAND CR 1.1
END DESCRIPTION:
XS GIS Cut Line= 2
      3549777.84     10533419.47      3549046.80     10533640.73
#Sta/Elev= 30
  4397.7  425.76  4426.1  423.60  4518.6  419.85  4530.2  418.78  4557.9  418.17
  4563.1  417.33  4581.3  416.91  4596.0  415.59  4667.1  412.14  4685.8  411.91
  4700.0  410.19  4717.1  409.43  4748.5  408.63  4771.1  407.05  4837.0  405.72
  4869.9  403.84  4908.1  402.96  4947.0  400.49  4967.9  400.53  4979.2  398.50
  5003.9  397.29  5006.6  396.79  5009.9  397.29  5012.1  398.45  5020.1  399.30
  5051.5  400.96  5116.1  402.09  5143.8  403.38  5149.1  402.43  5161.5  402.98
#Mann=3,-1,0
  4397.7    0.08       0  5003.9    0.07       0  5009.9    0.08       0
Bank Sta=5003.9,5009.9
Exp/Cntr=0.3,0.1

Type RM Length L Ch R = 1,4739,654,654,654
BEGIN DESCRIPTION:
UNT01732 IN SAND CR 1.0
END DESCRIPTION:
XS GIS Cut Line= 2
      3549721.37     10533347.87      3549036.37     10533603.66
#Sta/Elev= 30
  4400.7  425.24  4481.4  422.78  4486.8  421.90  4506.4  421.91  4567.0  419.15
  4634.8  413.73  4658.0  413.15  4732.4  409.22  4735.1  409.03  4784.2  406.88
  4798.8  405.27  4829.1  403.57  4859.4  402.44  4909.3  401.21  4939.7  401.86
  4946.7  401.42  4964.6  400.18  4976.3  397.76  4987.0  397.26  4988.7  396.26
  4991.9  394.38  4994.7  393.88  4997.9  394.38  5000.3  395.24  5008.4  395.09
  5019.0  397.24  5025.2  399.52  5030.6  400.04  5085.8  401.85  5131.9  402.35
#Mann=8,-1,0
  4400.7     0.1       0  4481.4    0.08       0  4732.4    0.16       0
  4735.1    0.08       0  4946.7    0.16       0  4988.7    0.08       0
  4991.9    0.07       0  4997.9    0.08       0
Bank Sta=4991.9,4997.9
Exp/Cntr=0.3,0.1

Type RM Length L Ch R = 1,4085,671,671,671
BEGIN DESCRIPTION:
UNT0146 IN SAND CR 6.1
END DESCRIPTION:
XS GIS Cut Line= 4
      3549372.56     10533056.00      3548787.45     10533312.96
      3548690.23     10533382.40      3548426.72     10533623.38
#Sta/Elev= 30
  4297.7  420.93  4538.5  412.06  4702.5  402.60  4772.6  399.97  4795.9  400.84
  4842.6  397.26  4848.1  394.40  4866.0  393.44  4888.0  397.11  4981.9  396.25
  5001.8  386.69  5004.5  386.19  5007.8  386.69  5017.5  394.74  5046.1  395.59
  5104.0  395.00  5175.0  397.40  5202.7  399.45  5216.9  401.63  5224.3  404.76
  5245.2  406.68  5252.7  409.63  5266.8  412.02  5281.0  412.68  5309.4  409.69
  5316.2  410.87  5323.6  409.10  5344.5  409.85  5358.7  408.00  5413.3  411.51
#Mann=4,-1,0
  4297.7    0.16       0  5001.8    0.07       0  5007.8    0.16       0
  5046.1    0.05       0
Bank Sta=5001.8,5007.8
Exp/Cntr=0.3,0.1

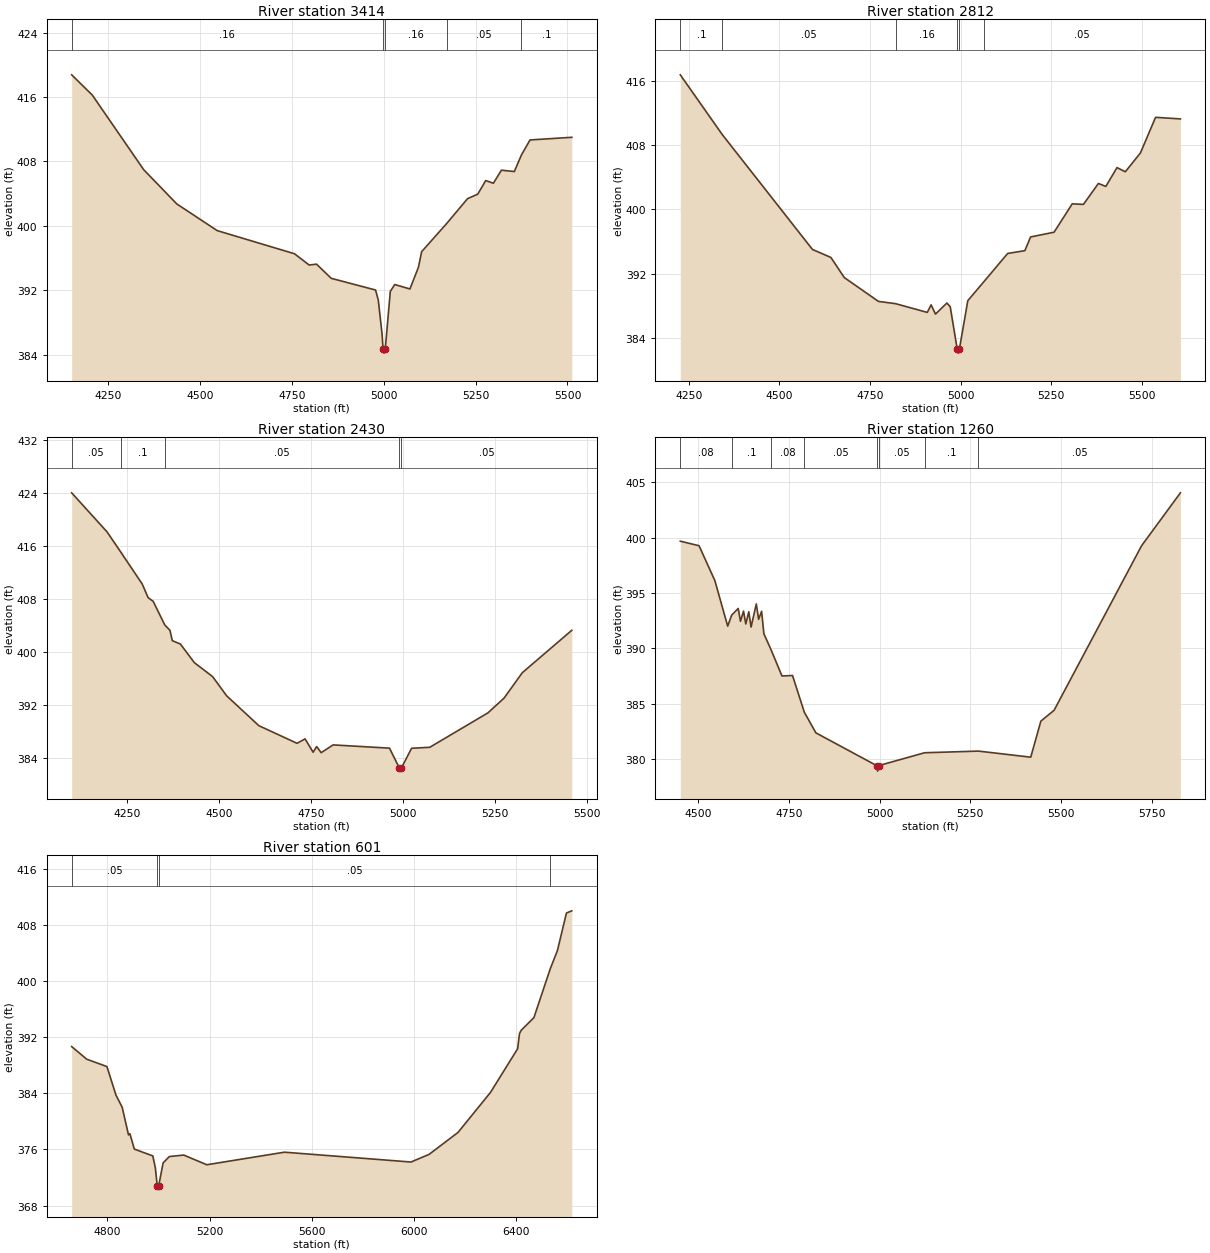
Type RM Length L Ch R = 1,3414,602,602,602
BEGIN DESCRIPTION:
UNT0146 IN SAND CR 6.0
END DESCRIPTION:
XS GIS Cut Line= 4
      3549218.04     10533017.82      3548478.43     10533012.61
      3548283.98     10533097.68      3548013.14     10533403.25
#Sta/Elev= 30
  4151.5  418.75  4207.4  416.25  4347.4  406.98  4437.4  402.73  4547.4  399.42
  4757.5  396.55  4797.5  395.15  4817.5  395.26  4857.5  393.50  4978.0  392.05
  4985.4  390.81  4995.9  386.49  4998.4  384.72  5001.1  384.22  5004.4  384.72
  5018.1  391.88  5030.2  392.73  5071.5  392.18  5094.5  394.86  5103.4  396.81
  5171.4  400.30  5228.3  403.39  5255.9  403.94  5277.6  405.63  5298.5  405.30
  5320.3  406.92  5355.4  406.75  5374.8  408.81  5398.1  410.67  5511.7  411.00
#Mann=5,-1,0
  4151.5    0.16       0  4998.4    0.07       0  5004.4    0.16       0
  5171.4    0.05       0  5374.8     0.1       0
Bank Sta=4998.4,5004.4
Exp/Cntr=0.3,0.1

Type RM Length L Ch R = 1,2812,382,382,382
BEGIN DESCRIPTION:
UNT0146 IN SAND CR 5.0
END DESCRIPTION:
XS GIS Cut Line= 3
      3548181.15     10532086.36      3547851.29     10533062.93
      3547933.75     10533401.45
#Sta/Elev= 30
  4226.7  416.79  4342.6  409.33  4591.2  395.01  4642.1  394.01  4678.9  391.51
  4773.2  388.53  4820.3  388.25  4907.8  387.16  4918.4  388.10  4930.5  386.95
  4962.0  388.33  4971.1  387.87  4990.4  382.58  4993.2  382.08  4996.4  382.58
  5019.6  388.62  5064.5  391.02  5129.5  394.51  5176.9  394.86  5192.8  396.57
  5257.5  397.16  5307.6  400.70  5338.5  400.63  5379.7  403.24  5400.2  402.87
  5431.1  405.22  5454.0  404.70  5495.7  407.05  5537.4  411.49  5605.9  411.29
#Mann=6,-1,0
  4226.7     0.1       0  4342.6    0.05       0  4820.3    0.16       0
  4990.4    0.07       0  4996.4    0.16       0  5064.5    0.05       0
Bank Sta=4990.4,4996.4
Exp/Cntr=0.3,0.1

Type RM Length L Ch R = 1,2430,1170,1170,1170
BEGIN DESCRIPTION:
UNT0146 IN SAND CR 4.0
END DESCRIPTION:
XS GIS Cut Line= 2
      3548007.56     10531917.06      3547360.82     10533110.71
#Sta/Elev= 30
  4100.2  423.99  4196.4  418.08  4232.8  415.10  4291.6  410.23  4307.8  408.16
  4321.5  407.60  4353.0  404.03  4367.0  403.23  4373.4  401.66  4395.2  401.16
  4433.3  398.34  4482.7  396.24  4520.8  393.34  4608.2  388.83  4711.9  386.16
  4733.8  386.83  4755.6  384.81  4765.1  385.67  4777.5  384.75  4809.9  385.92
  4963.0  385.43  4989.5  382.46  4992.3  381.96  4995.5  382.46  5022.9  385.41
  5072.3  385.56  5230.2  390.76  5273.9  392.98  5323.4  396.82  5457.8  403.23
#Mann=5,-1,0
  4100.2    0.05       0  4232.8     0.1       0  4353.0    0.05       0
  4989.5    0.03       0  4995.5    0.05       0
Bank Sta=4989.5,4995.5
Exp/Cntr=0.3,0.1

Type RM Length L Ch R = 1,1260,659,659,659
BEGIN DESCRIPTION:
UNT0146 IN SAND CR 3.0
END DESCRIPTION:
XS GIS Cut Line= 2
      3546439.04     10532061.18      3547275.17     10533157.53
#Sta/Elev= 30
  4450.5  399.68  4502.2  399.27  4545.8  396.12  4581.2  392.00  4592.2  393.00
  4610.2  393.60  4616.5  392.44  4624.8  393.36  4631.1  392.20  4639.3  393.30
  4645.6  391.92  4660.1  394.01  4666.4  392.62  4674.7  393.34  4681.0  391.31
  4700.3  389.90  4730.8  387.50  4759.9  387.54  4792.5  384.22  4824.3  382.36
  4991.8  379.40  4994.6  378.90  4997.8  379.40  5123.9  380.56  5272.6  380.71
  5416.7  380.16  5444.6  383.42  5481.1  384.40  5722.3  399.27  5829.3  404.05
#Mann=8,-1,0
  4450.5    0.08       0  4592.2     0.1       0  4700.3    0.08       0
  4792.5    0.05       0  4991.8    0.03       0  4997.8    0.05       0
  5123.9     0.1       0  5272.6    0.05       0
Bank Sta=4991.8,4997.8
Exp/Cntr=0.3,0.1

Type RM Length L Ch R = 1,601,0,0,0
BEGIN DESCRIPTION:
UNT0146 IN SAND CR 1.0
END DESCRIPTION:
XS GIS Cut Line= 4
      3546105.70     10532411.88      3546195.98     10532644.52
      3546157.78     10532908.40      3547167.67     10533935.65
#Sta/Elev= 30
  4660.6  390.65  4719.6  388.85  4798.6  387.80  4833.8  383.75  4858.4  381.99
  4882.9  378.08  4888.3  378.25  4905.9  376.05  4978.0  375.08  4988.1  373.37
  4995.2  370.85  4997.9  370.35  5001.2  370.85  5018.4  374.09  5042.8  374.99
  5099.2  375.20  5189.2  373.82  5493.2  375.61  5988.3  374.21  6059.0  375.30
  6172.1  378.42  6299.4  384.13  6405.4  390.34  6412.6  392.49  6419.6  392.98
  6469.1  394.77  6533.1  401.73  6561.0  404.31  6596.4  409.67  6617.3  409.98
#Mann=4,-1,0
  4660.6    0.05       0  4995.2    0.03       0  5001.2    0.05       0
  6533.1     0.1       0
Bank Sta=4995.2,5001.2
Exp/Cntr=0.3,0.1

Chan Stop Cuts=-1