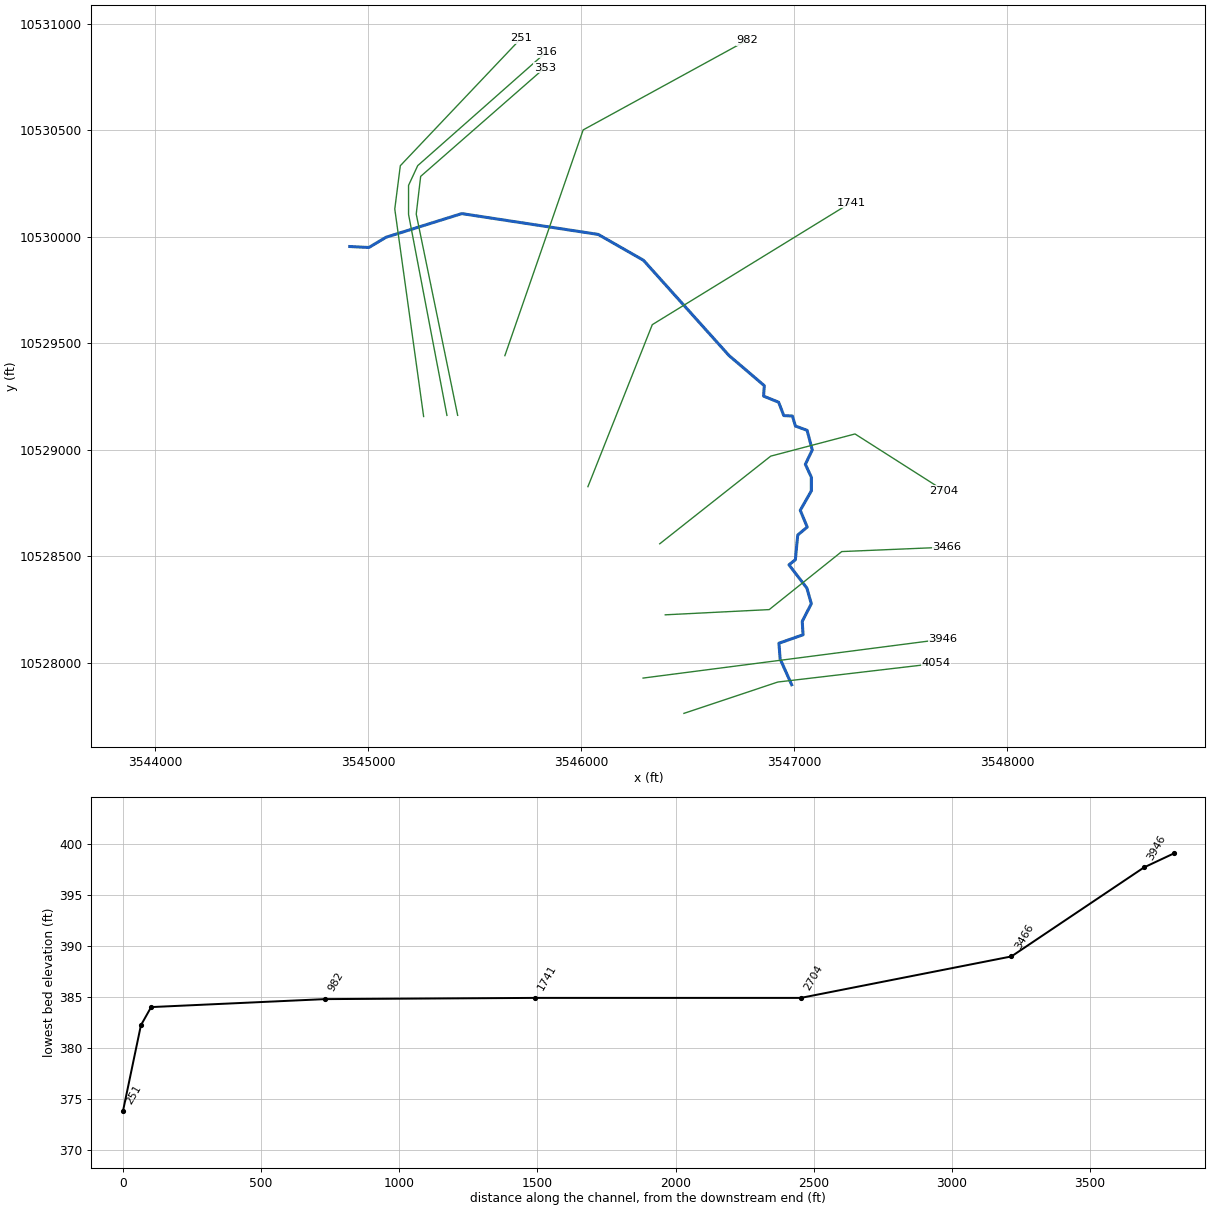
--- UNT0147 IN SAND CR.prj (project) ---

Proj Title=UNT0147 IN SAND CR Base Level Engineering
Current Plan=p01
Default Exp/Contr=0.3,0.1
English Units
Geom File=g01
Flow File=f01
Plan File=p01
BEGIN DESCRIPTION:
UNT0147 IN SAND CR
END DESCRIPTION:

--- UNT0147 IN SAND CR.p01 (plan) ---

Plan Title=Multiple Run
Short Identifier=Multiple
Geom File=g01
Flow File=f01
Subcritical Flow
K Sum by GR= 0
Std Step Tol= 0.01
Critical Tol= 0.01
Num of Std Step Trials= 20
Max Error Tol= 0.3
Flow Tol Ratio= 0.001
Split Flow NTrial= 30
Split Flow Tol= 0.02
Split Flow Ratio= 0.02
Log Output Level= 0
Friction Slope Method= 1
Unsteady Friction Slope Method= 2
Unsteady Bridges Friction Slope Method= 1
Parabolic Critical Depth
Global Vel Dist=  1 , 1 , 1
Global Log Level= 0
CheckData=True
Encroach Param= -1, 0, 0, 0
BEGIN DESCRIPTION:
Multiple Run
END DESCRIPTION:

--- UNT0147 IN SAND CR.f01 (steady flow) ---

Flow Title=Multiple
Number of Profiles=7
Profile Names=10-year,25-year,50-year,1pct_min,100-year,1pct_plu,500-year
River Rch & RM= UNT0147 IN SAND ,Reach-1,4054
     979    1344    1644    1468    1985    2685    2886
Boundary for River Rch & Prof#=UNT0147 IN SAND ,Reach-1,1
Up Type=0
Dn Type=3
Dn Slope=0.005
Boundary for River Rch & Prof#=UNT0147 IN SAND ,Reach-1,2
Up Type=0
Dn Type=3
Dn Slope=0.005
Boundary for River Rch & Prof#=UNT0147 IN SAND ,Reach-1,3
Up Type=0
Dn Type=3
Dn Slope=0.005
Boundary for River Rch & Prof#=UNT0147 IN SAND ,Reach-1,4
Up Type=0
Dn Type=3
Dn Slope=0.005
Boundary for River Rch & Prof#=UNT0147 IN SAND ,Reach-1,5
Up Type=0
Dn Type=3
Dn Slope=0.005
Boundary for River Rch & Prof#=UNT0147 IN SAND ,Reach-1,6
Up Type=0
Dn Type=3
Dn Slope=0.005
Boundary for River Rch & Prof#=UNT0147 IN SAND ,Reach-1,7
Up Type=0
Dn Type=3
Dn Slope=0.005

--- UNT0147 IN SAND CR.g01 (geometry) ---

Geom Title=Existing Conditions

River Reach=UNT0147 IN SAND ,Reach-1
Reach XY= 30
      3546988.40     10527897.09      3546934.23     10528017.74
      3546928.51     10528091.84      3547041.69     10528131.64
      3547037.92     10528194.67      3547080.50     10528277.34
      3547059.74     10528350.60      3546975.49     10528460.07
      3547005.57     10528483.67      3547016.77     10528600.03
      3547061.29     10528637.03      3547028.64     10528715.79
      3547080.61     10528807.04      3547080.59     10528871.32
      3547052.58     10528931.63      3547084.92     10528999.29
      3547060.70     10529091.18      3547005.90     10529111.40
      3546991.92     10529158.29      3546951.31     10529160.37
      3546927.01     10529223.21      3546856.52     10529251.69
      3546859.75     10529300.89      3546694.26     10529442.23
      3546292.79     10529889.28      3546080.11     10530010.80
      3545439.92     10530108.46      3545084.56     10529997.57
      3545003.83     10529949.39      3544914.26     10529953.96

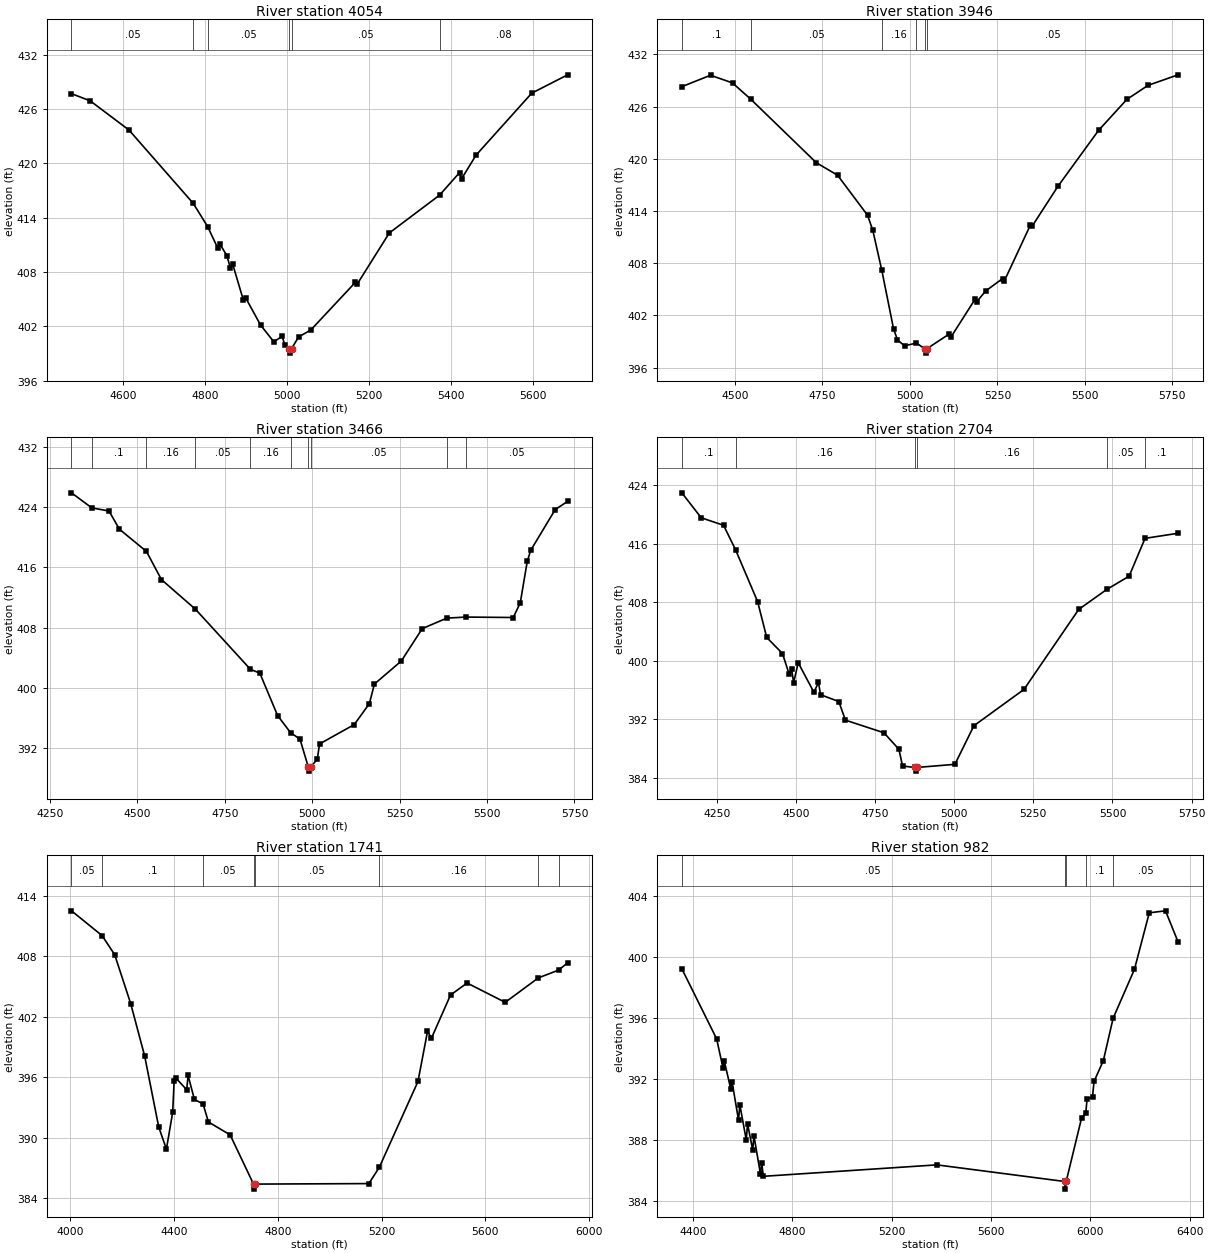
Type RM Length L Ch R = 1,4054,108,108,108
BEGIN DESCRIPTION:
UNT0147 IN SAND CR 8.4
END DESCRIPTION:
XS GIS Cut Line= 3
      3546482.52     10527762.67      3546923.29     10527909.81
      3547664.11     10527996.84
#Sta/Elev= 30
  4473.4  427.68  4519.0  426.89  4613.8  423.66  4770.6  415.56  4805.8  412.99
  4829.7  410.68  4835.0  411.11  4852.5  409.80  4861.3  408.39  4866.6  408.88
  4892.9  404.87  4898.2  405.15  4934.8  402.13  4967.1  400.28  4987.2  400.88
  4994.4  399.90  5004.4  399.53  5007.1  399.03  5010.4  399.53  5027.5  400.81
  5057.7  401.60  5165.7  406.83  5170.8  406.67  5248.9  412.30  5371.4  416.47
  5420.2  418.96  5425.2  418.28  5460.5  420.89  5596.5  427.74  5684.0  429.76
#Mann=6,-1,0
  4473.4    0.05       0  4770.6    0.08       0  4805.8    0.05       0
  5004.4    0.03       0  5010.4    0.05       0  5371.4    0.08       0
Bank Sta=5004.4,5010.4
Exp/Cntr=0.3,0.1

Type RM Length L Ch R = 1,3946,480,480,480
BEGIN DESCRIPTION:
UNT0147 IN SAND CR 8.1
END DESCRIPTION:
XS GIS Cut Line= 2
      3546290.92     10527928.37      3547697.15     10528110.66
#Sta/Elev= 30
  4348.1  428.30  4430.0  429.61  4492.9  428.73  4545.7  426.83  4732.5  419.55
  4793.0  418.12  4878.9  413.51  4893.8  411.78  4919.5  407.19  4953.1  400.46
  4964.4  399.17  4984.6  398.50  5018.7  398.82  5042.1  398.16  5044.8  397.66
  5048.1  398.16  5111.6  399.84  5116.6  399.47  5185.8  403.84  5190.8  403.57
  5216.5  404.81  5265.0  406.24  5270.0  405.98  5344.2  412.39  5349.2  412.26
  5423.4  416.87  5539.2  423.28  5619.8  426.83  5680.3  428.45  5766.1  429.66
#Mann=6,-1,0
  4348.1     0.1       0  4545.7    0.05       0  4919.5    0.16       0
  5018.7    0.05       0  5042.1    0.07       0  5048.1    0.05       0
Bank Sta=5042.1,5048.1
Exp/Cntr=0.3,0.1

Type RM Length L Ch R = 1,3466,762,762,762
BEGIN DESCRIPTION:
UNT0147 IN SAND CR 7.0
END DESCRIPTION:
XS GIS Cut Line= 4
      3546395.03     10528225.24      3546882.85     10528249.79
      3547223.18     10528522.12      3547717.53     10528542.93
#Sta/Elev= 30
  4311.3  425.88  4369.5  423.88  4418.5  423.47  4448.5  421.05  4525.7  418.10
  4568.7  414.36  4665.9  410.43  4823.2  402.45  4850.0  401.95  4900.8  396.32
  4937.8  394.05  4964.8  393.19  4989.0  389.44  4991.8  388.94  4995.0  389.44
  5014.4  390.55  5020.8  392.55  5120.1  395.12  5163.3  397.90  5177.7  400.50
  5254.6  403.55  5314.6  407.86  5385.0  409.25  5439.8  409.39  5574.8  409.33
  5594.9  411.28  5614.9  416.79  5624.9  418.26  5694.9  423.66  5730.4  424.75
#Mann=10,-1,0
  4311.3    0.05       0  4369.5     0.1       0  4525.7    0.16       0
  4665.9    0.05       0  4823.2    0.16       0  4937.8    0.05       0
  4989.0    0.03       0  4995.0    0.05       0  5385.0    0.08       0
  5439.8    0.05       0
Bank Sta=4989,4995
Exp/Cntr=0.3,0.1

Type RM Length L Ch R = 1,2704,963,963,963
BEGIN DESCRIPTION:
UNT0147 IN SAND CR 5.0
END DESCRIPTION:
XS GIS Cut Line= 4
      3546369.03     10528558.59      3546889.84     10528970.04
      3547285.68     10529074.20      3547702.37     10528808.56
#Sta/Elev= 30
  4139.8  422.98  4201.1  419.56  4271.6  418.54  4309.7  415.16  4379.1  408.09
  4407.9  403.18  4457.6  400.98  4478.4  398.20  4486.5  398.82  4492.9  396.99
  4507.3  399.72  4557.0  395.67  4571.4  397.04  4577.8  395.34  4635.6  394.41
  4656.4  391.86  4778.2  390.13  4825.4  387.87  4836.9  385.58  4875.3  385.38
  4878.0  384.88  4881.3  385.38  5002.3  385.81  5062.2  391.09  5220.5  396.07
  5393.4  407.02  5482.6  409.77  5552.5  411.57  5602.9  416.75  5707.0  417.44
#Mann=6,-1,0
  4139.8     0.1       0  4309.7    0.16       0  4875.3    0.07       0
  4881.3    0.16       0  5482.6    0.05       0  5602.9     0.1       0
Bank Sta=4875.3,4881.3
Exp/Cntr=0.3,0.1

Type RM Length L Ch R = 1,1741,759,759,759
BEGIN DESCRIPTION:
UNT0147 IN SAND CR 3.0
END DESCRIPTION:
XS GIS Cut Line= 3
      3546031.97     10528826.77      3546334.04     10529587.17
      3547266.37     10530160.11
#Sta/Elev= 30
  4004.8  412.52  4122.8  410.06  4171.4  408.16  4233.0  403.31  4287.0  398.09
  4341.0  391.06  4370.7  388.85  4395.0  392.52  4400.4  395.57  4408.2  395.88
  4449.0  394.75  4454.3  396.17  4478.6  393.79  4512.0  393.34  4532.6  391.55
  4616.3  390.27  4706.5  385.38  4709.2  384.88  4712.5  385.38  5151.0  385.43
  5191.0  387.03  5340.4  395.57  5377.1  400.54  5392.5  399.88  5465.9  404.16
  5529.8  405.35  5676.6  403.43  5804.4  405.86  5882.1  406.63  5917.3  407.35
#Mann=8,-1,0
  4004.8    0.05       0  4122.8     0.1       0  4512.0    0.05       0
  4706.5   0.033       0  4712.5    0.05       0  5191.0    0.16       0
  5804.4    0.05       0  5882.1     0.1       0
Bank Sta=4706.5,4712.5
Exp/Cntr=0.3,0.1

Type RM Length L Ch R = 1,982,629,629,629
BEGIN DESCRIPTION:
UNT0147 IN SAND CR 1.0
END DESCRIPTION:
XS GIS Cut Line= 3
      3545642.10     10529441.61      3546009.64     10530501.29
      3546778.77     10530922.23
#Sta/Elev= 30
  4354.6  399.20  4494.7  394.61  4520.6  392.68  4525.9  393.13  4551.7  391.32
  4557.0  391.78  4582.9  389.28  4588.1  390.29  4614.0  387.99  4619.3  389.03
  4639.8  387.34  4645.1  388.24  4671.0  385.77  4676.3  386.48  4682.7  385.60
  5381.8  386.35  5896.5  385.26  5899.3  384.76  5902.5  385.26  5965.0  389.45
  5981.2  389.73  5986.8  390.67  6008.6  390.82  6014.8  391.82  6052.2  393.18
  6091.6  395.96  6177.4  399.16  6237.2  402.87  6302.6  403.00  6353.0  400.97
#Mann=5,-1,0
  4354.6    0.05       0  5896.5   0.033       0  5902.5    0.05       0
  5981.2     0.1       0  6091.6    0.05       0
Bank Sta=5896.5,5902.5
Exp/Cntr=0.3,0.1

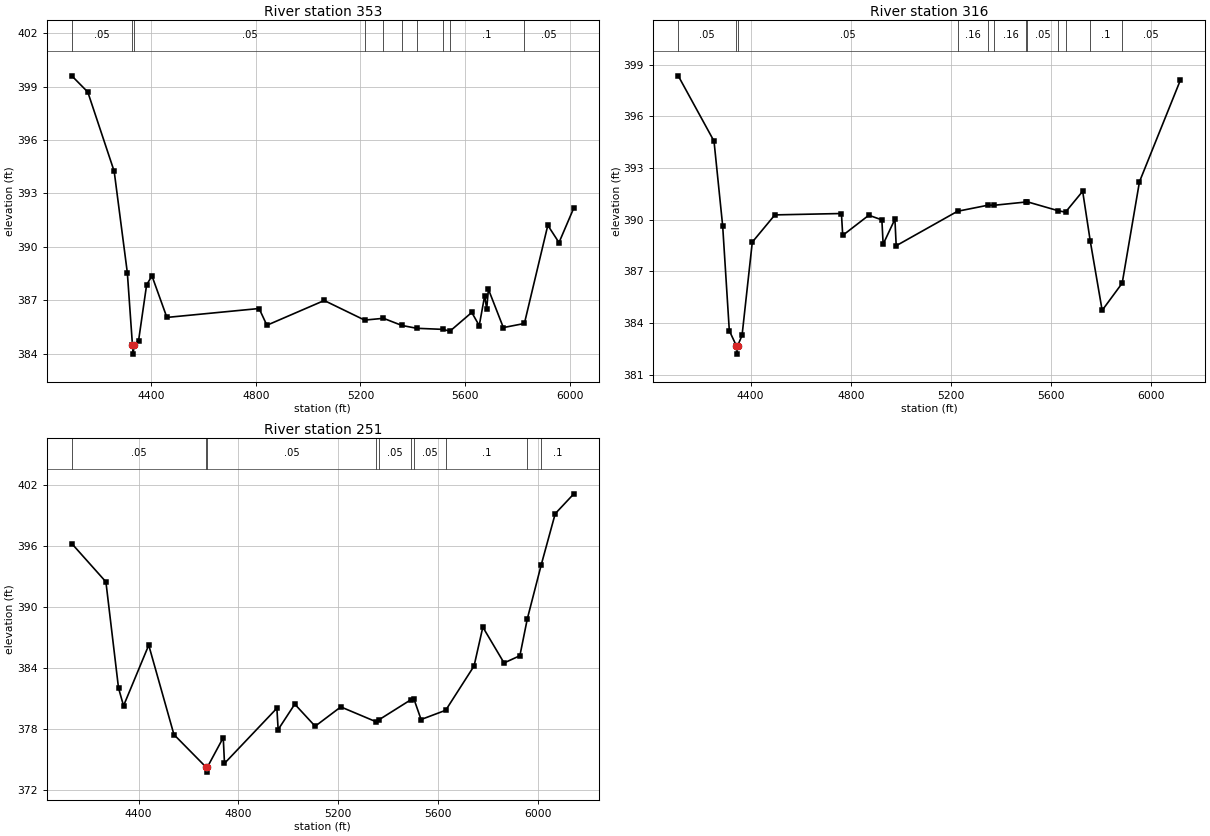
Type RM Length L Ch R = 1,353,37,37,37
BEGIN DESCRIPTION:
UNT0147 IN SAND CR 1.3
END DESCRIPTION:
XS GIS Cut Line= 4
      3545420.53     10529161.66      3545226.08     10530106.14
      3545246.91     10530283.22      3545830.23     10530793.63
#Sta/Elev= 30
  4097.5  399.60  4158.7  398.69  4259.5  394.24  4309.8  388.54  4329.3  384.48
  4332.1  383.98  4335.3  384.48  4352.7  384.74  4383.4  387.87  4403.8  388.37
  4460.8  386.04  4813.0  386.54  4842.8  385.60  5061.8  386.99  5216.0  385.89
  5288.1  385.99  5358.3  385.59  5415.1  385.43  5514.3  385.37  5542.1  385.27
  5625.3  386.32  5653.8  385.58  5674.7  387.26  5682.3  386.51  5688.9  387.62
  5745.9  385.47  5826.3  385.70  5915.7  391.21  5958.5  390.24  6015.2  392.19
#Mann=10,-1,0
  4097.5    0.05       0  4329.3   0.033       0  4335.3    0.05       0
  5216.0    0.16       0  5288.1    0.05       0  5358.3    0.16       0
  5415.1     0.1       0  5514.3    0.05       0  5542.1     0.1       0
  5826.3    0.05       0
Bank Sta=4329.3,4335.3
Exp/Cntr=0.3,0.1

Type RM Length L Ch R = 1,316,65,65,65
BEGIN DESCRIPTION:
UNT0147 IN SAND CR 1.1
END DESCRIPTION:
XS GIS Cut Line= 5
      3545370.18     10529161.33      3545190.09     10530104.41
      3545190.09     10530241.13      3545233.06     10530333.58
      3545836.68     10530866.96
#Sta/Elev= 30
  4110.9  398.35  4253.7  394.56  4288.3  389.64  4314.8  383.56  4342.5  382.70
  4345.2  382.20  4348.5  382.70  4365.7  383.29  4406.5  388.70  4496.7  390.28
  4762.4  390.36  4767.5  389.09  4871.7  390.26  4923.8  389.99  4928.9  388.58
  4975.9  390.03  4981.0  388.49  5225.8  390.49  5346.7  390.84  5373.1  390.84
  5500.6  391.03  5501.8  391.05  5628.1  390.52  5656.9  390.44  5725.4  391.65
  5755.6  388.77  5803.2  384.74  5883.2  386.32  5952.1  392.20  6115.2  398.09
#Mann=12,-1,0
  4110.9    0.05       0  4342.5    0.04       0  4348.5    0.05       0
  5225.8    0.16       0  5346.7    0.05       0  5373.1    0.16       0
  5500.6     0.1       0  5501.8    0.05       0  5628.1     0.1       0
  5656.9    0.05       0  5755.6     0.1       0  5883.2    0.05       0
Bank Sta=4342.5,4348.5
Exp/Cntr=0.3,0.1

Type RM Length L Ch R = 1,251,0,0,0
BEGIN DESCRIPTION:
UNT0147 IN SAND CR 1.2
END DESCRIPTION:
XS GIS Cut Line= 4
      3545260.80     10529156.15      3545125.38     10530130.10
      3545151.42     10530333.22      3545718.13     10530931.12
#Sta/Elev= 30
  4132.6  396.24  4269.4  392.48  4319.9  382.05  4340.1  380.30  4441.0  386.26
  4542.0  377.47  4670.2  374.28  4673.0  373.78  4676.2  374.28  4739.6  377.17
  4744.6  374.64  4954.5  380.06  4959.6  377.96  5026.2  380.46  5107.9  378.29
  5210.7  380.19  5350.1  378.75  5365.3  378.95  5490.5  380.88  5503.3  380.99
  5532.3  378.95  5631.0  379.86  5744.6  384.21  5779.8  388.03  5864.8  384.51
  5928.3  385.22  5958.0  388.84  6014.0  394.17  6069.9  399.18  6144.5  401.13
#Mann=10,-1,0
  4132.6    0.05       0  4670.2    0.04       0  4676.2    0.05       0
  5350.1    0.16       0  5365.3    0.05       0  5490.5     0.1       0
  5503.3    0.05       0  5631.0     0.1       0  5958.0    0.05       0
  6014.0     0.1       0
Bank Sta=4670.2,4676.2
Exp/Cntr=0.3,0.1

Chan Stop Cuts=-1