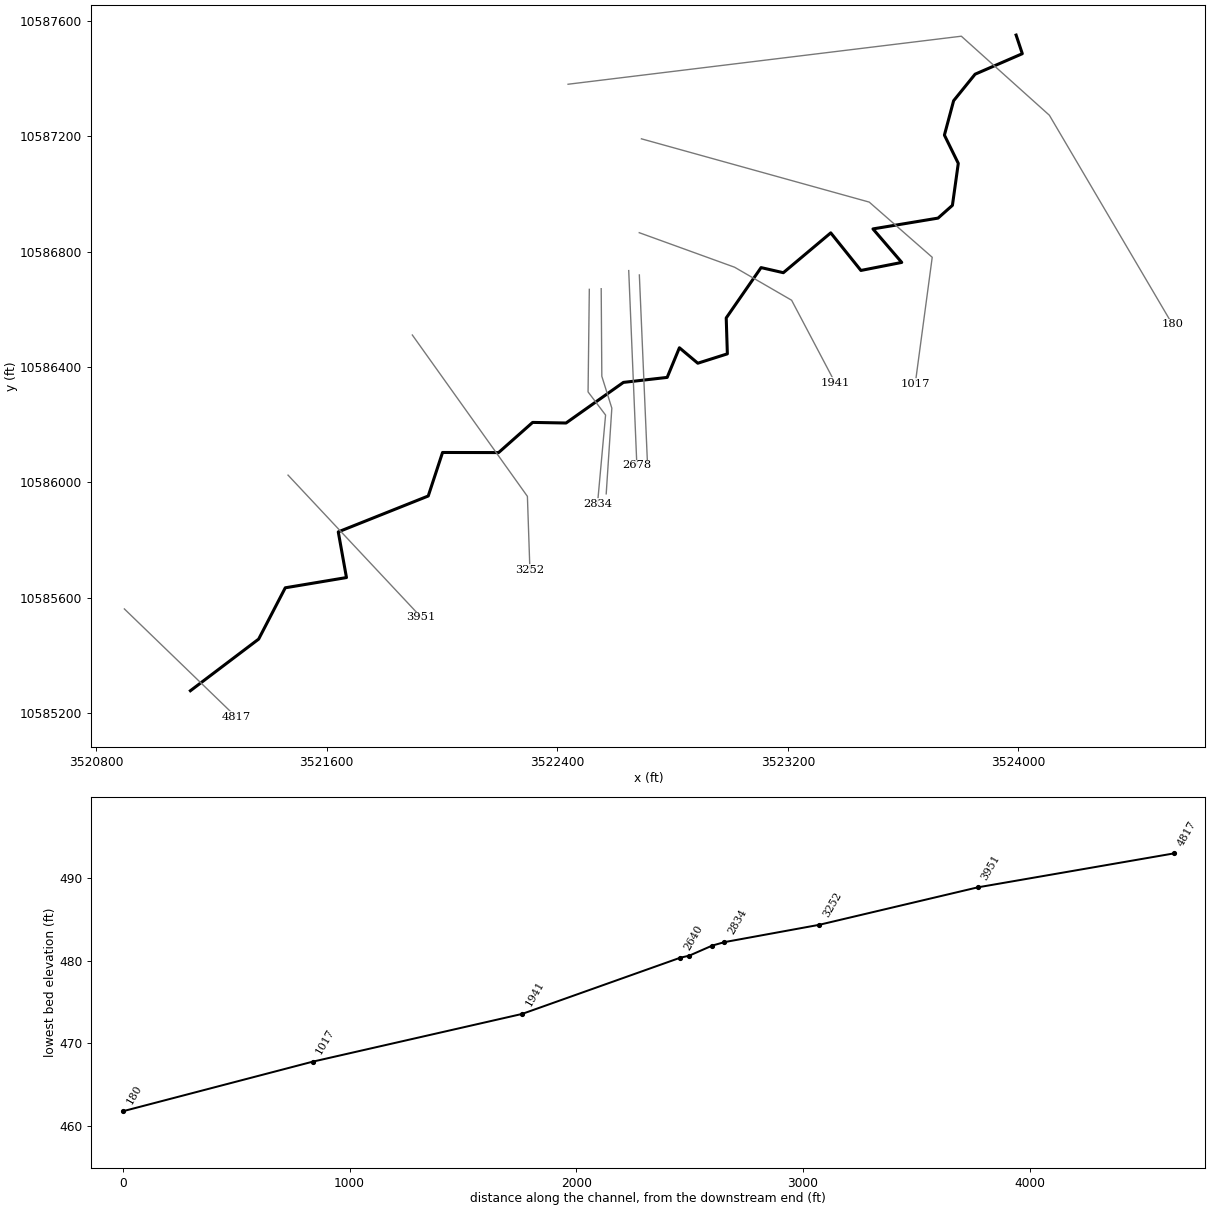
--- UNT01471 IN SAND CR.prj (project) ---

Proj Title=UNT01471 IN SAND CR Base Level Engineering
Current Plan=p01
Default Exp/Contr=0.3,0.1
English Units
Geom File=g01
Flow File=f01
Plan File=p01
BEGIN DESCRIPTION:
UNT01471 IN SAND CR
END DESCRIPTION:

--- UNT01471 IN SAND CR.p01 (plan) ---

Plan Title=Multiple Run
Short Identifier=Multiple
Geom File=g01
Flow File=f01
Subcritical Flow
K Sum by GR= 0
Std Step Tol= 0.01
Critical Tol= 0.01
Num of Std Step Trials= 20
Max Error Tol= 0.3
Flow Tol Ratio= 0.001
Split Flow NTrial= 30
Split Flow Tol= 0.02
Split Flow Ratio= 0.02
Log Output Level= 0
Friction Slope Method= 1
Unsteady Friction Slope Method= 2
Unsteady Bridges Friction Slope Method= 1
Parabolic Critical Depth
Global Vel Dist=  1 , 1 , 1
Global Log Level= 0
CheckData=True
Encroach Param= -1, 0, 0, 0
BEGIN DESCRIPTION:
Multiple Run
END DESCRIPTION:

--- UNT01471 IN SAND CR.f01 (steady flow) ---

Flow Title=Multiple
Number of Profiles=7
Profile Names=10-year,25-year,50-year,1pct_min,100-year,1pct_plu,500-year
River Rch & RM= UNT01471 IN SAND,Reach-1,4817
     378     489     576     496     671     907     907
River Rch & RM= UNT01471 IN SAND,Reach-1,2640
     552     732     876     766    1036    1401    1443
Boundary for River Rch & Prof#=UNT01471 IN SAND,Reach-1,1
Up Type=0
Dn Type=3
Dn Slope=0.005
Boundary for River Rch & Prof#=UNT01471 IN SAND,Reach-1,2
Up Type=0
Dn Type=3
Dn Slope=0.005
Boundary for River Rch & Prof#=UNT01471 IN SAND,Reach-1,3
Up Type=0
Dn Type=3
Dn Slope=0.005
Boundary for River Rch & Prof#=UNT01471 IN SAND,Reach-1,4
Up Type=0
Dn Type=3
Dn Slope=0.005
Boundary for River Rch & Prof#=UNT01471 IN SAND,Reach-1,5
Up Type=0
Dn Type=3
Dn Slope=0.005
Boundary for River Rch & Prof#=UNT01471 IN SAND,Reach-1,6
Up Type=0
Dn Type=3
Dn Slope=0.005
Boundary for River Rch & Prof#=UNT01471 IN SAND,Reach-1,7
Up Type=0
Dn Type=3
Dn Slope=0.005

--- UNT01471 IN SAND CR.g01 (geometry) ---

Geom Title=Existing Conditions

River Reach=UNT01471 IN SAND,Reach-1
Reach XY= 30
      3521127.11     10585276.64      3521363.90     10585455.80
      3521456.26     10585633.79      3521668.60     10585669.30
      3521640.16     10585827.78      3521952.34     10585952.31
      3522001.98     10586103.34      3522196.46     10586102.97
      3522314.58     10586207.66      3522430.52     10586205.57
      3522629.57     10586346.50      3522781.39     10586363.82
      3522823.86     10586466.65      3522887.65     10586413.05
      3522990.23     10586445.54      3522986.26     10586570.11
      3523107.25     10586744.81      3523184.48     10586727.12
      3523348.97     10586865.33      3523453.59     10586734.91
      3523595.33     10586762.80      3523495.39     10586879.06
      3523721.31     10586916.55      3523771.15     10586960.83
      3523791.49     10587106.45      3523743.33     10587204.55
      3523775.33     10587323.85      3523849.83     10587415.89
      3524013.66     10587487.00      3523992.11     10587551.64

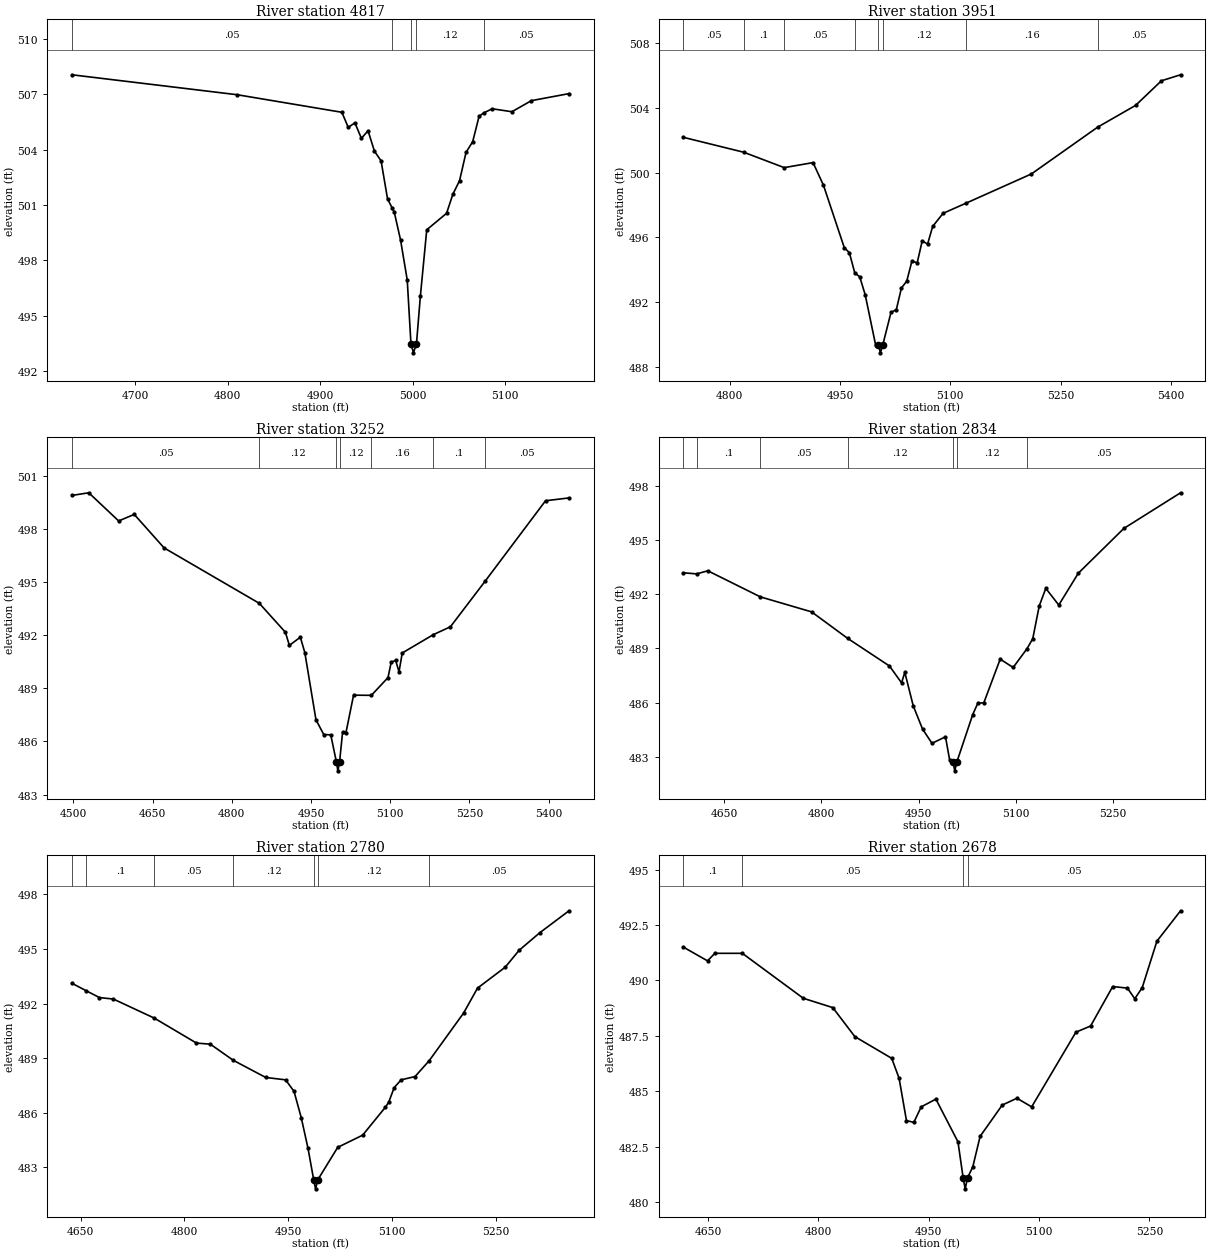
Type RM Length L Ch R = 1,4817,866,866,866
BEGIN DESCRIPTION:
UNT01471 IN SAND CR 9.0
END DESCRIPTION:
XS GIS Cut Line= 2
      3520897.95     10585560.46      3521284.69     10585186.74
#Sta/Elev= 30
  4631.5  508.05  4810.4  506.97  4923.6  506.02  4930.5  505.20  4937.7  505.45
  4944.7  504.61  4951.9  505.02  4958.8  503.92  4966.0  503.39  4973.0  501.33
  4977.8  500.86  4980.2  500.63  4987.1  499.10  4994.3  496.94  4998.3  493.50
  5001.0  493.00  5004.3  493.50  5008.5  496.07  5015.4  499.66  5036.8  500.55
  5043.7  501.59  5050.9  502.32  5057.9  503.85  5065.1  504.43  5072.0  505.80
  5076.8  505.98  5086.2  506.21  5107.5  506.05  5128.6  506.65  5169.3  507.03
#Mann=5,-1,0
  4631.5    0.05       0  4977.8    0.12       0  4998.3    0.07       0
  5004.3    0.12       0  5076.8    0.05       0
Bank Sta=4998.3,5004.3
Exp/Cntr=0.3,0.1

Type RM Length L Ch R = 1,3951,699,699,699
BEGIN DESCRIPTION:
UNT01471 IN SAND CR 8.0
END DESCRIPTION:
XS GIS Cut Line= 2
      3521465.86     10586024.73      3521928.24     10585531.18
#Sta/Elev= 30
  4736.9  502.18  4819.0  501.26  4874.1  500.31  4913.3  500.62  4927.5  499.22
  4955.8  495.37  4962.7  495.06  4970.0  493.82  4976.8  493.57  4984.2  492.47
  4998.3  489.39  5002.2  489.38  5004.9  488.88  5008.2  489.38  5019.3  491.37
  5026.6  491.55  5033.5  492.88  5040.8  493.31  5047.7  494.53  5055.0  494.44
  5061.8  495.79  5069.1  495.59  5076.0  496.68  5090.2  497.49  5121.1  498.11
  5210.3  499.92  5300.5  502.81  5352.0  504.15  5387.2  505.67  5413.2  506.04
#Mann=8,-1,0
  4736.9    0.05       0  4819.0     0.1       0  4874.1    0.05       0
  4970.0    0.12       0  5002.2    0.07       0  5008.2    0.12       0
  5121.1    0.16       0  5300.5    0.05       0
Bank Sta=5002.2,5008.2
Exp/Cntr=0.3,0.1

Type RM Length L Ch R = 1,3252,418,418,418
BEGIN DESCRIPTION:
UNT01471 IN SAND CR 7.1
END DESCRIPTION:
XS GIS Cut Line= 3
      3521897.12     10586510.93      3522296.41     10585951.06
      3522305.09     10585697.18
#Sta/Elev= 30
  4497.0  499.88  4529.1  500.03  4585.7  498.44  4615.2  498.81  4671.7  496.92
  4852.2  493.79  4901.5  492.16  4909.0  491.42  4929.8  491.88  4938.3  491.01
  4959.4  487.22  4974.1  486.39  4987.4  486.37  4998.1  484.84  5000.9  484.34
  5004.1  484.84  5009.8  486.52  5015.9  486.45  5030.6  488.61  5064.3  488.60
  5095.8  489.60  5101.9  490.47  5110.3  490.57  5116.7  489.93  5122.8  490.99
  5181.4  492.02  5214.1  492.47  5280.0  495.05  5394.2  499.58  5438.7  499.74
#Mann=7,-1,0
  4497.0    0.05       0  4852.2    0.12       0  4998.1    0.07       0
  5004.1    0.12       0  5064.3    0.16       0  5181.4     0.1       0
  5280.0    0.05       0
Bank Sta=4998.1,5004.1
Exp/Cntr=0.3,0.1

Type RM Length L Ch R = 1,2834,54,54,54
BEGIN DESCRIPTION:
UNT01471 IN SAND CR 7.0
END DESCRIPTION:
XS GIS Cut Line= 4
      3522511.25     10586669.35      3522506.91     10586313.48
      3522567.67     10586233.18      3522539.63     10585924.75
#Sta/Elev= 30
  4587.4  493.18  4607.9  493.12  4625.1  493.29  4706.1  491.85  4785.1  491.02
  4840.5  489.56  4905.1  488.03  4923.7  487.10  4928.7  487.68  4941.7  485.83
  4956.0  484.55  4970.6  483.76  4991.4  484.12  4997.7  482.86  5003.0  482.74
  5005.7  482.24  5009.0  482.74  5033.4  485.35  5041.4  485.99  5050.4  485.99
  5075.7  488.41  5095.7  487.95  5117.1  488.99  5125.9  489.54  5135.9  491.35
  5146.0  492.32  5166.0  491.40  5196.2  493.16  5266.3  495.63  5353.7  497.60
#Mann=7,-1,0
  4587.4    0.08       0  4607.9     0.1       0  4706.1    0.05       0
  4840.5    0.12       0  5003.0    0.07       0  5009.0    0.12       0
  5117.1    0.05       0
Bank Sta=5003,5009
Exp/Cntr=0.3,0.1

Type RM Length L Ch R = 1,2780,102,102,102
BEGIN DESCRIPTION:
UNT01471 IN SAND CR 6.0
END DESCRIPTION:
XS GIS Cut Line= 4
      3522552.48     10586671.51      3522554.65     10586367.73
      3522589.37     10586257.05      3522569.85     10585959.78
#Sta/Elev= 30
  4637.4  493.12  4658.4  492.70  4677.3  492.33  4697.3  492.25  4756.5  491.20
  4817.3  489.83  4837.3  489.77  4870.6  488.88  4917.3  487.94  4945.9  487.81
  4958.1  487.18  4968.5  485.74  4978.3  484.05  4986.5  482.32  4989.2  481.82
  4992.5  482.32  5021.2  484.10  5057.2  484.77  5089.7  486.29  5094.7  486.57
  5102.7  487.38  5112.7  487.81  5132.8  487.99  5153.2  488.86  5202.9  491.48
  5223.0  492.85  5263.0  494.00  5283.1  494.93  5313.1  495.90  5355.1  497.10
#Mann=7,-1,0
  4637.4    0.08       0  4658.4     0.1       0  4756.5    0.05       0
  4870.6    0.12       0  4986.5    0.07       0  4992.5    0.12       0
  5153.2    0.05       0
Bank Sta=4986.5,4992.5
Exp/Cntr=0.3,0.1

Type RM Length L Ch R = 1,2678,38,38,38
BEGIN DESCRIPTION:
UNT01471 IN SAND CR 5.0
END DESCRIPTION:
XS GIS Cut Line= 2
      3522647.97     10586734.45      3522676.18     10586059.54
#Sta/Elev= 30
  4616.7  491.50  4649.5  490.88  4659.5  491.22  4696.8  491.22  4779.7  489.19
  4819.7  488.77  4849.7  487.46  4899.8  486.48  4909.8  485.58  4919.8  483.67
  4929.8  483.59  4939.8  484.29  4959.8  484.64  4989.8  482.71  4996.8  481.09
  4999.6  480.59  5002.8  481.09  5009.9  481.58  5019.9  482.96  5049.9  484.37
  5069.9  484.68  5089.9  484.29  5150.0  487.66  5170.0  487.94  5200.0  489.72
  5220.0  489.65  5230.0  489.17  5240.1  489.67  5260.1  491.77  5292.2  493.14
#Mann=4,-1,0
  4616.7     0.1       0  4696.8    0.05       0  4996.8    0.04       0
  5002.8    0.05       0
Bank Sta=4996.8,5002.8
Exp/Cntr=0.3,0.1

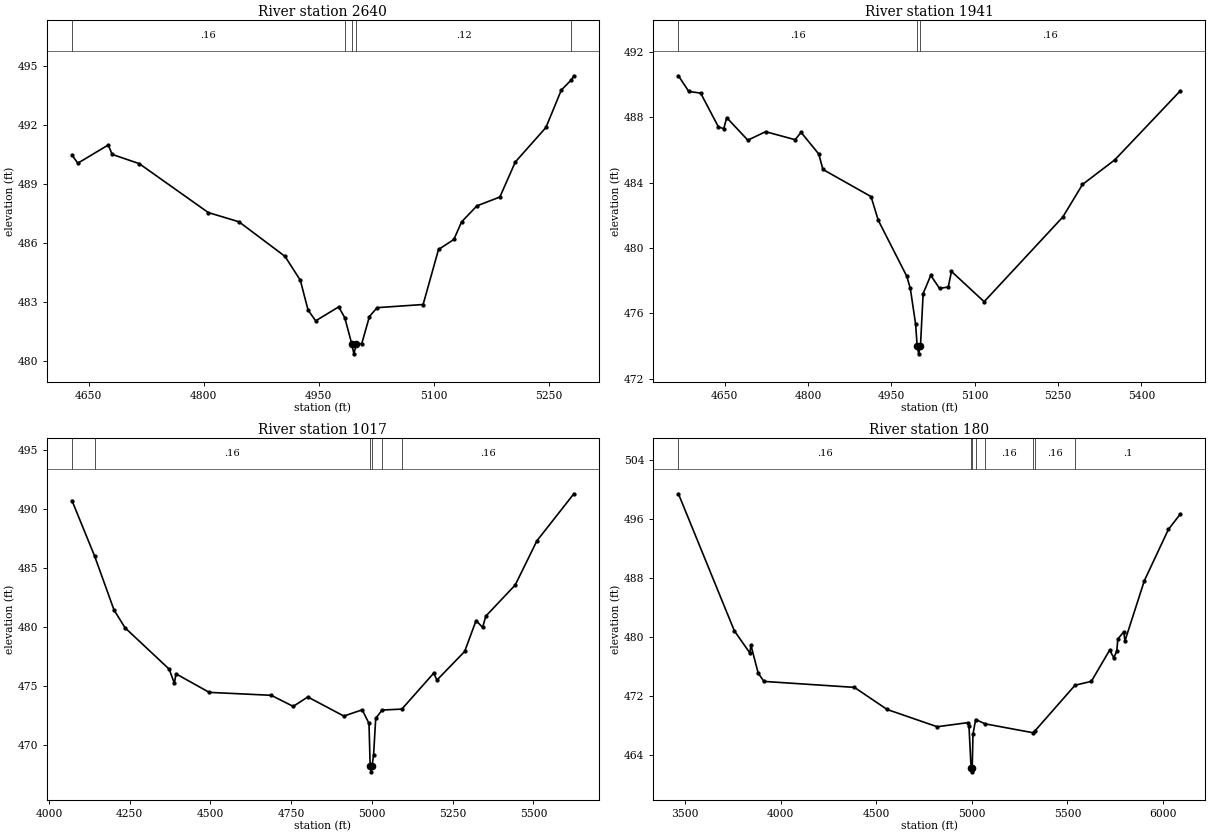
Type RM Length L Ch R = 1,2640,699,699,699
BEGIN DESCRIPTION:
UNT01471 IN SAND CR 4.0
END DESCRIPTION:
XS GIS Cut Line= 2
      3522684.86     10586719.26      3522713.01     10586065.27
#Sta/Elev= 30
  4628.1  490.48  4635.7  490.06  4675.5  490.99  4680.5  490.51  4715.8  490.04
  4805.9  487.55  4845.9  487.08  4906.0  485.32  4926.0  484.10  4936.0  482.59
  4946.0  482.04  4976.0  482.75  4983.9  482.20  4993.1  480.86  4995.8  480.36
  4999.1  480.86  5006.1  480.88  5016.1  482.26  5026.1  482.71  5086.1  482.87
  5106.2  485.67  5126.2  486.18  5136.2  487.07  5156.2  487.89  5186.2  488.34
  5206.3  490.12  5246.3  491.88  5266.3  493.78  5279.6  494.31  5282.7  494.51
#Mann=5,-1,0
  4628.1    0.16       0  4983.9    0.12       0  4993.1    0.07       0
  4999.1    0.12       0  5279.6    0.05       0
Bank Sta=4993.1,4999.1
Exp/Cntr=0.3,0.1

Type RM Length L Ch R = 1,1941,924,924,924
BEGIN DESCRIPTION:
UNT01471 IN SAND CR 3.0
END DESCRIPTION:
XS GIS Cut Line= 4
      3522684.54     10586865.92      3523015.30     10586746.12
      3523213.22     10586631.53      3523363.83     10586345.89
#Sta/Elev= 30
  4566.7  490.54  4585.4  489.58  4606.7  489.48  4638.6  487.42  4648.3  487.30
  4653.6  487.98  4691.7  486.60  4723.6  487.12  4776.8  486.63  4787.5  487.08
  4819.4  485.75  4826.8  484.81  4913.4  483.15  4926.4  481.70  4977.8  478.27
  4984.1  477.53  4993.6  475.36  4996.4  474.03  4999.1  473.53  5002.4  474.03
  5007.2  477.22  5020.9  478.33  5036.7  477.53  5052.4  477.62  5058.2  478.57
  5117.0  476.72  5258.6  481.90  5294.0  483.89  5352.3  485.40  5470.1  489.62
#Mann=3,-1,0
  4566.7    0.16       0  4996.4    0.07       0  5002.4    0.16       0
Bank Sta=4996.4,5002.4
Exp/Cntr=0.3,0.1

Type RM Length L Ch R = 1,1017,837,837,837
BEGIN DESCRIPTION:
UNT01471 IN SAND CR 2.0
END DESCRIPTION:
XS GIS Cut Line= 4
      3522692.12     10587191.64      3523482.50     10586972.09
      3523701.07     10586780.62      3523642.10     10586341.64
#Sta/Elev= 30
  4071.3  490.75  4141.7  486.02  4201.5  481.47  4235.8  479.95  4372.3  476.45
  4388.3  475.25  4393.5  476.05  4496.3  474.48  4688.3  474.23  4756.3  473.29
  4801.4  474.09  4913.0  472.47  4970.0  473.00  4990.9  471.84  4994.5  468.24
  4997.3  467.74  5000.5  468.24  5005.1  469.18  5011.7  472.27  5031.3  472.98
  5092.6  473.06  5191.2  476.11  5201.3  475.52  5287.1  477.95  5322.4  480.57
  5342.6  479.99  5352.7  480.95  5443.5  483.58  5510.7  487.33  5625.1  491.32
#Mann=6,-1,0
  4071.3    0.12       0  4141.7    0.16       0  4994.5    0.07       0
  5000.5    0.16       0  5031.3    0.12       0  5092.6    0.16       0
Bank Sta=4994.5,5000.5
Exp/Cntr=0.3,0.1

Type RM Length L Ch R = 1,180,0,0,0
BEGIN DESCRIPTION:
UNT01471 IN SAND CR 1.0
END DESCRIPTION:
XS GIS Cut Line= 4
      3522437.51     10587381.05      3523802.05     10587547.71
      3524107.60     10587273.40      3524534.67     10586547.74
#Sta/Elev= 30
  3463.9  499.46  3756.6  480.87  3838.1  477.85  3843.2  478.95  3881.6  475.11
  3911.8  474.00  4385.3  473.19  4556.6  470.19  4818.5  467.85  4977.3  468.40
  4984.8  468.00  4996.0  462.23  4998.8  461.73  5002.0  462.23  5005.7  466.82
  5019.8  468.83  5069.8  468.24  5319.3  467.04  5329.7  467.27  5540.0  473.48
  5625.6  474.01  5721.3  478.25  5742.7  477.21  5758.4  478.10  5764.2  479.76
  5795.5  480.74  5801.3  479.49  5902.8  487.66  6028.7  494.62  6091.2  496.71
#Mann=8,-1,0
  3463.9    0.16       0  4996.0    0.07       0  5002.0    0.16       0
  5019.8    0.12       0  5069.8    0.16       0  5319.3     0.1       0
  5329.7    0.16       0  5540.0     0.1       0
Bank Sta=4996,5002
Exp/Cntr=0.3,0.1

Chan Stop Cuts=-1