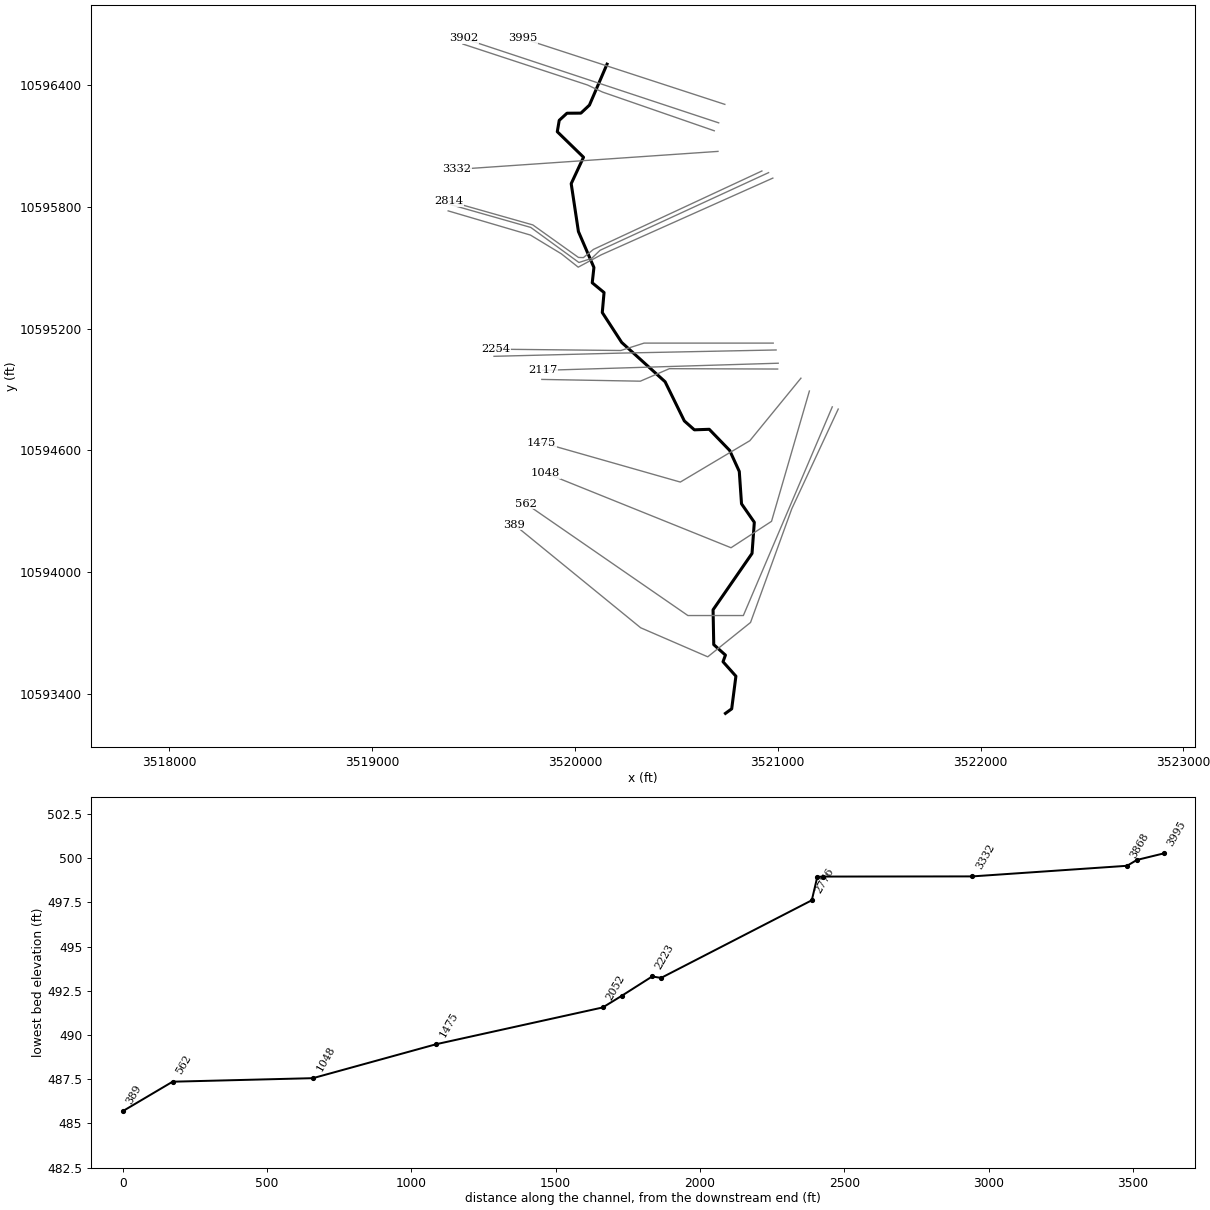
--- UNT01476 IN SAND CR.prj (project) ---

Proj Title=UNT01476 IN SAND CR Base Level Engineering
Current Plan=p01
Default Exp/Contr=0.3,0.1
English Units
Geom File=g01
Flow File=f01
Plan File=p01
BEGIN DESCRIPTION:
UNT01476 IN SAND CR
END DESCRIPTION:

--- UNT01476 IN SAND CR.p01 (plan) ---

Plan Title=Multiple Run
Short Identifier=Multiple
Geom File=g01
Flow File=f01
Subcritical Flow
K Sum by GR= 0
Std Step Tol= 0.01
Critical Tol= 0.01
Num of Std Step Trials= 20
Max Error Tol= 0.3
Flow Tol Ratio= 0.001
Split Flow NTrial= 30
Split Flow Tol= 0.02
Split Flow Ratio= 0.02
Log Output Level= 0
Friction Slope Method= 1
Unsteady Friction Slope Method= 2
Unsteady Bridges Friction Slope Method= 1
Parabolic Critical Depth
Global Vel Dist=  1 , 1 , 1
Global Log Level= 0
CheckData=True
Encroach Param= -1, 0, 0, 0
BEGIN DESCRIPTION:
Multiple Run
END DESCRIPTION:

--- UNT01476 IN SAND CR.f01 (steady flow) ---

Flow Title=Multiple
Number of Profiles=7
Profile Names=10-year,25-year,50-year,1pct_min,100-year,1pct_plu,500-year
River Rch & RM= UNT01476 IN SAND,Reach-1,3995
     220     273     311     261     353     477     449
River Rch & RM= UNT01476 IN SAND,Reach-1,3902
     361     462     540     462     624     844     831
River Rch & RM= UNT01476 IN SAND,Reach-1,389
     520     683     813     706     955    1292    1314
Boundary for River Rch & Prof#=UNT01476 IN SAND,Reach-1,1
Up Type=0
Dn Type=3
Dn Slope=0.005
Boundary for River Rch & Prof#=UNT01476 IN SAND,Reach-1,2
Up Type=0
Dn Type=3
Dn Slope=0.005
Boundary for River Rch & Prof#=UNT01476 IN SAND,Reach-1,3
Up Type=0
Dn Type=3
Dn Slope=0.005
Boundary for River Rch & Prof#=UNT01476 IN SAND,Reach-1,4
Up Type=0
Dn Type=3
Dn Slope=0.005
Boundary for River Rch & Prof#=UNT01476 IN SAND,Reach-1,5
Up Type=0
Dn Type=3
Dn Slope=0.005
Boundary for River Rch & Prof#=UNT01476 IN SAND,Reach-1,6
Up Type=0
Dn Type=3
Dn Slope=0.005
Boundary for River Rch & Prof#=UNT01476 IN SAND,Reach-1,7
Up Type=0
Dn Type=3
Dn Slope=0.005

--- UNT01476 IN SAND CR.g01 (geometry) ---

Geom Title=Existing Conditions

River Reach=UNT01476 IN SAND,Reach-1
Reach XY= 30
      3520158.32     10596503.71      3520071.57     10596301.81
      3520029.47     10596262.31      3519960.89     10596261.88
      3519922.70     10596226.72      3519913.15     10596170.73
      3520042.49     10596044.86      3519981.73     10595914.66
      3520017.32     10595678.54      3520093.71     10595501.46
      3520085.46     10595425.94      3520143.64     10595377.95
      3520134.94     10595279.35      3520230.65     10595131.85
      3520444.61     10594938.10      3520539.43     10594744.90
      3520588.89     10594701.07      3520662.24     10594703.67
      3520762.93     10594599.51      3520810.35     10594495.89
      3520821.35     10594336.36      3520884.46     10594245.34
      3520873.18     10594091.69      3520681.11     10593813.95
      3520684.47     10593642.23      3520742.11     10593590.44
      3520730.15     10593557.87      3520793.69     10593486.52
      3520772.94     10593325.68      3520742.11     10593303.23

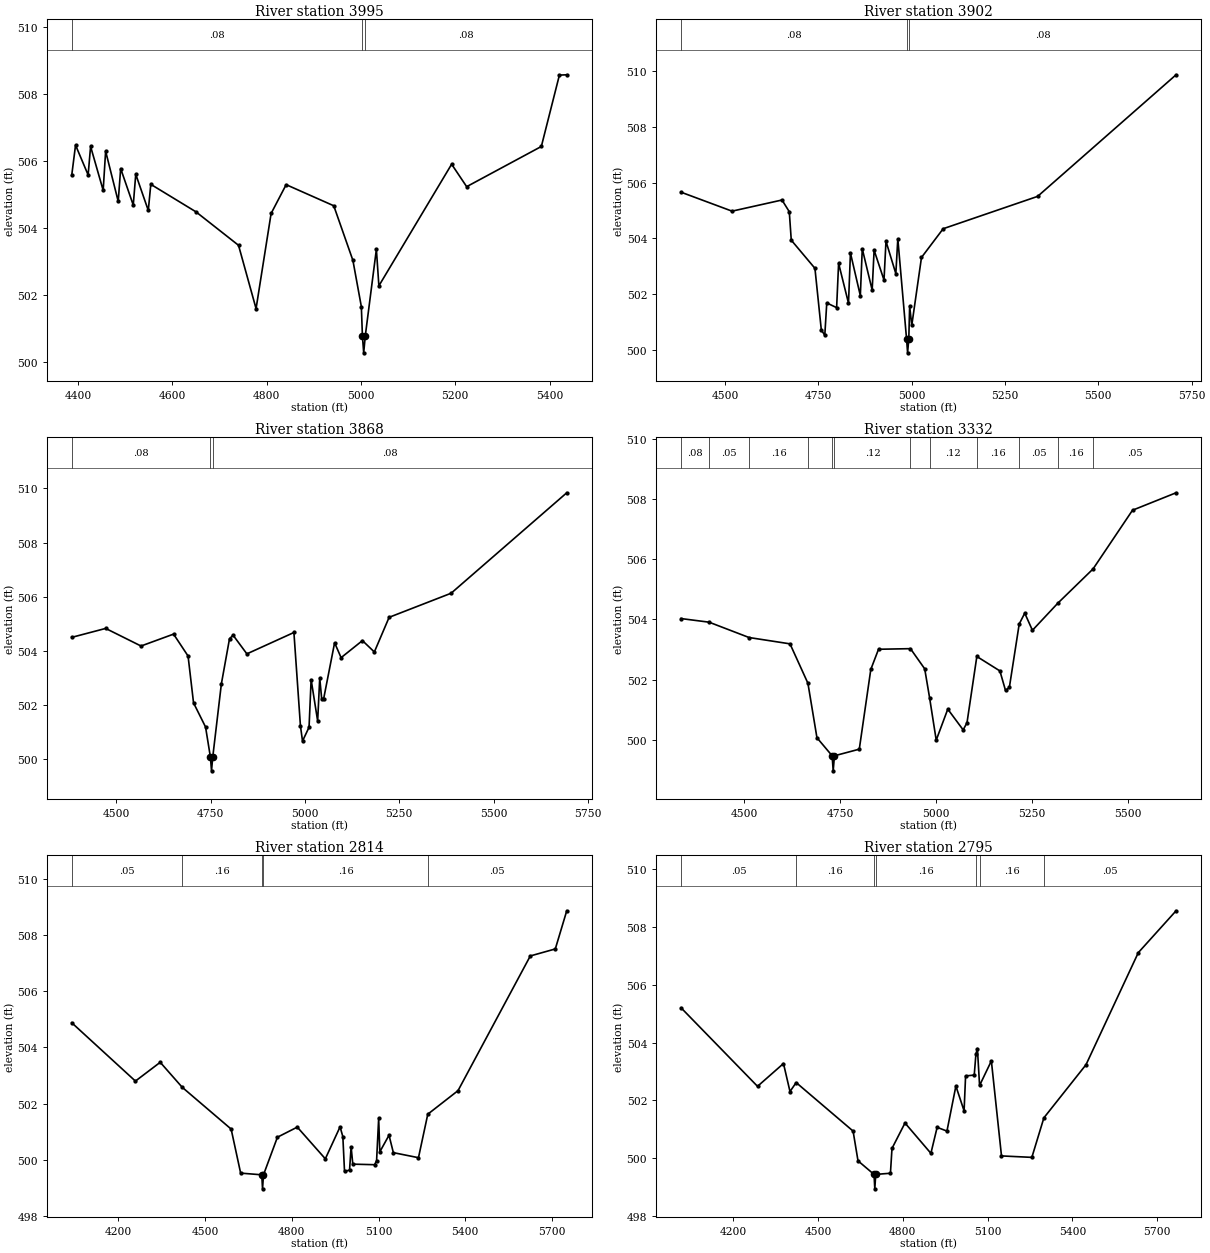
Type RM Length L Ch R = 1,3995,93,93,93
BEGIN DESCRIPTION:
UNT01476 IN SAND CR 4.2
END DESCRIPTION:
XS GIS Cut Line= 2
      3520739.13     10596305.52      3519740.86     10596631.04
#Sta/Elev= 30
  4386.4  505.57  4394.5  506.47  4421.2  505.58  4426.4  506.43  4453.1  505.12
  4458.3  506.29  4485.0  504.79  4490.2  505.77  4516.9  504.68  4522.2  505.60
  4548.8  504.52  4554.1  505.30  4649.8  504.48  4740.2  503.48  4777.4  501.59
  4809.3  504.43  4841.2  505.29  4942.2  504.66  4982.8  503.03  5000.7  501.65
  5003.0  500.77  5005.7  500.27  5009.0  500.77  5032.6  503.36  5037.9  502.27
  5192.2  505.90  5224.1  505.23  5382.5  506.43  5420.8  508.56  5436.4  508.57
#Mann=3,-1,0
  4386.4    0.08       0  5003.0    0.07       0  5009.0    0.08       0
Bank Sta=5003,5009
Exp/Cntr=0.3,0.1

Type RM Length L Ch R = 1,3902,34,34,34
BEGIN DESCRIPTION:
UNT01476 IN SAND CR 4.0
END DESCRIPTION:
XS GIS Cut Line= 2
      3520708.77     10596214.37      3519450.05     10596631.05
#Sta/Elev= 30
  4382.4  505.66  4519.0  504.98  4652.8  505.38  4672.3  504.96  4677.6  503.94
  4741.0  502.93  4758.1  500.72  4767.4  500.53  4772.7  501.69  4799.1  501.52
  4804.4  503.11  4830.9  501.68  4836.1  503.48  4862.6  501.95  4867.8  503.63
  4894.3  502.15  4899.5  503.58  4926.0  502.51  4931.3  503.90  4957.7  502.74
  4963.0  503.99  4986.4  500.40  4989.2  499.90  4992.4  500.40  4994.7  501.57
  5000.4  500.89  5026.4  503.32  5084.5  504.35  5337.5  505.51  5708.3  509.87
#Mann=3,-1,0
  4382.4    0.08       0  4986.4    0.07       0  4992.4    0.08       0
Bank Sta=4986.4,4992.4
Exp/Cntr=0.3,0.1

Type RM Length L Ch R = 1,3868,536,536,536
BEGIN DESCRIPTION:
UNT01476 IN SAND CR 4.1
END DESCRIPTION:
XS GIS Cut Line= 4
      3520687.07     10596175.31      3520135.86     10596366.28
      3520062.07     10596401.00      3519447.89     10596602.83
#Sta/Elev= 30
  4382.2  504.50  4472.1  504.83  4565.8  504.18  4652.0  504.62  4690.4  503.81
  4704.9  502.08  4736.7  501.19  4749.7  500.07  4752.5  499.57  4755.7  500.07
  4778.6  502.78  4800.2  504.45  4809.7  504.58  4846.2  503.89  4970.8  504.68
  4988.1  501.23  4993.6  500.67  5010.9  501.18  5016.4  502.94  5033.7  501.41
  5039.2  503.00  5044.3  502.24  5049.7  502.24  5078.6  504.30  5095.8  503.75
  5152.3  504.38  5183.9  503.96  5223.0  505.24  5387.3  506.13  5693.6  509.84
#Mann=3,-1,0
  4382.2    0.08       0  4749.7    0.07       0  4755.7    0.08       0
Bank Sta=4749.7,4755.7
Exp/Cntr=0.3,0.1

Type RM Length L Ch R = 1,3332,518,518,518
BEGIN DESCRIPTION:
UNT01476 IN SAND CR 2.3
END DESCRIPTION:
XS GIS Cut Line= 2
      3520705.29     10596073.70      3519418.83     10595985.16
#Sta/Elev= 30
  4335.1  504.03  4408.1  503.91  4512.3  503.40  4618.9  503.19  4665.6  501.88
  4689.1  500.07  4728.7  499.47  4731.4  498.97  4734.7  499.47  4799.4  499.69
  4829.4  502.34  4849.5  503.01  4932.7  503.03  4969.8  502.36  4982.5  501.40
  4999.8  499.99  5029.9  501.02  5070.0  500.33  5080.0  500.57  5105.6  502.77
  5165.7  502.29  5180.3  501.64  5190.3  501.74  5216.0  503.85  5230.4  504.21
  5250.4  503.64  5316.5  504.54  5408.4  505.68  5511.1  507.63  5624.6  508.21
#Mann=12,-1,0
  4335.1    0.08       0  4408.1    0.05       0  4512.3    0.16       0
  4665.6    0.12       0  4728.7    0.07       0  4734.7    0.12       0
  4932.7    0.16       0  4982.5    0.12       0  5105.6    0.16       0
  5216.0    0.05       0  5316.5    0.16       0  5408.4    0.05       0
Bank Sta=4728.7,4734.7
Exp/Cntr=0.3,0.1

Type RM Length L Ch R = 1,2814,19,19,19
BEGIN DESCRIPTION:
UNT01476 IN SAND CR 2.2
END DESCRIPTION:
XS GIS Cut Line= 6
      3520921.81     10595977.11      3520091.11     10595590.40
      3520041.89     10595550.12      3520017.58     10595550.82
      3519792.58     10595711.23      3519380.75     10595827.91
#Sta/Elev= 30
  4038.6  504.88  4258.9  502.80  4344.7  503.47  4420.7  502.58  4590.0  501.09
  4622.9  499.52  4695.9  499.46  4698.6  498.96  4701.9  499.46  4750.1  500.80
  4818.8  501.16  4915.8  500.03  4966.8  501.17  4976.4  500.82  4982.2  499.58
  4999.6  499.63  5005.0  500.46  5010.8  499.84  5086.1  499.82  5093.1  499.96
  5100.3  501.47  5104.3  500.28  5136.1  500.87  5151.1  500.25  5238.0  500.07
  5270.2  501.62  5374.8  502.46  5624.8  507.26  5711.3  507.51  5750.9  508.87
#Mann=5,-1,0
  4038.6    0.05       0  4420.7    0.16       0  4695.9    0.07       0
  4701.9    0.16       0  5270.2    0.05       0
Bank Sta=4695.9,4701.9
Exp/Cntr=0.3,0.1

Type RM Length L Ch R = 1,2795,19,19,19
BEGIN DESCRIPTION:
UNT01476 IN SAND CR 2.0
END DESCRIPTION:
XS GIS Cut Line= 6
      3520954.73     10595968.93      3520123.99     10595586.11
      3520082.33     10595546.11      3520019.83     10595525.97
      3519782.33     10595698.89      3519379.55     10595813.47
#Sta/Elev= 30
  4015.6  505.21  4286.1  502.49  4377.9  503.28  4400.9  502.31  4422.8  502.62
  4624.1  500.94  4641.5  499.91  4698.2  499.44  4700.9  498.94  4704.2  499.44
  4756.2  499.48  4761.7  500.34  4807.7  501.22  4899.3  500.17  4921.4  501.07
  4956.1  500.94  4987.7  502.50  5016.7  501.64  5022.0  502.85  5052.6  502.88
  5058.5  503.60  5063.8  503.80  5071.5  502.52  5113.2  503.37  5149.0  500.08
  5256.4  500.03  5299.0  501.40  5448.0  503.24  5632.9  507.12  5766.5  508.57
#Mann=7,-1,0
  4015.6    0.05       0  4422.8    0.16       0  4698.2    0.07       0
  4704.2    0.16       0  5058.5    0.05       0  5071.5    0.16       0
  5299.0    0.05       0
Bank Sta=4698.2,4704.2
Exp/Cntr=0.3,0.1

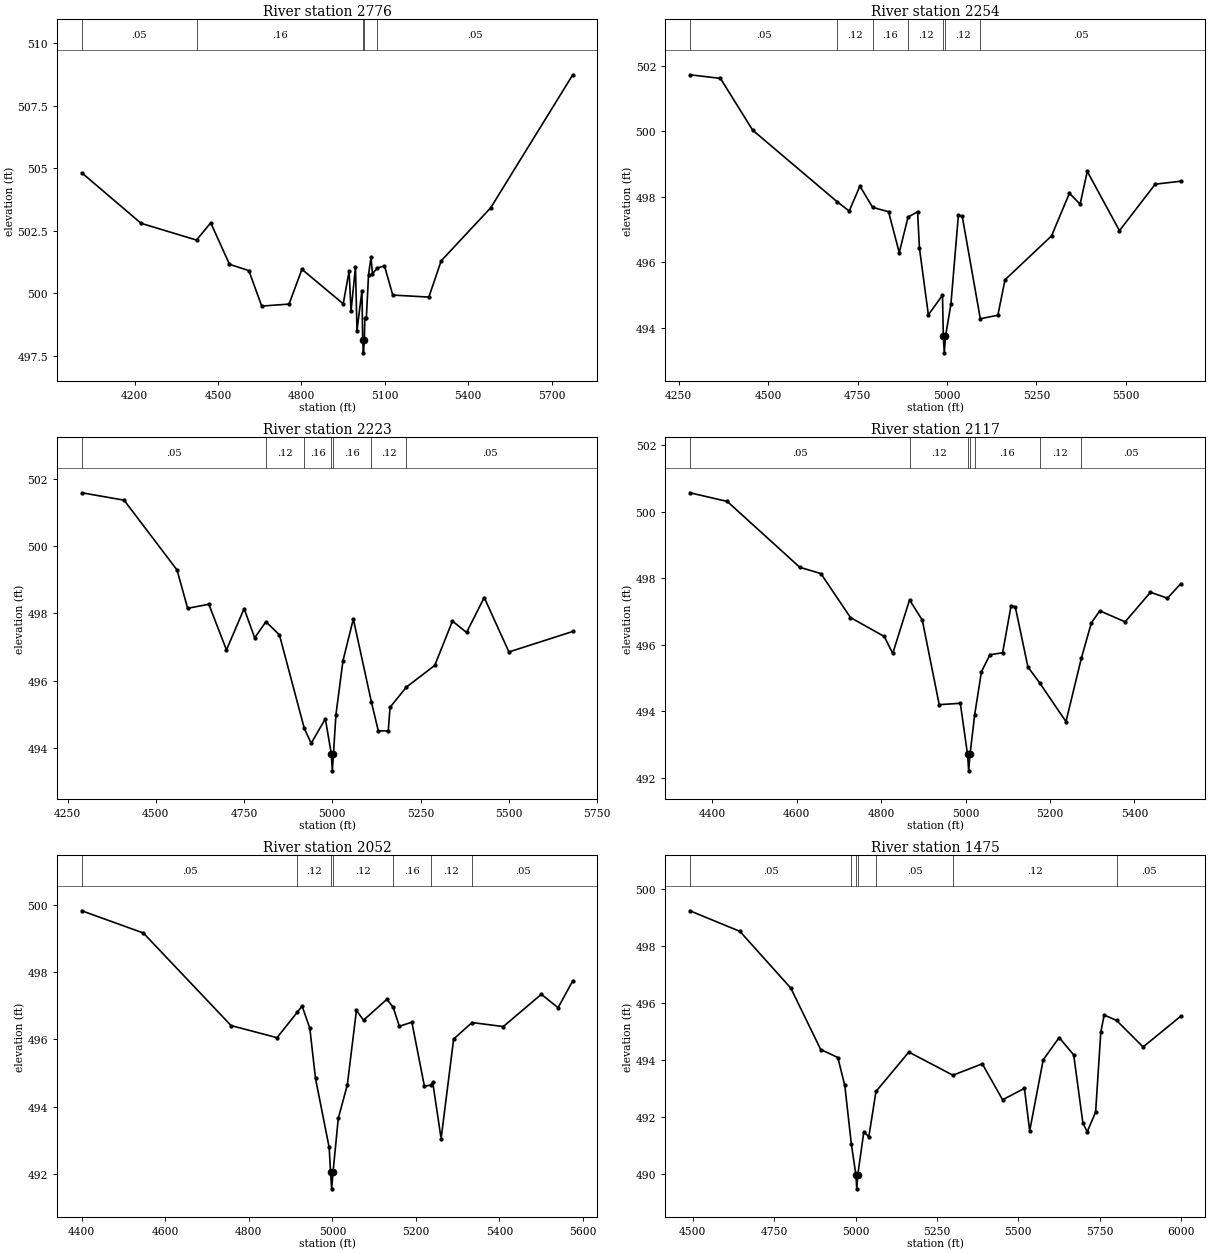
Type RM Length L Ch R = 1,2776,522,522,522
BEGIN DESCRIPTION:
UNT01476 IN SAND CR 2.1
END DESCRIPTION:
XS GIS Cut Line= 6
      3520975.71     10595942.02      3520128.80     10595563.40
      3520016.30     10595502.99      3519933.23     10595568.70
      3519780.89     10595661.15      3519375.18     10595780.40
#Sta/Elev= 30
  4009.6  504.82  4223.0  502.80  4422.5  502.13  4473.6  502.82  4541.1  501.16
  4610.7  500.91  4657.1  499.49  4755.4  499.57  4801.8  500.96  4950.4  499.58
  4971.5  500.89  4978.5  499.29  4994.4  501.05  4999.9  498.51  5017.8  500.11
  5020.3  498.12  5023.1  497.62  5026.3  498.12  5028.2  499.00  5033.5  499.00
  5041.5  500.75  5050.4  501.44  5055.6  500.78  5072.7  501.01  5098.7  501.10
  5128.6  499.93  5258.5  499.85  5302.9  501.30  5481.0  503.42  5776.4  508.74
#Mann=5,-1,0
  4009.6    0.05       0  4422.5    0.16       0  5020.3    0.07       0
  5026.3    0.16       0  5072.7    0.05       0
Bank Sta=5020.3,5026.3
Exp/Cntr=0.3,0.1

Type RM Length L Ch R = 1,2254,31,31,31
BEGIN DESCRIPTION:
UNT01476 IN SAND CR 3.3
END DESCRIPTION:
XS GIS Cut Line= 4
      3520977.61     10595128.60      3520340.87     10595128.60
      3520226.28     10595092.14      3519610.41     10595098.65
#Sta/Elev= 30
  4281.1  501.72  4366.6  501.61  4456.6  500.03  4693.3  497.84  4726.6  497.56
  4756.6  498.32  4792.2  497.67  4836.6  497.54  4866.6  496.29  4891.1  497.37
  4917.8  497.54  4923.1  496.42  4948.0  494.39  4987.5  494.99  4989.8  493.73
  4992.5  493.23  4995.8  493.73  5011.0  494.71  5032.0  497.44  5042.7  497.40
  5093.2  494.27  5142.3  494.38  5162.3  495.46  5292.3  496.80  5342.3  498.10
  5372.3  497.77  5392.3  498.77  5482.3  496.96  5582.3  498.38  5654.0  498.47
#Mann=7,-1,0
  4281.1    0.05       0  4693.3    0.12       0  4792.2    0.16       0
  4891.1    0.12       0  4989.8    0.07       0  4995.8    0.12       0
  5093.2    0.05       0
Bank Sta=4989.8,4995.8
Exp/Cntr=0.3,0.1

Type RM Length L Ch R = 1,2223,106,106,106
BEGIN DESCRIPTION:
UNT01476 IN SAND CR 3.2
END DESCRIPTION:
XS GIS Cut Line= 3
      3520991.92     10595094.75      3520218.47     10595079.12
      3519601.28     10595063.50
#Sta/Elev= 30
  4290.2  501.59  4410.0  501.37  4560.1  499.29  4590.1  498.15  4650.1  498.27
  4700.1  496.91  4750.1  498.14  4780.1  497.27  4811.8  497.75  4850.1  497.36
  4920.4  494.58  4940.1  494.13  4980.2  494.86  4997.2  493.81  4999.9  493.31
  5003.2  493.81  5010.2  494.98  5030.2  496.59  5059.5  497.83  5110.5  495.37
  5130.2  494.50  5158.5  494.50  5163.5  495.20  5209.4  495.80  5290.2  496.45
  5340.3  497.77  5380.3  497.43  5430.3  498.47  5500.3  496.85  5681.2  497.46
#Mann=7,-1,0
  4290.2    0.05       0  4811.8    0.12       0  4920.4    0.16       0
  4997.2    0.07       0  5003.2    0.16       0  5110.5    0.12       0
  5209.4    0.05       0
Bank Sta=4997.2,5003.2
Exp/Cntr=0.3,0.1

Type RM Length L Ch R = 1,2117,65,65,65
BEGIN DESCRIPTION:
UNT01476 IN SAND CR 3.0
END DESCRIPTION:
XS GIS Cut Line= 2
      3521002.14     10595029.43      3519840.27     10594994.22
#Sta/Elev= 30
  4347.4  500.57  4435.9  500.31  4607.6  498.33  4657.6  498.14  4727.6  496.82
  4807.6  496.25  4827.7  495.74  4867.5  497.35  4897.7  496.74  4937.7  494.20
  4987.7  494.24  5004.7  492.71  5007.5  492.21  5010.7  492.71  5021.7  493.90
  5037.7  495.19  5057.8  495.70  5087.8  495.76  5107.8  497.17  5117.8  497.14
  5147.8  495.33  5175.2  494.86  5237.8  493.69  5274.1  495.59  5297.9  496.66
  5317.9  497.02  5377.9  496.69  5437.9  497.58  5478.0  497.40  5509.8  497.84
#Mann=7,-1,0
  4347.4    0.05       0  4867.5    0.12       0  5004.7    0.07       0
  5010.7    0.12       0  5021.7    0.16       0  5175.2    0.12       0
  5274.1    0.05       0
Bank Sta=5004.7,5010.7
Exp/Cntr=0.3,0.1

Type RM Length L Ch R = 1,2052,577,577,577
BEGIN DESCRIPTION:
UNT01476 IN SAND CR 3.1
END DESCRIPTION:
XS GIS Cut Line= 4
      3520999.55     10595000.78      3520465.76     10595002.52
      3520322.53     10594940.89      3519836.93     10594949.53
#Sta/Elev= 30
  4400.1  499.82  4547.5  499.16  4757.5  496.41  4867.5  496.05  4915.5  496.80
  4927.5  496.99  4946.0  496.33  4959.6  494.84  4992.3  492.79  4995.6  492.06
  4998.3  491.56  5001.6  492.06  5014.1  493.65  5035.8  494.65  5057.6  496.86
  5074.6  496.57  5130.3  497.19  5145.7  496.95  5160.3  496.39  5190.3  496.51
  5220.3  494.61  5235.3  494.64  5240.3  494.72  5260.3  493.05  5290.3  496.01
  5334.3  496.50  5409.2  496.38  5500.3  497.34  5540.3  496.94  5575.5  497.74
#Mann=7,-1,0
  4400.1    0.05       0  4915.5    0.12       0  4995.6    0.07       0
  5001.6    0.12       0  5145.7    0.16       0  5235.3    0.12       0
  5334.3    0.05       0
Bank Sta=4995.6,5001.6
Exp/Cntr=0.3,0.1

Type RM Length L Ch R = 1,1475,427,427,427
BEGIN DESCRIPTION:
UNT01476 IN SAND CR 1.0
END DESCRIPTION:
XS GIS Cut Line= 4
      3521114.22     10594955.68      3520862.51     10594647.55
      3520519.63     10594443.56      3519835.48     10594638.41
#Sta/Elev= 30
  4491.2  499.22  4644.8  498.50  4801.3  496.51  4893.1  494.36  4945.7  494.08
  4967.1  493.10  4987.2  491.05  5001.1  489.98  5003.9  489.48  5007.1  489.98
  5025.6  491.48  5040.8  491.30  5062.9  492.89  5163.8  494.27  5299.3  493.46
  5389.4  493.86  5451.8  492.60  5518.9  493.00  5535.0  491.51  5576.6  494.00
  5625.6  494.78  5670.2  494.17  5698.5  491.78  5711.8  491.48  5737.6  492.17
  5753.4  494.96  5763.8  495.57  5801.7  495.38  5883.4  494.45  5999.4  495.53
#Mann=7,-1,0
  4491.2    0.05       0  4987.2    0.12       0  5001.1    0.07       0
  5007.1    0.12       0  5062.9    0.05       0  5299.3    0.12       0
  5801.7    0.05       0
Bank Sta=5001.1,5007.1
Exp/Cntr=0.3,0.1

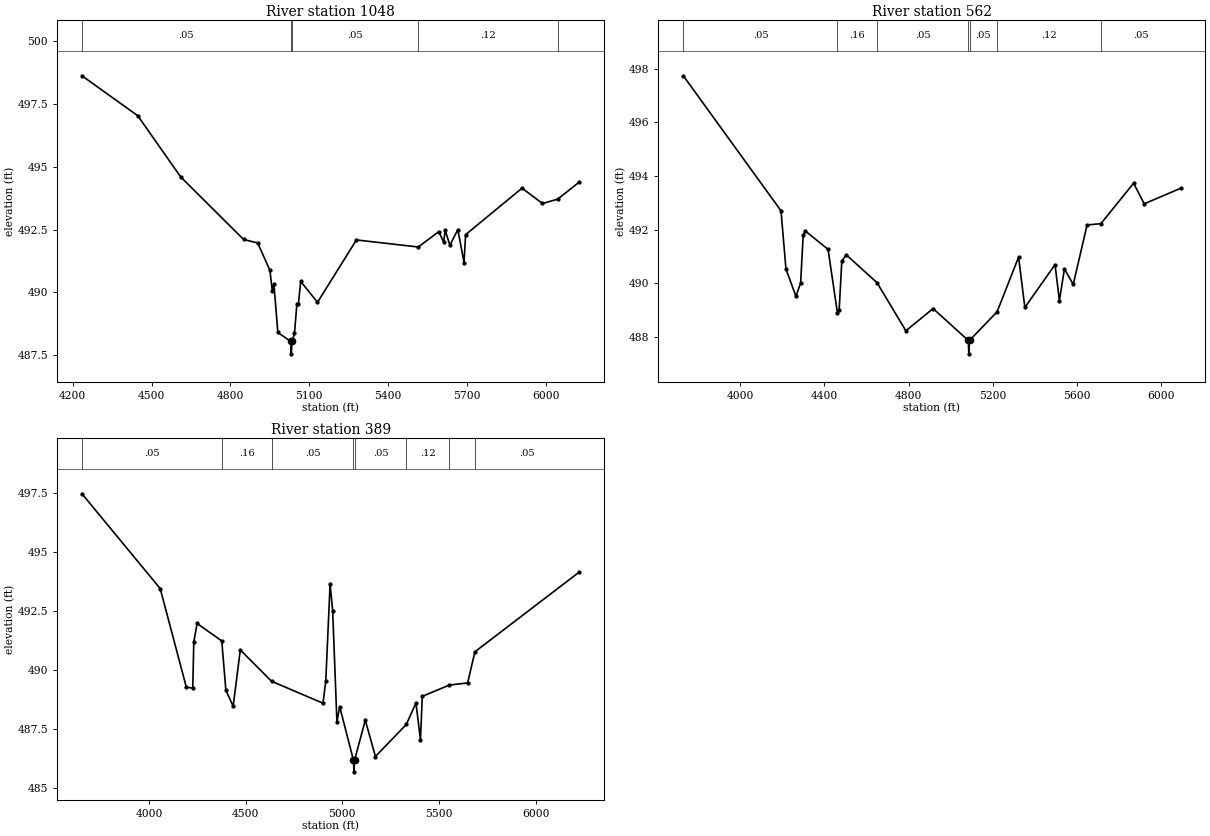
Type RM Length L Ch R = 1,1048,486,486,486
BEGIN DESCRIPTION:
UNT01476 IN SAND CR 1.1
END DESCRIPTION:
XS GIS Cut Line= 4
      3521155.92     10594892.37      3520969.28     10594249.98
      3520769.63     10594119.78      3519855.43     10594488.06
#Sta/Elev= 30
  4235.3  498.62  4447.8  497.03  4610.9  494.60  4850.5  492.11  4904.2  491.97
  4950.8  490.88  4959.9  490.06  4965.9  490.35  4981.0  488.41  5029.2  488.06
  5032.0  487.56  5035.2  488.06  5044.3  488.37  5053.5  489.55  5059.4  489.56
  5068.0  490.44  5131.9  489.61  5280.1  492.09  5515.4  491.81  5593.7  492.42
  5612.4  492.00  5617.8  492.48  5635.9  491.88  5666.1  492.50  5689.8  491.19
  5695.7  492.30  5910.5  494.15  5988.4  493.54  6045.8  493.71  6128.2  494.39
#Mann=5,-1,0
  4235.3    0.05       0  5029.2    0.03       0  5035.2    0.05       0
  5515.4    0.12       0  6045.8    0.05       0
Bank Sta=5029.2,5035.2
Exp/Cntr=0.3,0.1

Type RM Length L Ch R = 1,562,173,173,173
BEGIN DESCRIPTION:
UNT01476 IN SAND CR 1.2
END DESCRIPTION:
XS GIS Cut Line= 4
      3521268.77     10594814.24      3520830.39     10593785.57
      3520556.96     10593785.57      3519758.42     10594336.74
#Sta/Elev= 30
  3730.3  497.74  4194.4  492.70  4218.0  490.52  4265.3  489.51  4287.5  490.00
  4299.8  491.79  4309.2  491.95  4417.9  491.26  4462.5  488.88  4470.6  488.99
  4483.2  490.84  4505.1  491.05  4650.1  490.02  4787.5  488.22  4916.8  489.05
  5083.8  487.86  5086.5  487.36  5089.8  487.86  5220.8  488.93  5322.9  490.97
  5352.6  489.09  5495.9  490.69  5516.9  489.35  5540.6  490.53  5582.5  489.95
  5648.1  492.17  5713.9  492.22  5869.1  493.73  5919.8  492.96  6092.2  493.54
#Mann=7,-1,0
  3730.3    0.05       0  4462.5    0.16       0  4650.1    0.05       0
  5083.8    0.03       0  5089.8    0.05       0  5220.8    0.12       0
  5713.9    0.05       0
Bank Sta=5083.8,5089.8
Exp/Cntr=0.3,0.1

Type RM Length L Ch R = 1,389,0,0,0
BEGIN DESCRIPTION:
UNT01476 IN SAND CR 1.111
END DESCRIPTION:
XS GIS Cut Line= 6
      3521298.07     10594803.42      3521068.91     10594311.24
      3520865.78     10593751.34      3520654.85     10593582.07
      3520324.12     10593725.30      3519701.69     10594233.13
#Sta/Elev= 30
  3652.7  497.48  4057.5  493.46  4192.6  489.28  4226.0  489.24  4231.3  491.20
  4248.4  491.98  4376.0  491.24  4397.3  489.15  4435.0  488.47  4471.8  490.86
  4633.6  489.53  4899.8  488.60  4914.2  489.55  4936.5  493.66  4949.8  492.52
  4971.8  487.81  4986.2  488.45  5057.2  486.19  5060.0  485.69  5063.2  486.19
  5118.6  487.88  5171.0  486.34  5330.9  487.70  5380.7  488.61  5404.1  487.05
  5413.4  488.89  5553.8  489.37  5648.1  489.46  5685.7  490.78  6225.4  494.16
#Mann=8,-1,0
  3652.7    0.05       0  4376.0    0.16       0  4633.6    0.05       0
  5057.2    0.03       0  5063.2    0.05       0  5330.9    0.12       0
  5553.8    0.16       0  5685.7    0.05       0
Bank Sta=5057.2,5063.2
Exp/Cntr=0.3,0.1

Chan Stop Cuts=-1