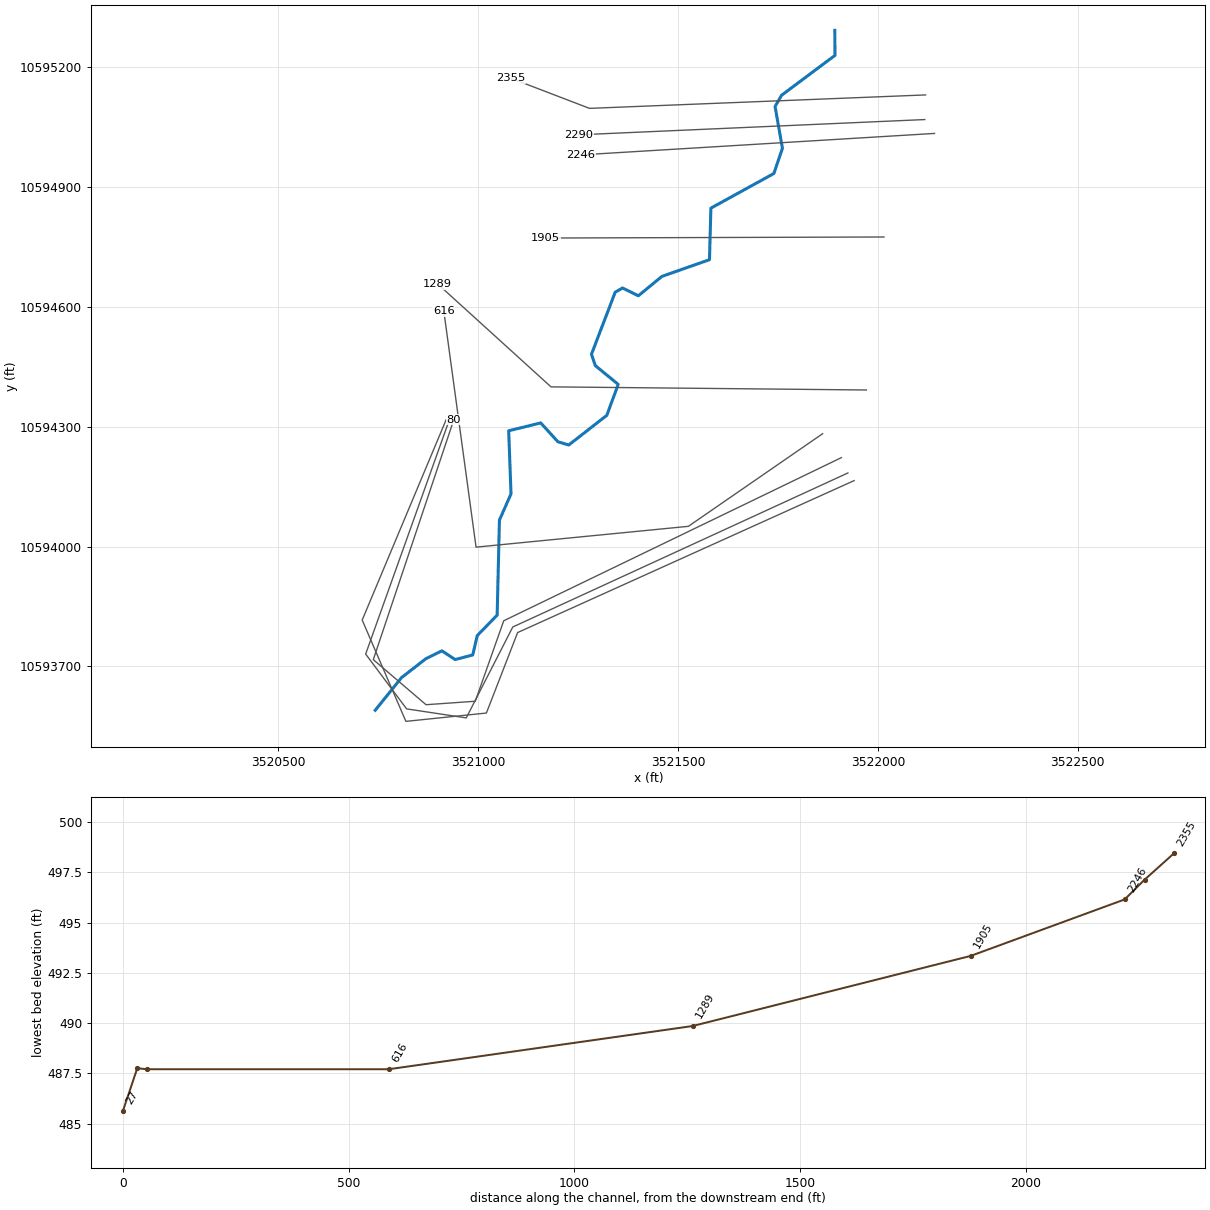
--- UNT01477 IN SAND CR.prj (project) ---

Proj Title=UNT01477 IN SAND CR Base Level Engineering
Current Plan=p01
Default Exp/Contr=0.3,0.1
English Units
Geom File=g01
Flow File=f01
Plan File=p01
BEGIN DESCRIPTION:
UNT01477 IN SAND CR
END DESCRIPTION:

--- UNT01477 IN SAND CR.p01 (plan) ---

Plan Title=Multiple Run
Short Identifier=Multiple
Geom File=g01
Flow File=f01
Subcritical Flow
K Sum by GR= 0
Std Step Tol= 0.01
Critical Tol= 0.01
Num of Std Step Trials= 20
Max Error Tol= 0.3
Flow Tol Ratio= 0.001
Split Flow NTrial= 30
Split Flow Tol= 0.02
Split Flow Ratio= 0.02
Log Output Level= 0
Friction Slope Method= 1
Unsteady Friction Slope Method= 2
Unsteady Bridges Friction Slope Method= 1
Parabolic Critical Depth
Global Vel Dist=  1 , 1 , 1
Global Log Level= 0
CheckData=True
Encroach Param= -1, 0, 0, 0
BEGIN DESCRIPTION:
Multiple Run
END DESCRIPTION:

--- UNT01477 IN SAND CR.f01 (steady flow) ---

Flow Title=Multiple
Number of Profiles=7
Profile Names=10-year,25-year,50-year,1pct_min,100-year,1pct_plu,500-year
River Rch & RM= UNT01477 IN SAND,Reach-1,2355
     225     279     319     268     362     489     463
River Rch & RM= UNT01477 IN SAND,Reach-1,80
     520     683     813     706     955    1292    1314
Boundary for River Rch & Prof#=UNT01477 IN SAND,Reach-1,1
Up Type=0
Dn Type=3
Dn Slope=0.005
Boundary for River Rch & Prof#=UNT01477 IN SAND,Reach-1,2
Up Type=0
Dn Type=3
Dn Slope=0.005
Boundary for River Rch & Prof#=UNT01477 IN SAND,Reach-1,3
Up Type=0
Dn Type=3
Dn Slope=0.005
Boundary for River Rch & Prof#=UNT01477 IN SAND,Reach-1,4
Up Type=0
Dn Type=3
Dn Slope=0.005
Boundary for River Rch & Prof#=UNT01477 IN SAND,Reach-1,5
Up Type=0
Dn Type=3
Dn Slope=0.005
Boundary for River Rch & Prof#=UNT01477 IN SAND,Reach-1,6
Up Type=0
Dn Type=3
Dn Slope=0.005
Boundary for River Rch & Prof#=UNT01477 IN SAND,Reach-1,7
Up Type=0
Dn Type=3
Dn Slope=0.005

--- UNT01477 IN SAND CR.g01 (geometry) ---

Geom Title=Existing Conditions

River Reach=UNT01477 IN SAND,Reach-1
Reach XY= 30
      3521892.05     10595291.64      3521892.46     10595229.03
      3521758.84     10595129.19      3521742.56     10595100.98
      3521760.96     10594996.53      3521739.50     10594933.43
      3521581.95     10594846.75      3521578.44     10594717.74
      3521459.59     10594676.07      3521400.42     10594627.49
      3521361.03     10594646.94      3521342.59     10594636.57
      3521283.10     10594481.05      3521292.79     10594452.73
      3521350.10     10594405.76      3521321.46     10594328.28
      3521226.24     10594254.09      3521199.16     10594262.23
      3521156.17     10594309.40      3521075.99     10594289.67
      3521081.84     10594131.77      3521052.86     10594066.33
      3521047.16     10593828.43      3520997.36     10593777.22
      3520986.11     10593728.73      3520942.13     10593717.25
      3520908.80     10593739.12      3520868.69     10593719.33
      3520807.75     10593671.93      3520742.11     10593590.44

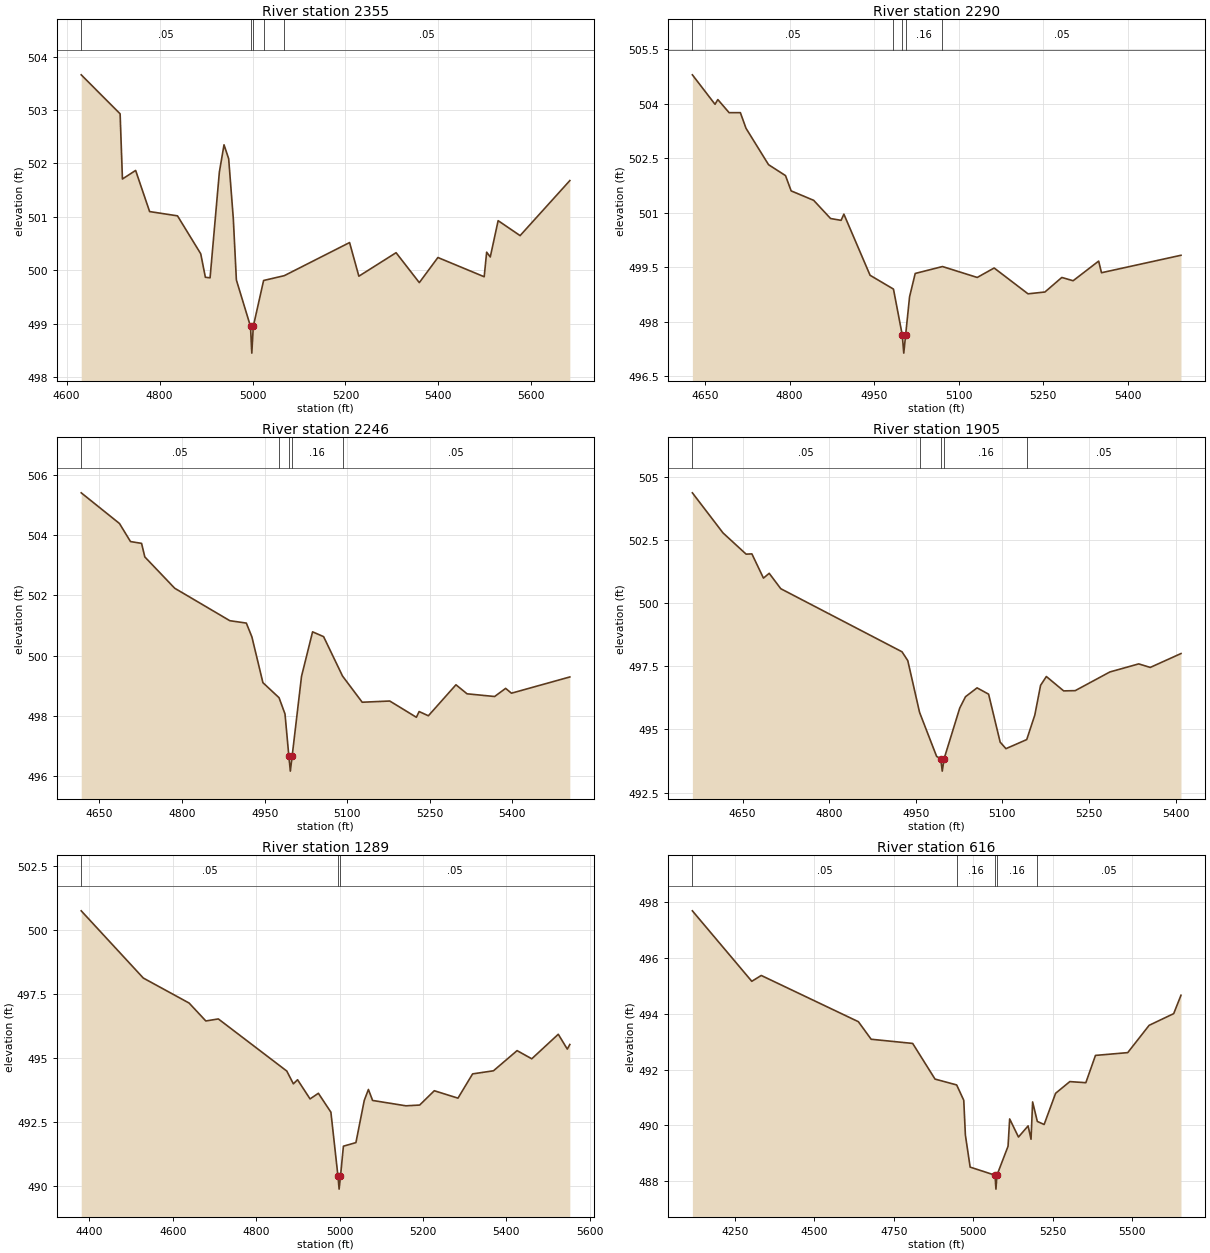
Type RM Length L Ch R = 1,2355,65,65,65
BEGIN DESCRIPTION:
UNT01477 IN SAND CR 4.2
END DESCRIPTION:
XS GIS Cut Line= 3
      3522119.14     10595130.05      3521278.22     10595096.41
      3521082.23     10595171.56
#Sta/Elev= 30
  4631.4  503.66  4715.1  502.93  4720.1  501.71  4748.5  501.87  4778.6  501.10
  4838.6  501.02  4888.6  500.31  4898.6  499.87  4908.7  499.86  4928.7  501.84
  4938.7  502.35  4948.7  502.09  4958.7  500.97  4965.3  499.82  4995.7  498.95
  4998.5  498.45  5001.7  498.95  5023.9  499.81  5068.4  499.90  5208.9  500.52
  5228.9  499.89  5309.0  500.33  5359.0  499.77  5399.0  500.24  5498.6  499.88
  5503.9  500.34  5511.7  500.25  5528.6  500.93  5575.9  500.65  5682.9  501.68
#Mann=5,-1,0
  4631.4    0.05       0  4995.7    0.03       0  5001.7    0.05       0
  5023.9    0.16       0  5068.4    0.05       0
Bank Sta=4995.7,5001.7
Exp/Cntr=0.3,0.1

Type RM Length L Ch R = 1,2290,44,44,44
BEGIN DESCRIPTION:
UNT01477 IN SAND CR 4.0
END DESCRIPTION:
XS GIS Cut Line= 2
      3522117.21     10595068.42      3521250.85     10595030.22
#Sta/Elev= 30
  4627.5  504.79  4667.7  503.98  4672.7  504.11  4692.7  503.75  4712.7  503.75
  4722.7  503.32  4762.7  502.32  4792.8  502.02  4802.8  501.60  4842.8  501.34
  4872.8  500.84  4891.4  500.79  4896.4  500.96  4942.9  499.28  4984.4  498.90
  5000.0  497.64  5002.7  497.14  5006.0  497.64  5013.0  498.69  5023.0  499.33
  5071.4  499.52  5133.1  499.22  5163.1  499.48  5223.2  498.77  5253.2  498.82
  5283.2  499.22  5303.3  499.13  5348.6  499.67  5353.6  499.35  5494.7  499.83
#Mann=5,-1,0
  4627.5    0.05       0  4984.4    0.16       0  5000.0    0.07       0
  5006.0    0.16       0  5071.4    0.05       0
Bank Sta=5000,5006
Exp/Cntr=0.3,0.1

Type RM Length L Ch R = 1,2246,341,341,341
BEGIN DESCRIPTION:
UNT01477 IN SAND CR 4.1
END DESCRIPTION:
XS GIS Cut Line= 2
      3522141.49     10595033.69      3521255.72     10594979.96
#Sta/Elev= 30
  4616.9  505.41  4686.4  504.39  4706.4  503.79  4726.5  503.73  4732.4  503.28
  4786.6  502.24  4886.8  501.16  4916.8  501.08  4926.9  500.62  4946.9  499.10
  4976.2  498.60  4987.0  498.06  4994.0  496.66  4996.7  496.16  5000.0  496.66
  5017.0  499.31  5037.1  500.79  5057.1  500.63  5091.5  499.32  5127.2  498.45
  5177.3  498.49  5225.6  497.95  5230.6  498.14  5247.4  498.00  5297.5  499.03
  5317.6  498.73  5367.7  498.64  5387.7  498.91  5398.3  498.75  5504.3  499.29
#Mann=5,-1,0
  4616.9    0.05       0  4976.2    0.16       0  4994.0    0.07       0
  5000.0    0.16       0  5091.5    0.05       0
Bank Sta=4994,5000
Exp/Cntr=0.3,0.1

Type RM Length L Ch R = 1,1905,616,616,616
BEGIN DESCRIPTION:
UNT01477 IN SAND CR 3.0
END DESCRIPTION:
XS GIS Cut Line= 2
      3522015.18     10594774.58      3521168.89     10594771.98
#Sta/Elev= 30
  4563.1  504.38  4616.2  502.79  4656.2  501.95  4666.2  501.96  4686.2  501.00
  4696.2  501.19  4716.2  500.58  4926.2  498.08  4936.2  497.73  4956.6  495.68
  4986.2  493.93  4993.2  493.85  4995.9  493.35  4999.2  493.85  5026.2  495.85
  5036.2  496.30  5056.2  496.65  5076.2  496.40  5096.2  494.50  5106.2  494.24
  5142.2  494.60  5156.2  495.57  5166.2  496.75  5176.2  497.10  5206.2  496.53
  5226.2  496.54  5286.2  497.28  5336.2  497.60  5356.2  497.46  5409.4  498.01
#Mann=5,-1,0
  4563.1    0.05       0  4956.6    0.16       0  4993.2    0.07       0
  4999.2    0.16       0  5142.2    0.05       0
Bank Sta=4993.2,4999.2
Exp/Cntr=0.3,0.1

Type RM Length L Ch R = 1,1289,673,673,673
BEGIN DESCRIPTION:
UNT01477 IN SAND CR 1.0
END DESCRIPTION:
XS GIS Cut Line= 3
      3521970.97     10594391.77      3521181.87     10594399.58
      3520898.46     10594656.99
#Sta/Elev= 30
  4380.2  500.75  4529.1  498.12  4639.1  497.14  4679.1  496.44  4709.1  496.52
  4873.3  494.48  4889.1  493.98  4899.1  494.14  4929.1  493.39  4949.1  493.61
  4979.1  492.87  4996.1  490.36  4998.8  489.86  5002.1  490.36  5009.1  491.54
  5039.1  491.68  5059.1  493.33  5069.1  493.76  5079.1  493.33  5159.1  493.12
  5192.0  493.15  5227.1  493.71  5283.9  493.42  5319.0  494.37  5369.0  494.49
  5425.7  495.28  5460.9  494.96  5524.5  495.92  5546.1  495.34  5552.2  495.52
#Mann=3,-1,0
  4380.2    0.05       0  4996.1    0.03       0  5002.1    0.05       0
Bank Sta=4996.1,5002.1
Exp/Cntr=0.3,0.1

Type RM Length L Ch R = 1,616,536,536,536
BEGIN DESCRIPTION:
UNT01477 IN SAND CR 1.1
END DESCRIPTION:
XS GIS Cut Line= 4
      3521861.53     10594282.38      3521525.62     10594050.62
      3520994.37     10593998.54      3520913.85     10594588.17
#Sta/Elev= 30
  4116.0  497.70  4302.9  495.17  4332.7  495.38  4638.2  493.72  4678.4  493.09
  4809.0  492.94  4879.3  491.66  4947.4  491.45  4969.7  490.90  4974.8  489.65
  4989.8  488.50  5068.1  488.21  5070.9  487.71  5074.1  488.21  5109.0  489.25
  5114.1  490.23  5141.8  489.58  5172.1  489.98  5181.3  489.50  5186.3  490.84
  5201.1  490.14  5222.5  490.03  5258.6  491.15  5303.3  491.57  5353.7  491.53
  5384.0  492.51  5485.5  492.61  5552.8  493.59  5630.1  494.01  5653.0  494.67
#Mann=5,-1,0
  4116.0    0.05       0  4947.4    0.16       0  5068.1    0.07       0
  5074.1    0.16       0  5201.1    0.05       0
Bank Sta=5068.1,5074.1
Exp/Cntr=0.3,0.1

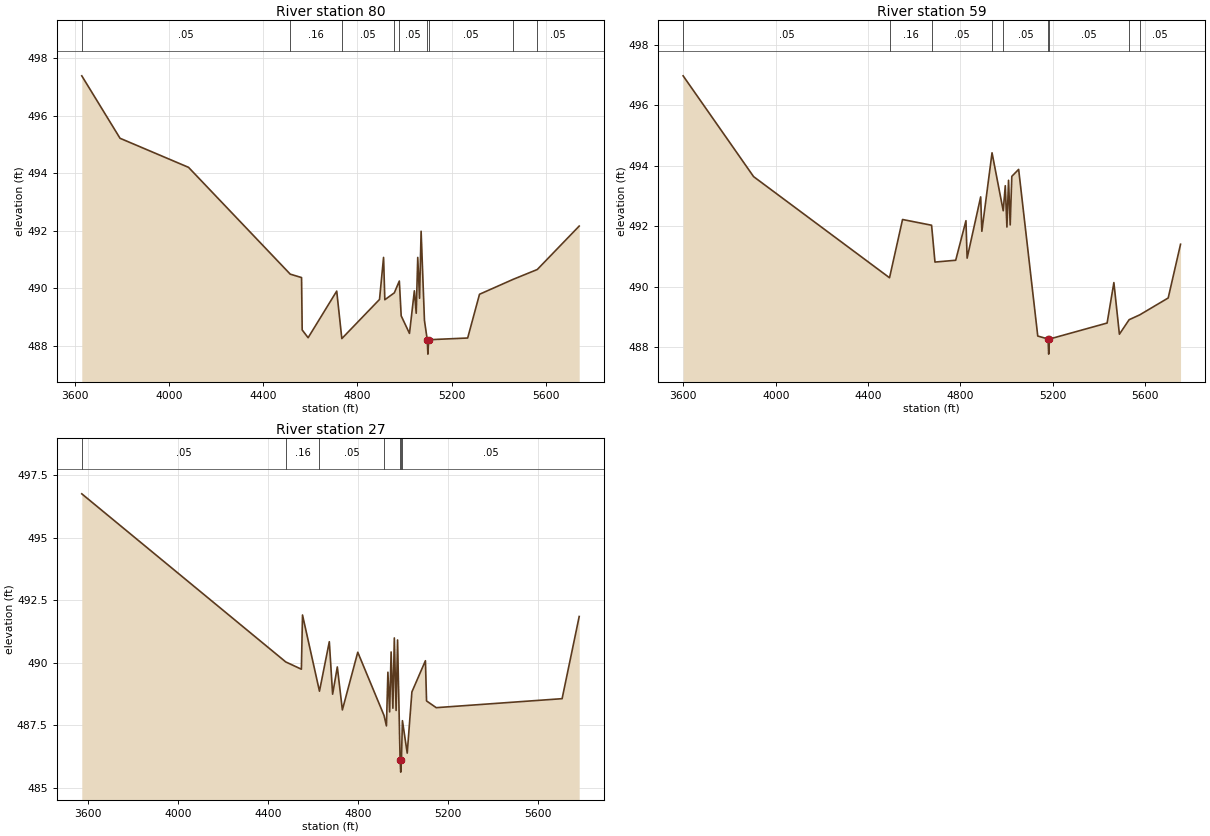
Type RM Length L Ch R = 1,80,21,21,21
BEGIN DESCRIPTION:
UNT01477 IN SAND CR 1.3
END DESCRIPTION:
XS GIS Cut Line= 6
      3521908.40     10594222.48      3521063.64     10593814.34
      3520992.46     10593612.95      3520869.20     10593604.27
      3520737.25     10593717.11      3520938.65     10594317.19
#Sta/Elev= 30
  3628.8  497.38  3791.3  495.21  4082.3  494.20  4514.2  490.49  4562.4  490.37
  4565.1  488.55  4590.3  488.28  4711.8  489.90  4733.5  488.25  4893.6  489.61
  4910.8  491.07  4916.2  489.60  4956.5  489.84  4977.8  490.25  4985.7  489.04
  5020.9  488.43  5041.7  489.91  5049.5  489.13  5056.0  491.07  5063.7  489.65
  5070.3  491.98  5084.5  488.88  5096.4  488.21  5099.1  487.71  5102.4  488.21
  5268.1  488.27  5318.4  489.79  5461.7  490.31  5563.8  490.65  5741.9  492.16
#Mann=9,-1,0
  3628.8    0.05       0  4514.2    0.16       0  4733.5    0.05       0
  4956.5    0.12       0  4977.8    0.05       0  5096.4    0.03       0
  5102.4    0.05       0  5461.7    0.16       0  5563.8    0.05       0
Bank Sta=5096.4,5102.4
Exp/Cntr=0.3,0.1

Type RM Length L Ch R = 1,59,32,32,32
BEGIN DESCRIPTION:
UNT01477 IN SAND CR 1.4
END DESCRIPTION:
XS GIS Cut Line= 6
      3521924.74     10594184.12      3521086.21     10593798.71
      3520969.89     10593571.28      3520820.58     10593593.85
      3520718.15     10593731.00      3520926.84     10594315.10
#Sta/Elev= 30
  3598.8  496.98  3904.2  493.64  4493.0  490.29  4549.4  492.22  4675.2  492.03
  4689.9  490.81  4779.7  490.87  4824.1  492.18  4829.2  490.94  4887.9  492.97
  4893.0  491.83  4937.1  494.43  4985.6  492.51  4994.5  493.34  5001.6  491.97
  5008.6  493.52  5015.8  492.04  5022.8  493.65  5052.4  493.88  5135.2  488.36
  5179.8  488.26  5182.6  487.76  5185.8  488.26  5435.7  488.79  5465.0  490.13
  5488.9  488.42  5531.0  488.90  5576.8  489.06  5700.3  489.62  5753.8  491.40
#Mann=9,-1,0
  3598.8    0.05       0  4493.0    0.16       0  4675.2    0.05       0
  4937.1    0.12       0  4985.6    0.05       0  5179.8    0.03       0
  5185.8    0.05       0  5531.0    0.16       0  5576.8    0.05       0
Bank Sta=5179.8,5185.8
Exp/Cntr=0.3,0.1

Type RM Length L Ch R = 1,27,0,0,0
BEGIN DESCRIPTION:
UNT01477 IN SAND CR 1.2
END DESCRIPTION:
XS GIS Cut Line= 6
      3521940.38     10594165.03      3521098.36     10593784.82
      3521020.24     10593583.43      3520818.85     10593562.60
      3520709.47     10593816.07      3520919.48     10594317.24
#Sta/Elev= 30
  3571.4  496.76  4479.2  490.03  4548.6  489.74  4553.6  491.91  4629.1  488.86
  4672.9  490.84  4687.6  488.74  4708.5  489.83  4731.0  488.11  4799.5  490.42
  4916.3  487.89  4927.1  487.47  4933.6  489.62  4941.4  488.03  4947.9  490.43
  4955.8  488.18  4962.2  490.99  4970.1  488.09  4976.6  490.91  4987.9  486.12
  4990.7  485.62  4993.9  486.12  4998.2  487.68  5019.6  486.38  5040.4  488.83
  5100.6  490.08  5105.6  488.47  5148.7  488.20  5708.8  488.56  5784.9  491.85
#Mann=7,-1,0
  3571.4    0.05       0  4479.2    0.16       0  4629.1    0.05       0
  4916.3    0.12       0  4987.9    0.03       0  4993.9    0.12       0
  4998.2    0.05       0
Bank Sta=4987.9,4993.9
Exp/Cntr=0.3,0.1

Chan Stop Cuts=-1