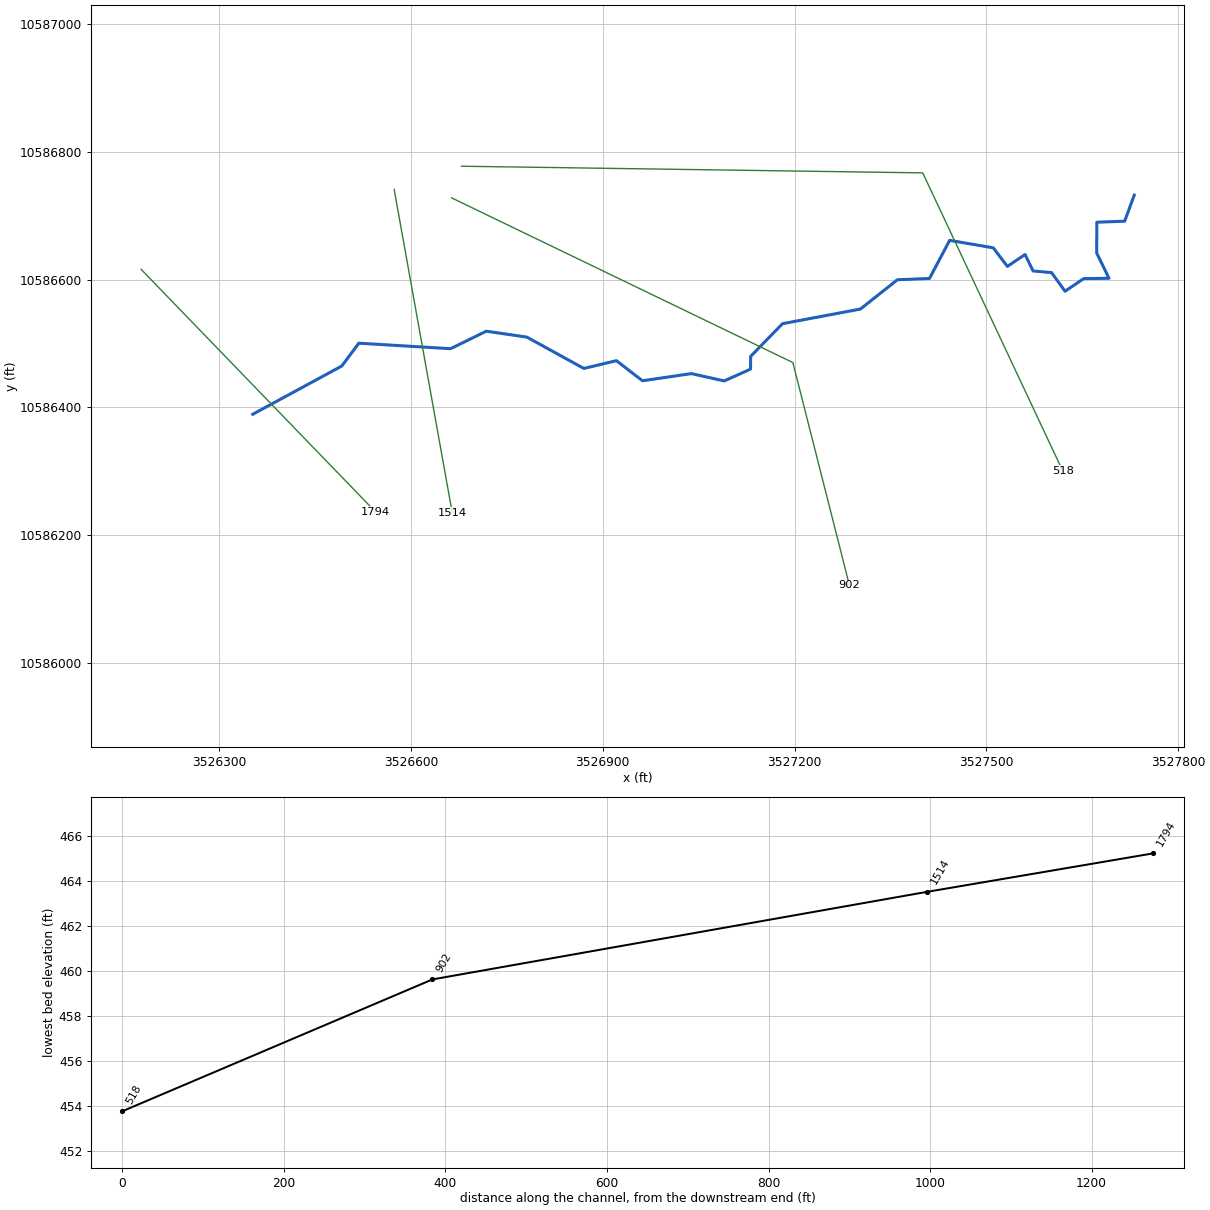
--- UNT01481 IN SAND CR.prj (project) ---

Proj Title=UNT01481 IN SAND CR Base Level Engineering
Current Plan=p01
Default Exp/Contr=0.3,0.1
English Units
Geom File=g01
Flow File=f01
Plan File=p01
BEGIN DESCRIPTION:
UNT01481 IN SAND CR
END DESCRIPTION:

--- UNT01481 IN SAND CR.p01 (plan) ---

Plan Title=Multiple Run
Short Identifier=Multiple
Geom File=g01
Flow File=f01
Subcritical Flow
K Sum by GR= 0
Std Step Tol= 0.01
Critical Tol= 0.01
Num of Std Step Trials= 20
Max Error Tol= 0.3
Flow Tol Ratio= 0.001
Split Flow NTrial= 30
Split Flow Tol= 0.02
Split Flow Ratio= 0.02
Log Output Level= 0
Friction Slope Method= 1
Unsteady Friction Slope Method= 2
Unsteady Bridges Friction Slope Method= 1
Parabolic Critical Depth
Global Vel Dist=  1 , 1 , 1
Global Log Level= 0
CheckData=True
Encroach Param= -1, 0, 0, 0
BEGIN DESCRIPTION:
Multiple Run
END DESCRIPTION:

--- UNT01481 IN SAND CR.f01 (steady flow) ---

Flow Title=Multiple
Number of Profiles=7
Profile Names=10-year,25-year,50-year,1pct_min,100-year,1pct_plu,500-year
River Rch & RM= UNT01481 IN SAND,Reach-1,1794
     277     351     407     347     469     634     617
Boundary for River Rch & Prof#=UNT01481 IN SAND,Reach-1,1
Up Type=0
Dn Type=3
Dn Slope=0.005
Boundary for River Rch & Prof#=UNT01481 IN SAND,Reach-1,2
Up Type=0
Dn Type=3
Dn Slope=0.005
Boundary for River Rch & Prof#=UNT01481 IN SAND,Reach-1,3
Up Type=0
Dn Type=3
Dn Slope=0.005
Boundary for River Rch & Prof#=UNT01481 IN SAND,Reach-1,4
Up Type=0
Dn Type=3
Dn Slope=0.005
Boundary for River Rch & Prof#=UNT01481 IN SAND,Reach-1,5
Up Type=0
Dn Type=3
Dn Slope=0.005
Boundary for River Rch & Prof#=UNT01481 IN SAND,Reach-1,6
Up Type=0
Dn Type=3
Dn Slope=0.005
Boundary for River Rch & Prof#=UNT01481 IN SAND,Reach-1,7
Up Type=0
Dn Type=3
Dn Slope=0.005

--- UNT01481 IN SAND CR.g01 (geometry) ---

Geom Title=Existing Conditions

River Reach=UNT01481 IN SAND,Reach-1
Reach XY= 30
      3526352.63     10586389.29      3526491.93     10586464.83
      3526518.51     10586500.52      3526661.97     10586491.89
      3526717.87     10586519.31      3526781.31     10586510.03
      3526870.47     10586460.98      3526921.36     10586473.16
      3526962.14     10586441.71      3527038.70     10586452.91
      3527090.01     10586441.45      3527131.15     10586459.94
      3527131.41     10586479.99      3527181.15     10586531.03
      3527303.03     10586553.95      3527360.84     10586599.78
      3527411.10     10586601.86      3527442.61     10586661.50
      3527510.84     10586649.78      3527532.86     10586620.66
      3527560.58     10586639.36      3527573.08     10586613.58
      3527601.98     10586610.98      3527623.08     10586581.81
      3527652.25     10586601.60      3527691.83     10586602.13
      3527672.56     10586641.71      3527672.82     10586689.89
      3527716.31     10586691.45      3527731.30     10586732.21

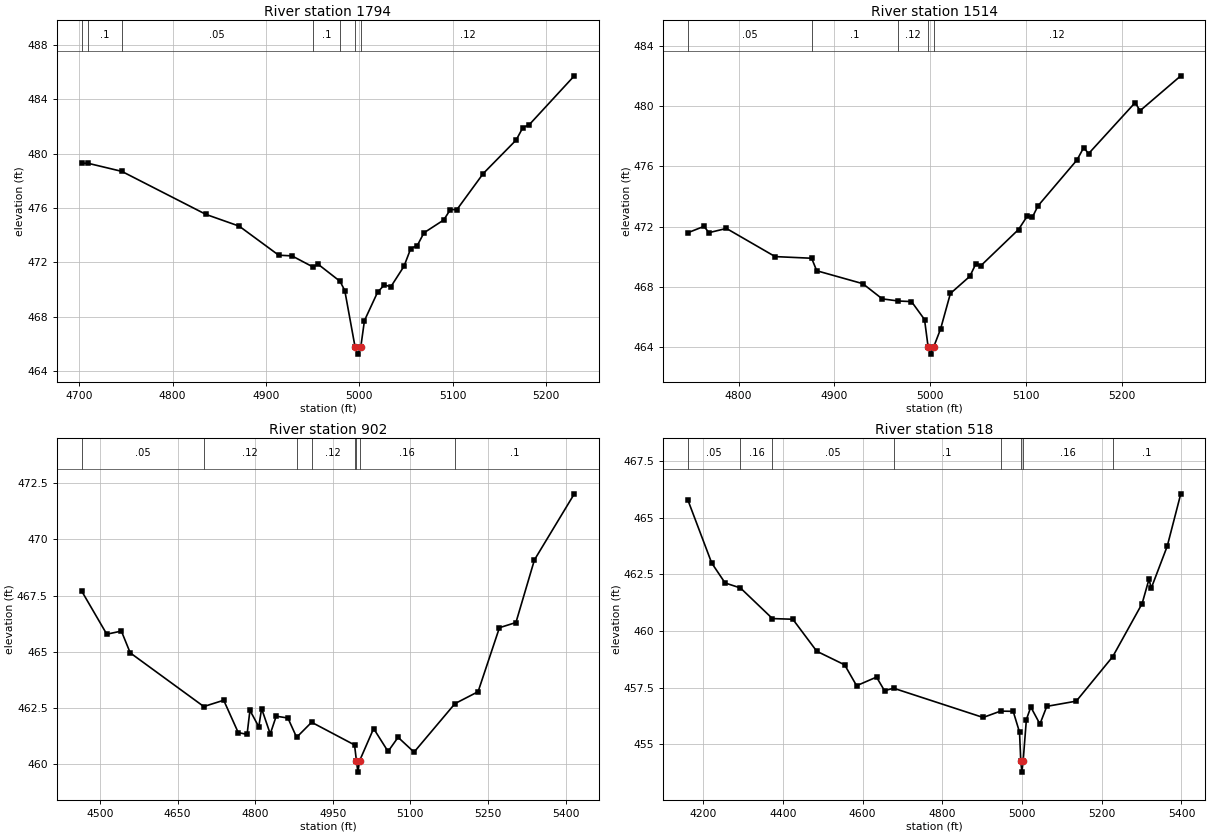
Type RM Length L Ch R = 1,1794,280,280,280
BEGIN DESCRIPTION:
UNT01481 IN SAND CR 1.0
END DESCRIPTION:
XS GIS Cut Line= 2
      3526177.94     10586616.20      3526544.80     10586236.33
#Sta/Elev= 30
  4702.4  479.29  4709.6  479.28  4745.5  478.69  4835.8  475.52  4871.3  474.66
  4913.7  472.52  4927.9  472.47  4950.0  471.67  4956.2  471.84  4979.4  470.60
  4984.5  469.92  4995.6  465.74  4998.4  465.24  5001.6  465.74  5005.6  467.71
  5019.7  469.80  5026.9  470.33  5033.9  470.20  5048.0  471.71  5055.2  473.01
  5062.2  473.23  5069.4  474.17  5090.5  475.11  5097.7  475.88  5104.6  475.87
  5132.9  478.53  5168.1  480.99  5175.3  481.90  5182.3  482.13  5230.5  485.72
#Mann=7,-1,0
  4702.4    0.05       0  4709.6     0.1       0  4745.5    0.05       0
  4950.0     0.1       0  4979.4    0.12       0  4995.6    0.07       0
  5001.6    0.12       0
Bank Sta=4995.6,5001.6
Exp/Cntr=0.3,0.1

Type RM Length L Ch R = 1,1514,612,612,612
BEGIN DESCRIPTION:
UNT01481 IN SAND CR 1.1
END DESCRIPTION:
XS GIS Cut Line= 2
      3526573.80     10586741.14      3526664.64     10586235.03
#Sta/Elev= 30
  4747.2  471.60  4763.9  472.02  4769.0  471.60  4787.3  471.88  4838.1  470.01
  4876.2  469.90  4881.5  469.07  4929.6  468.21  4949.9  467.20  4966.8  467.06
  4980.4  467.02  4994.0  465.83  4997.7  464.03  5000.4  463.53  5003.7  464.03
  5010.8  465.21  5021.0  467.56  5041.3  468.70  5047.7  469.55  5052.7  469.40
  5092.1  471.81  5101.4  472.72  5106.4  472.61  5112.4  473.38  5153.1  476.43
  5160.1  477.25  5165.2  476.85  5213.8  480.24  5218.9  479.70  5261.4  482.02
#Mann=5,-1,0
  4747.2    0.05       0  4876.2     0.1       0  4966.8    0.12       0
  4997.7    0.07       0  5003.7    0.12       0
Bank Sta=4997.7,5003.7
Exp/Cntr=0.3,0.1

Type RM Length L Ch R = 1,902,384,384,384
BEGIN DESCRIPTION:
UNT01481 IN SAND CR 2.0
END DESCRIPTION:
XS GIS Cut Line= 3
      3526663.48     10586728.06      3527197.37     10586470.23
      3527285.91     10586121.27
#Sta/Elev= 30
  4464.1  467.71  4512.9  465.78  4541.1  465.92  4558.2  464.95  4700.5  462.56
  4739.0  462.84  4767.1  461.40  4784.2  461.32  4789.7  462.39  4806.8  461.66
  4812.3  462.47  4829.0  461.34  4840.5  462.13  4863.1  462.05  4880.0  461.19
  4909.0  461.86  4992.0  460.85  4995.7  460.14  4998.5  459.64  5001.7  460.14
  5028.9  461.58  5056.8  460.56  5076.2  461.19  5107.1  460.53  5186.2  462.69
  5230.9  463.22  5272.2  466.07  5304.1  466.30  5339.9  469.09  5417.0  472.03
#Mann=8,-1,0
  4464.1    0.05       0  4700.5    0.12       0  4880.0    0.16       0
  4909.0    0.12       0  4992.0    0.16       0  4995.7    0.07       0
  5001.7    0.16       0  5186.2     0.1       0
Bank Sta=4995.7,5001.7
Exp/Cntr=0.3,0.1

Type RM Length L Ch R = 1,518,0,0,0
BEGIN DESCRIPTION:
UNT01481 IN SAND CR 3.0
END DESCRIPTION:
XS GIS Cut Line= 3
      3526679.12     10586777.52      3527400.49     10586767.10
      3527619.26     10586300.93
#Sta/Elev= 30
  4161.9  465.76  4221.3  463.00  4254.9  462.12  4293.4  461.90  4373.7  460.55
  4424.9  460.52  4484.9  459.11  4554.9  458.51  4584.9  457.59  4634.9  457.97
  4654.9  457.37  4677.6  457.48  4902.4  456.19  4946.1  456.47  4977.8  456.46
  4993.7  455.54  4996.8  454.28  4999.6  453.78  5002.8  454.28  5010.9  456.10
  5022.0  456.65  5044.9  455.90  5062.1  456.68  5136.1  456.91  5227.5  458.87
  5301.3  461.21  5318.6  462.29  5324.2  461.89  5364.3  463.74  5398.3  466.05
#Mann=8,-1,0
  4161.9    0.05       0  4293.4    0.16       0  4373.7    0.05       0
  4677.6     0.1       0  4946.1    0.16       0  4996.8    0.07       0
  5002.8    0.16       0  5227.5     0.1       0
Bank Sta=4996.8,5002.8
Exp/Cntr=0.3,0.1

Chan Stop Cuts=-1