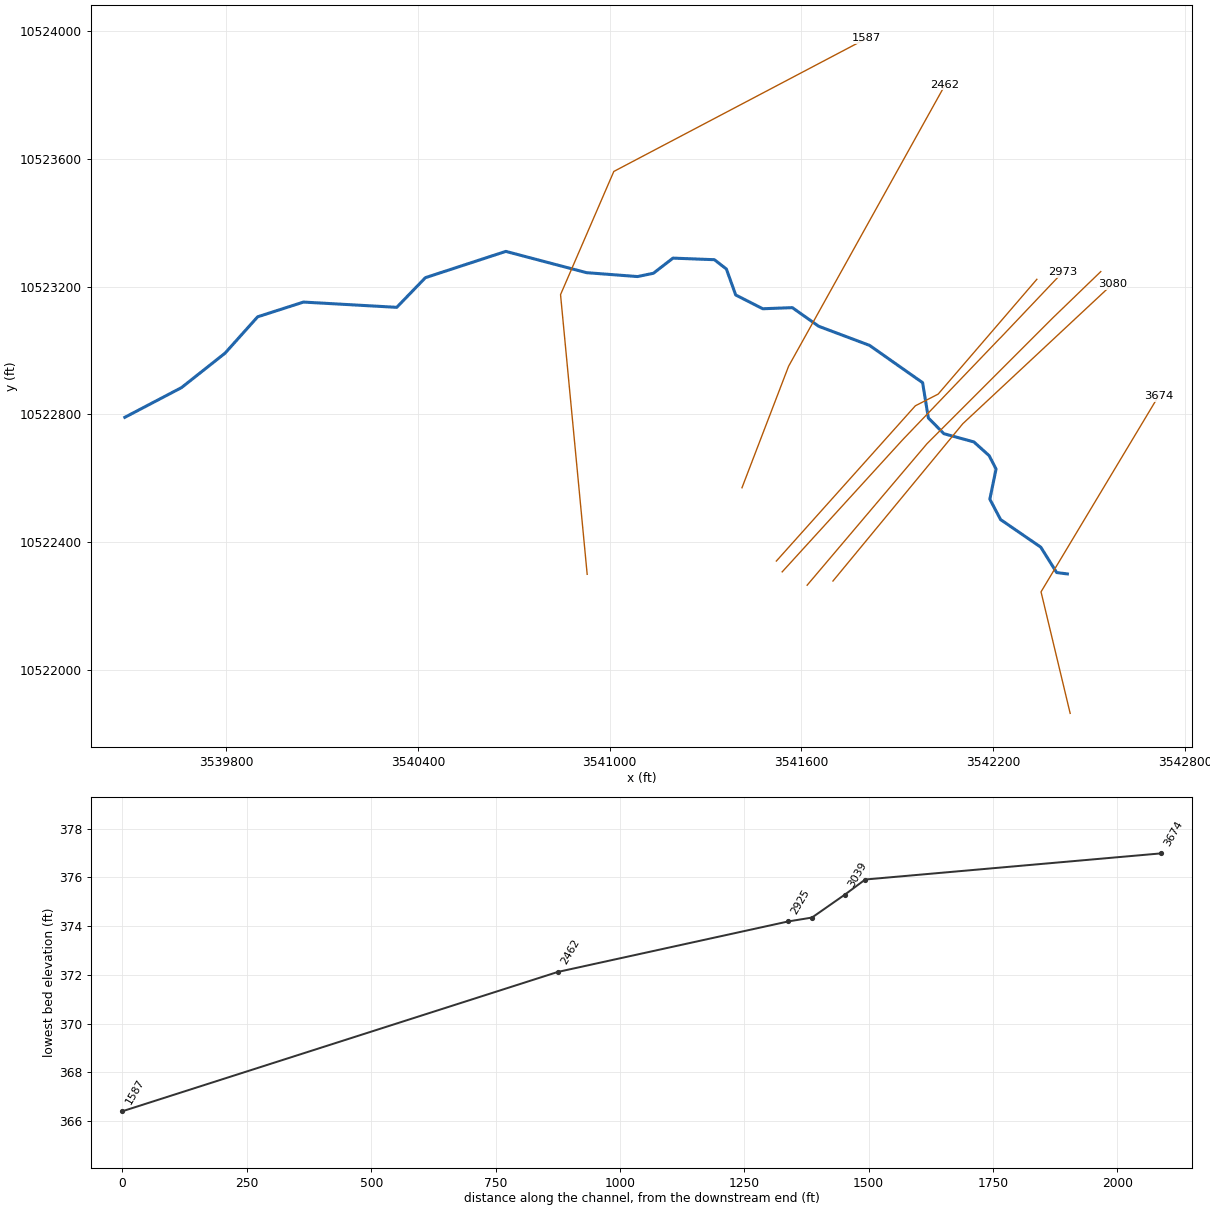
--- UNT0149 IN SAND CR.prj (project) ---

Proj Title=UNT0149 IN SAND CR Base Level Engineering
Current Plan=p01
Default Exp/Contr=0.3,0.1
English Units
Geom File=g01
Flow File=f01
Plan File=p01
Y Axis Title=Elevation
X Axis Title(PF)=Main Channel Distance
X Axis Title(XS)=Station
BEGIN DESCRIPTION:
UNT0149 IN SAND CR
END DESCRIPTION:
DSS Export Rating Curves= 0
DSS Export Rating Curve Sorted= 0
DSS Export Volume Flow Curves= 0
DXF OffsetX= 0
DXF OffsetY= 0
DXF ScaleX= 1
DXF ScaleY= 10

--- UNT0149 IN SAND CR.p01 (plan) ---

Plan Title=Multiple Run
Short Identifier=Multiple
Geom File=g01
Flow File=f01
Subcritical Flow
K Sum by GR= 0
Std Step Tol= 0.01
Critical Tol= 0.01
Num of Std Step Trials= 20
Max Error Tol= 0.3
Flow Tol Ratio= 0.001
Split Flow NTrial= 30
Split Flow Tol= 0.02
Split Flow Ratio= 0.02
Log Output Level= 0
Friction Slope Method= 1
Unsteady Friction Slope Method= 2
Unsteady Bridges Friction Slope Method= 1
Parabolic Critical Depth
Global Vel Dist=  1 , 1 , 1
Global Log Level= 0
CheckData=True
Encroach Param= -1, 0, 0, 0
BEGIN DESCRIPTION:
Multiple Run
END DESCRIPTION:

--- UNT0149 IN SAND CR.f01 (steady flow) ---

Flow Title=Multiple
Number of Profiles=7
Profile Names=10-year,25-year,50-year,1pct_min,100-year,1pct_plu,500-year
River Rch & RM= UNT0149 IN SAND ,Reach-1,3674
     985    1350    1651    1472    1991    2692    2887
Boundary for River Rch & Prof#=UNT0149 IN SAND ,Reach-1,1
Up Type=0
Dn Type=3
Dn Slope=0.005
Boundary for River Rch & Prof#=UNT0149 IN SAND ,Reach-1,2
Up Type=0
Dn Type=3
Dn Slope=0.005
Boundary for River Rch & Prof#=UNT0149 IN SAND ,Reach-1,3
Up Type=0
Dn Type=3
Dn Slope=0.005
Boundary for River Rch & Prof#=UNT0149 IN SAND ,Reach-1,4
Up Type=0
Dn Type=3
Dn Slope=0.005
Boundary for River Rch & Prof#=UNT0149 IN SAND ,Reach-1,5
Up Type=0
Dn Type=3
Dn Slope=0.005
Boundary for River Rch & Prof#=UNT0149 IN SAND ,Reach-1,6
Up Type=0
Dn Type=3
Dn Slope=0.005
Boundary for River Rch & Prof#=UNT0149 IN SAND ,Reach-1,7
Up Type=0
Dn Type=3
Dn Slope=0.005

--- UNT0149 IN SAND CR.g01 (geometry) ---

Geom Title=Existing Conditions
Program Version=4.10

River Reach=UNT0149 IN SAND ,Reach-1
Reach XY= 30
      3542432.22     10522301.06      3542398.73     10522305.34
      3542348.87     10522384.88       3542223.2     10522471.16
      3542189.64     10522534.93      3542209.09     10522629.37
      3542187.56     10522671.04      3542139.64      10522714.1
      3542045.89     10522739.79      3541997.28      10522789.1
      3541979.22     10522899.51      3541813.25     10523016.18
      3541654.22      10523075.9      3541571.59     10523134.23
      3541479.22     10523130.76       3541394.5     10523173.82
      3541365.33     10523255.07      3541327.84     10523284.23
      3541198.23     10523289.15        3541137.     10523241.79
      3541087.35     10523231.47      3540927.75     10523243.65
      3540675.18     10523310.22      3540423.62     10523227.99
      3540333.91     10523135.16      3540042.11     10523151.64
      3539898.71     10523105.53      3539796.62     10522991.64
      3539660.51       10522884.       3539483.2     10522791.06

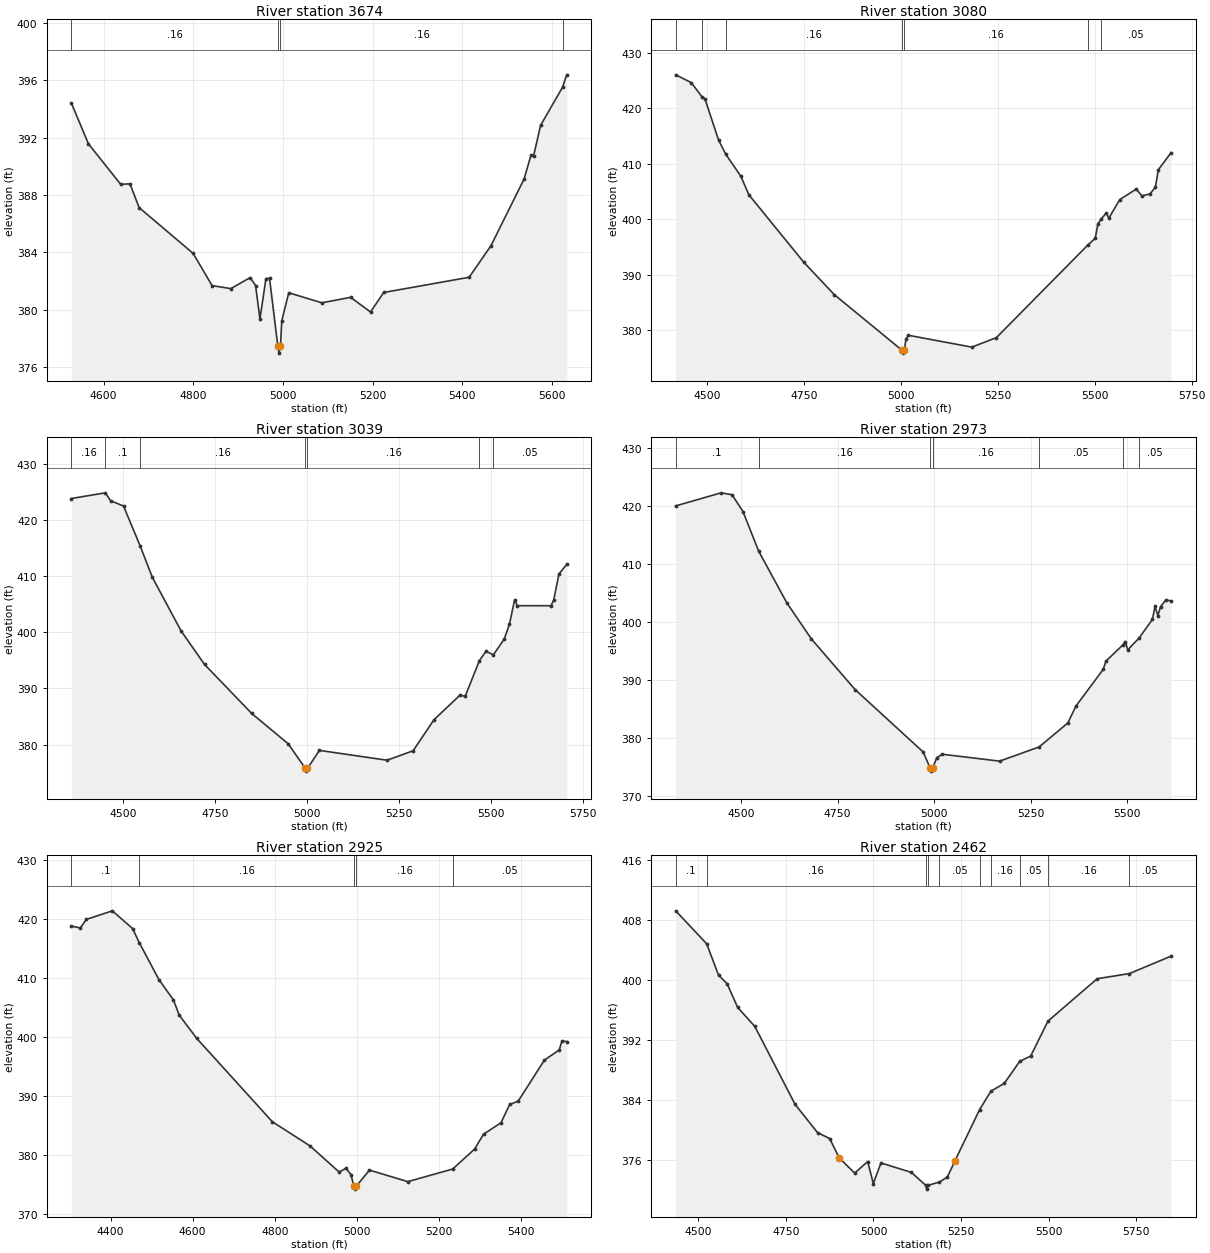
Type RM Length L Ch R = 1 ,3674    ,594,594,594
BEGIN DESCRIPTION:
UNT0149 IN SAND CR 5.1
END DESCRIPTION:
XS GIS Cut Line= 3
      3542440.96     10521864.77      3542349.81     10522245.01
       3542716.9     10522856.82
#Sta/Elev= 30
  4528.3  394.41  4566.2  391.58  4638.2  388.75  4658.8  388.79  4679.3  387.13
  4799.9  383.93  4841.9  381.69  4883.9  381.48    4927  382.25    4939  381.69
  4948.7  379.36    4962  382.17  4970.1   382.2  4988.5  377.48  4991.2  376.98
  4994.5  377.48  4997.3  379.22  5012.9  381.19  5086.7  380.49  5150.9  380.87
  5195.3  379.85  5224.7  381.21  5415.2  382.27  5463.8  384.47  5537.7  389.12
  5553.2  390.79    5559  390.75  5574.6  392.87  5623.6  395.53  5632.8  396.39
#Mann= 4 ,-1 , 0
  4528.3     .16       0  4988.5     .07       0  4994.5     .16       0
  5623.6      .1       0
Bank Sta=4988.5,4994.5
XS Rating Curve= 0 ,0
Exp/Cntr=0.3,0.1

Type RM Length L Ch R = 1 ,3080    ,41,41,41
BEGIN DESCRIPTION:
UNT0149 IN SAND CR 5.2
END DESCRIPTION:
XS GIS Cut Line= 3
      3541698.79     10522278.89      3542105.02     10522771.05
      3542572.78     10523207.63
#Sta/Elev= 30
  4418.8     426    4459  424.59  4486.9  422.01  4494.2  421.66  4529.3  414.26
  4547.8  411.71  4586.7  407.76  4607.5  404.41  4749.5  392.24  4827.7  386.45
  5002.9  376.41  5005.6  375.91  5008.9  376.41  5012.7  378.47  5019.2  379.12
  5182.7  376.99  5246.2   378.7  5483.2  395.44  5501.2  396.57    5508  399.17
    5517  400.08  5529.5  401.14  5536.4  400.23  5564.7  403.55  5607.2  405.45
  5621.4  404.21  5642.4  404.56  5656.5  405.77  5663.9   408.9  5696.8  411.99
#Mann= 7 ,-1 , 0
  4418.8     .16       0  4486.9     .05       0  4547.8     .16       0
  5002.9     .07       0  5008.9     .16       0  5483.2      .1       0
    5517     .05       0
Bank Sta=5002.9,5008.9
XS Rating Curve= 0 ,0
Exp/Cntr=0.3,0.1

Type RM Length L Ch R = 1 ,3039    ,66,66,66
BEGIN DESCRIPTION:
UNT0149 IN SAND CR 5.0
END DESCRIPTION:
XS GIS Cut Line= 4
      3541618.01     10522265.81      3541993.04     10522708.55
      3542386.27     10523101.78      3542536.74     10523247.06
#Sta/Elev= 30
  4360.2   423.8  4452.3  424.81  4466.6   423.4  4501.7  422.46  4547.5  415.27
  4579.7  409.82  4657.7  400.28  4721.7  394.28    4850  385.55    4949  380.16
  4995.5  375.79  4998.3  375.29  5001.5  375.79  5033.9  378.98  5217.7  377.23
  5288.4  378.91    5345  384.43  5415.7  388.81  5429.9   388.6  5468.6  394.96
  5486.4  396.61  5506.5  395.99  5535.9  398.79    5550   401.4  5564.2  405.78
  5571.4  404.73  5663.2  404.72  5670.4  405.75  5684.6  410.37  5705.7  412.08
#Mann= 7 ,-1 , 0
  4360.2     .16       0  4452.3      .1       0  4547.5     .16       0
  4995.5     .07       0  5001.5     .16       0  5468.6      .1       0
  5506.5     .05       0
Bank Sta=4995.5,5001.5
XS Rating Curve= 0 ,0
Exp/Cntr=0.3,0.1

Type RM Length L Ch R = 1 ,2973    ,48,48,48
BEGIN DESCRIPTION:
UNT0149 IN SAND CR 5.3
END DESCRIPTION:
XS GIS Cut Line= 5
      3541539.92     10522307.52      3541917.52     10522721.57
        3542217.     10523034.07      3542224.81     10523041.88
      3542417.35     10523244.83
#Sta/Elev= 30
  4330.3  420.05  4447.9   422.3  4476.3  421.97  4504.6  419.07  4545.4  412.23
  4618.1  403.37  4681.6  397.15  4795.1  388.41  4971.9  377.64    4990  374.85
  4992.7  374.35    4996  374.85  5007.1  376.65  5021.3  377.26  5169.7  376.07
  5272.3  378.51  5346.8  382.65  5367.8  385.56  5438.6  391.89  5445.5   393.3
  5490.4  396.16  5495.2  396.67  5502.1  395.25  5531.2  397.26    5566  400.48
  5572.9  402.78  5580.2  401.14  5587.1  402.69  5601.2  403.86  5614.3  403.67
#Mann= 7 ,-1 , 0
  4330.3      .1       0  4545.4     .16       0    4990     .07       0
    4996     .16       0  5272.3     .05       0  5490.4      .1       0
  5531.2     .05       0
Bank Sta=4990,4996
XS Rating Curve= 0 ,0
Exp/Cntr=0.3,0.1

Type RM Length L Ch R = 1 ,2925    ,463,463,463
BEGIN DESCRIPTION:
UNT0149 IN SAND CR 5.4
END DESCRIPTION:
XS GIS Cut Line= 4
      3541521.69     10522341.37      3541956.58     10522827.13
      3542027.76     10522863.58      3542336.77     10523222.94
#Sta/Elev= 30
  4304.8  418.75  4326.6  418.44  4340.8  419.88  4404.3  421.34  4453.7  418.34
  4469.9  415.96    4518  409.67  4553.1  406.25  4567.3  403.66    4610  399.72
  4793.9  385.61  4885.8  381.51  4956.5  377.09  4973.1  377.71  4985.5  376.66
  4992.3  374.69  4995.1  374.19  4998.3  374.69  5030.4  377.41  5123.9  375.46
  5233.2   377.6  5286.3  380.97  5308.2  383.49  5350.7  385.44  5371.8  388.53
  5392.7  389.11  5456.3  396.04  5492.5  397.77  5499.1  399.29  5510.7  399.19
#Mann= 5 ,-1 , 0
  4304.8      .1       0  4469.9     .16       0  4992.3     .07       0
  4998.3     .16       0  5233.2     .05       0
Bank Sta=4992.3,4998.3
XS Rating Curve= 0 ,0
Exp/Cntr=0.3,0.1

Type RM Length L Ch R = 1 ,2462    ,875,875,875
BEGIN DESCRIPTION:
UNT0149 IN SAND CR 3.0
END DESCRIPTION:
XS GIS Cut Line= 3
      3541414.13     10522570.69      3541559.98     10522950.94
      3542049.58     10523831.18
#Sta/Elev= 30
  4435.4  409.21  4523.8  404.81  4557.5  400.65  4582.2  399.49  4612.2  396.34
  4661.3   393.8  4776.3  383.41  4840.4  379.65    4875  378.86  4902.4  376.27
  4946.5  374.26  4983.6   375.8  4999.6  372.85  5021.4  375.61  5108.3  374.35
  5149.4  372.62  5152.2  372.12  5155.4  372.62  5188.3  373.06  5211.2  373.74
  5232.9   375.9  5303.1  382.71  5335.4  385.17  5373.6  386.21  5417.9  389.16
  5449.1  389.86  5498.4  394.51  5638.9  400.16  5731.2  400.85  5849.9  403.17
#Mann= 10 ,-1 , 0
  4435.4      .1       0  4523.8     .16       0  5149.4     .07       0
  5155.4     .16       0  5188.3     .05       0  5303.1      .1       0
  5335.4     .16       0  5417.9     .05       0  5498.4     .16       0
  5731.2     .05       0
Bank Sta=4902.4,5232.9
XS Rating Curve= 0 ,0
Exp/Cntr=0.3,0.1

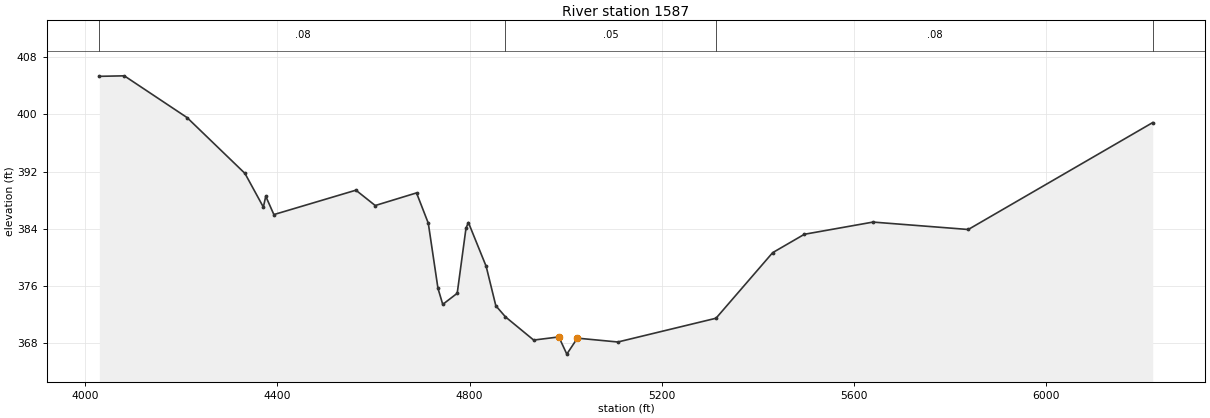
Type RM Length L Ch R = 1 ,1587    ,0,0,0
BEGIN DESCRIPTION:
UNT0149 IN SAND CR 1.0
END DESCRIPTION:
XS GIS Cut Line= 4
      3540929.78     10522299.86      3540846.44      10523174.9
      3541013.11     10523560.31      3541804.48     10523976.83
#Sta/Elev= 30
  4029.3  405.35  4081.3  405.42  4211.9  399.57  4332.5  391.74  4370.8  387.02
  4375.8  388.54  4392.7  385.97  4563.5  389.39  4603.7  387.24  4689.7  389.01
  4714.2  384.76  4734.3  375.64  4744.3  373.38  4774.4  374.94  4792.7  384.07
  4797.7  384.86  4834.7  378.71  4854.8  373.19  4874.9  371.63  4933.6  368.38
    4986  368.82  5002.6  366.41  5024.6  368.65  5108.9  368.11  5313.2  371.44
  5431.1  380.63  5497.2  383.21  5640.1  384.92  5838.4  383.88  6222.5  398.87
#Mann= 4 ,-1 , 0
  4029.3     .08       0  4874.9     .05       0  5313.2     .08       0
  6222.5     .16       0
Bank Sta=4986,5024.6
XS Rating Curve= 0 ,0
Exp/Cntr=0.3,0.1

Chan Stop Cuts=-1
Use User Specified Reach Order=0
Composite Channel Slope=5