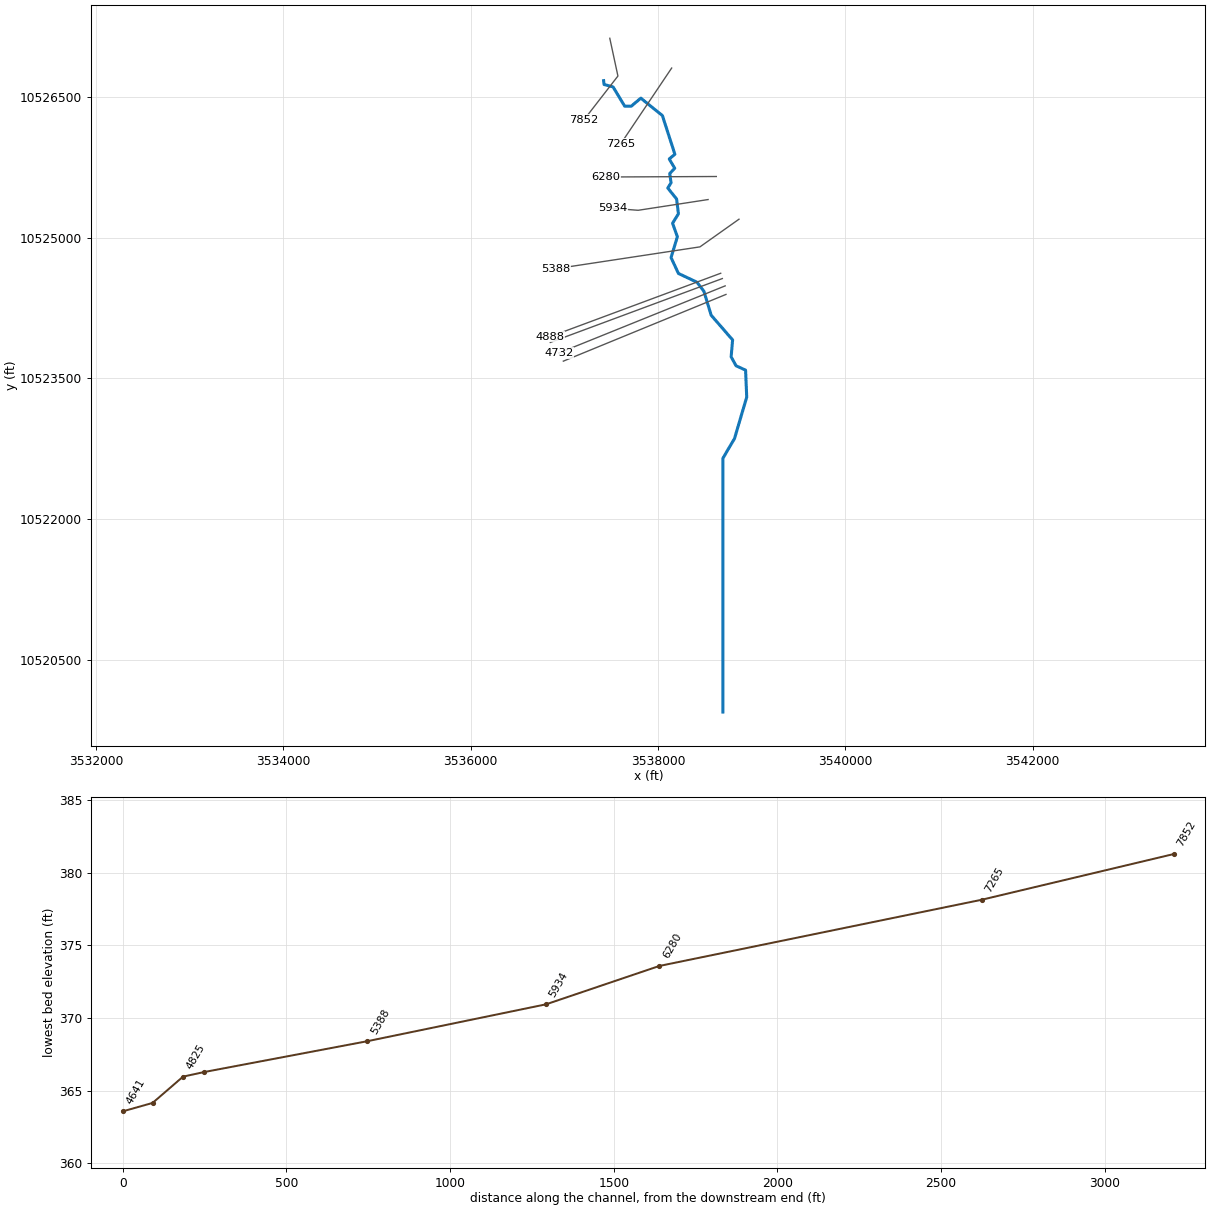
--- UNT0150 IN SAND CR.prj (project) ---

Proj Title=UNT0150 IN SAND CR Base Level Engineering
Current Plan=p01
Default Exp/Contr=0.3,0.1
English Units
Geom File=g01
Flow File=f01
Plan File=p01
BEGIN DESCRIPTION:
UNT0150 IN SAND CR
END DESCRIPTION:

--- UNT0150 IN SAND CR.p01 (plan) ---

Plan Title=Multiple Run
Short Identifier=Multiple
Geom File=g01
Flow File=f01
Subcritical Flow
K Sum by GR= 0
Std Step Tol= 0.01
Critical Tol= 0.01
Num of Std Step Trials= 20
Max Error Tol= 0.3
Flow Tol Ratio= 0.001
Split Flow NTrial= 30
Split Flow Tol= 0.02
Split Flow Ratio= 0.02
Log Output Level= 0
Friction Slope Method= 1
Unsteady Friction Slope Method= 2
Unsteady Bridges Friction Slope Method= 1
Parabolic Critical Depth
Global Vel Dist=  1 , 1 , 1
Global Log Level= 0
CheckData=True
Encroach Param= -1, 0, 0, 0
BEGIN DESCRIPTION:
Multiple Run
END DESCRIPTION:

--- UNT0150 IN SAND CR.f01 (steady flow) ---

Flow Title=Multiple
Number of Profiles=7
Profile Names=10-year,25-year,50-year,1pct_min,100-year,1pct_plu,500-year
River Rch & RM= UNT0150 IN SAND ,Reach-1,7852
     881    1195    1450    1284    1736    2348    2481
Boundary for River Rch & Prof#=UNT0150 IN SAND ,Reach-1,1
Up Type=0
Dn Type=3
Dn Slope=0.005
Boundary for River Rch & Prof#=UNT0150 IN SAND ,Reach-1,2
Up Type=0
Dn Type=3
Dn Slope=0.005
Boundary for River Rch & Prof#=UNT0150 IN SAND ,Reach-1,3
Up Type=0
Dn Type=3
Dn Slope=0.005
Boundary for River Rch & Prof#=UNT0150 IN SAND ,Reach-1,4
Up Type=0
Dn Type=3
Dn Slope=0.005
Boundary for River Rch & Prof#=UNT0150 IN SAND ,Reach-1,5
Up Type=0
Dn Type=3
Dn Slope=0.005
Boundary for River Rch & Prof#=UNT0150 IN SAND ,Reach-1,6
Up Type=0
Dn Type=3
Dn Slope=0.005
Boundary for River Rch & Prof#=UNT0150 IN SAND ,Reach-1,7
Up Type=0
Dn Type=3
Dn Slope=0.005

--- UNT0150 IN SAND CR.g01 (geometry) ---

Geom Title=Existing Conditions

River Reach=UNT0150 IN SAND ,Reach-1
Reach XY= 30
      3537418.96     10526677.42      3537423.91     10526635.74
      3537519.83     10526610.47      3537643.69     10526404.94
      3537713.85     10526404.48      3537816.13     10526490.52
      3538046.48     10526304.08      3538179.64     10525891.72
      3538119.40     10525841.59      3538178.04     10525742.32
      3538124.33     10525686.04      3538138.83     10525587.22
      3538103.57     10525531.50      3538197.64     10525414.57
      3538217.49     10525257.15      3538154.91     10525155.86
      3538206.11     10525011.68      3538138.78     10524789.96
      3538217.45     10524620.42      3538414.94     10524526.87
      3538489.35     10524430.51      3538567.02     10524174.63
      3538795.84     10523911.09      3538780.21     10523731.23
      3538832.30     10523635.52      3538934.29     10523588.87
      3538946.50     10523300.80      3538816.30     10522859.40
      3538692.11     10522648.46      3538692.11     10519941.64

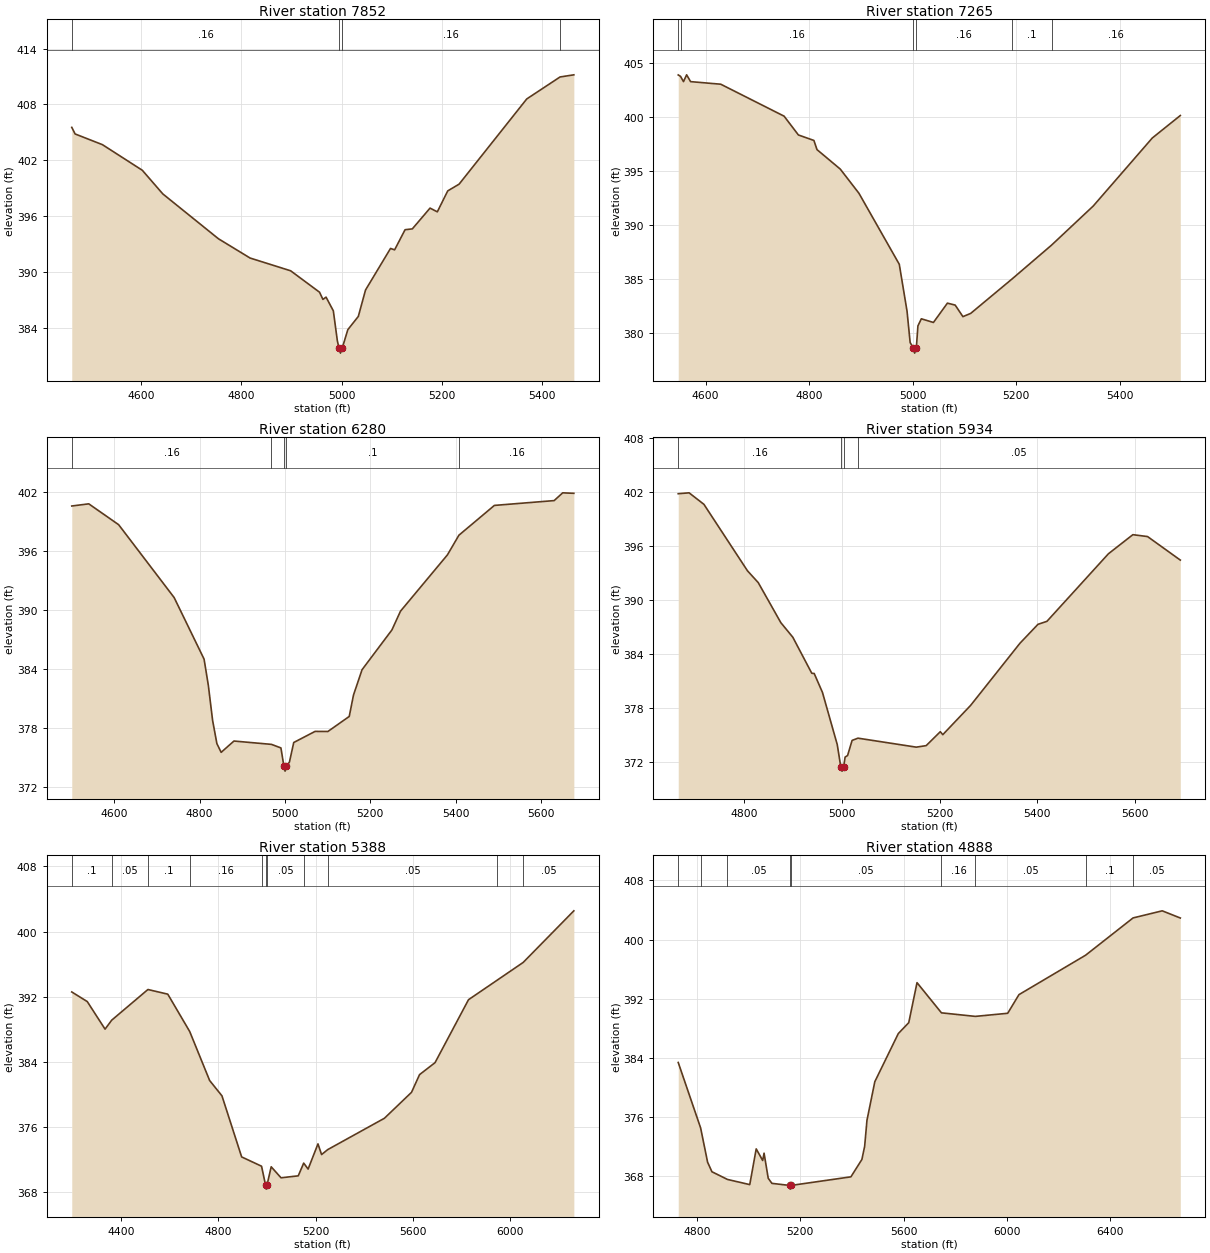
Type RM Length L Ch R = 1,7852,587,587,587
BEGIN DESCRIPTION:
UNT0150 IN SAND CK 1.3
END DESCRIPTION:
XS GIS Cut Line= 3
      3537484.81     10527129.18      3537571.63     10526726.36
      3537210.54     10526261.11
#Sta/Elev= 30
  4462.0  405.54  4468.7  404.83  4523.2  403.68  4602.7  400.93  4643.6  398.39
  4754.4  393.58  4817.5  391.51  4898.4  390.14  4956.0  387.84  4962.7  387.07
  4969.0  387.31  4983.5  385.84  4991.6  382.59  4995.0  381.80  4997.7  381.30
  5001.0  381.80  5012.4  383.82  5033.3  385.24  5047.7  388.08  5097.5  392.54
  5105.7  392.39  5126.5  394.55  5141.0  394.64  5176.3  396.87  5190.8  396.47
  5211.6  398.72  5234.2  399.44  5369.1  408.59  5435.5  410.95  5463.0  411.18
#Mann=4,-1,0
  4462.0    0.16       0  4995.0    0.07       0  5001.0    0.16       0
  5435.5     0.1       0
Bank Sta=4995,5001
Exp/Cntr=0.3,0.1

Type RM Length L Ch R = 1,7265,985,985,985
BEGIN DESCRIPTION:
UNT0150 IN SAND CK 1.0
END DESCRIPTION:
XS GIS Cut Line= 2
      3538145.26     10526811.46      3537603.84     10526006.27
#Sta/Elev= 30
  4547.2  403.92  4551.6  403.79  4557.4  403.30  4563.4  403.93  4571.1  403.30
  4629.4  403.06  4751.8  400.10  4779.4  398.36  4809.4  397.85  4815.4  397.00
  4860.3  395.20  4896.4  392.96  4974.4  386.38  4989.4  382.03  4995.4  379.13
  5001.4  378.65  5004.1  378.15  5007.4  378.65  5010.4  380.67  5017.0  381.33
  5040.4  380.99  5067.4  382.78  5082.4  382.60  5097.4  381.53  5112.4  381.83
  5192.1  385.01  5268.8  388.16  5349.3  391.78  5463.4  398.08  5517.5  400.16
#Mann=6,-1,0
  4547.2    0.05       0  4551.6    0.16       0  5001.4    0.07       0
  5007.4    0.16       0  5192.1     0.1       0  5268.8    0.16       0
Bank Sta=5001.4,5007.4
Exp/Cntr=0.3,0.1

Type RM Length L Ch R = 1,6280,346,346,346
BEGIN DESCRIPTION:
UNT0150 IN SAND CK 1.1
END DESCRIPTION:
XS GIS Cut Line= 2
      3538621.95     10525654.48      3537445.96     10525649.28
#Sta/Elev= 30
  4500.6  400.55  4540.4  400.77  4610.4  398.65  4740.4  391.24  4810.5  384.98
  4820.5  382.31  4830.5  378.74  4840.5  376.39  4850.5  375.50  4880.5  376.65
  4968.4  376.31  4990.5  375.95  4997.5  374.09  5000.2  373.59  5003.5  374.09
  5010.5  374.52  5020.5  376.50  5070.5  377.63  5100.5  377.62  5150.5  379.15
  5160.5  381.33  5180.5  383.90  5250.5  387.95  5270.5  389.85  5380.5  395.58
  5407.4  397.58  5490.5  400.61  5630.5  401.10  5650.5  401.89  5676.6  401.84
#Mann=5,-1,0
  4500.6    0.16       0  4968.4     0.1       0  4997.5    0.07       0
  5003.5     0.1       0  5407.4    0.16       0
Bank Sta=4997.5,5003.5
Exp/Cntr=0.3,0.1

Type RM Length L Ch R = 1,5934,546,546,546
BEGIN DESCRIPTION:
UNT0150 IN SAND CK 1.4
END DESCRIPTION:
XS GIS Cut Line= 3
      3538534.08     10525408.64      3537787.60     10525294.07
      3537515.21     10525314.76
#Sta/Elev= 30
  4664.5  401.84  4686.7  401.94  4717.1  400.66  4806.3  393.26  4828.4  391.94
  4874.7  387.48  4899.2  385.86  4938.0  381.85  4943.0  381.82  4959.9  379.72
  4990.2  373.91  4997.4  371.45  5000.1  370.95  5003.4  371.45  5006.3  372.51
  5011.4  372.69  5020.6  374.37  5032.7  374.62  5152.1  373.62  5172.4  373.79
  5201.3  375.34  5206.4  375.01  5263.4  378.27  5364.6  385.20  5401.4  387.30
  5419.7  387.63  5545.6  395.15  5595.7  397.28  5625.8  397.07  5692.9  394.45
#Mann=4,-1,0
  4664.5    0.16       0  4997.4    0.07       0  5003.4    0.16       0
  5032.7    0.05       0
Bank Sta=4997.4,5003.4
Exp/Cntr=0.3,0.1

Type RM Length L Ch R = 1,5388,500,500,500
BEGIN DESCRIPTION:
UNT0150 IN SAND CK 1.2
END DESCRIPTION:
XS GIS Cut Line= 3
      3538864.06     10525199.05      3538447.38     10524903.90
      3536912.63     10524671.25
#Sta/Elev= 30
  4198.4  392.59  4262.1  391.41  4335.2  388.03  4362.5  389.13  4511.3  392.89
  4592.9  392.32  4683.0  387.74  4764.9  381.73  4815.5  379.85  4896.4  372.36
  4978.2  371.22  4994.6  368.91  4997.3  368.41  5000.6  368.91  5017.8  371.15
  5058.2  369.80  5129.0  370.04  5151.3  371.60  5169.5  370.87  5210.0  373.96
  5224.8  372.65  5250.3  373.26  5483.0  377.10  5594.3  380.28  5627.3  382.45
  5691.0  383.92  5828.5  391.64  5947.5  394.06  6053.1  396.21  6261.3  402.54
#Mann=11,-1,0
  4198.4     0.1       0  4362.5    0.05       0  4511.3     0.1       0
  4683.0    0.16       0  4978.2    0.05       0  4994.6   0.035       0
  5000.6    0.05       0  5151.3    0.16       0  5250.3    0.05       0
  5947.5    0.08       0  6053.1    0.05       0
Bank Sta=4994.6,5000.6
Exp/Cntr=0.3,0.1

Type RM Length L Ch R = 1,4888,63,63,63
BEGIN DESCRIPTION:
UNT0150 IN SAND CK 3.0
END DESCRIPTION:
XS GIS Cut Line= 2
      3538668.73     10524622.30      3536846.47     10523945.46
#Sta/Elev= 30
  4727.8  383.40  4814.5  374.55  4841.5  369.92  4858.2  368.63  4918.4  367.59
  5004.7  366.89  5029.7  371.72  5054.8  370.15  5060.1  371.14  5076.2  367.75
  5090.5  367.06  5158.6  366.78  5161.3  366.28  5164.6  366.78  5396.3  367.94
  5438.9  370.29  5449.6  372.08  5458.5  375.58  5488.9  380.80  5579.9  387.31
  5620.3  388.78  5652.3  394.19  5746.9  390.11  5878.0  389.63  6003.4  390.05
  6047.0  392.57  6305.0  397.90  6488.8  402.94  6601.7  403.90  6671.7  402.93
#Mann=9,-1,0
  4727.8     0.1       0  4814.5    0.16       0  4918.4    0.05       0
  5158.6   0.033       0  5164.6    0.05       0  5746.9    0.16       0
  5878.0    0.05       0  6305.0     0.1       0  6488.8    0.05       0
Bank Sta=5158.6,5164.6
Exp/Cntr=0.3,0.1

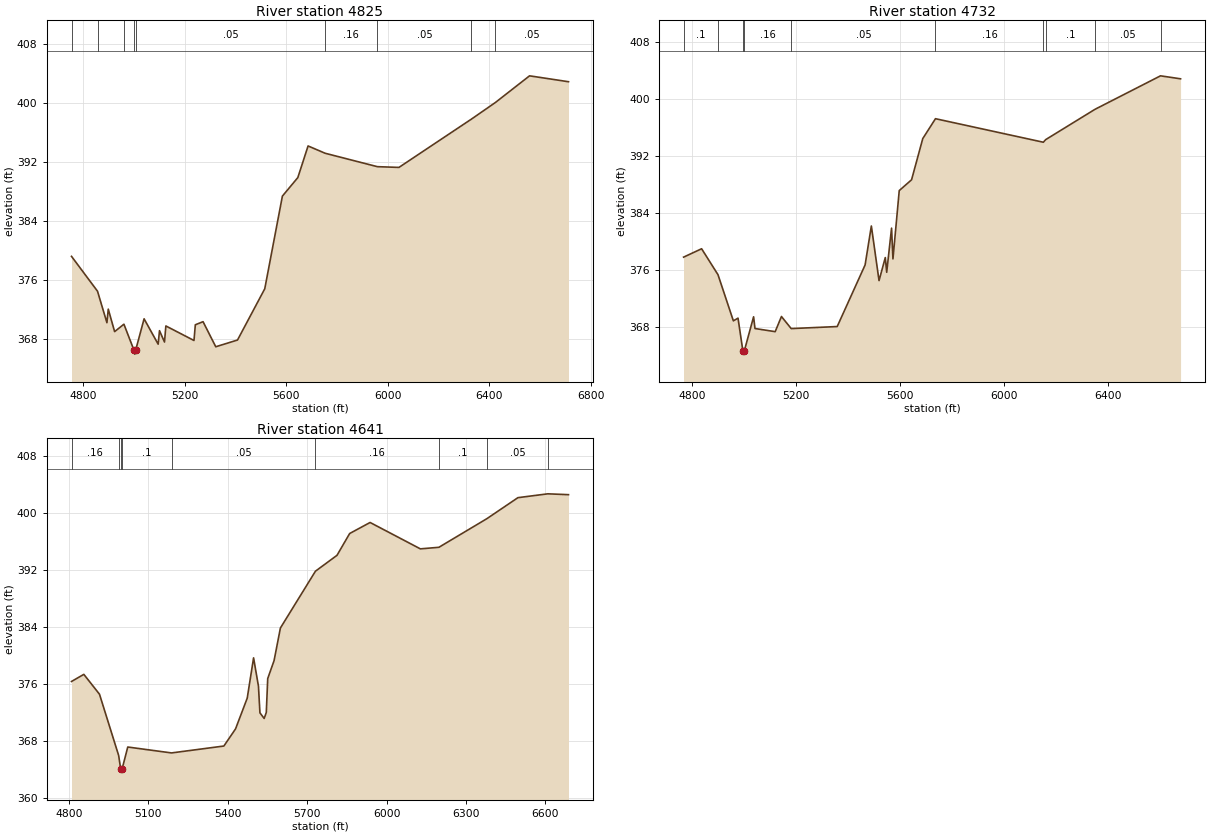
Type RM Length L Ch R = 1,4825,93,93,93
BEGIN DESCRIPTION:
UNT0150 IN SAND CK 2.0
END DESCRIPTION:
XS GIS Cut Line= 2
      3538686.05     10524565.86      3536850.13     10523884.44
#Sta/Elev= 30
  4753.7  379.23  4856.2  374.50  4893.2  370.23  4898.5  372.07  4923.6  369.02
  4960.2  370.03  5000.2  366.47  5003.0  365.97  5006.2  366.47  5039.7  370.76
  5095.1  367.32  5100.4  369.15  5120.1  367.61  5125.5  369.79  5236.3  367.82
  5241.6  369.95  5272.0  370.37  5322.1  366.97  5407.8  367.88  5515.2  374.83
  5584.7  387.40  5645.5  389.91  5685.9  394.20  5753.1  393.21  5959.0  391.39
  6044.0  391.29  6329.6  397.84  6424.3  400.10  6558.6  403.71  6712.0  402.91
#Mann=9,-1,0
  4753.7     0.1       0  4856.2    0.16       0  4960.2    0.05       0
  5000.2   0.033       0  5006.2    0.05       0  5753.1    0.16       0
  5959.0    0.05       0  6329.6     0.1       0  6424.3    0.05       0
Bank Sta=5000.2,5006.2
Exp/Cntr=0.3,0.1

Type RM Length L Ch R = 1,4732,91,91,91
BEGIN DESCRIPTION:
UNT0150 IN SAND CK 4.0
END DESCRIPTION:
XS GIS Cut Line= 2
      3538716.47     10524487.75      3536941.28     10523771.60
#Sta/Elev= 30
  4767.0  377.80  4836.4  378.98  4899.5  375.33  4958.7  368.84  4976.6  369.22
  4995.2  364.66  4997.9  364.16  5001.2  364.66  5036.6  369.41  5042.0  367.76
  5119.8  367.32  5143.9  369.45  5181.5  367.75  5358.7  368.04  5466.1  376.70
  5490.2  382.18  5519.8  374.50  5543.9  377.74  5549.3  375.67  5568.0  381.88
  5573.4  377.55  5597.6  387.16  5645.1  388.68  5688.3  394.48  5737.2  397.27
  6152.7  393.96  6161.4  394.32  6351.6  398.59  6604.0  403.30  6681.2  402.88
#Mann=10,-1,0
  4767.0     0.1       0  4899.5    0.16       0  4995.2    0.07       0
  5001.2    0.16       0  5181.5    0.05       0  5737.2    0.16       0
  6152.7    0.05       0  6161.4     0.1       0  6351.6    0.05       0
  6604.0     0.1       0
Bank Sta=4995.2,5001.2
Exp/Cntr=0.3,0.1

Type RM Length L Ch R = 1,4641,0,0,0
BEGIN DESCRIPTION:
UNT0150 IN SAND CK 5.0
END DESCRIPTION:
XS GIS Cut Line= 2
      3538725.11     10524396.59      3536989.06     10523684.81
#Sta/Elev= 30
  4810.5  376.33  4857.0  377.33  4916.1  374.54  4988.5  365.92  4995.9  364.08
  4998.6  363.58  5001.9  364.08  5022.9  367.11  5188.1  366.28  5385.7  367.25
  5429.8  369.66  5473.9  373.98  5497.9  379.65  5516.3  375.67  5521.9  371.92
  5537.9  371.13  5545.9  371.97  5551.3  376.74  5575.3  379.27  5599.2  383.85
  5731.5  391.84  5812.8  394.07  5860.7  397.14  5937.8  398.69  6127.6  394.98
  6197.6  395.20  6378.5  399.22  6495.9  402.18  6608.9  402.72  6686.8  402.60
#Mann=9,-1,0
  4810.5    0.16       0  4988.5     0.1       0  4995.9    0.07       0
  5001.9     0.1       0  5188.1    0.05       0  5731.5    0.16       0
  6197.6     0.1       0  6378.5    0.05       0  6608.9     0.1       0
Bank Sta=4995.9,5001.9
Exp/Cntr=0.3,0.1

Chan Stop Cuts=-1