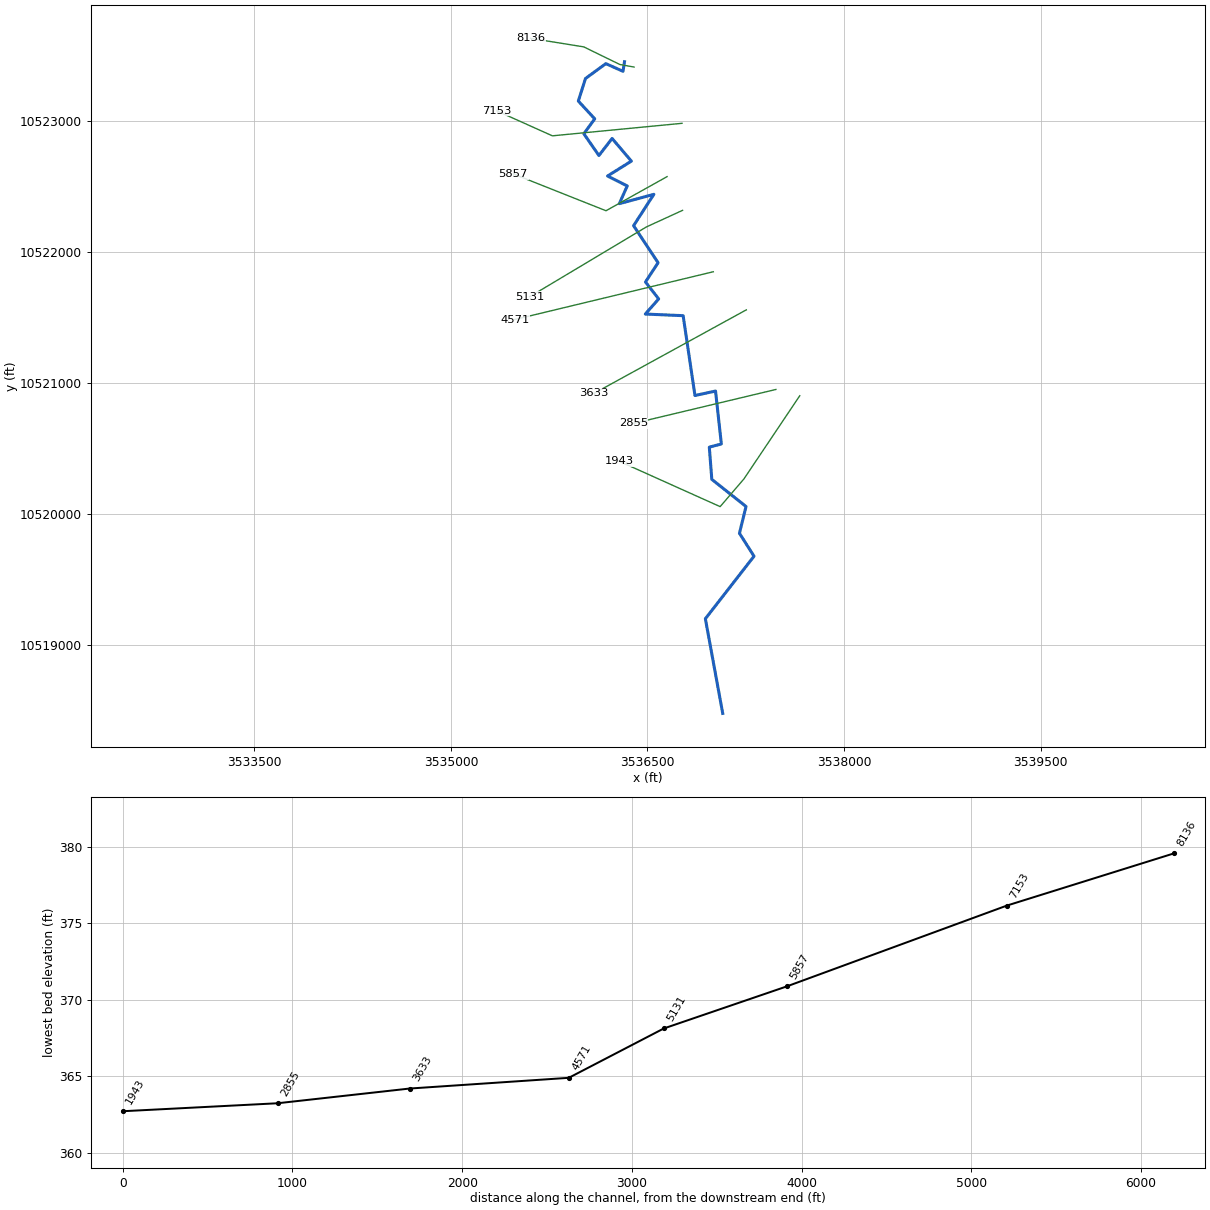
--- UNT0151 IN SAND CR.prj (project) ---

Proj Title=UNT0151 IN SAND CR Base Level Engineering
Current Plan=p01
Default Exp/Contr=0.3,0.1
English Units
Geom File=g01
Flow File=f01
Plan File=p01
BEGIN DESCRIPTION:
UNT0151 IN SAND CR
END DESCRIPTION:

--- UNT0151 IN SAND CR.p01 (plan) ---

Plan Title=Multiple Run
Short Identifier=Multiple
Geom File=g01
Flow File=f01
Subcritical Flow
K Sum by GR= 0
Std Step Tol= 0.01
Critical Tol= 0.01
Num of Std Step Trials= 20
Max Error Tol= 0.3
Flow Tol Ratio= 0.001
Split Flow NTrial= 30
Split Flow Tol= 0.02
Split Flow Ratio= 0.02
Log Output Level= 0
Friction Slope Method= 1
Unsteady Friction Slope Method= 2
Unsteady Bridges Friction Slope Method= 1
Parabolic Critical Depth
Global Vel Dist=  1 , 1 , 1
Global Log Level= 0
CheckData=True
Encroach Param= -1, 0, 0, 0
BEGIN DESCRIPTION:
Multiple Run
END DESCRIPTION:

--- UNT0151 IN SAND CR.f01 (steady flow) ---

Flow Title=Multiple
Number of Profiles=7
Profile Names=10-year,25-year,50-year,1pct_min,100-year,1pct_plu,500-year
River Rch & RM= UNT0151 IN SAND ,Reach-1,8136
     893    1211    1468    1298    1756    2375    2505
Boundary for River Rch & Prof#=UNT0151 IN SAND ,Reach-1,1
Up Type=0
Dn Type=3
Dn Slope=0.005
Boundary for River Rch & Prof#=UNT0151 IN SAND ,Reach-1,2
Up Type=0
Dn Type=3
Dn Slope=0.005
Boundary for River Rch & Prof#=UNT0151 IN SAND ,Reach-1,3
Up Type=0
Dn Type=3
Dn Slope=0.005
Boundary for River Rch & Prof#=UNT0151 IN SAND ,Reach-1,4
Up Type=0
Dn Type=3
Dn Slope=0.005
Boundary for River Rch & Prof#=UNT0151 IN SAND ,Reach-1,5
Up Type=0
Dn Type=3
Dn Slope=0.005
Boundary for River Rch & Prof#=UNT0151 IN SAND ,Reach-1,6
Up Type=0
Dn Type=3
Dn Slope=0.005
Boundary for River Rch & Prof#=UNT0151 IN SAND ,Reach-1,7
Up Type=0
Dn Type=3
Dn Slope=0.005

--- UNT0151 IN SAND CR.g01 (geometry) ---

Geom Title=Existing Conditions

River Reach=UNT0151 IN SAND ,Reach-1
Reach XY= 30
      3536325.08     10523452.69      3536313.53     10523379.32
      3536182.61     10523437.85      3536027.36     10523324.56
      3535972.59     10523152.25      3536097.90     10523016.48
      3536014.47     10522902.85      3536129.78     10522736.79
      3536230.34     10522866.89      3536377.45     10522694.06
      3536195.54     10522580.25      3536346.02     10522504.64
      3536285.34     10522369.25      3536548.93     10522440.59
      3536394.28     10522201.06      3536581.31     10521918.46
      3536484.96     10521771.64      3536585.87     10521642.41
      3536483.74     10521526.77      3536772.49     10521514.48
      3536862.77     10520905.11      3537019.71     10520939.14
      3537064.24     10520535.29      3536972.23     10520510.98
      3536991.33     10520265.32      3537252.61     10520057.86
      3537202.26     10519853.86      3537313.38     10519678.52
      3536942.11     10519201.67      3537074.57     10518479.27

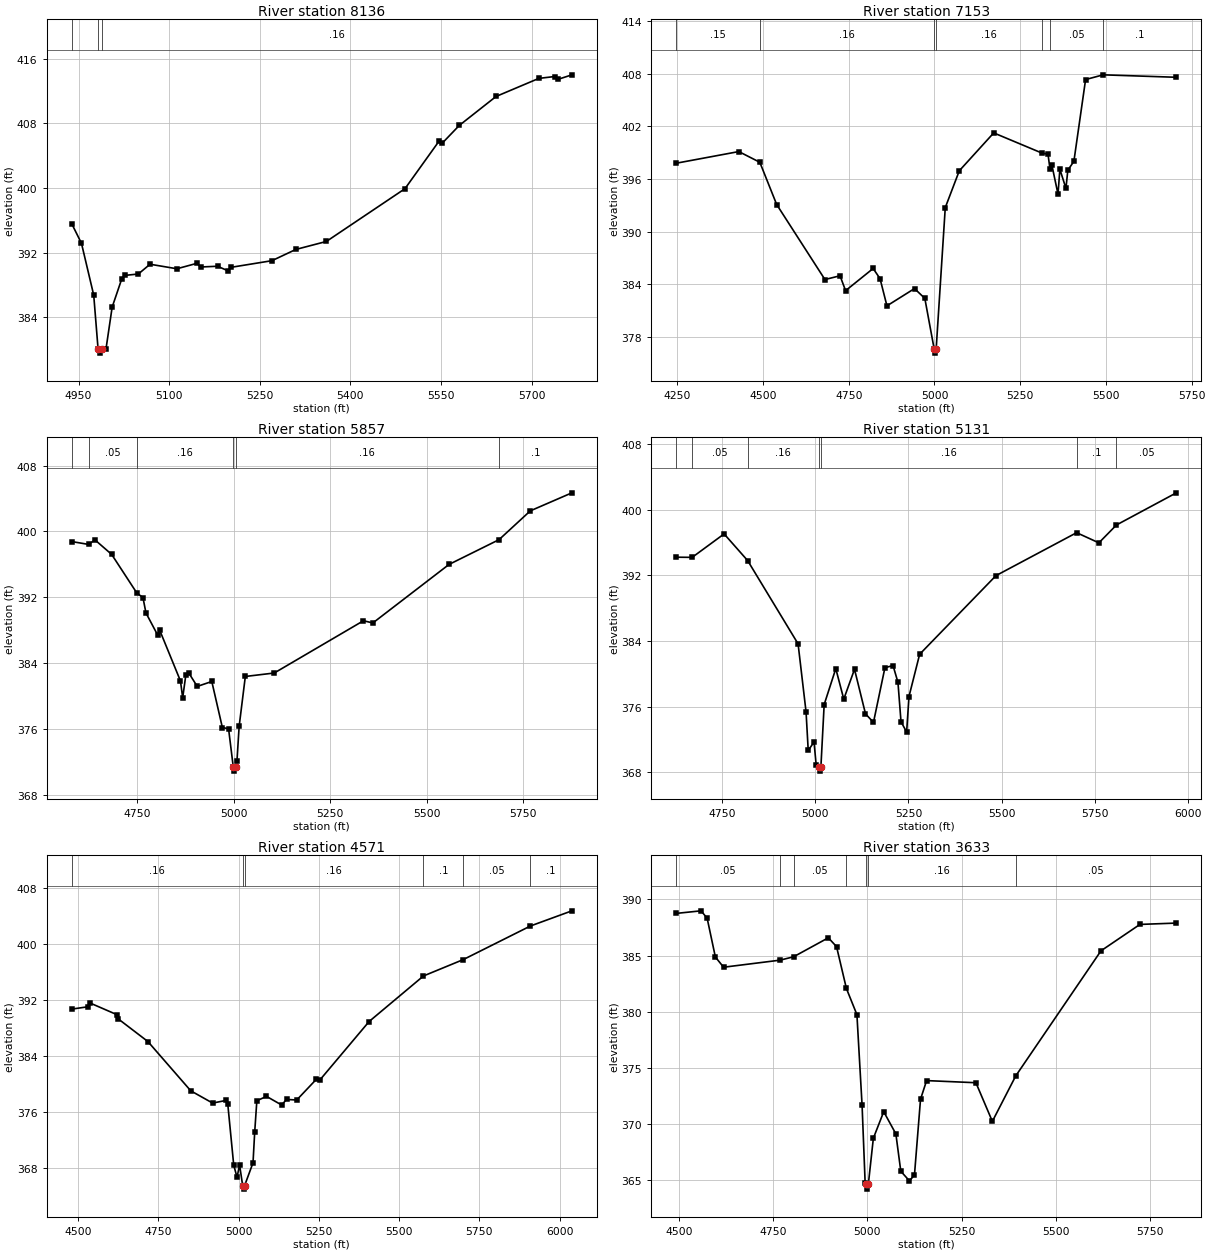
Type RM Length L Ch R = 1,8136,983,983,983
BEGIN DESCRIPTION:
UNT0151 IN SAND CR 12.0
END DESCRIPTION:
XS GIS Cut Line= 4
      3536398.06     10523411.83      3536289.53     10523431.36
      3536013.92     10523565.91      3535608.08     10523631.02
#Sta/Elev= 30
  4938.7  395.58  4954.9  393.14  4975.2  386.72  4982.4  380.05  4985.1  379.55
  4988.4  380.05  4995.5  380.06  5005.7  385.24  5021.6  388.74  5026.7  389.17
  5049.0  389.34  5068.4  390.55  5112.9  389.99  5146.3  390.67  5152.0  390.21
  5180.1  390.30  5197.1  389.75  5202.6  390.17  5270.2  390.99  5309.7  392.38
  5360.3  393.37  5490.4  399.90  5547.3  405.84  5552.3  405.55  5580.3  407.73
  5641.1  411.31  5712.0  413.55  5738.2  413.78  5743.2  413.42  5766.7  413.99
#Mann=3,-1,0
  4938.7    0.16       0  4982.4    0.07       0  4988.4    0.16       0
Bank Sta=4982.4,4988.4
Exp/Cntr=0.3,0.1

Type RM Length L Ch R = 1,7153,1296,1296,1296
BEGIN DESCRIPTION:
UNT0151 IN SAND CR 10.0
END DESCRIPTION:
XS GIS Cut Line= 3
      3536764.05     10522982.45      3535774.50     10522886.96
      3535350.61     10523077.28
#Sta/Elev= 30
  4246.6  397.80  4429.4  399.13  4490.7  397.91  4539.9  393.09  4680.6  384.54
  4724.6  384.97  4740.8  383.27  4821.2  385.80  4841.3  384.64  4861.4  381.54
  4941.8  383.51  4971.9  382.39  4999.0  376.65  5001.8  376.15  5005.0  376.65
  5031.5  392.74  5072.4  396.94  5172.8  401.26  5314.6  398.94  5331.1  398.84
  5336.7  397.18  5342.6  397.55  5360.3  394.27  5365.7  397.12  5383.4  394.93
  5388.9  397.00  5406.6  398.02  5440.7  407.34  5492.0  407.88  5705.4  407.60
#Mann=7,-1,0
  4246.6    0.15       0  4490.7    0.16       0  4999.0    0.07       0
  5005.0    0.16       0  5314.6     0.1       0  5336.7    0.05       0
  5492.0     0.1       0
Bank Sta=4999,5005
Exp/Cntr=0.3,0.1

Type RM Length L Ch R = 1,5857,726,726,726
BEGIN DESCRIPTION:
UNT0151 IN SAND CR 8.0
END DESCRIPTION:
XS GIS Cut Line= 3
      3536650.00     10522575.68      3536183.82     10522315.25
      3535476.34     10522596.16
#Sta/Elev= 30
  4580.7  398.77  4624.8  398.42  4640.8  398.98  4684.2  397.21  4749.4  392.52
  4765.3  391.96  4773.0  390.10  4803.0  387.44  4808.7  387.99  4862.4  381.83
  4868.1  379.78  4876.1  382.50  4884.1  382.79  4905.8  381.17  4943.5  381.77
  4970.9  376.17  4986.9  376.04  4999.1  371.38  5001.9  370.88  5005.1  371.38
  5008.6  372.07  5014.3  376.32  5030.3  382.38  5105.2  382.80  5336.2  389.15
  5360.5  388.88  5557.7  395.99  5687.2  399.00  5768.2  402.50  5875.9  404.69
#Mann=6,-1,0
  4580.7    0.16       0  4624.8    0.05       0  4749.4    0.16       0
  4999.1    0.07       0  5005.1    0.16       0  5687.2     0.1       0
Bank Sta=4999.1,5005.1
Exp/Cntr=0.3,0.1

Type RM Length L Ch R = 1,5131,560,560,560
BEGIN DESCRIPTION:
UNT0151 IN SAND CR 7.0
END DESCRIPTION:
XS GIS Cut Line= 3
      3536768.39     10522318.37      3536492.11     10522191.64
      3535600.88     10521658.66
#Sta/Elev= 30
  4626.6  394.22  4669.7  394.20  4755.4  397.06  4818.5  393.81  4953.9  383.65
  4975.3  375.35  4981.1  370.65  4996.7  371.68  5002.5  368.85  5009.1  368.63
  5011.9  368.13  5015.1  368.63  5023.9  376.25  5055.1  380.63  5076.5  376.91
  5105.3  380.55  5134.8  375.12  5156.2  374.07  5186.9  380.74  5208.7  381.01
  5221.9  378.96  5230.1  374.15  5245.2  372.90  5251.5  377.23  5280.1  382.38
  5484.9  391.97  5701.4  397.21  5761.1  395.97  5808.3  398.15  5969.0  402.07
#Mann=7,-1,0
  4626.6     0.1       0  4669.7    0.05       0  4818.5    0.16       0
  5009.1    0.07       0  5015.1    0.16       0  5701.4     0.1       0
  5808.3    0.05       0
Bank Sta=5009.1,5015.1
Exp/Cntr=0.3,0.1

Type RM Length L Ch R = 1,4571,938,938,938
BEGIN DESCRIPTION:
UNT0151 IN SAND CR 6.0
END DESCRIPTION:
XS GIS Cut Line= 2
      3537002.80     10521849.64      3535488.06     10521485.06
#Sta/Elev= 30
  4480.1  390.64  4531.4  390.98  4536.5  391.53  4620.4  389.86  4625.5  389.23
  4717.4  386.01  4851.1  378.96  4919.1  377.21  4961.0  377.59  4966.2  377.10
  4984.8  368.34  4995.1  366.60  5003.0  368.37  5012.7  365.41  5015.4  364.91
  5018.7  365.41  5044.9  368.68  5050.1  373.04  5056.8  377.54  5086.8  378.17
  5133.9  376.94  5149.4  377.73  5181.0  377.65  5241.9  380.60  5252.2  380.46
  5406.5  388.87  5575.8  395.38  5699.7  397.72  5908.8  402.52  6038.1  404.69
#Mann=6,-1,0
  4480.1    0.16       0  5012.7    0.07       0  5018.7    0.16       0
  5575.8     0.1       0  5699.7    0.05       0  5908.8     0.1       0
Bank Sta=5012.7,5018.7
Exp/Cntr=0.3,0.1

Type RM Length L Ch R = 1,3633,778,778,778
BEGIN DESCRIPTION:
UNT0151 IN SAND CR 4.0
END DESCRIPTION:
XS GIS Cut Line= 2
      3537254.54     10521558.84      3536091.33     10520920.81
#Sta/Elev= 30
  4492.6  388.75  4558.8  388.98  4574.9  388.32  4596.7  384.87  4618.5  383.96
  4768.4  384.59  4804.2  384.89  4896.3  386.58  4918.1  385.79  4944.2  382.07
  4972.1  379.74  4985.8  371.67  4993.9  364.78  4996.6  364.71  4999.3  364.21
  5002.6  364.71  5015.7  368.74  5043.2  371.10  5075.4  369.13  5088.5  365.80
  5111.3  364.95  5124.7  365.46  5140.8  372.21  5156.9  373.87  5287.7  373.68
  5331.3  370.24  5393.4  374.29  5619.4  385.42  5722.7  387.77  5819.3  387.89
#Mann=7,-1,0
  4492.6    0.05       0  4768.4     0.1       0  4804.2    0.05       0
  4944.2    0.16       0  4996.6    0.07       0  5002.6    0.16       0
  5393.4    0.05       0
Bank Sta=4996.6,5002.6
Exp/Cntr=0.3,0.1

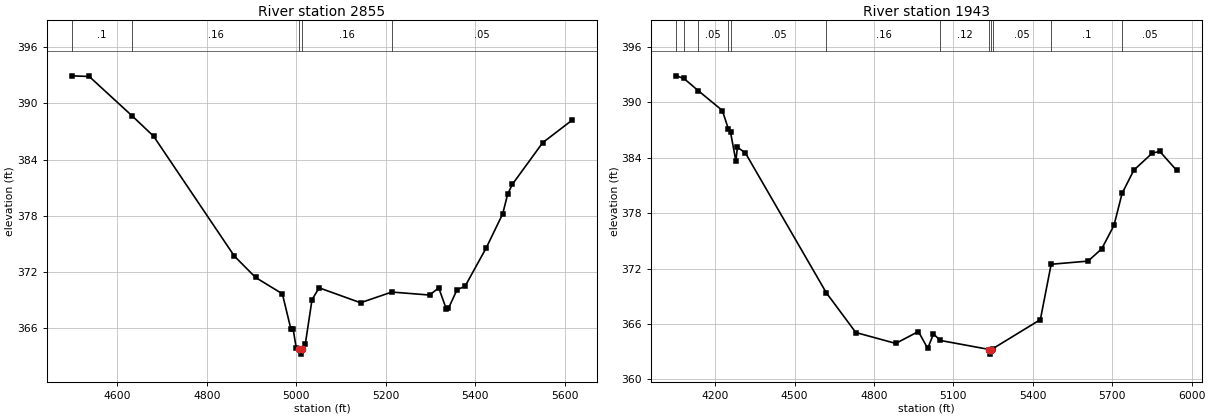
Type RM Length L Ch R = 1,2855,912,912,912
BEGIN DESCRIPTION:
UNT0151 IN SAND CR 3.0
END DESCRIPTION:
XS GIS Cut Line= 2
      3537480.21     10520951.20      3536392.14     10520691.65
#Sta/Elev= 30
  4497.6  392.93  4536.8  392.86  4633.1  388.64  4680.7  386.49  4861.3  373.70
  4908.6  371.43  4968.6  369.68  4987.6  365.92  4992.8  365.88  4999.4  363.95
  5006.7  363.75  5009.4  363.25  5012.7  363.75  5020.0  364.37  5034.9  369.07
  5050.8  370.32  5143.3  368.73  5213.3  369.87  5297.8  369.55  5318.1  370.32
  5334.8  368.09  5339.9  368.14  5359.2  370.13  5376.9  370.48  5424.2  374.57
  5461.1  378.21  5472.3  380.32  5482.6  381.35  5550.5  385.80  5616.2  388.20
#Mann=5,-1,0
  4497.6     0.1       0  4633.1    0.16       0  5006.7    0.07       0
  5012.7    0.16       0  5213.3    0.05       0
Bank Sta=5006.7,5012.7
Exp/Cntr=0.3,0.1

Type RM Length L Ch R = 1,1943,0,0,0
BEGIN DESCRIPTION:
UNT0151 IN SAND CR 1.0
END DESCRIPTION:
XS GIS Cut Line= 4
      3537662.52     10520903.45      3537236.28     10520268.23
      3537054.88     10520057.10      3536282.35     10520404.31
#Sta/Elev= 30
  4053.2  392.89  4081.7  392.61  4136.6  391.27  4227.2  389.13  4249.3  387.18
  4258.0  386.78  4278.2  383.69  4284.2  385.15  4314.2  384.53  4620.1  369.37
  4731.4  365.07  4882.2  363.89  4967.8  365.18  5002.9  363.35  5024.6  364.91
  5051.0  364.21  5236.2  363.23  5238.9  362.73  5242.2  363.23  5249.3  363.33
  5428.5  366.47  5469.3  372.47  5608.5  372.81  5660.3  374.14  5706.7  376.69
  5737.1  380.14  5781.6  382.67  5851.1  384.51  5879.7  384.70  5943.5  382.64
#Mann=12,-1,0
  4053.2    0.05       0  4081.7     0.1       0  4136.6    0.05       0
  4249.3     0.1       0  4258.0    0.05       0  4620.1    0.16       0
  5051.0    0.12       0  5236.2    0.07       0  5242.2    0.12       0
  5249.3    0.05       0  5469.3     0.1       0  5737.1    0.05       0
Bank Sta=5236.2,5242.2
Exp/Cntr=0.3,0.1

Chan Stop Cuts=-1