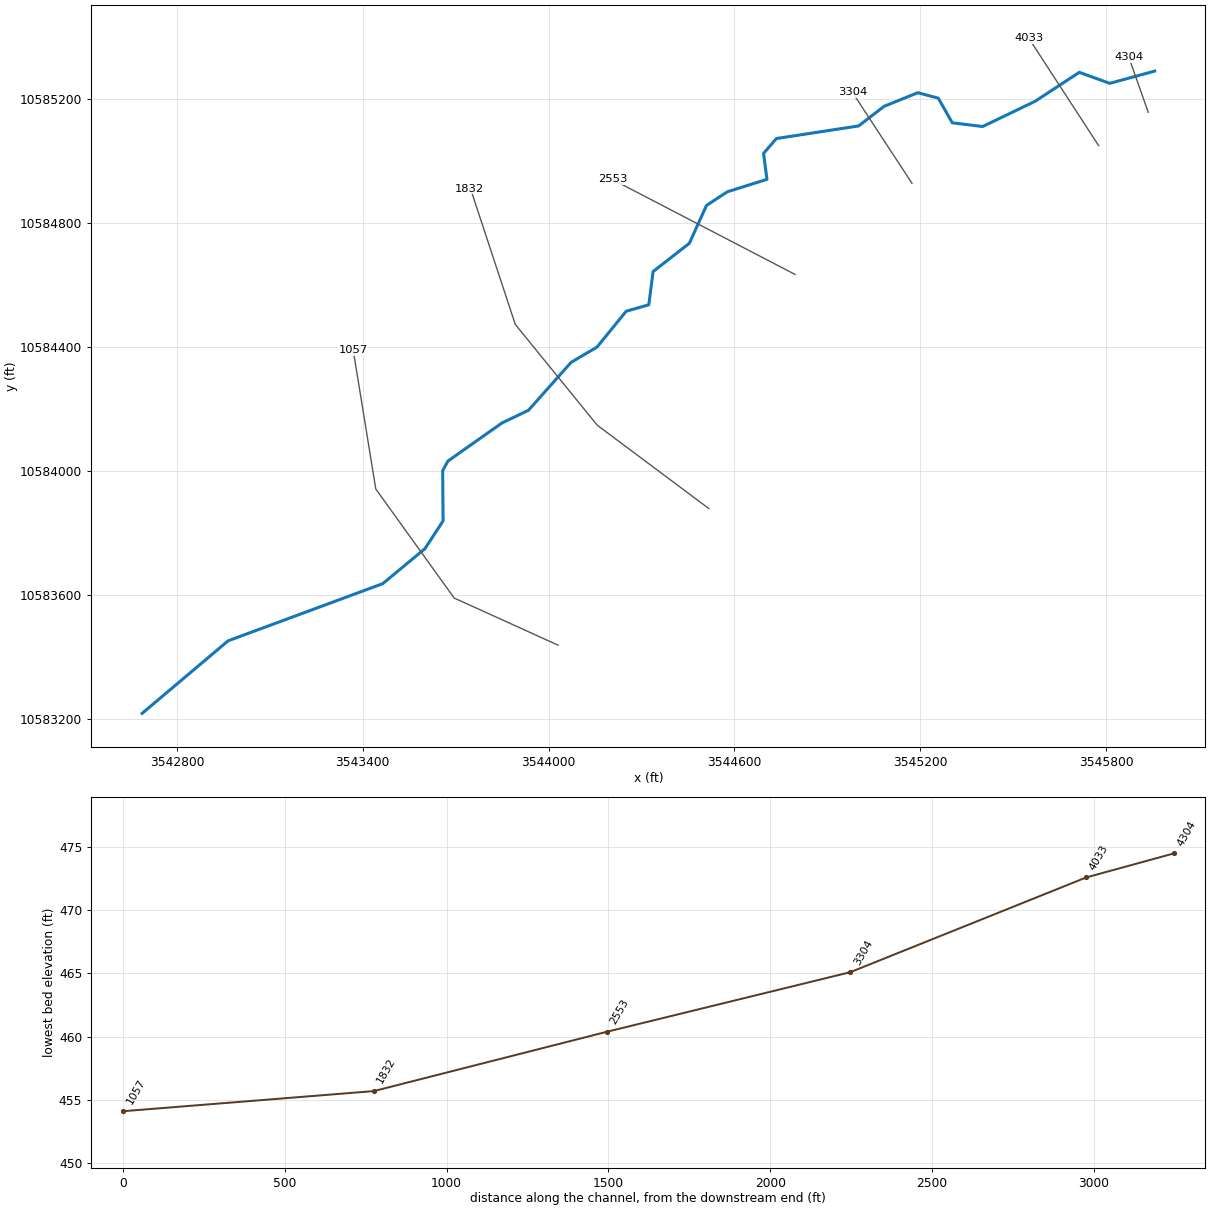
--- UNT01535 IN SAND CR.prj (project) ---

Proj Title=UNT01535 IN SAND CR Base Level Engineering
Current Plan=p01
Default Exp/Contr=0.3,0.1
English Units
Geom File=g01
Flow File=f01
Plan File=p01
BEGIN DESCRIPTION:
UNT01535 IN SAND CR
END DESCRIPTION:

--- UNT01535 IN SAND CR.p01 (plan) ---

Plan Title=Multiple Run
Short Identifier=Multiple
Geom File=g01
Flow File=f01
Subcritical Flow
K Sum by GR= 0
Std Step Tol= 0.01
Critical Tol= 0.01
Num of Std Step Trials= 20
Max Error Tol= 0.3
Flow Tol Ratio= 0.001
Split Flow NTrial= 30
Split Flow Tol= 0.02
Split Flow Ratio= 0.02
Log Output Level= 0
Friction Slope Method= 1
Unsteady Friction Slope Method= 2
Unsteady Bridges Friction Slope Method= 1
Parabolic Critical Depth
Global Vel Dist=  1 , 1 , 1
Global Log Level= 0
CheckData=True
Encroach Param= -1, 0, 0, 0
BEGIN DESCRIPTION:
Multiple Run
END DESCRIPTION:

--- UNT01535 IN SAND CR.f01 (steady flow) ---

Flow Title=Multiple
Number of Profiles=7
Profile Names=10-year,25-year,50-year,1pct_min,100-year,1pct_plu,500-year
River Rch & RM= UNT01535 IN SAND,Reach-1,4304
     467     610     722     626     846    1145    1156
Boundary for River Rch & Prof#=UNT01535 IN SAND,Reach-1,1
Up Type=0
Dn Type=3
Dn Slope=0.005
Boundary for River Rch & Prof#=UNT01535 IN SAND,Reach-1,2
Up Type=0
Dn Type=3
Dn Slope=0.005
Boundary for River Rch & Prof#=UNT01535 IN SAND,Reach-1,3
Up Type=0
Dn Type=3
Dn Slope=0.005
Boundary for River Rch & Prof#=UNT01535 IN SAND,Reach-1,4
Up Type=0
Dn Type=3
Dn Slope=0.005
Boundary for River Rch & Prof#=UNT01535 IN SAND,Reach-1,5
Up Type=0
Dn Type=3
Dn Slope=0.005
Boundary for River Rch & Prof#=UNT01535 IN SAND,Reach-1,6
Up Type=0
Dn Type=3
Dn Slope=0.005
Boundary for River Rch & Prof#=UNT01535 IN SAND,Reach-1,7
Up Type=0
Dn Type=3
Dn Slope=0.005

--- UNT01535 IN SAND CR.g01 (geometry) ---

Geom Title=Existing Conditions

River Reach=UNT01535 IN SAND,Reach-1
Reach XY= 30
      3545957.11     10585291.64      3545812.02     10585252.10
      3545713.58     10585287.64      3545571.11     10585194.24
      3545401.53     10585112.64      3545303.48     10585124.67
      3545258.32     10585204.19      3545192.38     10585221.92
      3545083.68     10585178.07      3545000.94     10585114.57
      3544735.65     10585073.89      3544694.05     10585025.85
      3544705.04     10584942.17      3544576.99     10584901.86
      3544509.73     10584857.72      3544454.49     10584735.59
      3544337.40     10584644.44      3544323.58     10584537.01
      3544250.60     10584516.30      3544156.27     10584400.42
      3544072.55     10584351.15      3543934.94     10584196.38
      3543849.86     10584155.68      3543674.90     10584032.46
      3543657.97     10584001.21      3543659.27     10583839.32
      3543600.68     10583749.47      3543464.39     10583636.55
      3542965.26     10583452.09      3542687.48     10583217.71

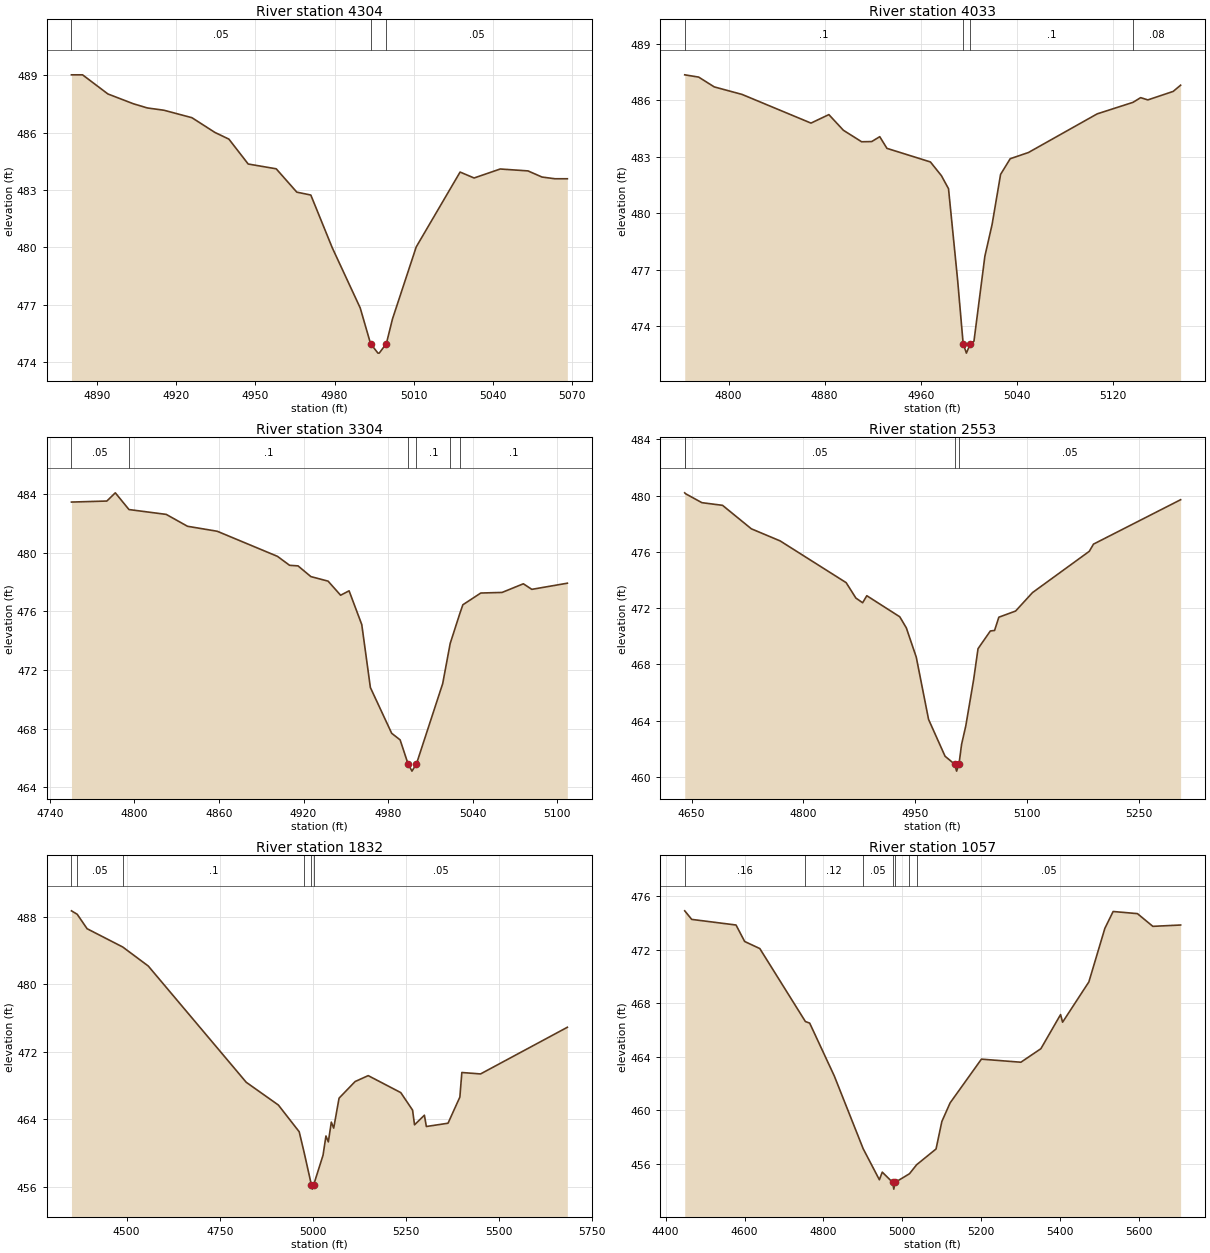
Type RM Length L Ch R = 1,4304,271,271,271
BEGIN DESCRIPTION:
UNT01535 IN SAND CR 8.1
END DESCRIPTION:
XS GIS Cut Line= 2
      3545936.32     10585158.59      3545873.85     10585335.59
#Sta/Elev= 28
  4880.4  489.02  4884.6  489.02  4894.2  488.02  4903.8  487.51  4909.1  487.29
  4915.4  487.17  4926.0  486.78  4934.7  486.01  4940.0  485.66  4947.3  484.36
  4957.9  484.11  4965.7  482.89  4971.0  482.74  4979.1  479.99  4989.7  476.84
  4993.6  474.98  4996.4  474.48  4996.9  474.48  4999.6  474.98  5001.9  476.26
  5010.9  480.03  5027.5  483.94  5032.8  483.63  5042.7  484.10  5053.2  484.00
  5058.5  483.68  5063.4  483.59  5068.1  483.59
#Mann=3,-1,0
  4880.4    0.05       0  4993.6    0.03       0  4999.6    0.05       0
Bank Sta=4993.6,4999.6
Exp/Cntr=0.3,0.1

Type RM Length L Ch R = 1,4033,729,729,729
BEGIN DESCRIPTION:
UNT01535 IN SAND CR 8.0
END DESCRIPTION:
XS GIS Cut Line= 2
      3545776.05     10585050.98      3545550.86     10585397.42
#Sta/Elev= 30
  4763.4  487.34  4775.0  487.22  4788.0  486.70  4811.2  486.30  4868.6  484.78
  4883.5  485.23  4895.6  484.40  4910.8  483.79  4919.2  483.80  4925.9  484.06
  4931.9  483.44  4968.1  482.72  4977.3  481.99  4983.2  481.30  4990.8  476.45
  4995.4  473.08  4998.1  472.58  5001.4  473.08  5004.4  473.21  5013.5  477.72
  5019.5  479.40  5026.6  482.06  5034.6  482.89  5049.8  483.22  5107.1  485.27
  5136.9  485.88  5143.3  486.13  5149.3  486.01  5170.4  486.46  5176.6  486.79
#Mann=4,-1,0
  4763.4     0.1       0  4995.4    0.07       0  5001.4     0.1       0
  5136.9    0.08       0
Bank Sta=4995.4,5001.4
Exp/Cntr=0.3,0.1

Type RM Length L Ch R = 1,3304,751,751,751
BEGIN DESCRIPTION:
UNT01535 IN SAND CR 6.0
END DESCRIPTION:
XS GIS Cut Line= 2
      3545173.30     10584929.41      3544980.62     10585223.63
#Sta/Elev= 30
  4755.4  483.44  4780.5  483.51  4786.5  484.07  4796.2  482.93  4822.6  482.60
  4837.7  481.79  4858.8  481.45  4901.5  479.74  4910.1  479.13  4916.1  479.09
  4925.2  478.36  4937.4  478.05  4946.3  477.09  4952.3  477.39  4961.3  475.09
  4967.4  470.80  4982.5  467.68  4988.5  467.23  4994.1  465.60  4996.9  465.10
  5000.1  465.60  5018.7  471.07  5024.0  473.80  5030.9  475.86  5033.0  476.44
  5045.7  477.24  5060.8  477.28  5075.9  477.87  5081.9  477.49  5107.1  477.91
#Mann=6,-1,0
  4755.4    0.05       0  4796.2     0.1       0  4994.1    0.07       0
  5000.1     0.1       0  5024.0    0.05       0  5030.9     0.1       0
Bank Sta=4994.1,5000.1
Exp/Cntr=0.3,0.1

Type RM Length L Ch R = 1,2553,721,721,721
BEGIN DESCRIPTION:
UNT01535 IN SAND CR 5.0
END DESCRIPTION:
XS GIS Cut Line= 2
      3544795.72     10584635.11      3544205.86     10584941.74
#Sta/Elev= 30
  4640.8  480.20  4641.8  480.14  4663.8  479.50  4691.5  479.31  4730.1  477.64
  4768.7  476.78  4857.2  473.81  4870.3  472.71  4879.3  472.38  4884.9  472.88
  4929.1  471.38  4937.9  470.59  4951.2  468.51  4967.7  464.08  4989.8  461.46
  5002.5  460.90  5005.3  460.40  5008.5  460.90  5011.9  462.29  5017.6  463.62
  5028.1  466.90  5034.0  469.11  5050.5  470.37  5056.2  470.41  5061.9  471.35
  5084.4  471.79  5107.0  473.10  5183.2  476.04  5188.8  476.55  5305.6  479.71
#Mann=4,-1,0
  4640.8    0.12       0  4641.8    0.05       0  5002.5    0.03       0
  5008.5    0.05       0
Bank Sta=5002.5,5008.5
Exp/Cntr=0.3,0.1

Type RM Length L Ch R = 1,1832,775,775,775
BEGIN DESCRIPTION:
UNT01535 IN SAND CR 3.0
END DESCRIPTION:
XS GIS Cut Line= 5
      3544517.40     10583879.06      3544157.15     10584148.16
      3543892.40     10584473.68      3543753.51     10584894.69
      3543744.82     10584912.06
#Sta/Elev= 30
  4351.8  488.69  4367.3  488.28  4393.8  486.57  4489.6  484.40  4558.1  482.15
  4821.3  468.37  4907.5  465.68  4963.5  462.51  4976.4  460.13  4996.3  456.21
  4999.0  455.71  5002.3  456.21  5027.5  459.72  5035.4  462.01  5041.8  461.31
  5049.8  463.65  5056.2  462.94  5070.6  466.49  5113.7  468.46  5148.9  469.16
  5236.3  467.15  5268.1  465.07  5273.3  463.33  5299.8  464.47  5305.1  463.13
  5363.3  463.52  5395.1  466.62  5400.4  469.53  5450.6  469.36  5683.8  474.89
#Mann=6,-1,0
  4351.8     0.1       0  4367.3    0.05       0  4489.6     0.1       0
  4976.4    0.05       0  4996.3    0.03       0  5002.3    0.05       0
Bank Sta=4996.3,5002.3
Exp/Cntr=0.3,0.1

Type RM Length L Ch R = 1,1057,0,0,0
BEGIN DESCRIPTION:
UNT01535 IN SAND CR 1.0
END DESCRIPTION:
XS GIS Cut Line= 4
      3544030.46     10583438.07      3543695.01     10583590.19
      3543441.98     10583942.28      3543368.97     10584391.17
#Sta/Elev= 30
  4448.4  474.91  4466.1  474.27  4578.4  473.85  4600.3  472.62  4638.7  472.09
  4754.2  466.64  4765.1  466.52  4827.5  462.57  4900.6  457.14  4941.7  454.82
  4949.0  455.39  4975.5  454.62  4978.2  454.12  4981.5  454.62  5018.0  455.27
  5036.0  455.94  5085.3  457.12  5100.0  459.17  5120.9  460.56  5200.3  463.83
  5300.3  463.60  5351.0  464.61  5400.9  467.16  5406.0  466.59  5472.6  469.60
  5513.1  473.60  5534.1  474.86  5595.7  474.70  5634.7  473.75  5705.1  473.85
#Mann=7,-1,0
  4448.4    0.16       0  4754.2    0.12       0  4900.6    0.05       0
  4975.5   0.033       0  4981.5    0.05       0  5018.0    0.16       0
  5036.0    0.05       0
Bank Sta=4975.5,4981.5
Exp/Cntr=0.3,0.1

Chan Stop Cuts=-1