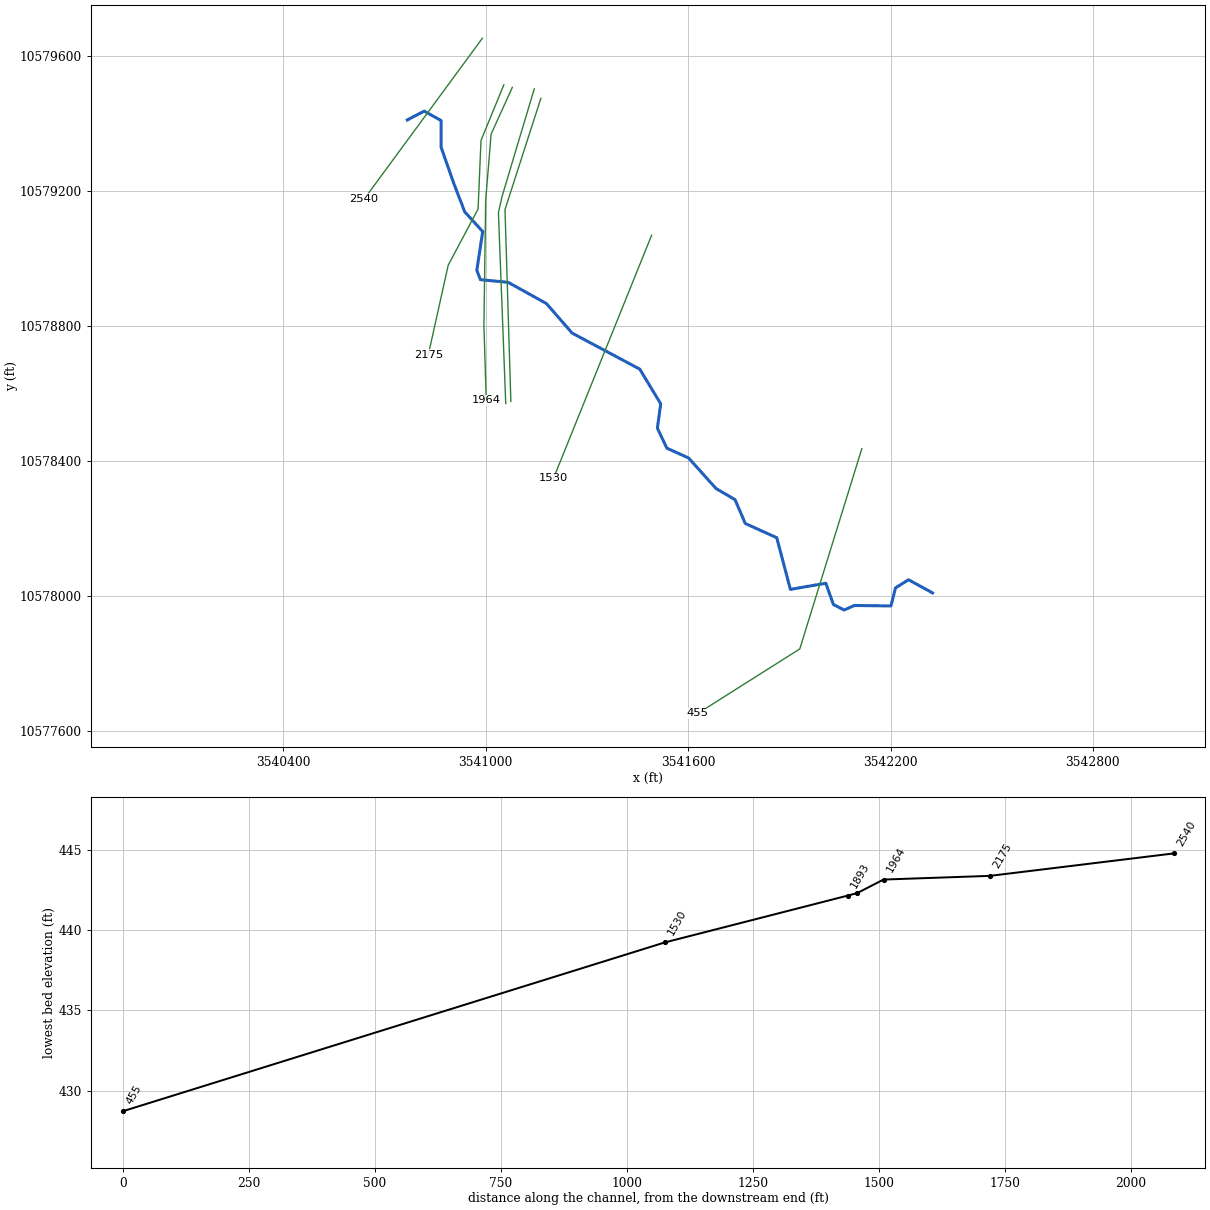
--- UNT01539 IN SAND CR.prj (project) ---

Proj Title=UNT01539 IN SAND CR Base Level Engineering
Current Plan=p01
Default Exp/Contr=0.3,0.1
English Units
Geom File=g01
Flow File=f01
Plan File=p01
BEGIN DESCRIPTION:
UNT01539 IN SAND CR
END DESCRIPTION:

--- UNT01539 IN SAND CR.p01 (plan) ---

Plan Title=Multiple Run
Short Identifier=Multiple
Geom File=g01
Flow File=f01
Subcritical Flow
K Sum by GR= 0
Std Step Tol= 0.01
Critical Tol= 0.01
Num of Std Step Trials= 20
Max Error Tol= 0.3
Flow Tol Ratio= 0.001
Split Flow NTrial= 30
Split Flow Tol= 0.02
Split Flow Ratio= 0.02
Log Output Level= 0
Friction Slope Method= 1
Unsteady Friction Slope Method= 2
Unsteady Bridges Friction Slope Method= 1
Parabolic Critical Depth
Global Vel Dist=  1 , 1 , 1
Global Log Level= 0
CheckData=True
Encroach Param= -1, 0, 0, 0
BEGIN DESCRIPTION:
Multiple Run
END DESCRIPTION:

--- UNT01539 IN SAND CR.f01 (steady flow) ---

Flow Title=Multiple
Number of Profiles=7
Profile Names=10-year,25-year,50-year,1pct_min,100-year,1pct_plu,500-year
River Rch & RM= UNT01539 IN SAND,Reach-1,2540
     445     581     688     597     807    1092    1104
Boundary for River Rch & Prof#=UNT01539 IN SAND,Reach-1,1
Up Type=0
Dn Type=3
Dn Slope=0.005
Boundary for River Rch & Prof#=UNT01539 IN SAND,Reach-1,2
Up Type=0
Dn Type=3
Dn Slope=0.005
Boundary for River Rch & Prof#=UNT01539 IN SAND,Reach-1,3
Up Type=0
Dn Type=3
Dn Slope=0.005
Boundary for River Rch & Prof#=UNT01539 IN SAND,Reach-1,4
Up Type=0
Dn Type=3
Dn Slope=0.005
Boundary for River Rch & Prof#=UNT01539 IN SAND,Reach-1,5
Up Type=0
Dn Type=3
Dn Slope=0.005
Boundary for River Rch & Prof#=UNT01539 IN SAND,Reach-1,6
Up Type=0
Dn Type=3
Dn Slope=0.005
Boundary for River Rch & Prof#=UNT01539 IN SAND,Reach-1,7
Up Type=0
Dn Type=3
Dn Slope=0.005

--- UNT01539 IN SAND CR.g01 (geometry) ---

Geom Title=Existing Conditions

River Reach=UNT01539 IN SAND,Reach-1
Reach XY= 30
      3540767.11     10579411.64      3540817.58     10579437.89
      3540867.76     10579409.79      3540867.36     10579331.43
      3540905.41     10579222.91      3540937.70     10579139.16
      3540990.91     10579080.78      3540973.40     10578966.00
      3540984.17     10578938.06      3541066.29     10578930.32
      3541179.80     10578867.39      3541255.98     10578779.74
      3541456.63     10578672.85      3541518.64     10578570.04
      3541508.79     10578497.85      3541536.81     10578438.60
      3541601.28     10578409.48      3541682.62     10578318.91
      3541739.04     10578285.93      3541769.42     10578215.18
      3541862.74     10578173.08      3541903.10     10578019.87
      3542008.14     10578038.10      3542030.71     10577975.16
      3542062.39     10577958.67      3542092.77     10577972.12
      3542201.28     10577970.82      3542214.74     10578024.21
      3542253.36     10578048.51      3542324.54     10578009.45

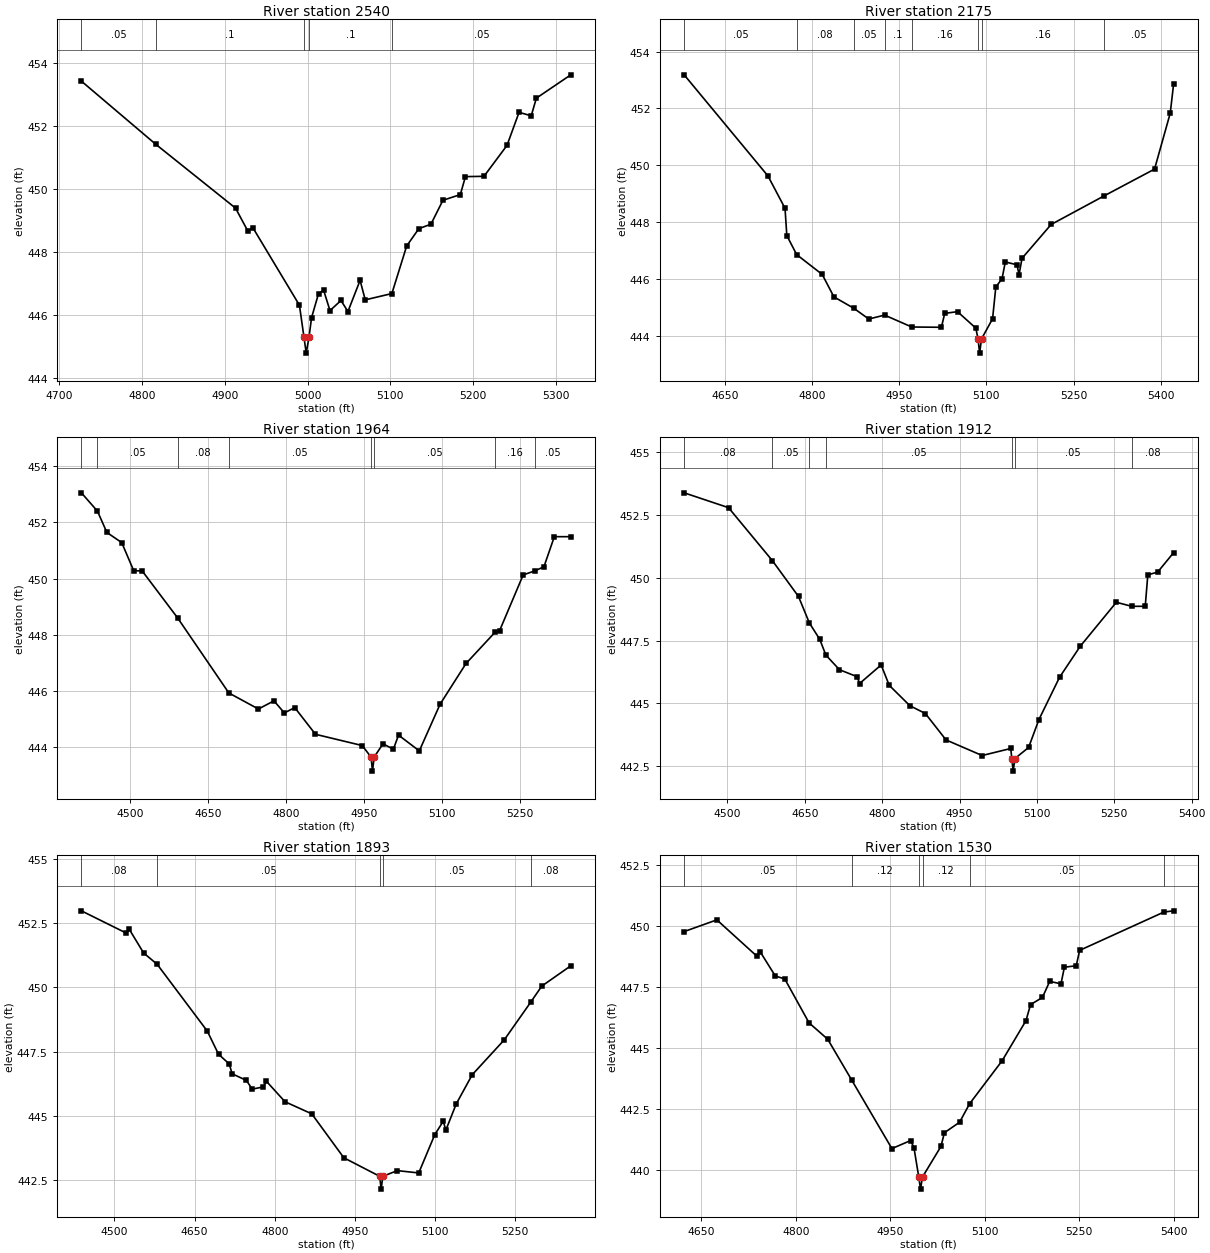
Type RM Length L Ch R = 1,2540,365,365,365
BEGIN DESCRIPTION:
UNT01539 IN SAND CR 4.4
END DESCRIPTION:
XS GIS Cut Line= 2
      3540989.73     10579653.67      3540639.49     10579177.13
#Sta/Elev= 30
  4726.6  453.41  4816.3  451.41  4912.9  449.38  4927.6  448.66  4933.8  448.76
  4990.1  446.30  4995.6  445.28  4998.3  444.78  5001.6  445.28  5004.8  445.91
  5013.2  446.67  5019.4  446.77  5027.0  446.13  5040.3  446.45  5048.7  446.10
  5063.4  447.09  5069.6  446.47  5101.8  446.67  5119.7  448.18  5134.4  448.73
  5149.0  448.87  5163.5  449.63  5184.5  449.81  5190.7  450.38  5213.1  450.39
  5240.9  451.37  5255.5  452.42  5270.2  452.31  5276.4  452.87  5318.0  453.61
#Mann=5,-1,0
  4726.6    0.05       0  4816.3     0.1       0  4995.6    0.07       0
  5001.6     0.1       0  5101.8    0.05       0
Bank Sta=4995.6,5001.6
Exp/Cntr=0.3,0.1

Type RM Length L Ch R = 1,2175,211,211,211
BEGIN DESCRIPTION:
UNT01539 IN SAND CR 4.3
END DESCRIPTION:
XS GIS Cut Line= 5
      3541053.54     10579515.76      3540985.82     10579350.80
      3540977.14     10579147.68      3540888.60     10578981.01
      3540829.71     10578716.03
#Sta/Elev= 30
  4580.1  453.18  4724.2  449.62  4753.6  448.48  4756.7  447.52  4773.6  446.85
  4817.6  446.15  4837.7  445.36  4871.9  444.96  4897.7  444.58  4924.8  444.72
  4971.6  444.30  5022.6  444.29  5028.3  444.78  5050.3  444.84  5081.8  444.26
  5085.6  443.88  5088.3  443.38  5091.6  443.88  5110.6  444.59  5116.2  445.71
  5126.9  446.00  5132.5  446.59  5152.7  446.49  5156.1  446.14  5161.3  446.72
  5211.3  447.91  5301.8  448.91  5389.2  449.86  5416.2  451.83  5421.9  452.84
#Mann=8,-1,0
  4580.1    0.05       0  4773.6    0.08       0  4871.9    0.05       0
  4924.8     0.1       0  4971.6    0.16       0  5085.6    0.07       0
  5091.6    0.16       0  5301.8    0.05       0
Bank Sta=5085.6,5091.6
Exp/Cntr=0.3,0.1

Type RM Length L Ch R = 1,1964,52,52,52
BEGIN DESCRIPTION:
UNT01539 IN SAND CR 4.2
END DESCRIPTION:
XS GIS Cut Line= 5
      3541078.72     10579508.39      3541015.77     10579369.47
      3540999.71     10579173.72      3540994.50     10578800.46
      3541001.44     10578579.99
#Sta/Elev= 30
  4405.8  453.05  4436.7  452.40  4454.9  451.64  4483.5  451.28  4506.6  450.28
  4523.0  450.27  4591.2  448.60  4689.9  445.93  4746.8  445.36  4776.8  445.65
  4796.8  445.22  4816.8  445.41  4856.8  444.46  4946.8  444.06  4963.8  443.65
  4966.6  443.15  4969.8  443.65  4986.8  444.12  5006.8  443.93  5016.8  444.43
  5056.8  443.87  5096.8  445.53  5146.8  446.98  5203.2  448.10  5211.3  448.14
  5256.9  450.13  5278.8  450.27  5296.9  450.42  5316.9  451.49  5348.6  451.49
#Mann=8,-1,0
  4405.8    0.08       0  4436.7    0.05       0  4591.2    0.08       0
  4689.9    0.05       0  4963.8    0.04       0  4969.8    0.05       0
  5203.2    0.16       0  5278.8    0.05       0
Bank Sta=4963.8,4969.8
Exp/Cntr=0.3,0.1

Type RM Length L Ch R = 1,1912,19,19,19
BEGIN DESCRIPTION:
UNT01539 IN SAND CR 4.1
END DESCRIPTION:
XS GIS Cut Line= 4
      3541143.80     10579504.00      3541048.32     10579185.00
      3541037.47     10579137.26      3541059.17     10578570.82
#Sta/Elev= 30
  4416.1  453.37  4502.1  452.78  4587.3  450.67  4637.8  449.25  4658.8  448.20
  4678.9  447.55  4690.9  446.92  4717.2  446.34  4751.8  446.06  4756.1  445.79
  4798.0  446.53  4813.7  445.72  4853.7  444.91  4883.7  444.60  4923.8  443.55
  4993.8  442.93  5049.3  443.21  5051.3  442.81  5054.0  442.31  5057.3  442.81
  5083.9  443.25  5103.9  444.36  5143.9  446.04  5183.9  447.27  5254.0  449.02
  5283.8  448.86  5310.0  448.86  5315.0  450.11  5334.1  450.22  5364.9  450.99
#Mann=7,-1,0
  4416.1    0.08       0  4587.3    0.05       0  4658.8    0.08       0
  4690.9    0.05       0  5051.3    0.04       0  5057.3    0.05       0
  5283.8    0.08       0
Bank Sta=5051.3,5057.3
Exp/Cntr=0.3,0.1

Type RM Length L Ch R = 1,1893,363,363,363
BEGIN DESCRIPTION:
UNT01539 IN SAND CR 4.0
END DESCRIPTION:
XS GIS Cut Line= 3
      3541163.33     10579475.77      3541057.00     10579145.94
      3541074.36     10578577.35
#Sta/Elev= 30
  4438.4  452.98  4522.7  452.11  4528.0  452.26  4554.8  451.34  4580.1  450.90
  4673.9  448.30  4694.9  447.40  4715.0  447.02  4720.3  446.64  4747.1  446.38
  4757.9  446.04  4779.0  446.13  4784.4  446.35  4819.3  445.55  4869.3  445.08
  4929.3  443.37  4996.3  442.65  4999.1  442.15  5002.3  442.65  5029.4  442.87
  5069.4  442.78  5099.4  444.27  5115.2  444.79  5120.2  444.45  5139.4  445.46
  5169.4  446.60  5229.4  447.96  5278.7  449.42  5299.5  450.05  5353.8  450.84
#Mann=5,-1,0
  4438.4    0.08       0  4580.1    0.05       0  4996.3    0.04       0
  5002.3    0.05       0  5278.7    0.08       0
Bank Sta=4996.3,5002.3
Exp/Cntr=0.3,0.1

Type RM Length L Ch R = 1,1530,1075,1075,1075
BEGIN DESCRIPTION:
UNT01539 IN SAND CR 2.0
END DESCRIPTION:
XS GIS Cut Line= 2
      3541491.67     10579069.76      3541200.89     10578349.33
#Sta/Elev= 30
  4622.9  449.78  4674.8  450.26  4738.0  448.78  4743.4  448.96  4767.6  447.96
  4782.6  447.84  4821.2  446.04  4850.8  445.37  4888.6  443.71  4952.7  440.89
  4982.3  441.22  4987.7  440.93  4995.3  439.73  4998.1  439.23  5001.3  439.73
  5030.6  440.98  5036.0  441.54  5060.1  441.97  5076.1  442.73  5127.7  444.49
  5165.5  446.13  5172.8  446.79  5191.6  447.08  5203.2  447.74  5221.1  447.64
  5226.5  448.32  5245.3  448.38  5250.7  449.01  5384.5  450.58  5399.8  450.63
#Mann=6,-1,0
  4622.9    0.05       0  4888.6    0.12       0  4995.3    0.07       0
  5001.3    0.12       0  5076.1    0.05       0  5384.5    0.08       0
Bank Sta=4995.3,5001.3
Exp/Cntr=0.3,0.1

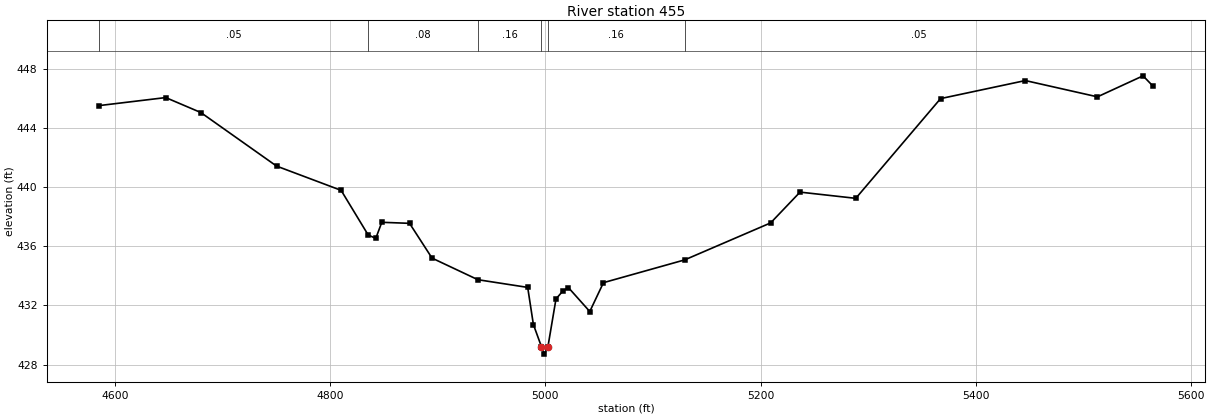
Type RM Length L Ch R = 1,455,0,0,0
BEGIN DESCRIPTION:
UNT01539 IN SAND CR 1.0
END DESCRIPTION:
XS GIS Cut Line= 3
      3542114.94     10578436.98      3541930.92     10577843.23
      3541628.83     10577652.26
#Sta/Elev= 30
  4585.5  445.51  4647.2  446.05  4679.8  445.04  4750.2  441.42  4810.2  439.78
  4835.3  436.77  4842.4  436.53  4848.0  437.62  4873.8  437.55  4894.7  435.20
  4937.3  433.74  4983.6  433.22  4988.9  430.71  4996.4  429.21  4999.1  428.71
  5002.4  429.21  5009.9  432.44  5016.2  432.97  5021.4  433.21  5041.3  431.59
  5054.0  433.54  5129.5  435.08  5209.4  437.58  5236.7  439.66  5288.5  439.24
  5367.3  445.98  5446.1  447.20  5513.1  446.10  5555.5  447.52  5564.5  446.84
#Mann=6,-1,0
  4585.5    0.05       0  4835.3    0.08       0  4937.3    0.16       0
  4996.4    0.07       0  5002.4    0.16       0  5129.5    0.05       0
Bank Sta=4996.4,5002.4
Exp/Cntr=0.3,0.1

Chan Stop Cuts=-1