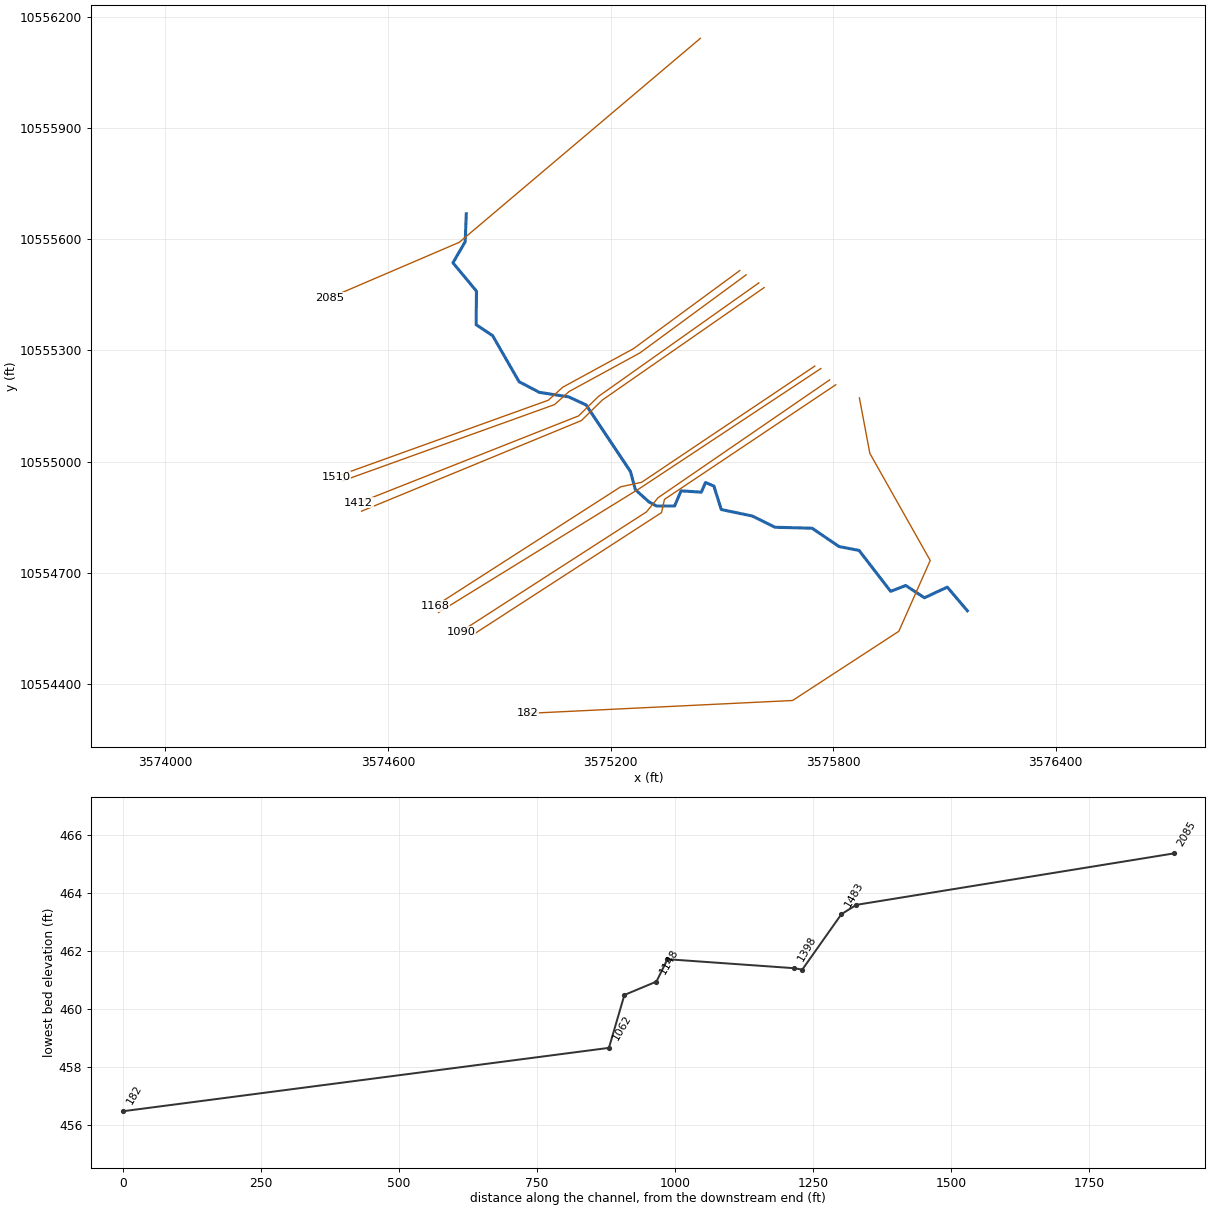
--- UNT0155 IN SAND CR.prj (project) ---

Proj Title=UNT0155 IN SAND CR Base Level Engineering
Current Plan=p01
Default Exp/Contr=0.3,0.1
English Units
Geom File=g01
Flow File=f01
Plan File=p01
BEGIN DESCRIPTION:
UNT0155 IN SAND CR
END DESCRIPTION:

--- UNT0155 IN SAND CR.p01 (plan) ---

Plan Title=Multiple Run
Short Identifier=Multiple
Geom File=g01
Flow File=f01
Subcritical Flow
K Sum by GR= 0
Std Step Tol= 0.01
Critical Tol= 0.01
Num of Std Step Trials= 20
Max Error Tol= 0.3
Flow Tol Ratio= 0.001
Split Flow NTrial= 30
Split Flow Tol= 0.02
Split Flow Ratio= 0.02
Log Output Level= 0
Friction Slope Method= 1
Unsteady Friction Slope Method= 2
Unsteady Bridges Friction Slope Method= 1
Parabolic Critical Depth
Global Vel Dist=  1 , 1 , 1
Global Log Level= 0
CheckData=True
Encroach Param= -1, 0, 0, 0
BEGIN DESCRIPTION:
Multiple Run
END DESCRIPTION:

--- UNT0155 IN SAND CR.f01 (steady flow) ---

Flow Title=Multiple
Number of Profiles=7
Profile Names=10-year,25-year,50-year,1pct_min,100-year,1pct_plu,500-year
River Rch & RM= UNT0155 IN SAND ,Reach-1,2085
     811    1089    1314    1156    1563    2114    2206
River Rch & RM= UNT0155 IN SAND ,Reach-1,1510
     864    1165    1408    1242    1679    2271    2380
Boundary for River Rch & Prof#=UNT0155 IN SAND ,Reach-1,1
Up Type=0
Dn Type=3
Dn Slope=0.005
Boundary for River Rch & Prof#=UNT0155 IN SAND ,Reach-1,2
Up Type=0
Dn Type=3
Dn Slope=0.005
Boundary for River Rch & Prof#=UNT0155 IN SAND ,Reach-1,3
Up Type=0
Dn Type=3
Dn Slope=0.005
Boundary for River Rch & Prof#=UNT0155 IN SAND ,Reach-1,4
Up Type=0
Dn Type=3
Dn Slope=0.005
Boundary for River Rch & Prof#=UNT0155 IN SAND ,Reach-1,5
Up Type=0
Dn Type=3
Dn Slope=0.005
Boundary for River Rch & Prof#=UNT0155 IN SAND ,Reach-1,6
Up Type=0
Dn Type=3
Dn Slope=0.005
Boundary for River Rch & Prof#=UNT0155 IN SAND ,Reach-1,7
Up Type=0
Dn Type=3
Dn Slope=0.005

--- UNT0155 IN SAND CR.g01 (geometry) ---

Geom Title=Existing Conditions

River Reach=UNT0155 IN SAND ,Reach-1
Reach XY= 30
      3574811.04     10555668.74      3574808.04     10555593.20
      3574775.00     10555536.41      3574838.45     10555460.06
      3574837.63     10555369.53      3574881.99     10555340.06
      3574953.41     10555215.75      3575008.09     10555187.10
      3575087.09     10555174.95      3575133.96     10555153.25
      3575253.75     10554973.56      3575266.78     10554924.95
      3575303.23     10554891.96      3575324.07     10554880.68
      3575372.68     10554880.68      3575390.04     10554921.48
      3575444.73     10554918.01      3575456.01     10554944.05
      3575478.58     10554934.50      3575498.55     10554871.13
      3575581.88     10554853.77      3575643.51     10554823.39
      3575743.34     10554820.78      3575816.25     10554771.30
      3575870.07     10554760.89      3575955.14     10554650.65
      3575995.94     10554666.27      3576046.29     10554633.28
      3576107.92     10554661.93      3576162.10     10554598.22

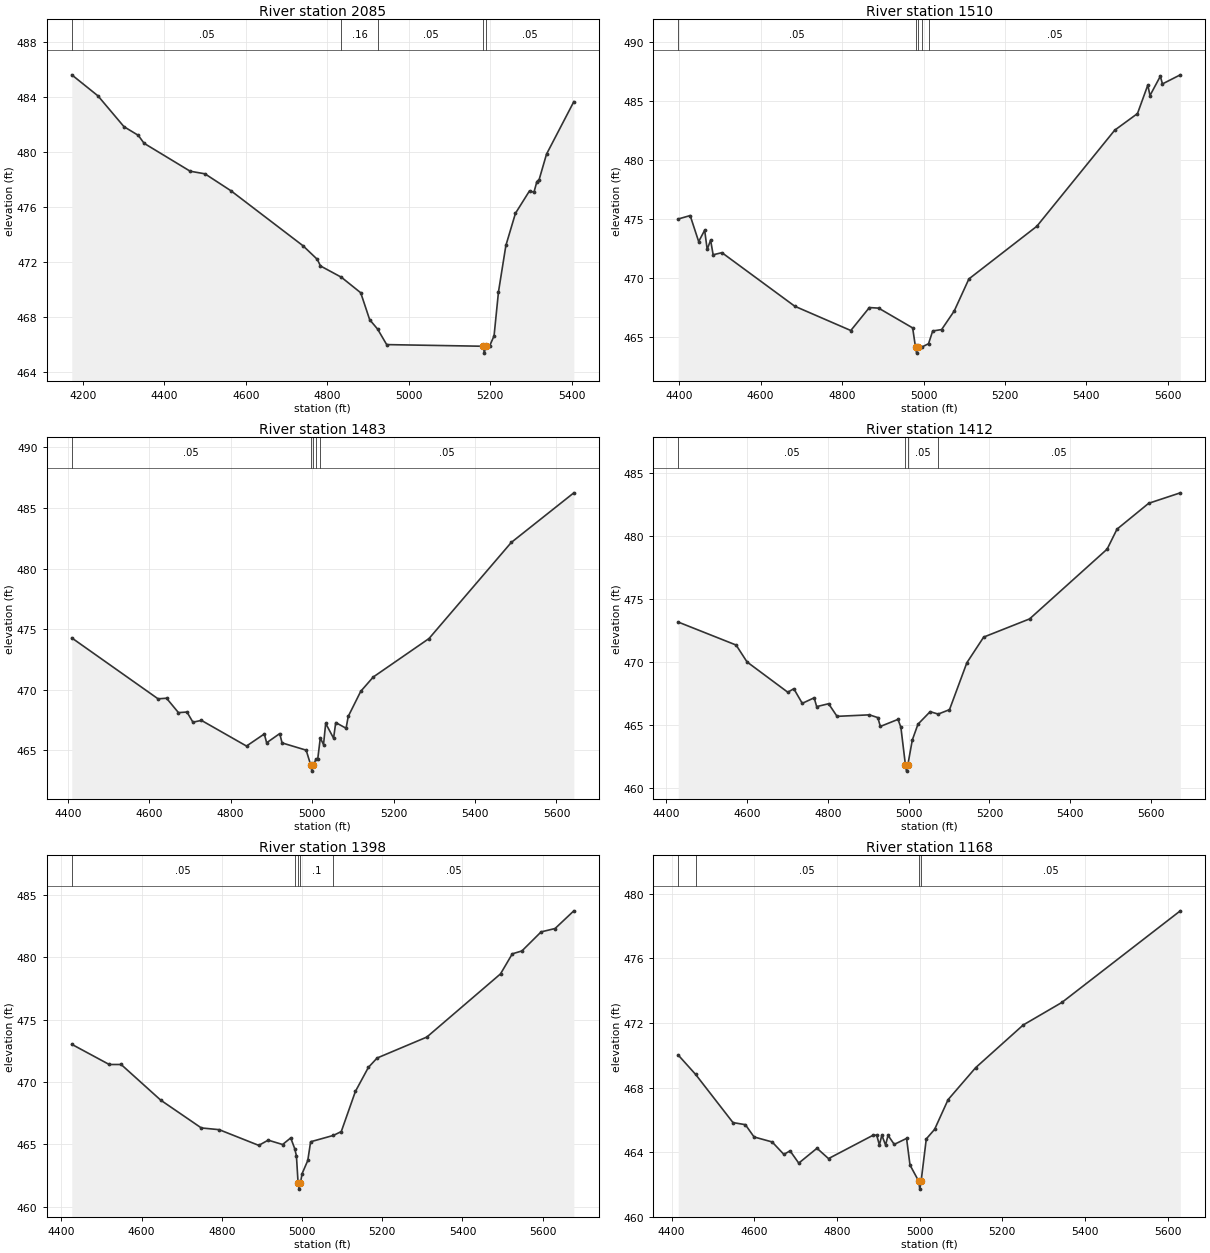
Type RM Length L Ch R = 1,2085,575,575,575
BEGIN DESCRIPTION:
UNT0155 IN SAND CR 4.0
END DESCRIPTION:
XS GIS Cut Line= 3
      3575442.14     10556141.67      3574792.11     10555591.64
      3574442.10     10555441.64
#Sta/Elev= 30
  4172.7  485.60  4237.0  484.07  4300.8  481.83  4335.9  481.20  4350.2  480.62
  4463.3  478.59  4499.6  478.40  4563.3  477.17  4740.2  473.17  4775.3  472.18
  4783.1  471.70  4834.4  470.88  4881.9  469.75  4903.9  467.79  4923.3  467.11
  4945.6  465.98  5182.6  465.86  5185.3  465.36  5188.6  465.86  5198.3  465.88
  5209.2  466.62  5220.0  469.81  5238.2  473.19  5261.7  475.53  5296.2  477.16
  5307.1  477.06  5314.3  477.84  5319.8  477.98  5337.9  479.83  5405.0  483.65
#Mann=5,-1,0
  4172.7    0.05       0  4834.4    0.16       0  4923.3    0.05       0
  5182.6   0.033       0  5188.6    0.05       0
Bank Sta=5182.6,5188.6
Exp/Cntr=0.3,0.1

Type RM Length L Ch R = 1,1510,27,27,27
BEGIN DESCRIPTION:
UNT0155 IN SAND CR 1.6
END DESCRIPTION:
XS GIS Cut Line= 5
      3575548.58     10555515.62      3575262.10     10555305.10
      3575071.23     10555201.04      3575032.17     10555165.88
      3574460.53     10554960.14
#Sta/Elev= 30
  4397.6  474.98  4426.9  475.27  4447.8  473.06  4462.5  474.03  4468.7  472.39
  4477.1  473.19  4483.3  471.94  4504.9  472.12  4683.9  467.57  4821.4  465.51
  4867.0  467.46  4889.8  467.41  4973.3  465.73  4980.3  464.09  4983.0  463.59
  4986.3  464.09  4996.7  464.12  5012.3  464.39  5022.5  465.47  5044.4  465.59
  5075.4  467.17  5111.4  469.89  5278.2  474.36  5469.5  482.52  5525.4  483.93
  5550.8  486.35  5556.1  485.46  5581.5  487.10  5586.8  486.45  5630.6  487.22
#Mann=5,-1,0
  4397.6    0.05       0  4980.3    0.07       0  4986.3    0.05       0
  4996.7     0.1       0  5012.3    0.05       0
Bank Sta=4980.3,4986.3
Exp/Cntr=0.3,0.1

Type RM Length L Ch R = 1,1483,71,71,71
BEGIN DESCRIPTION:
UNT0155 IN SAND CR 1.5
END DESCRIPTION:
XS GIS Cut Line= 5
      3575565.46     10555503.86      3575279.02     10555293.38
      3575088.16     10555189.32      3575049.10     10555154.16
      3574477.49     10554948.44
#Sta/Elev= 30
  4409.8  474.27  4621.7  469.24  4642.5  469.29  4671.8  468.10  4692.7  468.15
  4707.3  467.31  4728.2  467.46  4838.9  465.34  4882.6  466.34  4888.3  465.61
  4920.5  466.37  4926.2  465.60  4985.4  465.00  4996.6  463.77  4999.3  463.27
  5002.6  463.77  5009.7  464.26  5013.8  464.27  5020.1  466.01  5028.0  465.46
  5033.3  467.21  5052.7  465.99  5058.0  467.28  5083.4  466.81  5088.7  467.79
  5119.4  469.86  5150.1  471.04  5287.1  474.22  5489.0  482.15  5642.7  486.25
#Mann=5,-1,0
  4409.8    0.05       0  4996.6    0.03       0  5002.6    0.05       0
  5009.7     0.1       0  5020.1    0.05       0
Bank Sta=4996.6,5002.6
Exp/Cntr=0.3,0.1

Type RM Length L Ch R = 1,1412,14,14,14
BEGIN DESCRIPTION:
UNT0155 IN SAND CR 1.7
END DESCRIPTION:
XS GIS Cut Line= 4
      3575599.90     10555482.30      3575167.59     10555176.30
      3575113.77     10555123.61      3574520.89     10554889.23
#Sta/Elev= 30
  4429.8  473.17  4573.0  471.35  4600.1  470.01  4701.0  467.61  4715.8  467.89
  4736.7  466.73  4766.2  467.17  4772.4  466.47  4801.9  466.70  4822.8  465.70
  4902.9  465.82  4923.8  465.60  4929.9  464.90  4973.7  465.46  4980.8  464.83
  4992.0  461.86  4994.7  461.36  4998.0  461.86  5009.1  463.83  5023.1  465.08
  5053.2  466.07  5073.1  465.88  5101.1  466.23  5144.1  469.95  5185.7  471.98
  5299.3  473.42  5491.2  478.95  5515.6  480.53  5594.0  482.58  5672.3  483.41
#Mann=4,-1,0
  4429.8    0.05       0  4992.0    0.07       0  4998.0    0.05       0
  5073.1    0.05       0
Bank Sta=4992,4998
Exp/Cntr=0.3,0.1

Type RM Length L Ch R = 1,1398,230,230,230
BEGIN DESCRIPTION:
UNT0155 IN SAND CR 1.8
END DESCRIPTION:
XS GIS Cut Line= 4
      3575614.17     10555469.63      3575177.57     10555166.27
      3575121.58     10555111.15      3574528.68     10554866.78
#Sta/Elev= 30
  4426.1  473.03  4519.5  471.41  4549.2  471.41  4647.8  468.55  4749.0  466.32
  4793.6  466.18  4892.2  464.92  4915.7  465.34  4951.6  464.99  4971.9  465.52
  4981.9  464.65  4986.1  464.08  4990.2  461.91  4993.0  461.41  4996.2  461.91
  5000.2  462.65  5014.4  463.71  5021.5  465.21  5078.2  465.72  5097.9  466.03
  5133.1  469.25  5165.5  471.18  5187.2  471.93  5311.1  473.61  5494.8  478.68
  5524.2  480.29  5548.1  480.52  5596.0  482.05  5630.8  482.32  5677.6  483.74
#Mann=5,-1,0
  4426.1    0.05       0  4981.9     0.1       0  4990.2    0.07       0
  4996.2     0.1       0  5078.2    0.05       0
Bank Sta=4990.2,4996.2
Exp/Cntr=0.3,0.1

Type RM Length L Ch R = 1,1168,20,20,20
BEGIN DESCRIPTION:
UNT0155 IN SAND CR 1.1
END DESCRIPTION:
XS GIS Cut Line= 4
      3575750.75     10555257.97      3575283.73     10554944.59
      3575227.30     10554932.44      3574727.31     10554611.26
#Sta/Elev= 30
  4416.1  470.02  4457.9  468.83  4548.5  465.84  4578.5  465.71  4599.5  464.95
  4643.3  464.64  4671.6  463.87  4686.6  464.09  4707.6  463.33  4751.7  464.25
  4779.6  463.61  4887.6  465.06  4896.2  465.06  4902.6  464.45  4908.6  465.06
  4917.6  464.45  4923.6  465.05  4938.6  464.49  4968.4  464.86  4976.7  463.21
  4997.6  462.22  5000.4  461.72  5003.6  462.22  5016.1  464.83  5036.2  465.42
  5068.8  467.26  5135.5  469.24  5250.4  471.88  5344.2  473.28  5630.5  478.95
#Mann=4,-1,0
  4416.1    0.08       0  4457.9    0.05       0  4997.6    0.03       0
  5003.6    0.05       0
Bank Sta=4997.6,5003.6
Exp/Cntr=0.3,0.1

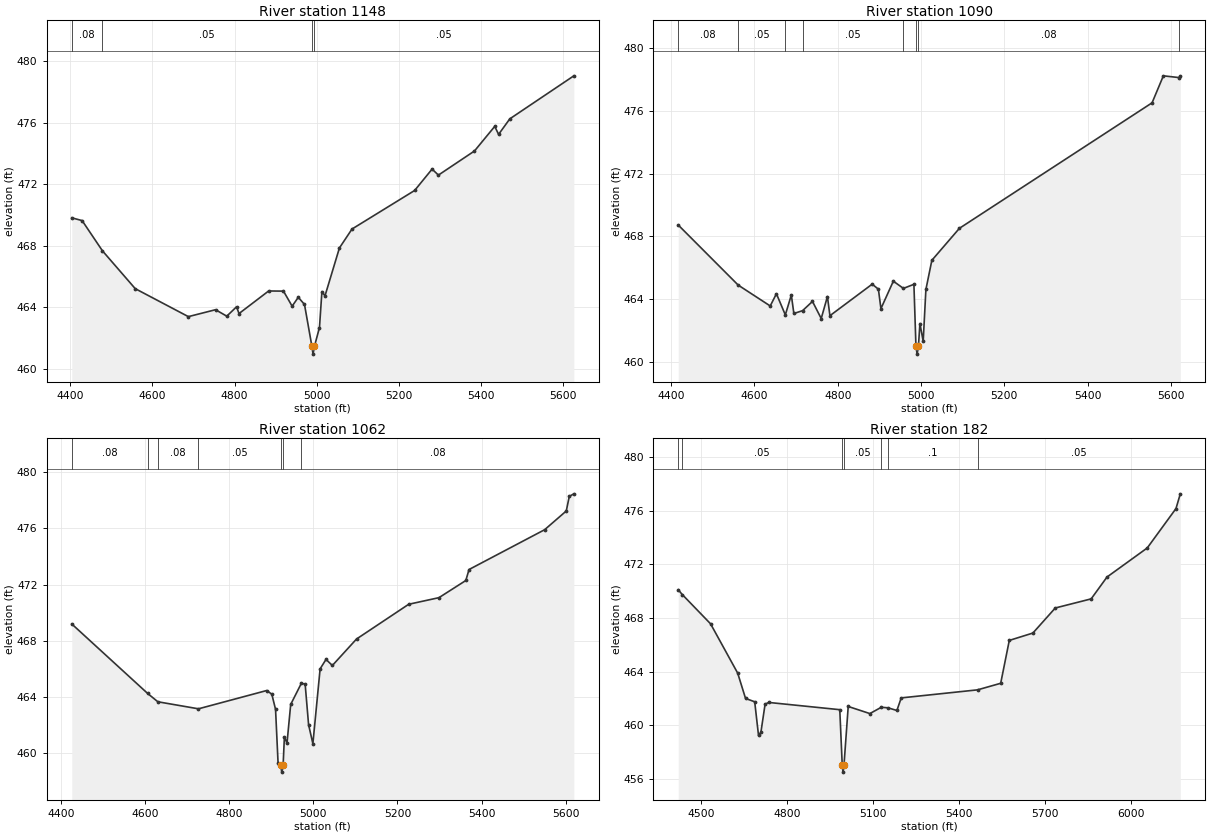
Type RM Length L Ch R = 1,1148,58,58,58
BEGIN DESCRIPTION:
UNT0155 IN SAND CR 1.0
END DESCRIPTION:
XS GIS Cut Line= 3
      3575767.04     10555251.32      3575278.52     10554928.10
      3574736.11     10554593.64
#Sta/Elev= 30
  4403.6  469.82  4428.8  469.64  4478.4  467.67  4558.2  465.21  4687.6  463.39
  4753.8  463.84  4781.2  463.42  4805.0  464.03  4811.0  463.59  4883.2  465.06
  4919.3  465.05  4940.4  464.07  4955.4  464.65  4970.5  464.18  4988.6  461.45
  4991.3  460.95  4994.6  461.45  5007.0  462.68  5012.9  465.02  5020.4  464.74
  5055.6  467.86  5086.2  469.09  5238.8  471.60  5281.3  472.99  5296.7  472.60
  5384.6  474.17  5433.9  475.77  5443.3  475.25  5470.6  476.26  5626.6  479.06
#Mann=4,-1,0
  4403.6    0.08       0  4478.4    0.05       0  4988.6    0.03       0
  4994.6    0.05       0
Bank Sta=4988.6,4994.6
Exp/Cntr=0.3,0.1

Type RM Length L Ch R = 1,1090,28,28,28
BEGIN DESCRIPTION:
UNT0155 IN SAND CR 1.2
END DESCRIPTION:
XS GIS Cut Line= 4
      3575790.69     10555220.65      3575328.00     10554902.93
      3575296.75     10554864.73      3574796.52     10554542.23
#Sta/Elev= 30
  4416.9  468.72  4560.9  464.89  4637.8  463.56  4652.7  464.34  4674.1  462.99
  4688.5  464.26  4694.6  463.08  4715.5  463.26  4739.3  463.85  4760.3  462.76
  4775.2  464.16  4781.2  462.94  4882.7  464.95  4897.6  464.63  4903.7  463.39
  4933.5  465.14  4957.7  464.68  4982.9  464.94  4987.8  460.99  4990.6  460.49
  4993.8  460.99  4997.3  462.44  5005.2  461.31  5011.7  464.61  5026.0  466.47
  5092.2  468.51  5554.9  476.51  5582.0  478.23  5619.1  478.12  5622.7  478.21
#Mann=8,-1,0
  4416.9    0.08       0  4560.9    0.05       0  4674.1    0.08       0
  4715.5    0.05       0  4957.7    0.08       0  4987.8    0.07       0
  4993.8    0.08       0  5619.1    0.05       0
Bank Sta=4987.8,4993.8
Exp/Cntr=0.3,0.1

Type RM Length L Ch R = 1,1062,880,880,880
BEGIN DESCRIPTION:
UNT0155 IN SAND CR 1.3
END DESCRIPTION:
XS GIS Cut Line= 4
      3575807.17     10555207.62      3575345.36     10554898.58
      3575337.55     10554862.99      3574833.05     10554536.20
#Sta/Elev= 30
  4426.0  469.20  4606.4  464.26  4630.6  463.67  4727.1  463.17  4889.3  464.47
  4901.4  464.21  4910.3  463.13  4916.3  459.31  4922.3  459.17  4925.1  458.67
  4928.3  459.17  4931.3  461.17  4937.5  460.73  4946.3  463.48  4971.4  464.97
  4980.6  464.94  4988.8  462.04  4999.0  460.69  5016.2  466.01  5030.2  466.68
  5045.3  466.25  5102.7  468.13  5226.7  470.60  5298.6  471.07  5362.5  472.29
  5370.1  473.07  5549.8  475.90  5601.2  477.23  5608.4  478.27  5619.2  478.45
#Mann=7,-1,0
  4426.0    0.08       0  4606.4    0.05       0  4630.6    0.08       0
  4727.1    0.05       0  4922.3    0.07       0  4928.3    0.05       0
  4971.4    0.08       0
Bank Sta=4922.3,4928.3
Exp/Cntr=0.3,0.1

Type RM Length L Ch R = 1,182,0,0,0
BEGIN DESCRIPTION:
UNT0155 IN SAND CR 1.4
END DESCRIPTION:
XS GIS Cut Line= 6
      3575870.96     10555172.26      3575899.18     10555022.50
      3576061.94     10554733.87      3575977.30     10554542.90
      3575690.84     10554356.27      3574977.01     10554321.55
#Sta/Elev= 30
  4421.4  470.10  4435.6  469.74  4534.0  467.56  4628.5  463.88  4655.9  461.99
  4687.8  461.74  4701.1  459.23  4709.4  459.46  4724.0  461.56  4736.8  461.69
  4984.2  461.15  4992.8  456.99  4995.6  456.49  4998.8  456.99  5013.6  461.39
  5089.0  460.86  5128.9  461.33  5152.3  461.29  5183.2  461.09  5198.3  462.03
  5464.1  462.63  5544.8  463.12  5574.8  466.32  5657.0  466.87  5735.0  468.74
  5860.0  469.42  5915.2  471.05  6055.4  473.22  6155.5  476.16  6170.6  477.26
#Mann=7,-1,0
  4421.4    0.08       0  4435.6    0.05       0  4992.8    0.03       0
  4998.8    0.05       0  5128.9    0.08       0  5152.3     0.1       0
  5464.1    0.05       0
Bank Sta=4992.8,4998.8
Exp/Cntr=0.3,0.1

Chan Stop Cuts=-1