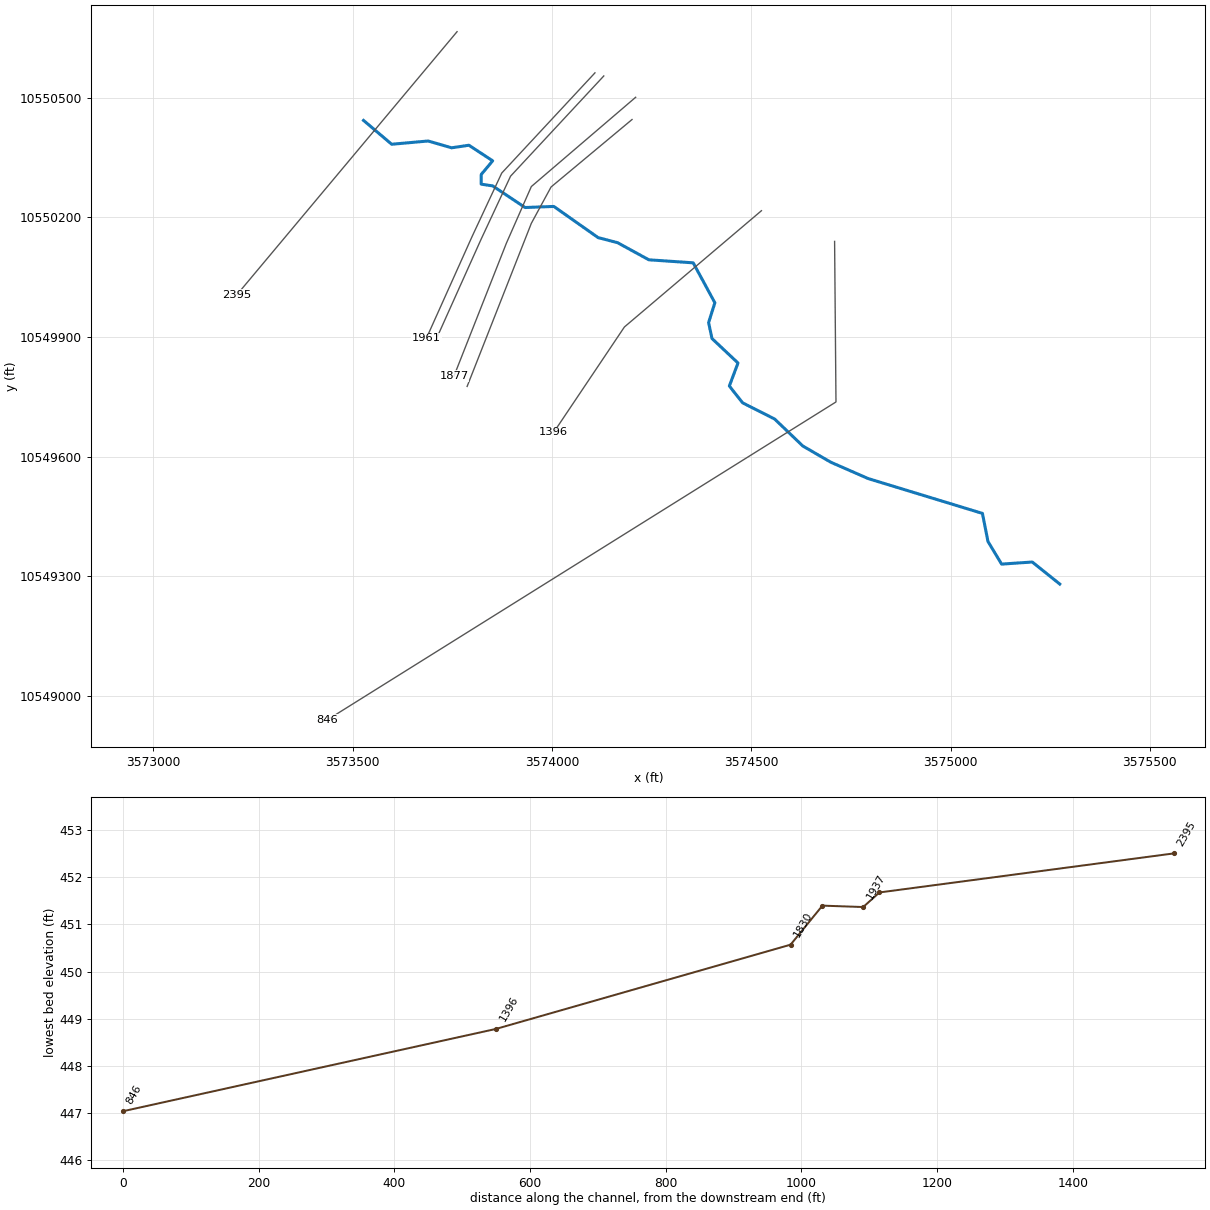
--- UNT0156 IN SAND CR.prj (project) ---

Proj Title=UNT0156 IN SAND CR Base Level Engineering
Current Plan=p01
Default Exp/Contr=0.3,0.1
English Units
Geom File=g01
Flow File=f01
Plan File=p01
BEGIN DESCRIPTION:
UNT0156 IN SAND CR
END DESCRIPTION:

--- UNT0156 IN SAND CR.p01 (plan) ---

Plan Title=Multiple Run
Short Identifier=Multiple
Geom File=g01
Flow File=f01
Subcritical Flow
K Sum by GR= 0
Std Step Tol= 0.01
Critical Tol= 0.01
Num of Std Step Trials= 20
Max Error Tol= 0.3
Flow Tol Ratio= 0.001
Split Flow NTrial= 30
Split Flow Tol= 0.02
Split Flow Ratio= 0.02
Log Output Level= 0
Friction Slope Method= 1
Unsteady Friction Slope Method= 2
Unsteady Bridges Friction Slope Method= 1
Parabolic Critical Depth
Global Vel Dist=  1 , 1 , 1
Global Log Level= 0
CheckData=True
Encroach Param= -1, 0, 0, 0
BEGIN DESCRIPTION:
Multiple Run
END DESCRIPTION:

--- UNT0156 IN SAND CR.f01 (steady flow) ---

Flow Title=Multiple
Number of Profiles=7
Profile Names=10-year,25-year,50-year,1pct_min,100-year,1pct_plu,500-year
River Rch & RM= UNT0156 IN SAND ,Reach-1,2395
     826    1112    1342    1181    1598    2161    2258
Boundary for River Rch & Prof#=UNT0156 IN SAND ,Reach-1,1
Up Type=0
Dn Type=3
Dn Slope=0.005
Boundary for River Rch & Prof#=UNT0156 IN SAND ,Reach-1,2
Up Type=0
Dn Type=3
Dn Slope=0.005
Boundary for River Rch & Prof#=UNT0156 IN SAND ,Reach-1,3
Up Type=0
Dn Type=3
Dn Slope=0.005
Boundary for River Rch & Prof#=UNT0156 IN SAND ,Reach-1,4
Up Type=0
Dn Type=3
Dn Slope=0.005
Boundary for River Rch & Prof#=UNT0156 IN SAND ,Reach-1,5
Up Type=0
Dn Type=3
Dn Slope=0.005
Boundary for River Rch & Prof#=UNT0156 IN SAND ,Reach-1,6
Up Type=0
Dn Type=3
Dn Slope=0.005
Boundary for River Rch & Prof#=UNT0156 IN SAND ,Reach-1,7
Up Type=0
Dn Type=3
Dn Slope=0.005

--- UNT0156 IN SAND CR.g01 (geometry) ---

Geom Title=Existing Conditions

River Reach=UNT0156 IN SAND ,Reach-1
Reach XY= 30
      3573527.48     10550443.43      3573598.04     10550383.64
      3573689.46     10550391.83      3573748.47     10550374.74
      3573791.71     10550381.18      3573851.39     10550342.12
      3573822.67     10550307.80      3573822.49     10550283.56
      3573851.39     10550279.19      3573932.77     10550224.93
      3574004.77     10550227.68      3574115.91     10550149.45
      3574164.78     10550136.70      3574243.12     10550093.82
      3574354.48     10550086.18      3574408.77     10549985.98
      3574393.08     10549936.28      3574401.53     10549896.35
      3574466.77     10549834.93      3574445.10     10549777.20
      3574478.26     10549735.09      3574558.62     10549694.44
      3574629.45     10549626.69      3574699.26     10549586.18
      3574793.48     10549544.96      3575080.00     10549457.62
      3575093.84     10549387.21      3575128.15     10549330.45
      3575204.98     10549335.68      3575274.02     10549280.27

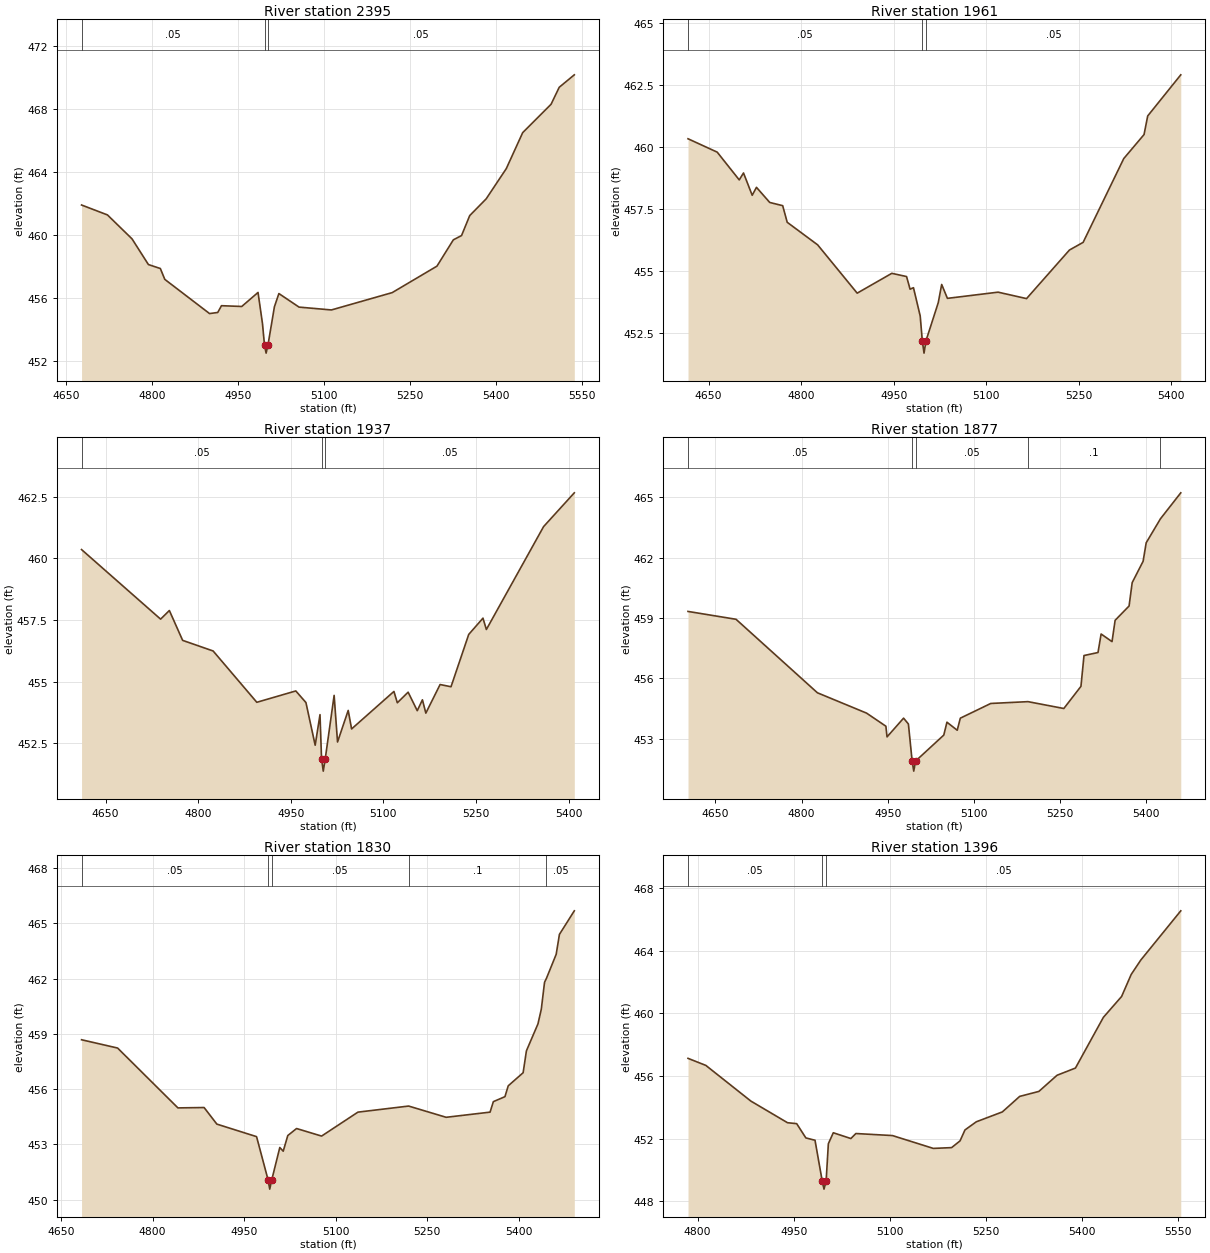
Type RM Length L Ch R = 1,2395,434,434,434
BEGIN DESCRIPTION:
UNT0156 IN SAND CR 3.0
END DESCRIPTION:
XS GIS Cut Line= 2
      3573762.07     10550666.07      3573210.15     10550006.54
#Sta/Elev= 30
  4676.7  461.91  4721.9  461.28  4764.8  459.76  4793.4  458.13  4814.2  457.88
  4822.0  457.19  4900.1  455.02  4914.4  455.09  4920.9  455.52  4956.3  455.47
  4984.7  456.36  4992.5  454.38  4996.0  453.01  4998.8  452.51  5002.0  453.01
  5013.3  455.45  5021.1  456.29  5056.3  455.43  5112.8  455.25  5218.9  456.35
  5297.0  458.03  5325.6  459.70  5339.9  459.97  5354.2  461.24  5382.9  462.30
  5418.0  464.22  5446.6  466.50  5496.1  468.30  5510.4  469.38  5536.7  470.17
#Mann=3,-1,0
  4676.7    0.05       0  4996.0    0.03       0  5002.0    0.05       0
Bank Sta=4996,5002
Exp/Cntr=0.3,0.1

Type RM Length L Ch R = 1,1961,24,24,24
BEGIN DESCRIPTION:
UNT0156 IN SAND CR 2.2
END DESCRIPTION:
XS GIS Cut Line= 4
      3574107.99     10550562.77      3573874.15     10550311.40
      3573799.93     10550152.54      3573685.35     10549897.34
#Sta/Elev= 30
  4616.8  460.33  4664.1  459.79  4699.8  458.67  4706.7  458.95  4720.8  458.05
  4727.7  458.37  4749.2  457.76  4770.2  457.63  4777.5  456.96  4826.8  456.05
  4890.9  454.10  4947.0  454.90  4970.9  454.77  4976.6  454.26  4982.1  454.32
  4993.0  453.18  4996.4  452.18  4999.2  451.68  5002.4  452.18  5022.3  453.72
  5027.8  454.45  5037.1  453.89  5119.2  454.14  5165.3  453.88  5234.8  455.84
  5257.0  456.15  5322.8  459.53  5355.7  460.50  5361.6  461.25  5415.2  462.91
#Mann=3,-1,0
  4616.8    0.05       0  4996.4    0.03       0  5002.4    0.05       0
Bank Sta=4996.4,5002.4
Exp/Cntr=0.3,0.1

Type RM Length L Ch R = 1,1937,60,60,60
BEGIN DESCRIPTION:
UNT0156 IN SAND CR 2.1
END DESCRIPTION:
XS GIS Cut Line= 4
      3574130.16     10550555.00      3573896.29     10550303.59
      3573822.07     10550144.73      3573707.47     10549889.49
#Sta/Elev= 30
  4610.9  460.35  4739.0  457.53  4753.2  457.88  4774.7  456.67  4824.1  456.24
  4894.9  454.16  4958.1  454.62  4974.5  454.15  4989.5  452.42  4997.3  453.66
  4999.8  451.87  5002.6  451.37  5005.8  451.87  5020.2  454.44  5025.7  452.55
  5043.0  453.83  5048.5  453.08  5117.1  454.60  5122.6  454.14  5140.1  454.57
  5154.9  453.82  5163.3  454.26  5168.8  453.72  5191.9  454.88  5209.6  454.79
  5238.3  456.91  5261.4  457.57  5266.9  457.11  5359.6  461.28  5409.4  462.65
#Mann=3,-1,0
  4610.9    0.05       0  4999.8    0.03       0  5005.8    0.05       0
Bank Sta=4999.8,5005.8
Exp/Cntr=0.3,0.1

Type RM Length L Ch R = 1,1877,47,47,47
BEGIN DESCRIPTION:
UNT0156 IN SAND CR 2.3
END DESCRIPTION:
XS GIS Cut Line= 4
      3574210.10     10550501.51      3573948.37     10550277.54
      3573885.87     10550135.62      3573754.36     10549802.27
#Sta/Elev= 30
  4602.3  459.33  4685.9  458.94  4827.6  455.29  4913.2  454.28  4946.8  453.63
  4948.8  453.10  4977.6  454.03  4986.0  453.74  4992.5  451.90  4995.3  451.40
  4998.5  451.90  5047.6  453.19  5053.1  453.83  5071.0  453.43  5076.4  454.03
  5129.4  454.76  5194.2  454.85  5256.6  454.51  5286.4  455.61  5291.7  457.14
  5316.1  457.29  5321.5  458.21  5340.5  457.83  5345.9  458.89  5370.2  459.60
  5375.6  460.76  5394.6  461.82  5400.0  462.74  5424.8  463.93  5460.2  465.22
#Mann=5,-1,0
  4602.3    0.05       0  4992.5    0.03       0  4998.5    0.05       0
  5194.2     0.1       0  5424.8    0.05       0
Bank Sta=4992.5,4998.5
Exp/Cntr=0.3,0.1

Type RM Length L Ch R = 1,1830,434,434,434
BEGIN DESCRIPTION:
UNT0156 IN SAND CR 2.4
END DESCRIPTION:
XS GIS Cut Line= 4
      3574200.98     10550445.69      3573997.85     10550276.42
      3573948.37     10550185.27      3573787.32     10549776.15
#Sta/Elev= 30
  4683.5  458.68  4742.6  458.23  4841.5  454.98  4884.4  455.00  4905.3  454.10
  4970.4  453.42  4989.3  451.07  4992.0  450.57  4995.3  451.07  5008.5  452.83
  5014.1  452.63  5021.6  453.48  5036.0  453.86  5077.0  453.45  5136.6  454.75
  5219.7  455.08  5281.2  454.47  5353.2  454.75  5358.6  455.32  5377.6  455.59
  5383.0  456.18  5407.4  456.89  5412.8  458.08  5431.7  459.54  5437.2  460.34
  5442.5  461.80  5445.7  462.02  5461.6  463.32  5466.9  464.40  5491.3  465.68
#Mann=5,-1,0
  4683.5    0.05       0  4989.3    0.03       0  4995.3    0.05       0
  5219.7     0.1       0  5445.7    0.05       0
Bank Sta=4989.3,4995.3
Exp/Cntr=0.3,0.1

Type RM Length L Ch R = 1,1396,550,550,550
BEGIN DESCRIPTION:
UNT0156 IN SAND CR 2.0
END DESCRIPTION:
XS GIS Cut Line= 3
      3574525.61     10550216.94      3574181.88     10549925.29
      3574004.79     10549661.39
#Sta/Elev= 30
  4785.1  457.13  4812.9  456.68  4883.2  454.40  4940.3  453.02  4954.6  452.96
  4968.9  452.05  4983.2  451.90  4994.5  449.28  4997.2  448.78  5000.5  449.28
  5004.0  451.68  5011.7  452.38  5039.1  452.01  5046.9  452.33  5104.0  452.20
  5167.7  451.38  5196.2  451.43  5209.4  451.86  5217.1  452.56  5234.8  453.08
  5275.4  453.71  5302.4  454.70  5332.4  455.02  5360.7  456.05  5389.4  456.51
  5433.0  459.75  5461.4  461.08  5476.4  462.49  5491.4  463.41  5553.7  466.55
#Mann=3,-1,0
  4785.1    0.05       0  4994.5    0.03       0  5000.5    0.05       0
Bank Sta=4994.5,5000.5
Exp/Cntr=0.3,0.1

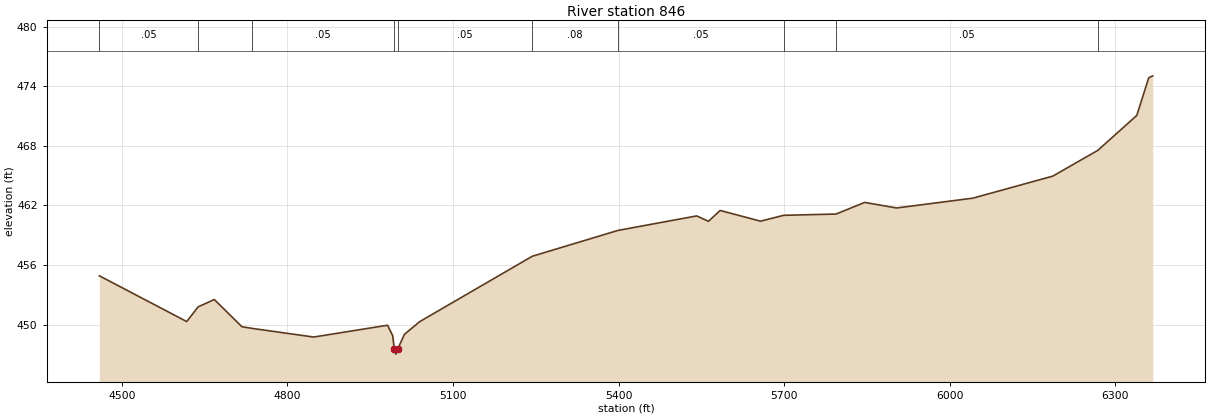
Type RM Length L Ch R = 1,846,0,0,0
BEGIN DESCRIPTION:
UNT0156 IN SAND CR 1.0
END DESCRIPTION:
XS GIS Cut Line= 3
      3574709.13     10550139.96      3574712.60     10549737.19
      3573435.92     10548939.27
#Sta/Elev= 30
  4459.2  454.92  4617.5  450.31  4638.2  451.79  4667.5  452.53  4717.5  449.79
  4736.2  449.62  4847.5  448.75  4981.3  449.94  4990.7  448.88  4993.6  447.53
  4996.4  447.03  4999.6  447.53  5012.0  449.03  5039.5  450.30  5243.6  456.89
  5398.8  459.49  5541.4  460.95  5562.7  460.41  5583.9  461.50  5657.0  460.42
  5698.8  461.01  5793.8  461.14  5845.7  462.31  5903.5  461.75  6041.8  462.74
  6186.5  464.96  6267.9  467.55  6338.6  471.07  6360.2  474.86  6367.5  475.06
#Mann=10,-1,0
  4459.2    0.05       0  4638.2    0.08       0  4736.2    0.05       0
  4993.6    0.03       0  4999.6    0.05       0  5243.6    0.08       0
  5398.8    0.05       0  5698.8    0.08       0  5793.8    0.05       0
  6267.9    0.15       0
Bank Sta=4993.6,4999.6
Exp/Cntr=0.3,0.1

Chan Stop Cuts=-1