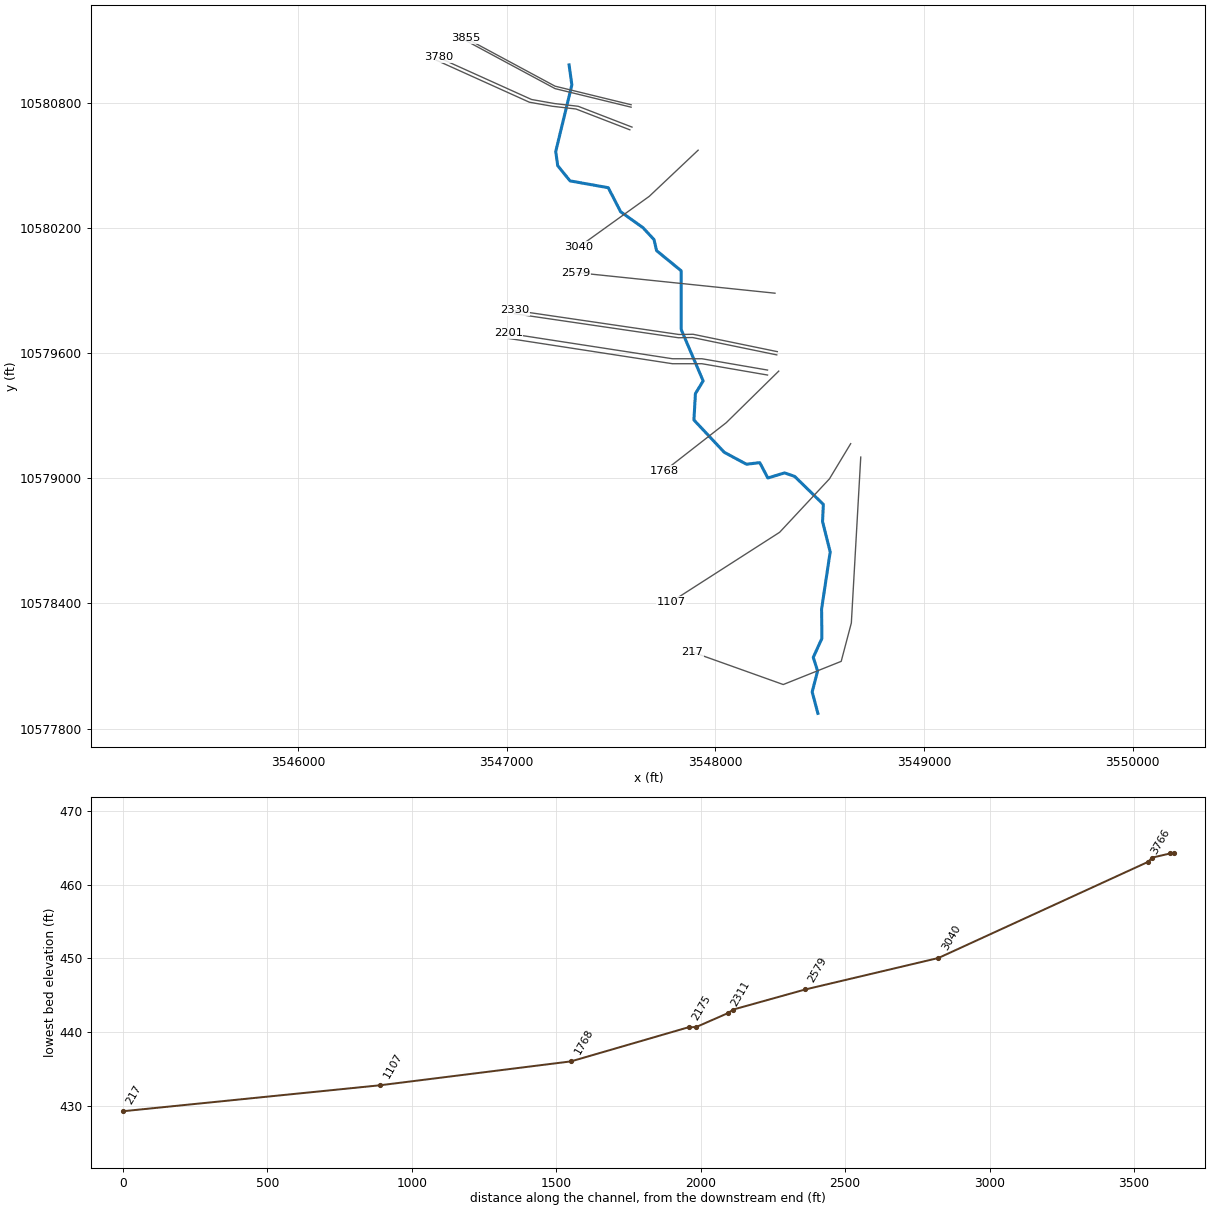
--- UNT01560 IN SAND CR.prj (project) ---

Proj Title=UNT01560 IN SAND CR Base Level Engineering
Current Plan=p01
Default Exp/Contr=0.3,0.1
English Units
Geom File=g01
Flow File=f01
Plan File=p01
Y Axis Title=Elevation
X Axis Title(PF)=Main Channel Distance
X Axis Title(XS)=Station
BEGIN DESCRIPTION:
UNT01560 IN SAND CR
END DESCRIPTION:
DSS Export Rating Curves= 0
DSS Export Rating Curve Sorted= 0
DSS Export Volume Flow Curves= 0
DXF OffsetX= 0
DXF OffsetY= 0
DXF ScaleX= 1
DXF ScaleY= 10

--- UNT01560 IN SAND CR.p01 (plan) ---

Plan Title=Multiple Run
Short Identifier=Multiple
Geom File=g01
Flow File=f01
Subcritical Flow
K Sum by GR= 0
Std Step Tol= 0.01
Critical Tol= 0.01
Num of Std Step Trials= 20
Max Error Tol= 0.3
Flow Tol Ratio= 0.001
Split Flow NTrial= 30
Split Flow Tol= 0.02
Split Flow Ratio= 0.02
Log Output Level= 0
Friction Slope Method= 1
Unsteady Friction Slope Method= 2
Unsteady Bridges Friction Slope Method= 1
Parabolic Critical Depth
Global Vel Dist=  1 , 1 , 1
Global Log Level= 0
CheckData=True
Encroach Param= -1, 0, 0, 0
BEGIN DESCRIPTION:
Multiple Run
END DESCRIPTION:

--- UNT01560 IN SAND CR.f01 (steady flow) ---

Flow Title=Multiple
Number of Profiles=7
Profile Names=10-year,25-year,50-year,1pct_min,100-year,1pct_plu,500-year
River Rch & RM= UNT01560 IN SAND,Reach-1,3855
     172     209     235     195     264     357     329
River Rch & RM= UNT01560 IN SAND,Reach-1,3040
     376     486     572     493     667     902     901
River Rch & RM= UNT01560 IN SAND,Reach-1,2201
     468     612     726     630     852    1153    1169
Boundary for River Rch & Prof#=UNT01560 IN SAND,Reach-1,1
Up Type=0
Dn Type=3
Dn Slope=0.005
Boundary for River Rch & Prof#=UNT01560 IN SAND,Reach-1,2
Up Type=0
Dn Type=3
Dn Slope=0.005
Boundary for River Rch & Prof#=UNT01560 IN SAND,Reach-1,3
Up Type=0
Dn Type=3
Dn Slope=0.005
Boundary for River Rch & Prof#=UNT01560 IN SAND,Reach-1,4
Up Type=0
Dn Type=3
Dn Slope=0.005
Boundary for River Rch & Prof#=UNT01560 IN SAND,Reach-1,5
Up Type=0
Dn Type=3
Dn Slope=0.005
Boundary for River Rch & Prof#=UNT01560 IN SAND,Reach-1,6
Up Type=0
Dn Type=3
Dn Slope=0.005
Boundary for River Rch & Prof#=UNT01560 IN SAND,Reach-1,7
Up Type=0
Dn Type=3
Dn Slope=0.005

--- UNT01560 IN SAND CR.g01 (geometry) ---

Geom Title=Existing Conditions
Program Version=4.10

River Reach=UNT01560 IN SAND,Reach-1
Reach XY= 30
      3547299.25     10580980.98      3547312.44     10580885.15
       3547235.1     10580565.86       3547244.6     10580498.18
      3547303.63     10580425.27      3547486.97     10580392.48
      3547546.12     10580277.43       3547653.5      10580200.8
      3547706.11     10580143.94      3547718.58     10580090.84
      3547836.31     10579994.36      3547836.72     10579712.48
       3547941.7     10579466.32       3547904.7     10579405.57
      3547897.55     10579279.13      3548043.11     10579124.11
      3548149.19     10579067.12      3548213.24     10579074.58
      3548251.81     10579001.03      3548332.19     10579025.51
      3548380.62     10579008.51      3548517.89     10578874.54
      3548514.17     10578792.13      3548550.77     10578646.66
       3548509.5     10578373.12      3548511.02     10578231.78
      3548469.57     10578141.46      3548490.41     10578075.92
      3548464.37     10577975.66      3548491.71     10577872.79

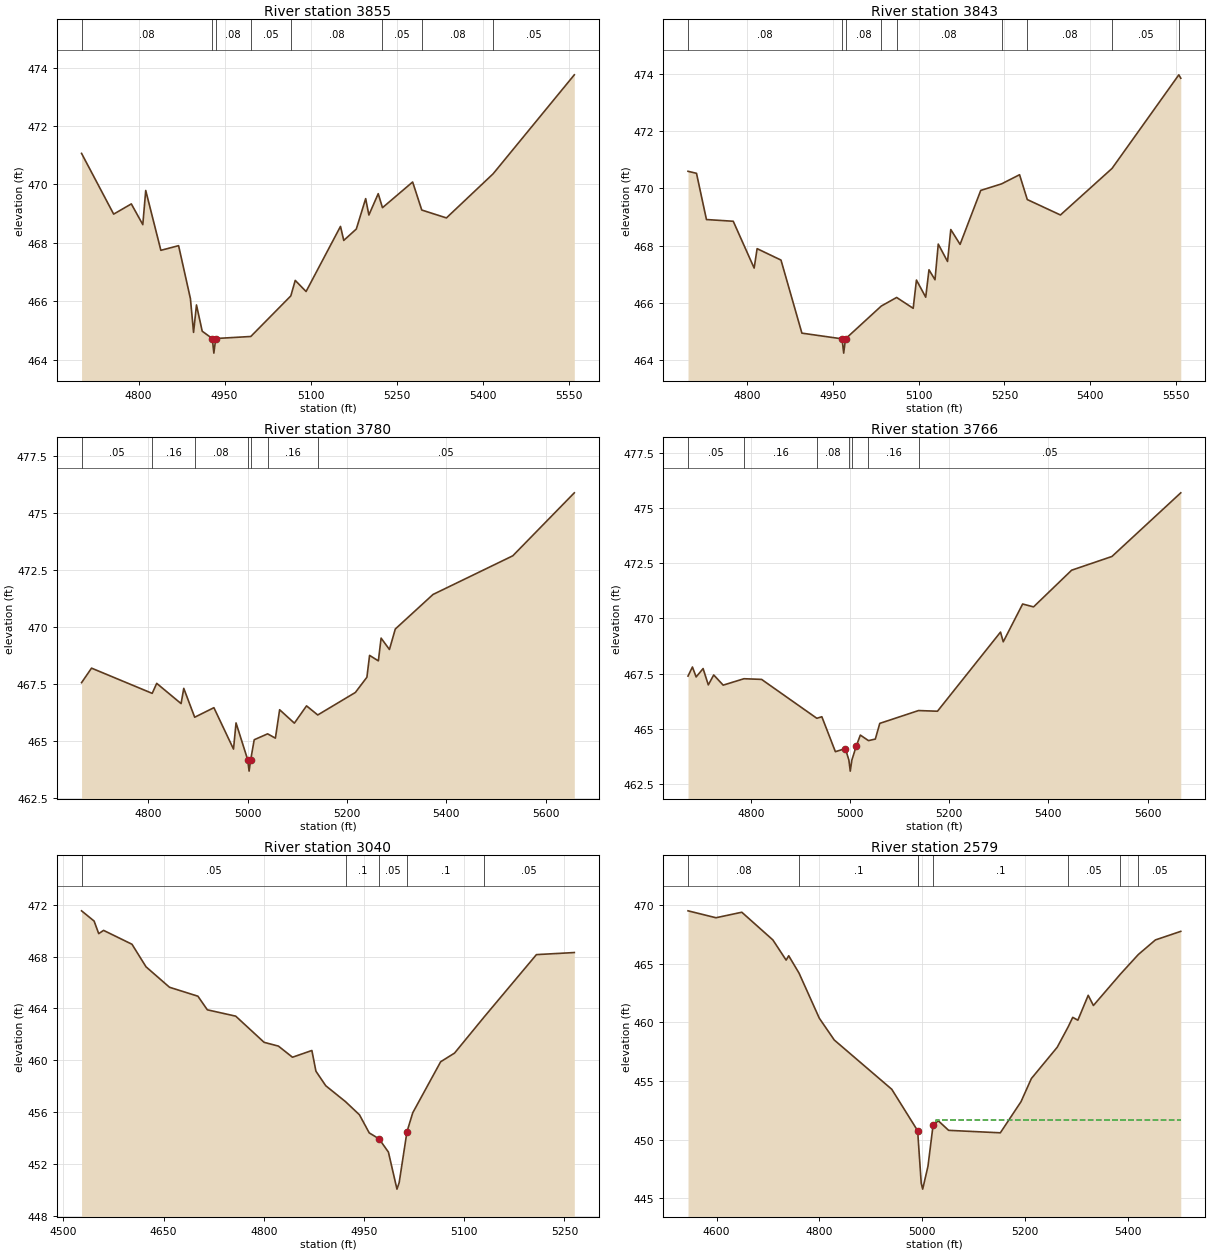
Type RM Length L Ch R = 1 ,3855    ,12,12,12
BEGIN DESCRIPTION:
UNT01560 IN SAND CR 7.3
END DESCRIPTION:
XS GIS Cut Line= 3
      3547596.47     10580790.25       3547231.9     10580879.23
      3546805.75     10581108.53
#Sta/Elev= 30
  4700.6  471.06  4756.6  468.98  4787.4  469.33  4807.4  468.62  4812.5  469.79
  4838.9  467.74  4869.8   467.9  4890.4  466.09  4895.9  464.93    4901  465.87
    4911  464.97  4928.6  464.72  4931.3  464.22  4934.6  464.72  4995.7  464.79
  5065.5  466.18  5073.2  466.71  5092.1  466.33  5152.1  468.56  5157.8  468.08
  5179.7  468.47    5196  469.51  5201.6  468.95  5217.9  469.68  5225.3   469.2
  5277.9  470.08  5293.8  469.12  5336.8  468.85  5418.2  470.36  5559.8  473.75
#Mann= 8 ,-1 , 0
  4700.6     .08       0  4928.6     .03       0  4934.6     .08       0
  4995.7     .05       0  5065.5     .08       0  5225.3     .05       0
  5293.8     .08       0  5418.2     .05       0
Bank Sta=4928.6,4934.6
XS Rating Curve= 0 ,0
Exp/Cntr=0.3,0.1

Type RM Length L Ch R = 1 ,3843    ,63,63,63
BEGIN DESCRIPTION:
UNT01560 IN SAND CR 7.1
END DESCRIPTION:
XS GIS Cut Line= 3
      3547596.45     10580778.54       3547231.9     10580867.51
      3546804.41     10581097.53
#Sta/Elev= 30
  4697.4   470.6  4712.2  470.53  4729.6  468.91  4776.4  468.85  4812.9  467.21
  4818.1  467.89  4859.8  467.49  4896.3  464.93  4966.5  464.73  4969.3  464.23
  4972.5  464.73    5035  465.88  5061.8  466.18  5090.7   465.8  5096.4  466.79
  5112.6  466.19  5118.3  467.15  5128.8   466.8  5134.5  468.05  5150.7  467.44
  5156.4  468.56  5172.6  468.04  5208.7  469.93  5245.1  470.16  5276.5  470.48
    5290  469.61  5347.9  469.07    5438   470.7  5554.7  473.98  5558.1  473.86
#Mann= 9 ,-1 , 0
  4697.4     .08       0  4966.5     .07       0  4972.5     .08       0
    5035     .05       0  5061.8     .08       0  5245.1     .05       0
    5290     .08       0    5438     .05       0  5554.7     .08       0
Bank Sta=4966.5,4972.5
XS Rating Curve= 0 ,0
Exp/Cntr=0.3,0.1

Type RM Length L Ch R = 1 ,3780    ,14,14,14
BEGIN DESCRIPTION:
UNT01560 IN SAND CR 7.0
END DESCRIPTION:
XS GIS Cut Line= 5
      3547600.81     10580683.05      3547342.57     10580782.87
      3547229.73     10580795.89      3547119.05     10580815.42
      3546672.67     10581016.94
#Sta/Elev= 30
  4665.3  467.55  4685.4  468.19  4807.6  467.08  4816.7  467.52  4865.8  466.63
  4871.2   467.3  4893.2  466.03  4931.9  466.45  4971.4  464.63  4976.5  465.78
    5000  464.16  5002.8  463.66    5006  464.16  5013.1  465.04  5040.1   465.3
  5055.8  465.11  5064.3  466.36    5094  465.77  5118.5  466.53  5141.1  466.13
  5216.9  467.12  5240.1  467.79  5245.5  468.75  5263.2  468.51  5268.7  469.51
  5285.5  469.01  5297.3  469.91  5373.3  471.43    5534  473.13  5657.9   475.9
#Mann= 7 ,-1 , 0
  4665.3     .05       0  4807.6     .16       0  4893.2     .08       0
    5000     .07       0    5006     .08       0  5040.1     .16       0
  5141.1     .05       0
Bank Sta=5000,5006
XS Rating Curve= 0 ,0
Exp/Cntr=0.3,0.1

Type RM Length L Ch R = 1 ,3766    ,726,726,726
BEGIN DESCRIPTION:
UNT01560 IN SAND CR 7.2
END DESCRIPTION:
XS GIS Cut Line= 5
      3547590.45     10580670.01      3547332.16     10580769.85
      3547219.31     10580782.87      3547108.63      10580802.4
      3546661.58     10581004.23
#Sta/Elev= 30
  4673.6  467.39  4682.5   467.8    4690  467.35    4704  467.73  4714.5  466.99
  4725.4  467.44  4744.5  466.98  4786.4  467.27  4821.9  467.24  4933.3  465.48
  4943.4  465.55  4970.7  463.97  4990.8  464.11  4997.9  463.59  5000.7  463.09
  5003.9  463.59  5012.9  464.23    5021  464.72  5037.4  464.47  5051.2  464.54
  5060.2  465.25  5138.3  465.83  5176.5   465.8  5303.6  469.38  5309.1  468.94
  5348.2  470.65  5370.2  470.52    5447  472.18  5528.2   472.8    5667  475.68
#Mann= 7 ,-1 , 0
  4673.6     .05       0  4786.4     .16       0  4933.3     .08       0
  4997.9     .07       0  5003.9     .08       0  5037.4     .16       0
  5138.3     .05       0
Bank Sta=4990.8,5012.9
XS Rating Curve= 0 ,0
Exp/Cntr=0.3,0.1

Type RM Length L Ch R = 1 ,3040    ,461,461,461
BEGIN DESCRIPTION:
UNT01560 IN SAND CR 6.0
END DESCRIPTION:
XS GIS Cut Line= 3
      3547917.77     10580572.41      3547683.41     10580351.07
      3547346.02     10580108.84
#Sta/Elev= 30
  4527.1  471.53  4545.9  470.74  4552.8  469.77  4560.1  470.02  4602.6  468.95
  4623.6  467.21  4658.8  465.63  4701.3  464.94  4715.4  463.89  4757.9   463.4
  4800.4  461.38  4821.8  461.09  4842.9  460.23  4871.9  460.75    4878  459.15
  4892.7  458.03  4922.3   456.8  4943.1  455.79  4957.8  454.39  4972.5  453.93
  4986.5  452.91  4999.3  450.05  5002.6  450.55  5014.3  454.48  5022.9  455.94
  5064.7  459.88  5085.5  460.55  5129.7  463.33  5208.1  468.15  5264.8  468.31
#Mann= 5 ,-1 , 0
  4527.1     .05       0  4922.3      .1       0  4972.5     .05       0
  5014.3      .1       0  5129.7     .05       0
Bank Sta=4972.5,5014.3
XS Rating Curve= 0 ,0
Exp/Cntr=0.3,0.1

Type RM Length L Ch R = 1 ,2579    ,249,249,249
BEGIN DESCRIPTION:
UNT01560 IN SAND CR 6.1
END DESCRIPTION:
XS GIS Cut Line= 2
      3548286.18     10579886.87       3547333.1     10579985.82
#Sta/Elev= 30
  4544.5   469.5  4598.9  468.91  4649.1  469.38  4709.5  467.02  4735.3   465.3
  4740.3  465.67  4760.4  464.19  4799.9  460.34  4828.9  458.49  4940.7  454.29
    4991  450.76    4998  446.28  5000.8  445.78  5011.1  447.73  5021.1  451.25
  5031.3   451.6  5051.3  450.79  5151.8  450.58    5192  453.23  5212.1   455.2
  5262.4  457.87  5283.6   459.6  5292.6  460.42  5302.6  460.18  5322.7   462.3
  5332.8  461.43  5384.8  464.08    5420  465.77  5453.4  467.02  5502.7  467.75
#Mann= 8 ,-1 , 0
  4544.5     .08       0  4760.4      .1       0    4991     .16       0
    4991     .05       0  5021.1      .1       0  5283.6     .05       0
  5384.8     .16       0    5420     .05       0
#XS Ineff= 2 , 0
                         5027.56          451.65
Permanent Ineff=
       F       F
Bank Sta=4991,5021.1
XS Rating Curve= 0 ,0
Exp/Cntr=0.3,0.1

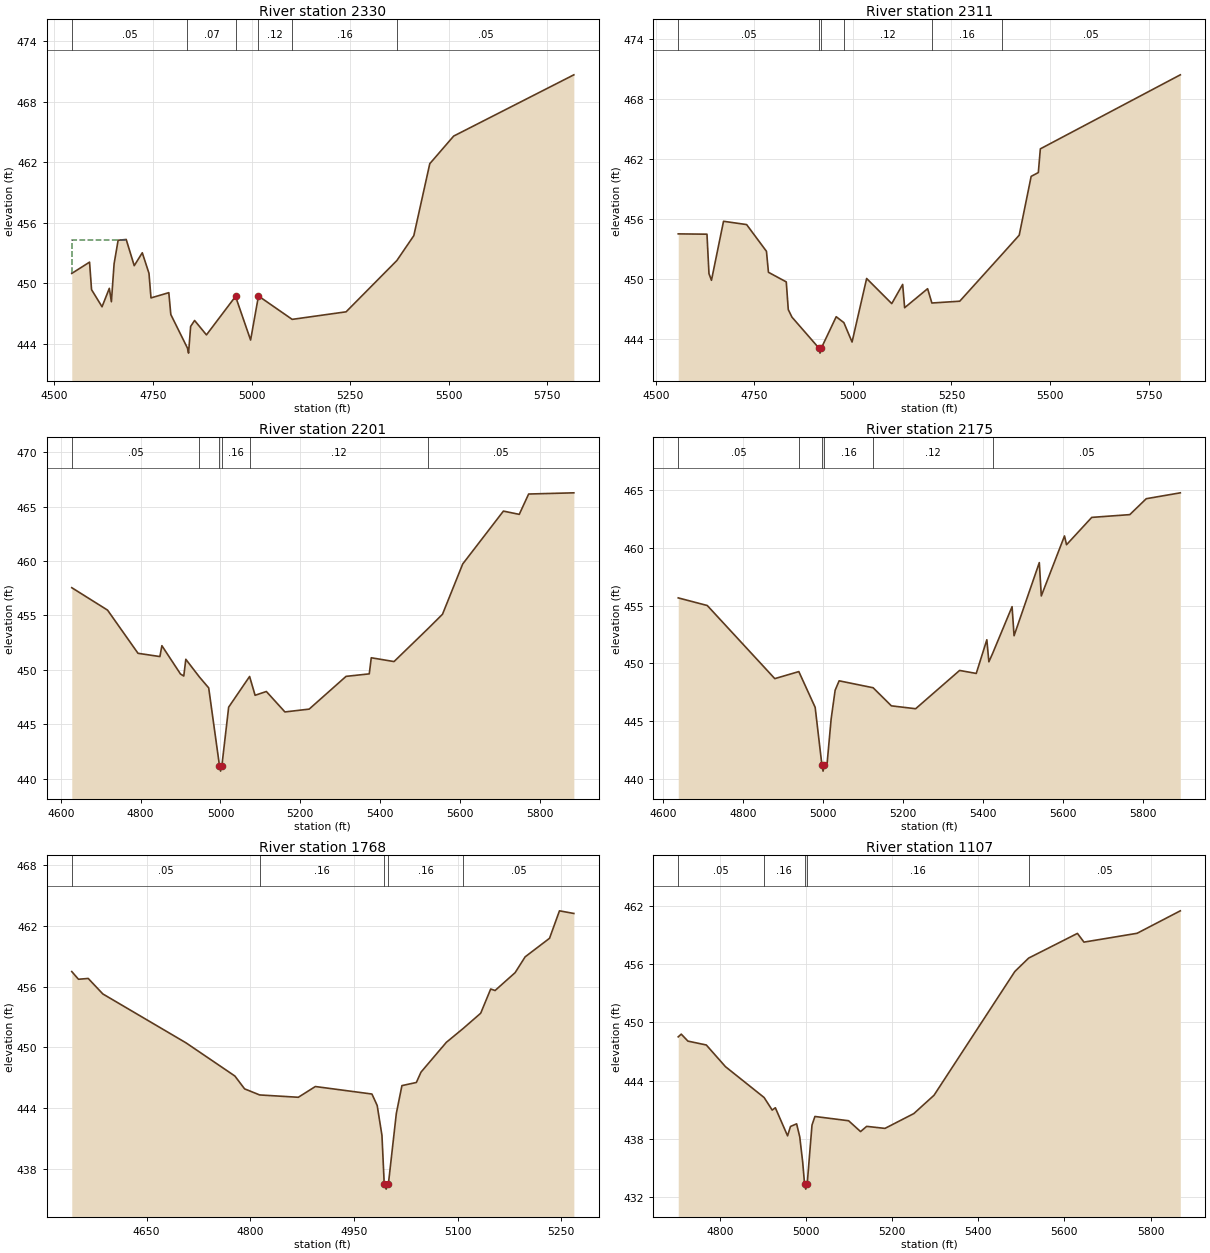
Type RM Length L Ch R = 1 ,2330    ,19,19,19
BEGIN DESCRIPTION:
UNT01560 IN SAND CR 4.3
END DESCRIPTION:
XS GIS Cut Line= 4
      3548297.33     10579606.74       3547893.5     10579689.99
      3547825.79     10579688.95      3547040.42     10579804.05
#Sta/Elev= 30
    4544  450.97  4589.1  452.09  4594.2  449.36  4620.8  447.66  4639.3  449.49
  4644.5  448.16  4651.4  451.93  4661.6  454.26  4682.1  454.34  4702.5  451.74
  4722.9  453.02  4739.9  450.98    4745  448.54  4790.2  449.06  4795.3  446.89
  4837.5  443.56  4840.3  443.06  4845.6  445.71  4855.6   446.3  4885.7  444.87
  4959.5  448.69  4997.7  444.36  5017.7  448.73  5103.2  446.41    5240  447.16
  5368.8  452.25  5411.8  454.72  5452.3  461.86  5512.9   464.6  5817.8  470.68
#Mann= 6 ,-1 , 0
    4544     .05       0  4837.5     .07       0  4959.5     .05       0
  5017.7     .12       0  5103.2     .16       0  5368.8     .05       0
#XS Ineff= 2 , 0
         4683.16  454.33
Permanent Ineff=
       F       F
Bank Sta=4959.5,5017.7
XS Rating Curve= 0 ,0
Exp/Cntr=0.3,0.1

Type RM Length L Ch R = 1 ,2311    ,110,110,110
BEGIN DESCRIPTION:
UNT01560 IN SAND CR 4.2
END DESCRIPTION:
XS GIS Cut Line= 4
      3548294.66     10579591.13       3547890.9     10579674.37
      3547823.19     10579673.32      3547037.75     10579788.43
#Sta/Elev= 30
  4556.9  454.49  4629.8  454.46  4634.9  450.52  4641.2  449.85  4671.8  455.75
  4730.4  455.42  4780.7  452.75  4785.8  450.65    4831  449.69  4836.1  446.92
  4845.4  446.17  4913.9  443.07  4916.6  442.57  4919.9  443.07  4957.7  446.21
  4977.1  445.62  4997.9  443.68  5034.9  450.03  5098.6  447.52  5126.3  449.44
  5131.3  447.11  5189.6  449.01  5200.4  447.58  5271.1  447.76  5378.3  452.44
    5422  454.36  5452.3  460.24  5470.5  460.62  5475.6  462.99  5830.7  470.39
#Mann= 6 ,-1 , 0
  4556.9     .05       0  4913.9     .07       0  4919.9     .05       0
  4977.1     .12       0  5200.4     .16       0  5378.3     .05       0
Bank Sta=4913.9,4919.9
XS Rating Curve= 0 ,0
Exp/Cntr=0.3,0.1

Type RM Length L Ch R = 1 ,2201    ,26,26,26
BEGIN DESCRIPTION:
UNT01560 IN SAND CR 4.0
END DESCRIPTION:
XS GIS Cut Line= 4
      3548250.38     10579518.43      3547935.75     10579572.68
      3547794.69     10579572.68      3547007.04     10579694.19
#Sta/Elev= 30
  4627.6  457.54  4717.2  455.48  4793.5  451.51  4848.3  451.21  4853.3  452.21
  4899.8  449.61  4908.1  449.42  4913.2  450.96  4947.3  449.33  4970.5  448.33
  4997.5  441.18  5000.3  440.68  5003.5  441.18  5020.5  446.56  5072.9  449.38
  5086.7  447.65  5114.9     448  5161.4  446.12  5222.1  446.38  5314.5  449.39
  5372.6  449.62  5377.6   451.1  5434.6  450.75  5520.1  453.79    5556   455.1
  5606.6  459.72  5708.5  464.58  5748.2  464.28  5771.7  466.15  5884.9  466.26
#Mann= 6 ,-1 , 0
  4627.6     .05       0  4947.3     .16       0  4997.5     .07       0
  5003.5     .16       0  5072.9     .12       0  5520.1     .05       0
Bank Sta=4997.5,5003.5
XS Rating Curve= 0 ,0
Exp/Cntr=0.3,0.1

Type RM Length L Ch R = 1 ,2175    ,407,407,407
BEGIN DESCRIPTION:
UNT01560 IN SAND CR 4.1
END DESCRIPTION:
XS GIS Cut Line= 4
      3548250.38     10579494.56      3547935.75     10579548.81
      3547794.69     10579548.81      3547007.04     10579670.32
#Sta/Elev= 30
  4637.1  455.68  4709.8  455.02  4878.9  448.68  4939.1  449.29    4980  446.19
    4997  441.16  4999.8  440.66    5003  441.16    5010  441.36    5020  445.18
    5030  447.67    5040  448.49  5125.1  447.89  5170.9  446.32  5231.6  446.07
  5341.7  449.39  5383.4  449.13  5409.9  452.05    5415  450.14  5424.1  450.84
  5473.1  454.92  5478.1   452.4  5541.3  458.74  5546.3  455.85  5604.4  461.05
  5609.5  460.29  5672.6  462.66  5767.9   462.9  5809.1  464.28  5894.4  464.79
#Mann= 6 ,-1 , 0
  4637.1     .05       0  4939.1     .16       0    4997     .07       0
    5003     .16       0  5125.1     .12       0  5424.1     .05       0
Bank Sta=4997,5003
XS Rating Curve= 0 ,0
Exp/Cntr=0.3,0.1

Type RM Length L Ch R = 1 ,1768    ,661,661,661
BEGIN DESCRIPTION:
UNT01560 IN SAND CR 3.0
END DESCRIPTION:
XS GIS Cut Line= 3
      3548304.06     10579513.38      3548052.34       10579266.
      3547757.62     10579036.29
#Sta/Elev= 30
  4541.6  457.49  4551.3  456.73  4565.4  456.81  4586.6  455.28  4706.9  450.46
  4777.6  447.19  4791.7  445.92  4813.5  445.32  4869.5  445.09  4894.1  446.15
    4976  445.41  4983.6  444.28  4990.5  441.33  4993.8  436.53  4996.6  436.03
  4999.8  436.53  5011.3  443.49  5019.4  446.24  5040.3  446.55    5047  447.57
  5083.7  450.51  5107.6  451.85  5133.4  453.38  5147.9  455.77  5154.2  455.62
  5183.2  457.38  5197.7  458.94    5233  460.77  5247.4  463.48  5268.2  463.22
#Mann= 5 ,-1 , 0
  4541.6     .05       0  4813.5     .16       0  4993.8     .07       0
  4999.8     .16       0  5107.6     .05       0
Bank Sta=4993.8,4999.8
XS Rating Curve= 0 ,0
Exp/Cntr=0.3,0.1

Type RM Length L Ch R = 1 ,1107    ,890,890,890
BEGIN DESCRIPTION:
UNT01560 IN SAND CR 1.0
END DESCRIPTION:
XS GIS Cut Line= 4
      3548648.94     10579165.58      3548547.13      10578996.9
      3548308.41     10578740.83      3547787.61     10578406.65
#Sta/Elev= 30
  4703.3  448.51  4710.3  448.79  4725.8  448.07  4768.5  447.67    4813  445.43
  4902.7  442.25  4921.5  440.95  4928.8  441.19  4957.2  438.29    4964  439.26
  4978.2  439.53  4985.5  438.18  4992.4  435.54  4996.7  433.29  4999.4  432.79
  5002.7  433.29  5013.9   439.4  5020.7  440.29  5098.9  439.85  5126.7  438.73
  5140.9  439.27  5183.4  439.06  5250.4  440.59  5297.3  442.48    5485  455.26
    5517  456.64  5630.3  459.19  5645.5  458.29  5768.8   459.2  5869.2  461.52
#Mann= 5 ,-1 , 0
  4703.3     .05       0  4902.7     .16       0  4996.7     .07       0
  5002.7     .16       0    5517     .05       0
Bank Sta=4996.7,5002.7
XS Rating Curve= 0 ,0
Exp/Cntr=0.3,0.1

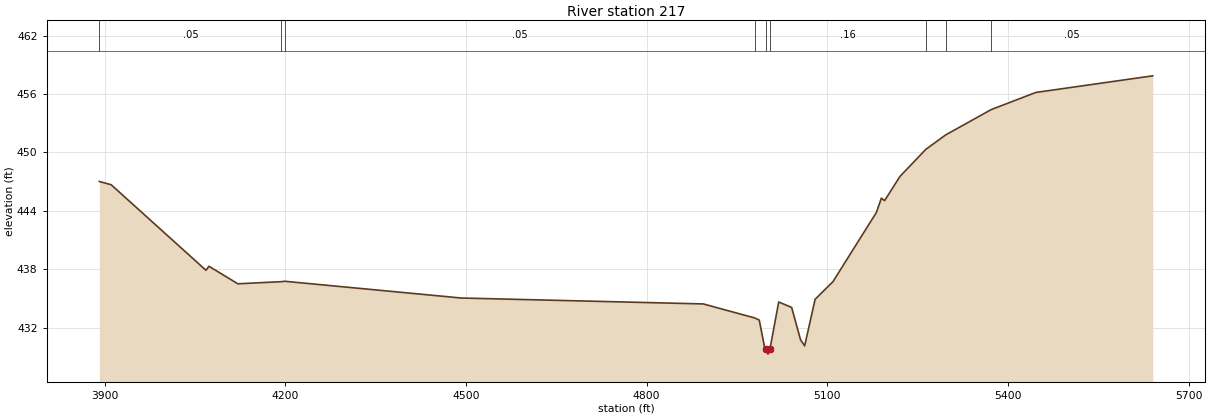
Type RM Length L Ch R = 1 ,217     ,0,0,0
BEGIN DESCRIPTION:
UNT01560 IN SAND CR 1.1
END DESCRIPTION:
XS GIS Cut Line= 5
      3548697.26     10579101.33      3548652.12     10578306.18
      3548603.51     10578122.16      3548325.74     10578011.05
      3547889.18     10578166.96
#Sta/Elev= 30
  3891.1  447.02  3910.8  446.68  4068.2  437.89  4073.2   438.3  4121.2   436.5
  4193.6  436.72  4198.8  436.76  4491.8  435.04  4894.1  434.43  4979.5  432.99
  4987.1  432.77  4996.4  429.84  4998.8  429.77  5001.6  429.27  5004.8  429.77
  5019.4  434.63  5040.9  434.07  5055.7  430.74  5062.5  430.12  5079.9  434.91
  5109.5  436.72  5181.6  443.83  5189.9   445.3  5195.3  445.05  5220.7  447.53
  5263.7  450.32  5296.8  451.81  5372.4  454.41  5446.4  456.17  5640.6  457.88
#Mann= 9 ,-1 , 0
  3891.1     .05       0  4193.6     .08       0  4198.8     .05       0
  4979.5     .16       0  4998.8     .07       0  5004.8     .16       0
  5263.7     .05       0  5296.8     .16       0  5372.4     .05       0
Bank Sta=4998.8,5004.8
XS Rating Curve= 0 ,0
Exp/Cntr=0.3,0.1

Chan Stop Cuts=-1
Use User Specified Reach Order=0
Composite Channel Slope=5