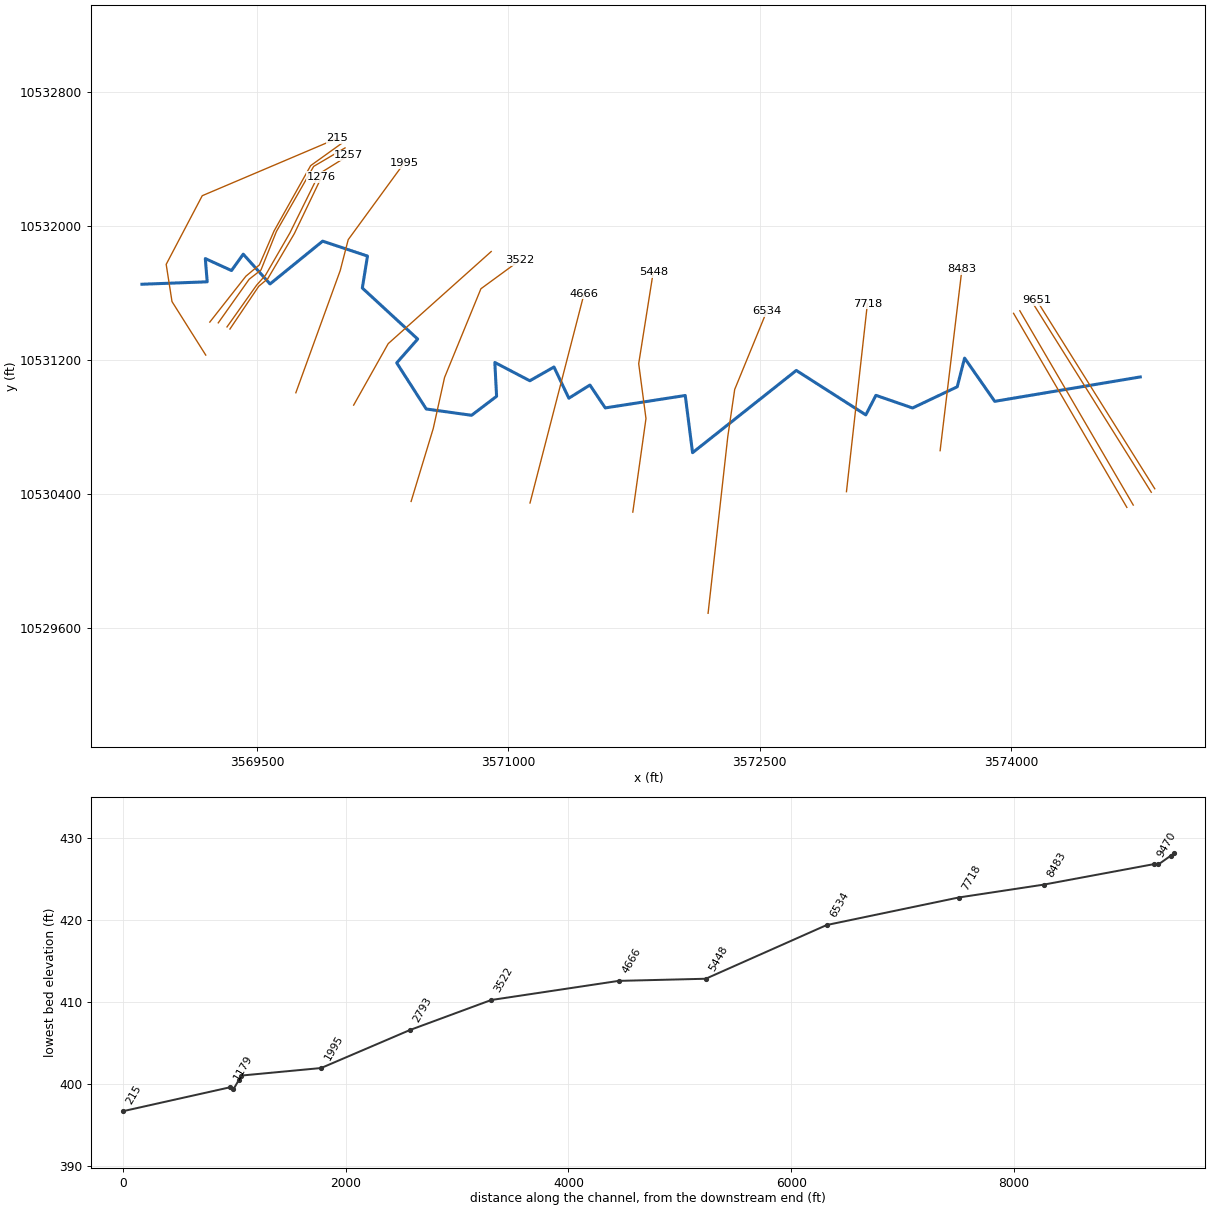
--- UNT0157 IN SAND CR.prj (project) ---

Proj Title=UNT0157 IN SAND CR Base Level Engineering
Current Plan=p01
Default Exp/Contr=0.3,0.1
English Units
Geom File=g01
Flow File=f01
Plan File=p01
Y Axis Title=Elevation
X Axis Title(PF)=Main Channel Distance
X Axis Title(XS)=Station
BEGIN DESCRIPTION:
UNT0157 IN SAND CR
END DESCRIPTION:
DSS Export Rating Curves= 0
DSS Export Rating Curve Sorted= 0
DSS Export Volume Flow Curves= 0
DXF OffsetX= 0
DXF OffsetY= 0
DXF ScaleX= 1
DXF ScaleY= 10

--- UNT0157 IN SAND CR.p01 (plan) ---

Plan Title=Multiple Run
Short Identifier=Multiple
Geom File=g01
Flow File=f01
Subcritical Flow
K Sum by GR= 0
Std Step Tol= 0.01
Critical Tol= 0.01
Num of Std Step Trials= 20
Max Error Tol= 0.3
Flow Tol Ratio= 0.001
Split Flow NTrial= 30
Split Flow Tol= 0.02
Split Flow Ratio= 0.02
Log Output Level= 0
Friction Slope Method= 1
Unsteady Friction Slope Method= 2
Unsteady Bridges Friction Slope Method= 1
Parabolic Critical Depth
Global Vel Dist=  1 , 1 , 1
Global Log Level= 0
CheckData=True
Encroach Param= -1, 0, 0, 0
BEGIN DESCRIPTION:
Multiple Run
END DESCRIPTION:

--- UNT0157 IN SAND CR.f01 (steady flow) ---

Flow Title=Multiple
Number of Profiles=7
Profile Names=10-year,25-year,50-year,1pct_min,100-year,1pct_plu,500-year
River Rch & RM= UNT0157 IN SAND ,Reach-1,9651
    1614    2261    2805    2534    3426    4634    5101
Boundary for River Rch & Prof#=UNT0157 IN SAND ,Reach-1,1
Up Type=0
Dn Type=3
Dn Slope=0.005
Boundary for River Rch & Prof#=UNT0157 IN SAND ,Reach-1,2
Up Type=0
Dn Type=3
Dn Slope=0.005
Boundary for River Rch & Prof#=UNT0157 IN SAND ,Reach-1,3
Up Type=0
Dn Type=3
Dn Slope=0.005
Boundary for River Rch & Prof#=UNT0157 IN SAND ,Reach-1,4
Up Type=0
Dn Type=3
Dn Slope=0.005
Boundary for River Rch & Prof#=UNT0157 IN SAND ,Reach-1,5
Up Type=0
Dn Type=3
Dn Slope=0.005
Boundary for River Rch & Prof#=UNT0157 IN SAND ,Reach-1,6
Up Type=0
Dn Type=3
Dn Slope=0.005
Boundary for River Rch & Prof#=UNT0157 IN SAND ,Reach-1,7
Up Type=0
Dn Type=3
Dn Slope=0.005

--- UNT0157 IN SAND CR.g01 (geometry) ---

Geom Title=Existing Conditions
Program Version=4.10

River Reach=UNT0157 IN SAND ,Reach-1
Reach XY= 30
      3574771.03     10531098.35      3573902.28      10530952.8
      3573722.44      10531210.8      3573678.48     10531039.53
      3573411.95     10530912.99      3573193.17     10530988.54
      3573132.76     10530871.75      3572717.81     10531137.16
      3572098.77     10530646.21      3572055.13     10530987.65
      3571577.67     10530913.49      3571486.11     10531050.09
      3571360.25     10530971.35      3571271.48     10531157.68
      3571127.38     10531075.52      3570918.48     10531184.74
        3570929.     10530982.86      3570779.72     10530869.39
      3570509.16     10530907.06      3570332.91     10531182.19
      3570458.04     10531324.39      3570127.57     10531629.16
      3570158.42     10531819.82      3569890.83     10531908.89
      3569576.77     10531653.34      3569416.92     10531830.96
      3569346.56     10531733.54      3569190.41     10531804.74
      3569201.63     10531666.18      3568812.11     10531651.64

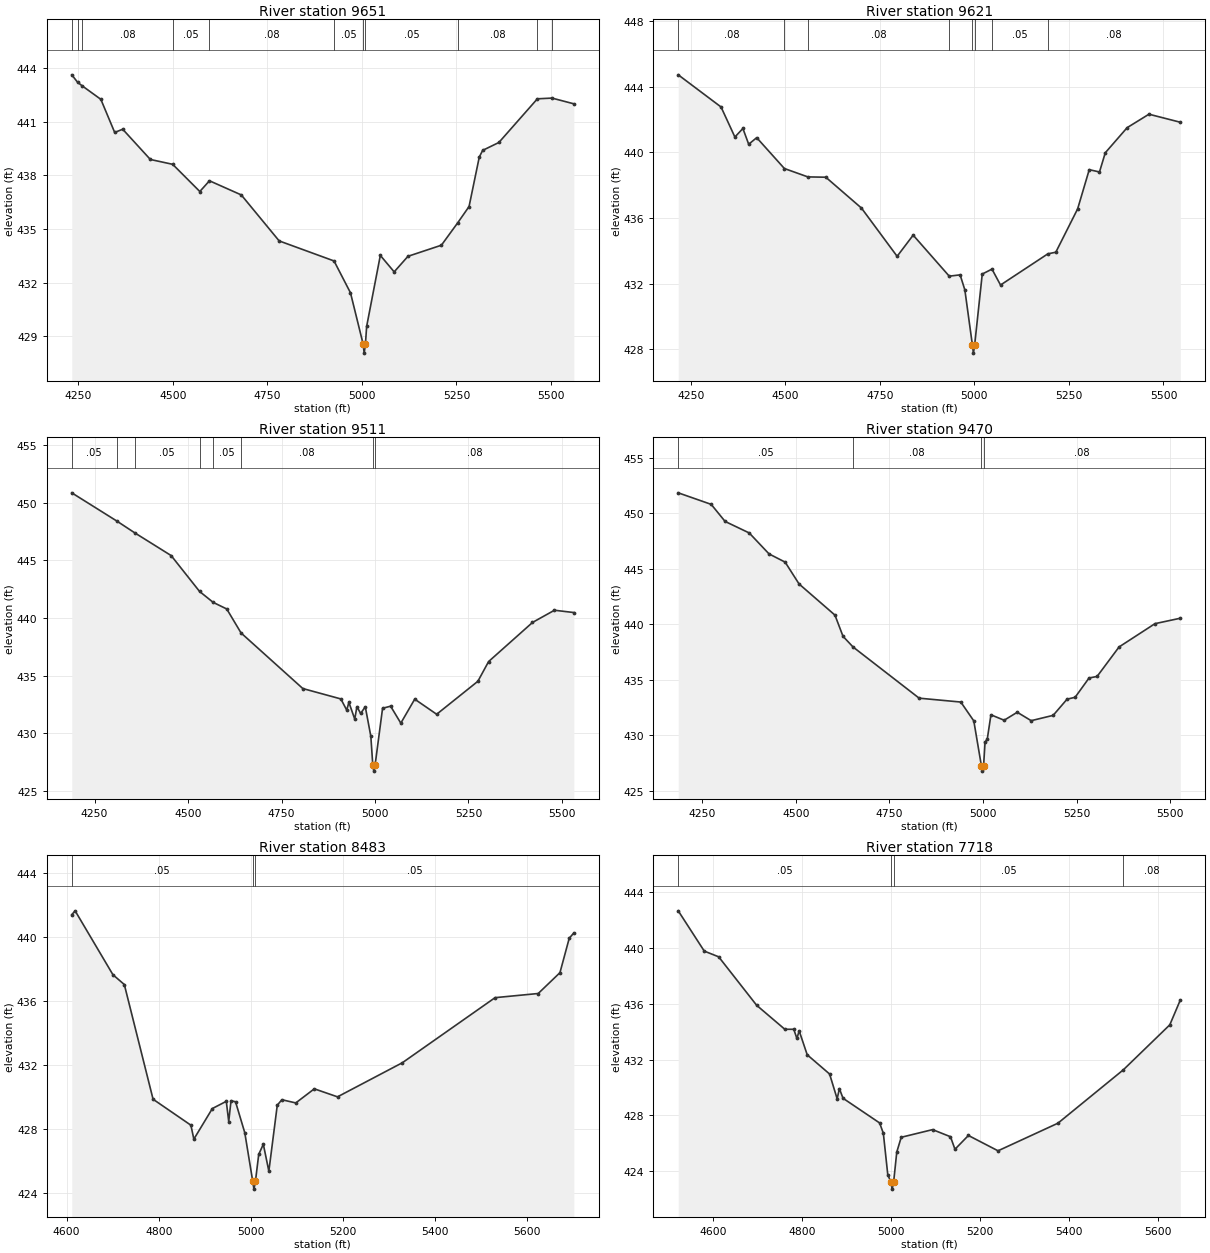
Type RM Length L Ch R = 1 ,9651    ,30,30,30
BEGIN DESCRIPTION:
UNT0157 IN SAND CR 15.0
END DESCRIPTION:
XS GIS Cut Line= 2
       3574857.6     10530430.88      3574152.73     10531555.91
#Sta/Elev= 30
  4232.7  443.62  4248.3   443.2  4259.9  443.01  4309.6  442.25  4346.2   440.4
  4367.4  440.58  4440.5  438.89  4499.5  438.62  4571.3   437.1  4596.8   437.7
  4680.9  436.91  4781.1  434.34  4926.2  433.22  4969.7  431.44  5003.2  428.57
  5005.9  428.07  5009.2  428.57  5012.4  429.56  5048.6  433.53  5085.2  432.61
  5121.7  433.48  5210.1   434.1  5253.5  435.36  5283.2  436.26  5310.3  439.03
  5319.3   439.4  5362.1  439.84  5463.9  442.28  5502.6  442.32  5560.3     442
#Mann= 11 ,-1 , 0
  4232.7     .05       0  4248.3      .1       0  4259.9     .08       0
  4499.5     .05       0  4596.8     .08       0  4926.2     .05       0
  5003.2     .03       0  5009.2     .05       0  5253.5     .08       0
  5463.9     .05       0  5502.6     .08       0
Bank Sta=5003.2,5009.2
XS Rating Curve= 0 ,0
Exp/Cntr=0.3,0.1

Type RM Length L Ch R = 1 ,9621    ,110,110,110
BEGIN DESCRIPTION:
UNT0157 IN SAND CR 15.1
END DESCRIPTION:
XS GIS Cut Line= 2
       3574836.8       10530410.      3574131.93     10531535.02
#Sta/Elev= 30
    4217  444.73  4330.2  442.77  4366.8  440.94    4388  441.46  4403.3   440.5
  4424.5   440.9  4497.7  439.02  4559.7  438.51  4607.2  438.49  4701.5  436.61
  4795.8  433.67  4838.2  434.96  4933.6  432.46  4962.4  432.54  4974.9  431.62
  4994.8  428.27  4997.5  427.77  5000.8  428.27  5020.9  432.59  5046.6  432.89
  5069.2  431.92  5194.3  433.82  5215.4  433.92  5273.1  436.56  5303.8  438.95
  5330.9  438.81  5346.2  439.98    5404  441.51  5461.7  442.33  5544.6  441.84
#Mann= 8 ,-1 , 0
    4217     .08       0  4497.7     .05       0  4559.7     .08       0
  4933.6     .05       0  4994.8     .07       0  5000.8     .05       0
  5046.6     .05       0  5194.3     .08       0
Bank Sta=4994.8,5000.8
XS Rating Curve= 0 ,0
Exp/Cntr=0.3,0.1

Type RM Length L Ch R = 1 ,9511    ,41,41,41
BEGIN DESCRIPTION:
UNT0157 IN SAND CR 14.0
END DESCRIPTION:
XS GIS Cut Line= 2
      3574729.14     10530333.65      3574052.06     10531493.36
#Sta/Elev= 30
  4188.9  450.85  4308.6  448.42  4356.9  447.39  4454.7  445.41  4530.7   442.3
  4567.2  441.35  4603.4  440.78  4641.7   438.7  4806.9  433.88  4908.6  432.98
  4924.3  432.01  4930.1  432.68  4945.8  431.23  4951.6  432.31  4961.5  431.72
    4974   432.3  4988.8  429.74  4994.1  427.22  4996.9  426.72  5000.1  427.22
  5020.2  432.17  5041.7  432.35    5069  430.88  5106.2  432.96  5164.9  431.65
  5275.1  434.51  5303.8  436.22  5421.2  439.61  5479.9  440.67  5531.8  440.47
#Mann= 8 ,-1 , 0
  4188.9     .05       0  4308.6     .08       0  4356.9     .05       0
  4530.7     .08       0  4567.2     .05       0  4641.7     .08       0
  4994.1     .07       0  5000.1     .08       0
Bank Sta=4994.1,5000.1
XS Rating Curve= 0 ,0
Exp/Cntr=0.3,0.1

Type RM Length L Ch R = 1 ,9470    ,987,987,987
BEGIN DESCRIPTION:
UNT0157 IN SAND CR 14.1
END DESCRIPTION:
XS GIS Cut Line= 2
      3574690.97     10530319.72      3574014.69     10531478.06
#Sta/Elev= 30
    4186  451.86    4274  450.82  4311.2  449.28  4375.7  448.24  4428.6  446.35
  4471.6  445.61  4508.8  443.64  4604.7  440.83  4626.2  438.92  4652.9  437.96
  4829.6  433.34  4940.9  432.99  4975.6  431.29  4995.8  427.26  4998.5  426.76
  5001.8  427.26  5005.7  429.39  5011.5  429.63  5021.4  431.84  5056.7  431.35
  5091.7  432.07  5128.9  431.31  5187.6  431.79  5224.8  433.25  5246.3  433.42
  5283.5  435.16    5305   435.3  5363.7  437.96  5459.6  440.06  5527.3  440.55
#Mann= 4 ,-1 , 0
    4186     .05       0  4652.9     .08       0  4995.8     .07       0
  5001.8     .08       0
Bank Sta=4995.8,5001.8
XS Rating Curve= 0 ,0
Exp/Cntr=0.3,0.1

Type RM Length L Ch R = 1 ,8483    ,765,765,765
BEGIN DESCRIPTION:
UNT0157 IN SAND CR 13.0
END DESCRIPTION:
XS GIS Cut Line= 2
      3573576.37     10530658.28      3573706.57     10531741.59
#Sta/Elev= 30
  4611.1   441.4  4618.4  441.64  4700.6  437.65  4725.3  437.04  4787.8  429.88
    4870  428.26  4876.4  427.39  4916.6   429.3  4946.9  429.75  4952.2  428.49
  4957.2  429.79    4967  429.72  4987.1  427.79  5004.3  424.77    5007  424.27
  5010.3  424.77  5017.4  426.44  5027.4  427.07  5039.4  425.39  5057.7  429.51
  5067.7  429.85  5097.9  429.65  5138.2  430.53  5188.6  430.03  5329.6  432.16
    5531  436.22  5624.8  436.48    5672  437.78  5692.2  439.93  5702.2  440.26
#Mann= 3 ,-1 , 0
  4611.1     .05       0  5004.3     .03       0  5010.3     .05       0
Bank Sta=5004.3,5010.3
XS Rating Curve= 0 ,0
Exp/Cntr=0.3,0.1

Type RM Length L Ch R = 1 ,7718    ,1184,1184,1184
BEGIN DESCRIPTION:
UNT0157 IN SAND CR 11.0
END DESCRIPTION:
XS GIS Cut Line= 2
      3573017.34      10530413.5      3573142.34     10531535.06
#Sta/Elev= 30
  4521.2  442.67  4579.7  439.78  4612.1  439.37  4697.5  435.89  4760.8  434.17
  4780.9  434.17  4787.9  433.51    4793  434.06  4811.1  432.34  4861.4  430.96
  4878.4  429.18  4883.4  429.91  4891.6  429.22  4973.8  427.45  4982.2  426.71
  4992.2  423.73  4999.3   423.2    5002   422.7  5005.3   423.2  5012.4  425.36
  5022.4  426.42  5092.9  426.97  5133.1  426.46  5143.2  425.56  5173.4  426.55
    5240  425.45  5374.6  427.43  5521.6  431.26  5626.1  434.49  5649.7  436.27
#Mann= 4 ,-1 , 0
  4521.2     .05       0  4999.3     .03       0  5005.3     .05       0
  5521.6     .08       0
Bank Sta=4999.3,5005.3
XS Rating Curve= 0 ,0
Exp/Cntr=0.3,0.1

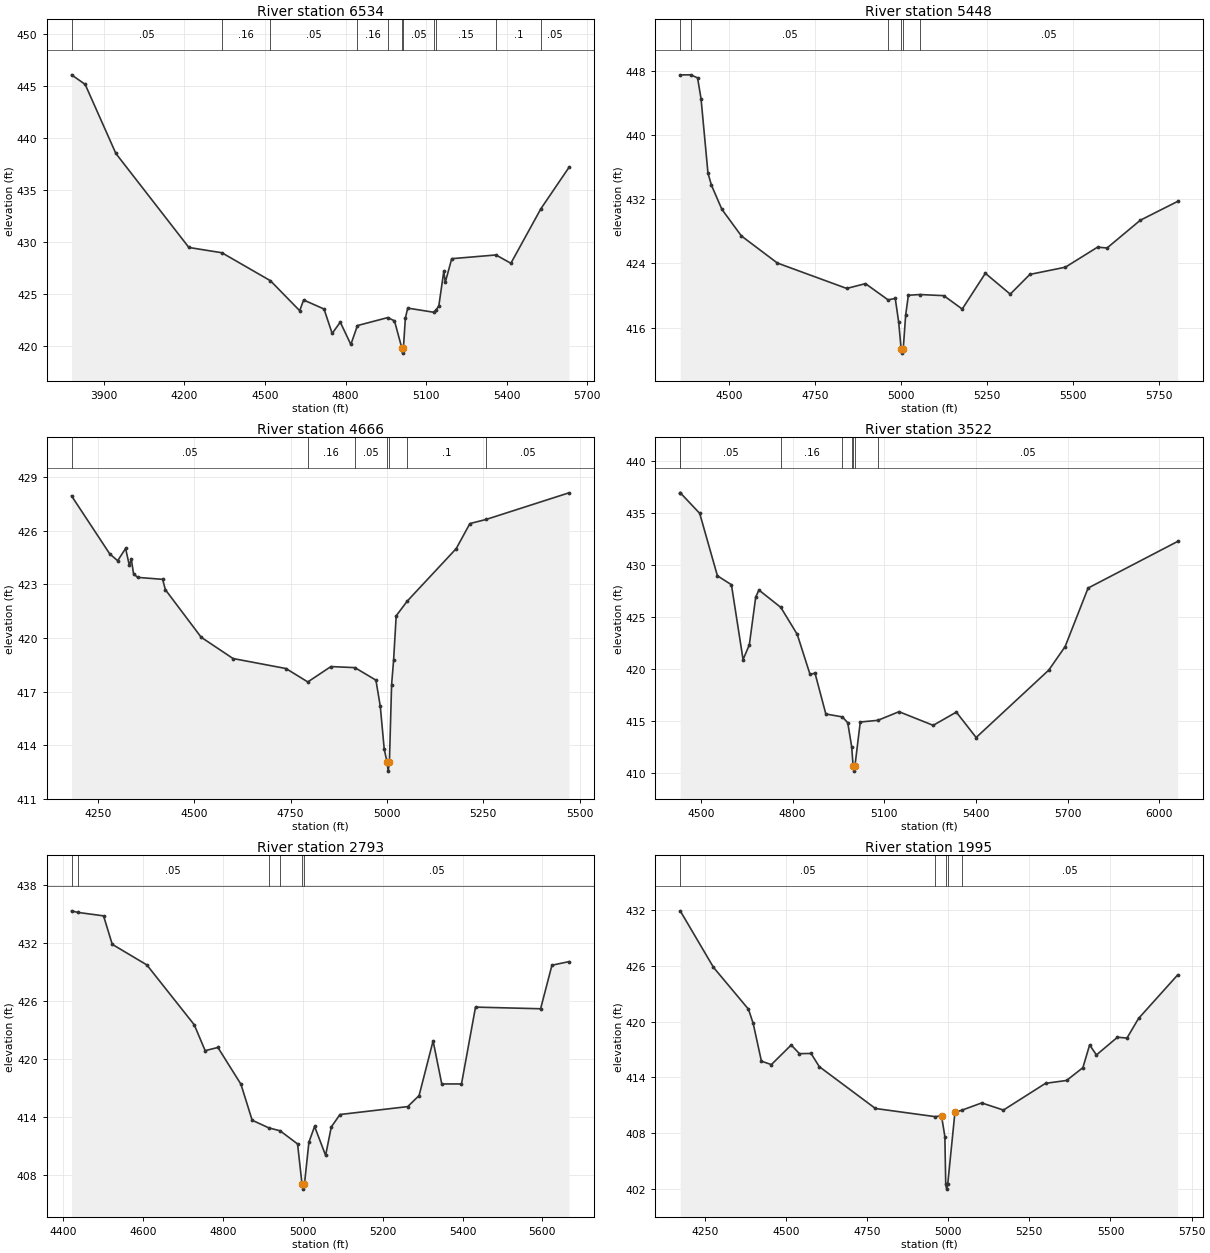
Type RM Length L Ch R = 1 ,6534    ,1086,1086,1086
BEGIN DESCRIPTION:
UNT0157 IN SAND CR 9.0
END DESCRIPTION:
XS GIS Cut Line= 4
      3572191.32     10529687.65      3572308.93     10530741.43
      3572350.17     10531023.55      3572542.12     10531491.68
#Sta/Elev= 30
    3780  446.11  3830.7  445.19    3945  438.55  4216.7  429.51  4339.7     429
  4520.4  426.31  4629.2  423.43  4643.9  424.46  4719.8  423.59    4750  421.24
  4780.2  422.33  4819.6  420.18  4844.1     422  4957.4  422.77    4982  422.45
  5009.3  419.85  5012.1  419.35  5015.3  419.85  5022.5  422.72  5031.3  423.68
  5128.1  423.28  5135.4  423.45  5147.1   423.9  5165.6  427.23  5171.1  426.16
    5195  428.43  5359.7  428.79  5415.2  427.99  5526.8  433.23  5631.4  437.21
#Mann= 11 ,-1 , 0
    3780     .05       0  4339.7     .16       0  4520.4     .05       0
  4844.1     .16       0  4957.4     .05       0  5009.3     .03       0
  5015.3     .05       0  5128.1      .1       0  5135.4     .15       0
  5359.7      .1       0  5526.8     .05       0
Bank Sta=5009.3,5015.3
XS Rating Curve= 0 ,0
Exp/Cntr=0.3,0.1

Type RM Length L Ch R = 1 ,5448    ,782,782,782
BEGIN DESCRIPTION:
UNT0157 IN SAND CR 7.0
END DESCRIPTION:
XS GIS Cut Line= 4
      3571742.11     10530291.64      3571820.65     10530849.94
      3571777.25     10531177.63      3571864.06     10531724.54
#Sta/Elev= 30
  4357.4  447.52  4388.1  447.53  4407.9  447.15    4418  444.56  4438.2  435.27
  4448.3  433.76  4478.6  430.76  4535.5  427.43  4640.2  424.05  4842.1  420.88
  4896.7  421.48  4962.7  419.45  4983.4  419.64  4993.5  416.64  5000.6  413.31
  5003.4  412.81  5006.6  413.31  5013.7  417.55  5021.6  420.03  5055.2  420.12
  5124.7  419.98  5178.4  418.31  5245.7  422.77  5318.1  420.17  5375.3  422.63
  5478.6  423.53  5572.3  426.03  5600.1  425.93  5696.8  429.39  5805.5  431.74
#Mann= 6 ,-1 , 0
  4357.4      .1       0  4388.1     .05       0  4962.7     .16       0
  5000.6     .07       0  5006.6     .16       0  5055.2     .05       0
Bank Sta=5000.6,5006.6
XS Rating Curve= 0 ,0
Exp/Cntr=0.3,0.1

Type RM Length L Ch R = 1 ,4666    ,1144,1144,1144
BEGIN DESCRIPTION:
UNT0157 IN SAND CR 6.0
END DESCRIPTION:
XS GIS Cut Line= 2
      3571128.46     10530345.82      3571451.36     10531595.78
#Sta/Elev= 30
  4181.3  427.95  4280.3  424.71    4301  424.32  4321.6  425.01  4331.3  424.06
  4336.4  424.41  4342.2   423.6  4352.6  423.39  4417.7  423.28  4424.9   422.7
  4517.8  420.04  4600.4  418.85  4737.8  418.29  4794.5  417.54  4854.5   418.4
  4916.8  418.34  4971.3  417.64  4982.6  416.18  4992.9  413.77  5000.3  413.05
    5003  412.55  5006.3  413.05    5012  417.39  5017.1  418.74  5023.9  421.24
  5052.5  422.06  5179.7     425  5215.2   426.4  5257.2  426.63  5472.3  428.12
#Mann= 7 ,-1 , 0
  4181.3     .05       0  4794.5     .16       0  4916.8     .05       0
  5000.3     .03       0  5006.3     .05       0  5052.5      .1       0
  5257.2     .05       0
Bank Sta=5000.3,5006.3
XS Rating Curve= 0 ,0
Exp/Cntr=0.3,0.1

Type RM Length L Ch R = 1 ,3522    ,729,729,729
BEGIN DESCRIPTION:
UNT0157 IN SAND CR 5.0
END DESCRIPTION:
XS GIS Cut Line= 5
      3570418.75     10530355.17      3570551.12     10530791.35
       3570618.4     10531095.17      3570835.41     10531624.68
      3571068.46     10531795.15
#Sta/Elev= 30
  4432.4  436.96  4433.1  436.95  4496.1  434.99  4554.1  428.99    4600  428.13
  4638.1  420.94  4658.6  422.35  4679.5  426.95    4690  427.62  4761.7  425.95
  4815.4  423.36  4857.2  419.52  4873.6  419.63    4909  415.71    4963  415.43
  4980.7  414.87  4993.7  412.54  4998.2  410.72  5000.9  410.22  5004.2  410.72
  5021.7  414.94  5079.1   415.1  5148.4  415.93  5260.4  414.62  5336.1  415.89
  5400.9  413.45  5638.7  419.93  5692.2  422.19  5767.3  427.81  6060.4  432.29
#Mann= 8 ,-1 , 0
  4432.4     .16       0  4433.1     .05       0  4761.7     .16       0
    4963      .1       0  4993.7     .16       0  4998.2     .07       0
  5004.2     .16       0  5079.1     .05       0
Bank Sta=4998.2,5004.2
XS Rating Curve= 0 ,0
Exp/Cntr=0.3,0.1

Type RM Length L Ch R = 1 ,2793    ,798,798,798
BEGIN DESCRIPTION:
UNT0157 IN SAND CR 4.0
END DESCRIPTION:
XS GIS Cut Line= 3
      3570075.84      10530930.2      3570282.02     10531296.99
      3570896.84     10531846.86
#Sta/Elev= 30
  4420.9  435.33  4436.1  435.17  4501.1  434.81  4522.8  431.87  4609.5  429.74
  4728.1  423.56  4755.5  420.88  4787.4  421.21  4845.1  417.41  4873.2  413.69
  4914.9   412.9  4943.1   412.6  4986.9  411.24  4998.1  407.07  5000.9  406.57
  5004.1  407.07  5015.3  411.42  5029.5  413.05  5057.1  410.06  5071.4     413
  5093.1  414.28  5262.8   415.1  5291.2  416.24  5326.3  421.89    5348  417.44
  5397.4  417.44  5432.5  425.38  5595.5  425.21  5623.9  429.71  5666.5  430.08
#Mann= 6 ,-1 , 0
  4420.9      .1       0  4436.1     .05       0  4914.9     .16       0
  4943.1     .05       0  4998.1     .03       0  5004.1     .05       0
Bank Sta=4998.1,5004.1
XS Rating Curve= 0 ,0
Exp/Cntr=0.3,0.1

Type RM Length L Ch R = 1 ,1995    ,719,719,719
BEGIN DESCRIPTION:
UNT0157 IN SAND CR 3.0
END DESCRIPTION:
XS GIS Cut Line= 4
       3569730.8     10531004.01      3569995.57     10531733.19
      3570043.31     10531917.65      3570377.28     10532375.23
#Sta/Elev= 30
  4174.1  431.93  4276.6  425.84  4384.4  421.33    4399  419.79  4424.3  415.73
  4454.9  415.36  4516.1  417.47  4541.4  416.54  4577.3  416.56  4602.6  415.14
  4775.6  410.63  4959.8  409.75  4979.3  409.84  4989.6  407.61  4992.3  402.44
  4995.1  401.94  4998.3  402.44  5020.6   410.2  5043.9  410.47  5103.2  411.23
  5170.1  410.46  5299.8  413.34  5364.7  413.65  5414.9  415.03  5435.7  417.48
  5456.6   416.4  5521.5  418.31  5550.8  418.22  5586.4  420.33  5706.9  425.02
#Mann= 5 ,-1 , 0
  4174.1     .05       0  4959.8     .16       0  4992.3     .07       0
  4998.3     .16       0  5043.9     .05       0
Bank Sta=4979.3,5020.6
XS Rating Curve= 0 ,0
Exp/Cntr=0.3,0.1

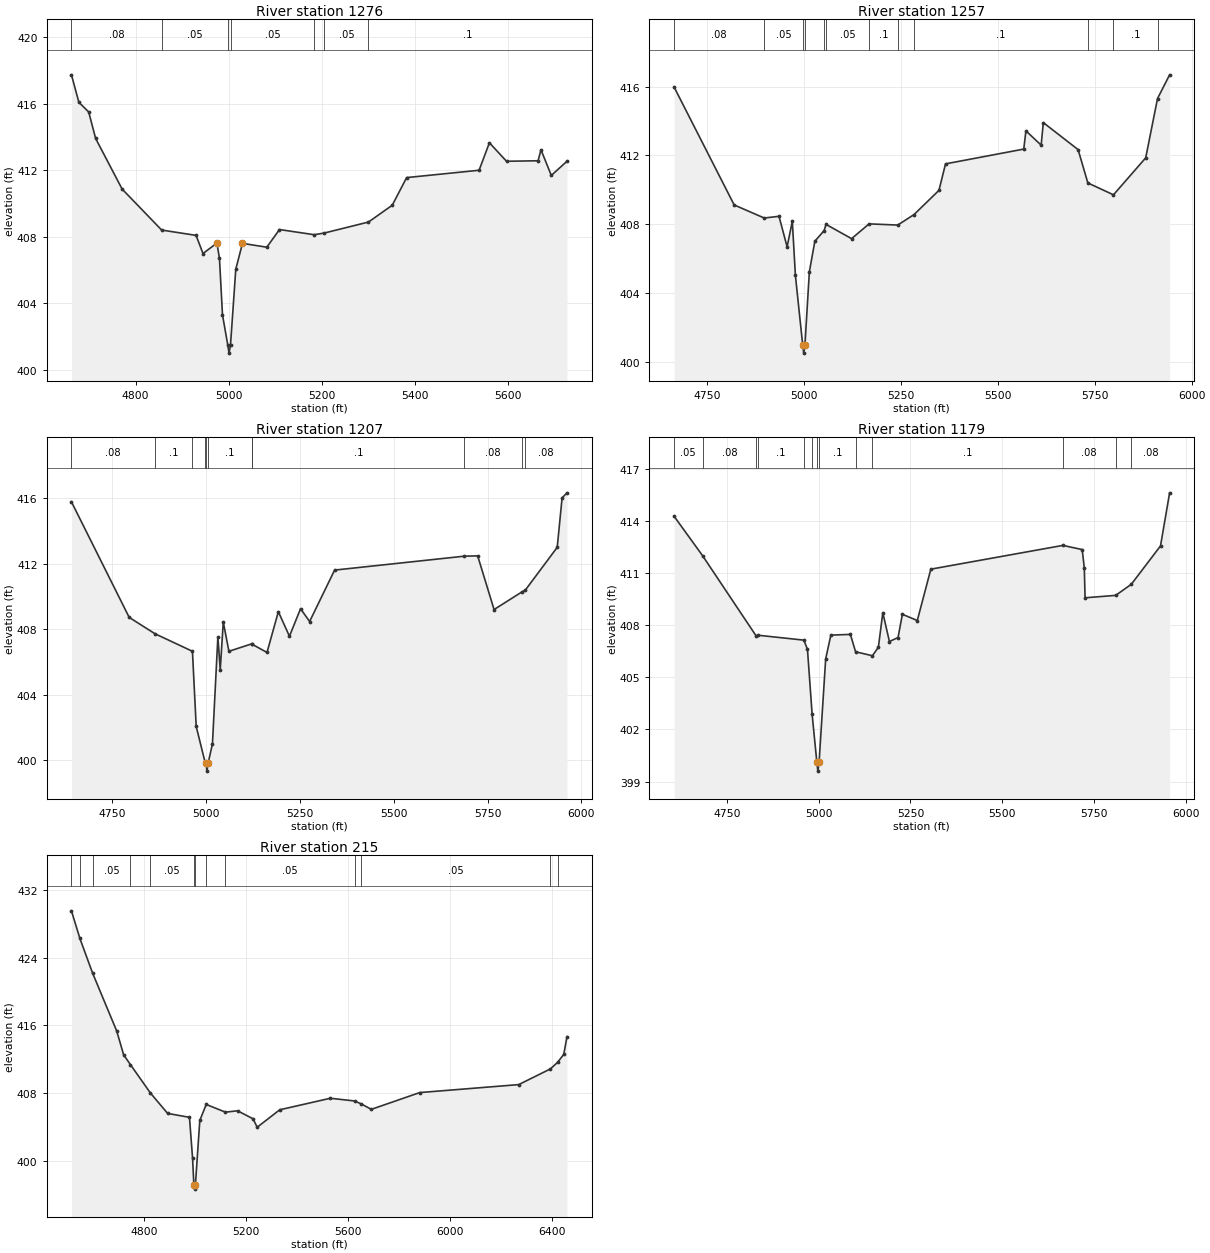
Type RM Length L Ch R = 1 ,1276    ,19,19,19
BEGIN DESCRIPTION:
UNT0157 IN SAND CR 2.3
END DESCRIPTION:
XS GIS Cut Line= 5
      3569337.44     10531384.38      3569509.32      10531639.6
      3569562.71     10531683.87      3569721.56     10531953.41
      3569884.34     10532291.98
#Sta/Elev= 30
    4662  417.73    4678  416.08  4699.1   415.5    4714  413.91    4771  410.87
    4856  408.41    4930  408.09  4944.9     407  4974.8  407.63  4980.3  406.71
  4986.8  403.32  4998.1  401.52  5000.9  401.02  5004.1  401.52  5015.4  406.06
  5029.8  407.61  5082.1  407.38  5109.4  408.44  5184.1  408.13  5205.6  408.23
  5300.7  408.89  5351.9   409.9  5382.8  411.56  5538.6     412  5560.8  413.65
  5597.6  412.54  5665.5  412.57  5671.7  413.23  5693.9  411.69  5727.6  412.54
#Mann= 7 ,-1 , 0
    4662     .08       0    4856     .05       0  4998.1    .035       0
  5004.1     .05       0  5184.1      .1       0  5205.6     .05       0
  5300.7      .1       0
Bank Sta=4974.8,5029.8
XS Rating Curve= 0 ,0
Exp/Cntr=0.3,0.1

Type RM Length L Ch R = 1 ,1257    ,50,50,50
BEGIN DESCRIPTION:
UNT0157 IN SAND CR 2.1
END DESCRIPTION:
XS GIS Cut Line= 6
       3569319.8     10531396.75      3569496.17     10531645.68
      3569549.56     10531705.58      3569695.39     10531958.18
      3569869.87     10532311.04      3570046.53     10532421.15
#Sta/Elev= 30
  4664.3  415.97  4819.4  409.11    4897  408.35  4935.1  408.45    4956  406.67
  4969.4  408.16  4977.4  405.01  4996.1  400.99  4998.9  400.49  5002.1  400.99
  5013.4  405.22  5027.6     407  5051.6  407.62  5056.4  407.98  5122.4  407.15
  5167.5  408.01  5241.5  407.94  5283.5  408.55  5347.9  409.96  5364.8   411.5
  5566.7  412.36  5572.3  413.42  5611.6  412.59  5617.2   413.9  5706.9  412.33
  5732.1  410.39  5798.2   409.7  5881.4  411.85  5911.9   415.3  5943.1  416.68
#Mann= 12 ,-1 , 0
  4664.3     .08       0    4897     .05       0  4996.1    .035       0
  5002.1     .05       0  5051.6      .1       0  5056.4     .05       0
  5167.5      .1       0  5241.5     .05       0  5283.5      .1       0
  5732.1     .08       0  5798.2      .1       0  5911.9     .08       0
Bank Sta=4996.1,5002.1
XS Rating Curve= 0 ,0
Exp/Cntr=0.3,0.1

Type RM Length L Ch R = 1 ,1207    ,28,28,28
BEGIN DESCRIPTION:
UNT0157 IN SAND CR 2.0
END DESCRIPTION:
XS GIS Cut Line= 6
      3569267.78     10531421.32      3569452.09     10531681.37
      3569522.62     10531736.71      3569614.85     10531966.74
      3569837.14     10532355.05      3570024.46     10532465.46
#Sta/Elev= 30
  4640.6  415.78  4794.6  408.72  4863.5  407.72  4963.2  406.65  4973.2  402.06
    4997  399.86  4999.1  399.83  5001.8  399.33  5005.1  399.83  5016.5  400.99
    5031  407.53  5037.3  405.53  5045.4  408.44  5060.4  406.65  5120.7   407.1
    5123  407.07    5162  406.58  5192.2  409.07  5221.8  407.57  5251.4  409.25
  5275.6  408.47  5342.2  411.61  5687.9  412.46  5723.6  412.48  5767.3   409.2
  5841.8  410.28  5850.4  410.38  5935.7     413  5948.7  416.02  5961.7  416.33
#Mann= 11 ,-1 , 0
  4640.6     .08       0  4863.5      .1       0  4963.2     .05       0
    4997      .1       0  4999.1     .07       0  5005.1      .1       0
  5120.7     .05       0    5123      .1       0  5687.9     .08       0
  5841.8      .1       0  5850.4     .08       0
Bank Sta=4999.1,5005.1
XS Rating Curve= 0 ,0
Exp/Cntr=0.3,0.1

Type RM Length L Ch R = 1 ,1179    ,964,964,964
BEGIN DESCRIPTION:
UNT0157 IN SAND CR 2.2
END DESCRIPTION:
XS GIS Cut Line= 6
      3569217.26     10531425.79       3569432.5      10531699.5
      3569513.23     10531767.21      3569600.47     10531969.03
      3569819.22     10532359.66      3570004.89     10532492.78
#Sta/Elev= 30
  4606.1  414.29  4683.6  412.02  4829.7  407.39  4835.9  407.43  4959.5  407.15
  4969.4  406.62  4982.1  402.87    4995   400.1  4997.7   399.6    5001   400.1
    5019  406.07  5033.1  407.44  5086.3  407.48  5100.4  406.48  5146.3  406.25
  5162.5  406.74  5174.6  408.73  5192.6  407.07  5216.1   407.3  5227.9  408.64
  5268.5  408.28  5305.4  411.24    5665  412.61  5717.6  412.37  5723.3  411.33
  5725.5  409.59  5808.9  409.73  5851.4  410.37  5930.9  412.58  5955.7  415.64
#Mann= 13 ,-1 , 0
  4606.1     .05       0  4683.6     .08       0  4829.7     .05       0
  4835.9      .1       0  4959.5     .05       0  4982.1      .1       0
    4995     .07       0    5001      .1       0  5100.4     .05       0
  5146.3      .1       0    5665     .08       0  5808.9     .05       0
  5851.4     .08       0
Bank Sta=4995,5001
XS Rating Curve= 0 ,0
Exp/Cntr=0.3,0.1

Type RM Length L Ch R = 1 ,215     ,0,0,0
BEGIN DESCRIPTION:
UNT0157 IN SAND CR 1.0
END DESCRIPTION:
XS GIS Cut Line= 5
      3569192.96     10531228.75      3568991.57      10531548.2
      3568956.85     10531770.42      3569172.13     10532180.14
      3569977.37     10532522.02
#Sta/Elev= 30
    4517  429.51  4550.1  426.25  4600.1  422.14  4694.3  415.33  4721.4  412.52
  4747.9  411.37  4826.5  408.01  4893.7  405.61  4979.1  405.15  4991.3  400.32
  4996.3  397.18  4999.1  396.68  5002.3  397.18  5019.6  404.78  5044.7  406.67
  5120.1  405.76  5167.4  405.92  5227.9  404.98  5244.3  403.98  5332.5  406.04
  5530.9   407.4  5625.6  407.08  5652.6  406.72    5691  406.09  5880.8  408.07
  6268.3  409.01  6392.2  410.86  6420.3  411.63  6444.7  412.58  6457.2  414.66
#Mann= 13 ,-1 , 0
    4517     .05       0  4550.1      .1       0  4600.1     .05       0
  4747.9      .1       0  4826.5     .05       0  4996.3     .03       0
  5002.3     .05       0  5044.7     .16       0  5120.1     .05       0
  5625.6     .16       0  5652.6     .05       0  6392.2     .08       0
  6420.3     .05       0
Bank Sta=4996.3,5002.3
XS Rating Curve= 0 ,0
Exp/Cntr=0.3,0.1

Chan Stop Cuts=-1
Use User Specified Reach Order=0
Composite Channel Slope=5