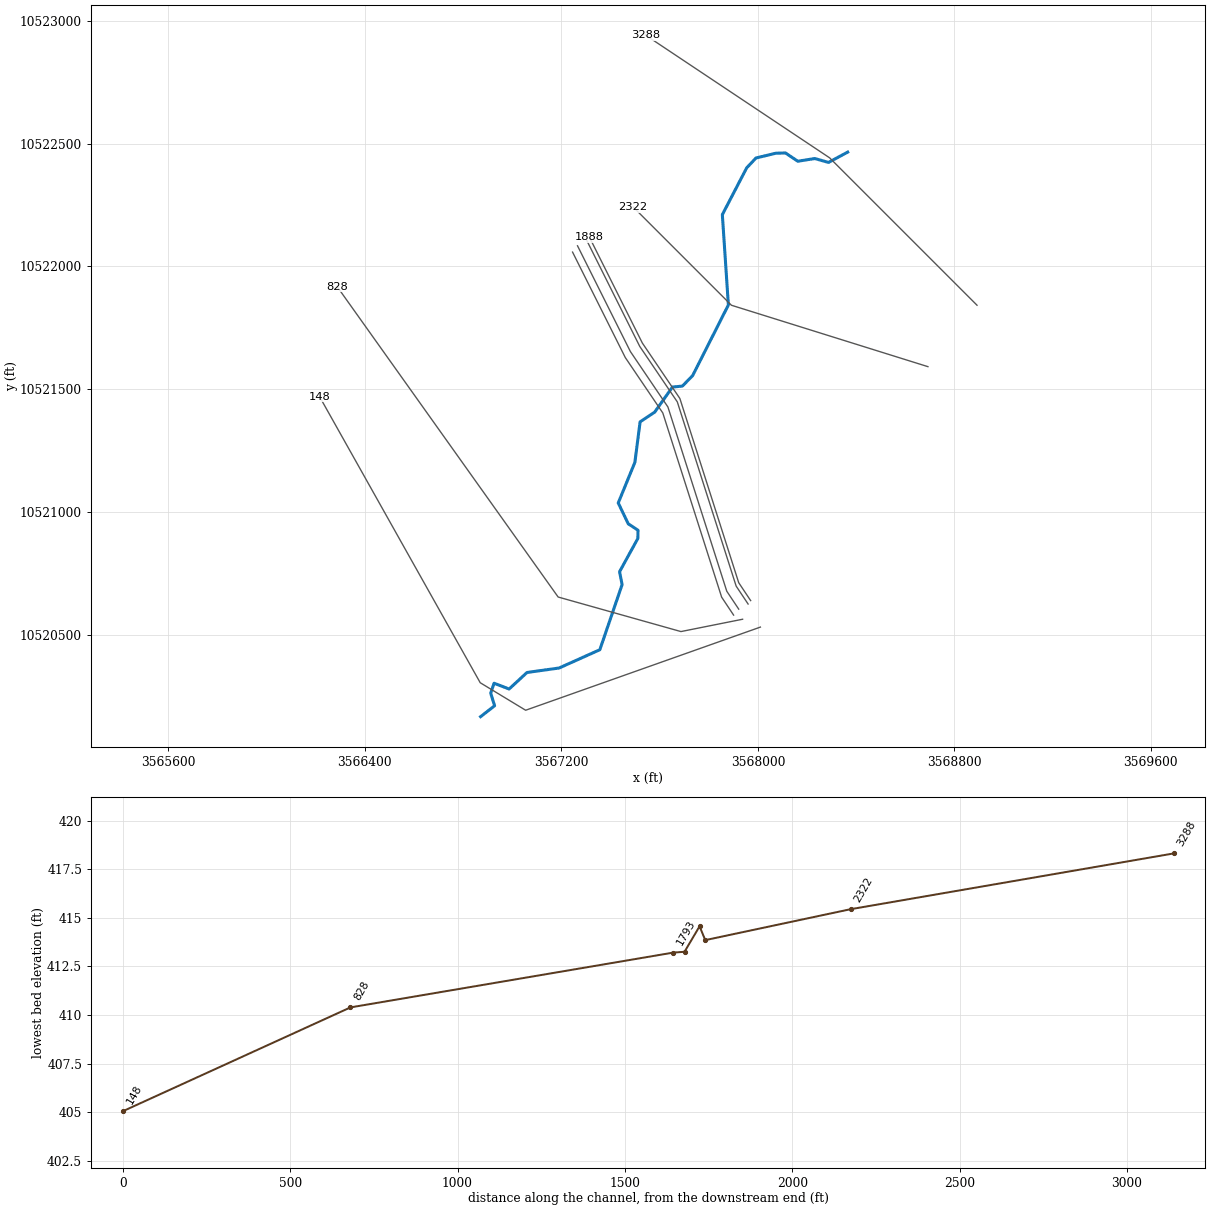
--- UNT0161 IN SAND CR.prj (project) ---

Proj Title=UNT0161 IN SAND CR Base Level Engineering
Current Plan=p01
Default Exp/Contr=0.3,0.1
English Units
Geom File=g01
Flow File=f01
Plan File=p01
BEGIN DESCRIPTION:
UNT0161 IN SAND CR
END DESCRIPTION:

--- UNT0161 IN SAND CR.p01 (plan) ---

Plan Title=Multiple Run
Short Identifier=Multiple
Geom File=g01
Flow File=f01
Subcritical Flow
K Sum by GR= 0
Std Step Tol= 0.01
Critical Tol= 0.01
Num of Std Step Trials= 20
Max Error Tol= 0.3
Flow Tol Ratio= 0.001
Split Flow NTrial= 30
Split Flow Tol= 0.02
Split Flow Ratio= 0.02
Log Output Level= 0
Friction Slope Method= 1
Unsteady Friction Slope Method= 2
Unsteady Bridges Friction Slope Method= 1
Parabolic Critical Depth
Global Vel Dist=  1 , 1 , 1
Global Log Level= 0
CheckData=True
Encroach Param= -1, 0, 0, 0
BEGIN DESCRIPTION:
Multiple Run
END DESCRIPTION:

--- UNT0161 IN SAND CR.f01 (steady flow) ---

Flow Title=Multiple
Number of Profiles=7
Profile Names=10-year,25-year,50-year,1pct_min,100-year,1pct_plu,500-year
River Rch & RM= UNT0161 IN SAND ,Reach-1,3288
    1139    1574    1935    1736    2347    3174    3442
Boundary for River Rch & Prof#=UNT0161 IN SAND ,Reach-1,1
Up Type=0
Dn Type=3
Dn Slope=0.005
Boundary for River Rch & Prof#=UNT0161 IN SAND ,Reach-1,2
Up Type=0
Dn Type=3
Dn Slope=0.005
Boundary for River Rch & Prof#=UNT0161 IN SAND ,Reach-1,3
Up Type=0
Dn Type=3
Dn Slope=0.005
Boundary for River Rch & Prof#=UNT0161 IN SAND ,Reach-1,4
Up Type=0
Dn Type=3
Dn Slope=0.005
Boundary for River Rch & Prof#=UNT0161 IN SAND ,Reach-1,5
Up Type=0
Dn Type=3
Dn Slope=0.005
Boundary for River Rch & Prof#=UNT0161 IN SAND ,Reach-1,6
Up Type=0
Dn Type=3
Dn Slope=0.005
Boundary for River Rch & Prof#=UNT0161 IN SAND ,Reach-1,7
Up Type=0
Dn Type=3
Dn Slope=0.005

--- UNT0161 IN SAND CR.g01 (geometry) ---

Geom Title=Existing Conditions

River Reach=UNT0161 IN SAND ,Reach-1
Reach XY= 30
      3568365.54     10522465.09      3568287.14     10522422.97
      3568232.08     10522438.92      3568162.27     10522427.98
      3568112.11     10522461.64      3568072.99     10522460.56
      3567992.15     10522441.16      3567954.24     10522400.94
      3567855.11     10522210.38      3567879.77     10521842.78
      3567734.20     10521555.11      3567692.57     10521512.52
      3567652.16     10521508.64      3567579.76     10521406.55
      3567520.39     10521366.97      3567499.04     10521201.86
      3567431.35     10521036.69      3567472.09     10520951.86
      3567511.78     10520925.65      3567511.26     10520892.32
      3567436.78     10520756.90      3567447.07     10520704.23
      3567356.46     10520439.16      3567190.81     10520364.77
      3567059.94     10520346.53      3566987.03     10520279.17
      3566925.92     10520302.79      3566912.03     10520262.51
      3566928.00     10520211.12      3566871.06     10520166.67

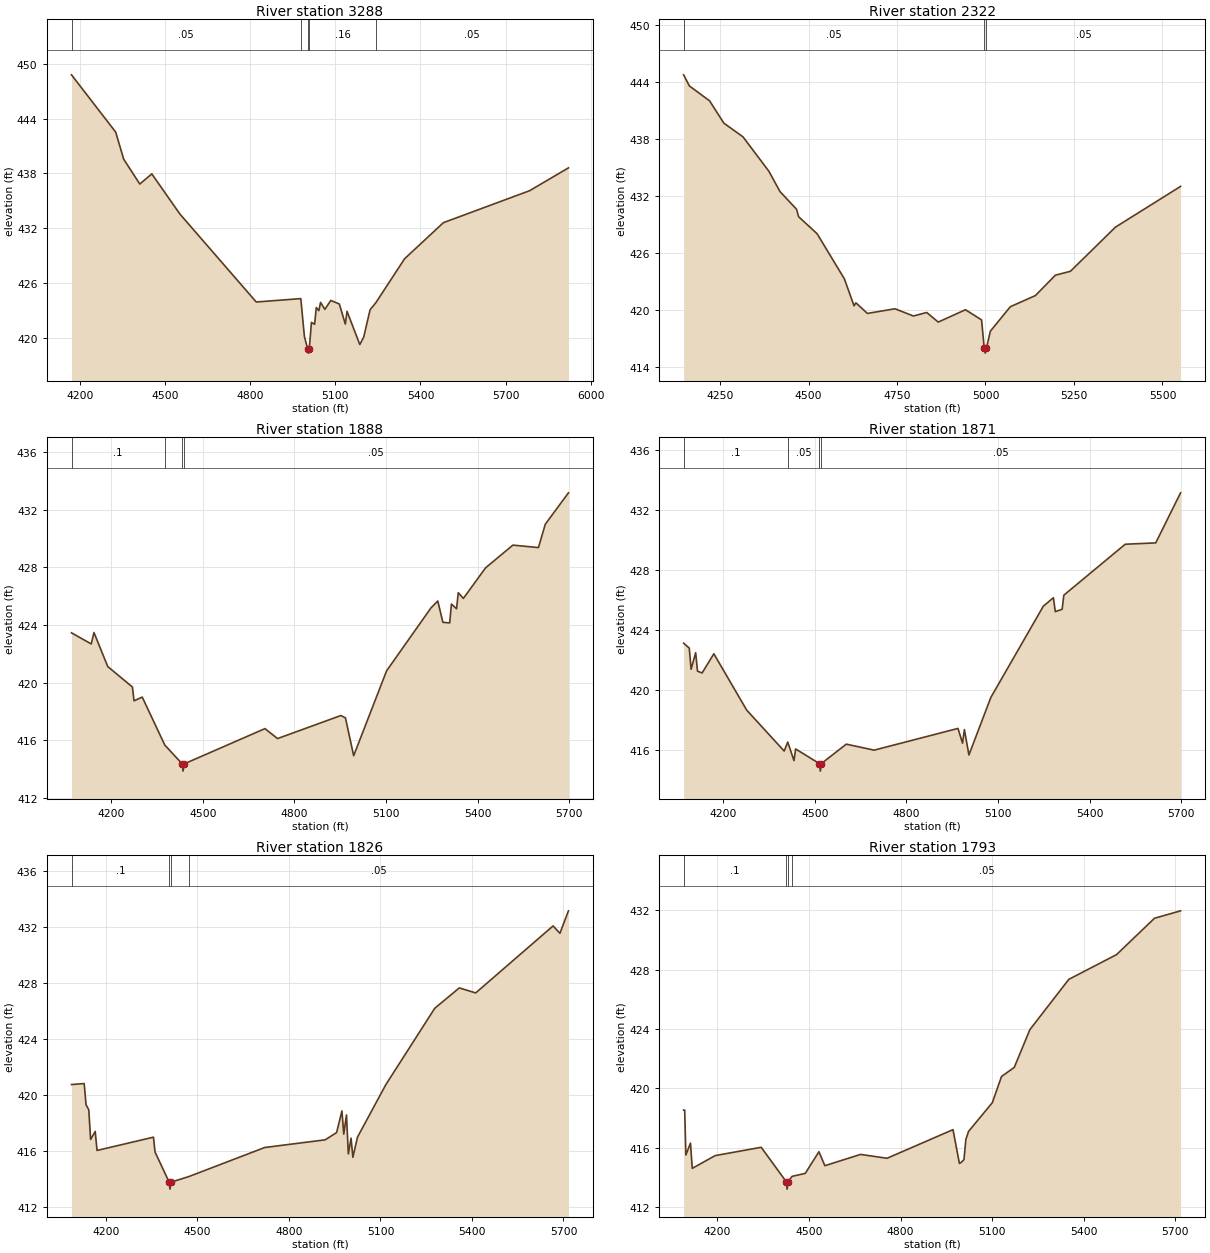
Type RM Length L Ch R = 1,3288,966,966,966
BEGIN DESCRIPTION:
UNT0161 IN SAND CR 5.0
END DESCRIPTION:
XS GIS Cut Line= 3
      3568892.07     10521841.68      3568292.11     10522441.64
      3567542.08     10522941.66
#Sta/Elev= 30
  4171.3  448.79  4326.8  442.52  4355.1  439.55  4411.7  436.83  4454.1  437.94
  4553.1  433.54  4821.8  423.91  4978.7  424.28  4991.5  420.11  5002.6  418.81
  5005.4  418.31  5008.6  418.81  5016.2  421.68  5027.3  421.47  5033.3  423.30
  5042.3  422.96  5048.3  423.87  5063.3  423.10  5084.4  424.08  5114.4  423.69
  5135.5  421.49  5141.5  422.89  5186.5  419.25  5200.1  420.06  5222.6  423.05
  5243.1  423.84  5344.3  428.65  5481.0  432.60  5784.5  436.10  5921.2  438.60
#Mann=5,-1,0
  4171.3    0.05       0  4978.7    0.16       0  5002.6    0.07       0
  5008.6    0.16       0  5243.1    0.05       0
Bank Sta=5002.6,5008.6
Exp/Cntr=0.3,0.1

Type RM Length L Ch R = 1,2322,434,434,434
BEGIN DESCRIPTION:
UNT0161 IN SAND CR 3.0
END DESCRIPTION:
XS GIS Cut Line= 3
      3568692.14     10521591.63      3567892.11     10521841.64
      3567492.09     10522241.66
#Sta/Elev= 30
  4147.2  444.75  4163.5  443.58  4220.6  442.01  4260.9  439.66  4314.9  438.22
  4388.2  434.59  4419.6  432.45  4466.3  430.59  4472.0  429.81  4524.4  428.01
  4601.4  423.26  4628.7  420.42  4633.9  420.74  4666.4  419.62  4744.4  420.11
  4796.3  419.35  4834.0  419.72  4866.5  418.71  4943.5  420.01  4988.9  418.94
  4996.5  415.94  4999.3  415.44  5002.5  415.94  5013.7  417.75  5070.2  420.33
  5141.0  421.50  5197.5  423.65  5240.0  424.06  5367.2  428.71  5551.1  433.00
#Mann=3,-1,0
  4147.2    0.05       0  4996.5    0.03       0  5002.5    0.05       0
Bank Sta=4996.5,5002.5
Exp/Cntr=0.3,0.1

Type RM Length L Ch R = 1,1888,17,17,17
BEGIN DESCRIPTION:
UNT0161 IN SAND CR 2.3
END DESCRIPTION:
XS GIS Cut Line= 5
      3567970.43     10520639.18      3567921.81     10520712.10
      3567682.23     10521462.10      3567529.45     10521687.80
      3567314.62     10522117.46
#Sta/Elev= 30
  4070.0  423.45  4134.6  422.68  4143.6  423.47  4188.7  421.11  4269.5  419.69
  4274.8  418.73  4301.7  418.99  4375.6  415.66  4432.7  414.35  4435.4  413.85
  4438.7  414.35  4703.6  416.80  4745.0  416.11  4952.3  417.71  4967.3  417.55
  4994.3  414.92  5102.1  420.81  5247.5  425.18  5269.8  425.66  5286.6  424.18
  5308.9  424.14  5314.5  425.45  5331.3  425.12  5336.9  426.24  5353.7  425.84
  5426.3  427.96  5515.8  429.54  5599.6  429.37  5622.0  430.99  5697.9  433.17
#Mann=4,-1,0
  4070.0     0.1       0  4375.6    0.05       0  4432.7    0.03       0
  4438.7    0.05       0
Bank Sta=4432.7,4438.7
Exp/Cntr=0.3,0.1

Type RM Length L Ch R = 1,1871,45,45,45
BEGIN DESCRIPTION:
UNT0161 IN SAND CR 2.2
END DESCRIPTION:
XS GIS Cut Line= 5
      3567960.03     10520625.26      3567911.39     10520698.22
      3567671.81     10521448.22      3567519.03     10521673.91
      3567303.77     10522104.44
#Sta/Elev= 30
  4069.5  423.10  4088.0  422.77  4094.0  421.36  4109.0  422.46  4115.0  421.23
  4130.1  421.11  4168.6  422.39  4276.3  418.63  4399.1  415.90  4410.8  416.50
  4431.3  415.26  4436.6  416.04  4514.7  415.06  4517.5  414.56  4520.7  415.06
  4602.7  416.36  4694.0  415.96  4968.8  417.41  4983.7  416.43  4989.8  417.33
  5004.7  415.64  5076.6  419.48  5248.7  425.57  5281.6  426.13  5287.8  425.20
  5310.2  425.36  5315.8  426.30  5517.0  429.70  5617.0  429.79  5698.4  433.13
#Mann=4,-1,0
  4069.5     0.1       0  4410.8    0.05       0  4514.7    0.03       0
  4520.7    0.05       0
Bank Sta=4514.7,4520.7
Exp/Cntr=0.3,0.1

Type RM Length L Ch R = 1,1826,33,33,33
BEGIN DESCRIPTION:
UNT0161 IN SAND CR 2.0
END DESCRIPTION:
XS GIS Cut Line= 5
      3567921.81     10520604.47      3567873.20     10520677.38
      3567633.62     10521427.38      3567480.84     10521653.08
      3567265.55     10522083.65
#Sta/Elev= 30
  4087.4  420.74  4129.0  420.81  4135.0  419.30  4144.0  418.93  4150.0  416.81
  4165.1  417.38  4171.1  416.02  4356.0  416.97  4361.3  415.90  4407.5  413.75
  4410.2  413.25  4413.5  413.75  4472.1  414.15  4720.5  416.23  4918.8  416.78
  4956.3  417.30  4973.8  418.85  4979.8  417.19  4988.7  418.56  4994.8  415.77
  5003.7  416.90  5009.7  415.53  5024.7  416.97  5117.6  420.73  5278.0  426.20
  5358.5  427.66  5412.2  427.30  5665.9  432.10  5688.3  431.57  5716.3  433.18
#Mann=4,-1,0
  4087.4     0.1       0  4407.5    0.03       0  4413.5     0.1       0
  4472.1    0.05       0
Bank Sta=4407.5,4413.5
Exp/Cntr=0.3,0.1

Type RM Length L Ch R = 1,1793,965,965,965
BEGIN DESCRIPTION:
UNT0161 IN SAND CR 2.1
END DESCRIPTION:
XS GIS Cut Line= 5
      3567900.98     10520580.16      3567852.37     10520653.08
      3567612.78     10521403.08      3567460.00     10521628.77
      3567245.39     10522057.99
#Sta/Elev= 30
  4089.6  418.54  4093.1  418.54  4097.0  415.51  4112.0  416.31  4118.0  414.61
  4193.0  415.47  4343.7  416.03  4425.7  413.71  4428.5  413.21  4431.7  413.71
  4444.8  414.07  4487.9  414.27  4532.7  415.73  4552.2  414.79  4669.1  415.55
  4755.8  415.29  4971.8  417.22  4992.8  414.94  4999.1  415.02  5007.7  415.20
  5013.8  416.55  5022.7  417.10  5100.6  419.04  5130.6  420.80  5172.5  421.42
  5223.5  423.96  5351.0  427.35  5507.5  429.02  5631.6  431.47  5717.0  431.97
#Mann=4,-1,0
  4089.6     0.1       0  4425.7    0.03       0  4431.7     0.1       0
  4444.8    0.05       0
Bank Sta=4425.7,4431.7
Exp/Cntr=0.3,0.1

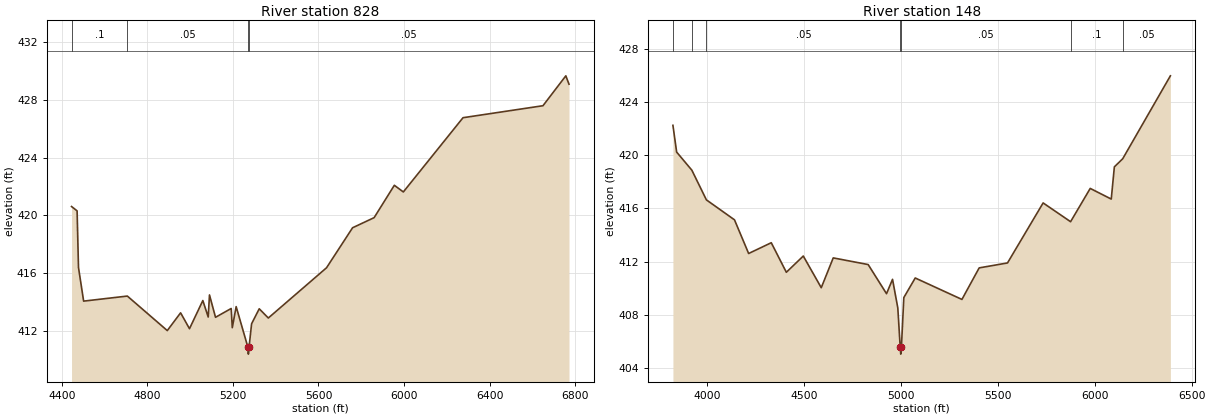
Type RM Length L Ch R = 1,828,680,680,680
BEGIN DESCRIPTION:
UNT0161 IN SAND CR 1.0
END DESCRIPTION:
XS GIS Cut Line= 4
      3567937.64     10520563.29      3567686.67     10520513.10
      3567186.67     10520653.72      3566287.34     10521916.95
#Sta/Elev= 30
  4445.3  420.61  4471.3  420.31  4477.8  416.39  4501.9  414.06  4706.2  414.41
  4893.0  412.02  4955.3  413.25  4996.8  412.15  5059.2  414.10  5084.4  412.96
  5090.3  414.49  5118.5  412.94  5191.8  413.55  5196.9  412.22  5215.0  413.68
  5269.5  410.89  5272.2  410.39  5275.5  410.89  5287.2  412.49  5322.9  413.53
  5365.4  412.89  5637.6  416.37  5759.4  419.14  5860.2  419.84  5954.6  422.08
  5996.7  421.62  6275.8  426.76  6649.6  427.59  6756.5  429.66  6771.3  429.08
#Mann=4,-1,0
  4445.3     0.1       0  4706.2    0.05       0  5269.5    0.03       0
  5275.5    0.05       0
Bank Sta=5269.5,5275.5
Exp/Cntr=0.3,0.1

Type RM Length L Ch R = 1,148,0,0,0
BEGIN DESCRIPTION:
UNT0161 IN SAND CR 1.01
END DESCRIPTION:
XS GIS Cut Line= 4
      3568010.07     10520531.32      3567054.37     10520192.79
      3566869.47     10520304.77      3566215.81     10521468.85
#Sta/Elev= 30
  3825.2  422.24  3844.4  420.23  3922.8  418.87  3997.8  416.64  4142.7  415.14
  4215.6  412.61  4332.3  413.42  4410.0  411.20  4497.4  412.42  4590.1  410.04
  4651.8  412.28  4831.9  411.78  4926.6  409.59  4957.6  410.67  4984.8  408.52
  4997.3  405.55  5000.0  405.05  5003.3  405.55  5015.8  409.30  5074.6  410.77
  5315.4  409.16  5404.4  411.53  5550.4  411.90  5734.1  416.41  5875.7  415.00
  5977.0  417.50  6085.4  416.70  6101.4  419.12  6144.5  419.73  6390.3  425.96
#Mann=7,-1,0
  3825.2    0.05       0  3922.8     0.1       0  3997.8    0.05       0
  4997.3    0.03       0  5003.3    0.05       0  5875.7     0.1       0
  6144.5    0.05       0
Bank Sta=4997.3,5003.3
Exp/Cntr=0.3,0.1

Chan Stop Cuts=-1