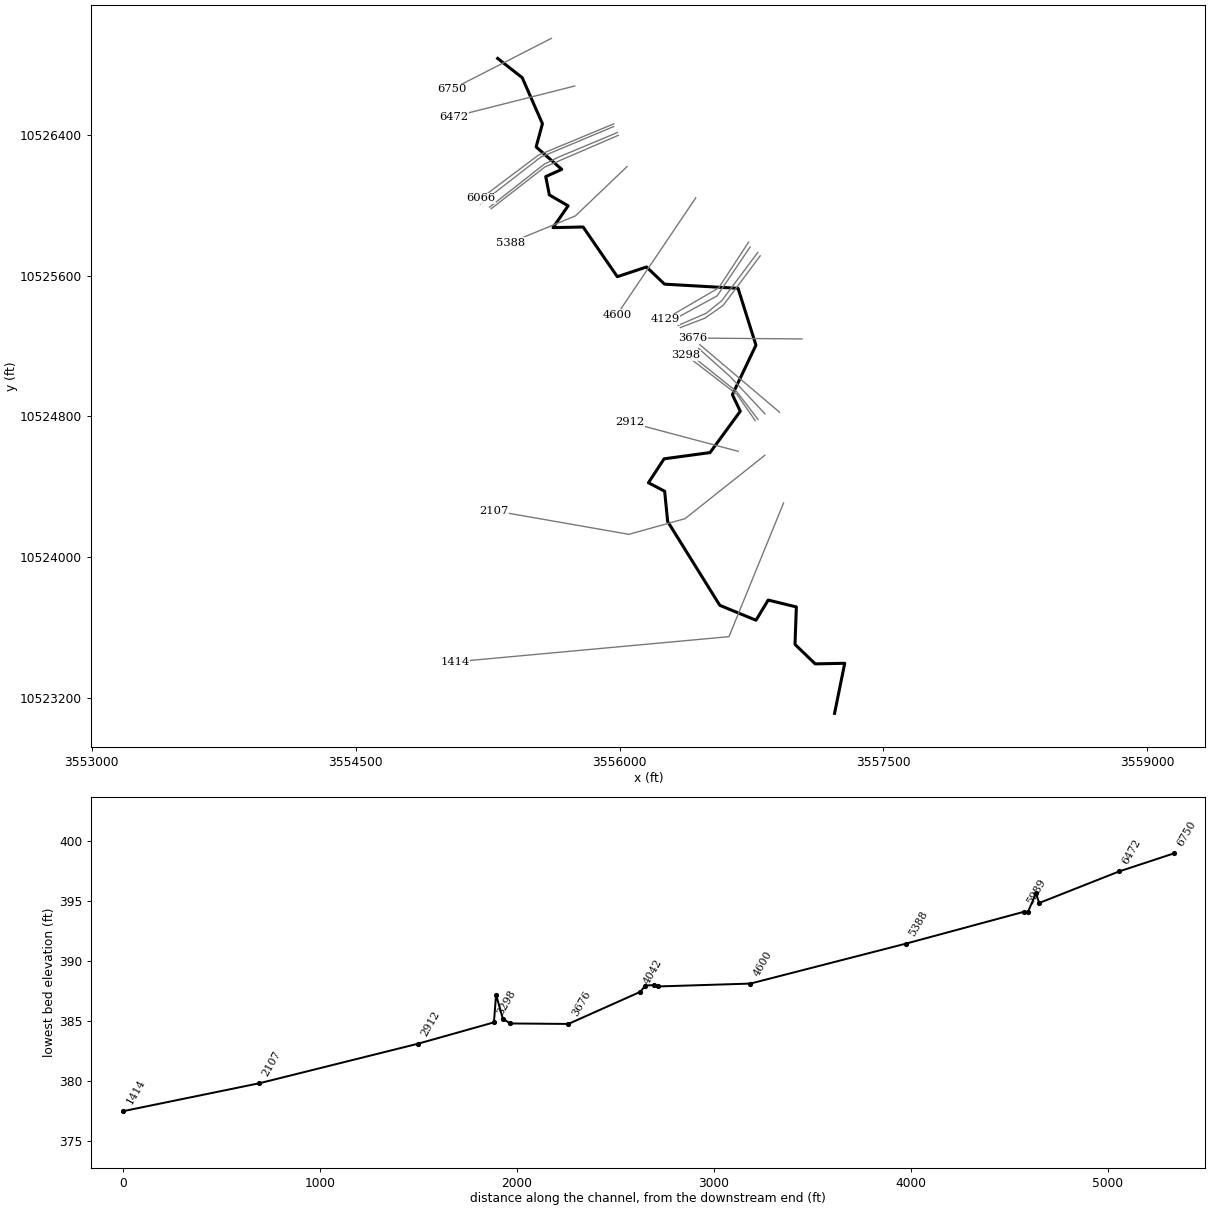
--- UNT0162 IN SAND CR.prj (project) ---

Proj Title=UNT0162 IN SAND CR Base Level Engineering
Current Plan=p01
Default Exp/Contr=0.3,0.1
English Units
Geom File=g01
Flow File=f01
Plan File=p01
BEGIN DESCRIPTION:
UNT0162 IN SAND CR
END DESCRIPTION:

--- UNT0162 IN SAND CR.p01 (plan) ---

Plan Title=Multiple Run
Short Identifier=Multiple
Geom File=g01
Flow File=f01
Subcritical Flow
K Sum by GR= 0
Std Step Tol= 0.01
Critical Tol= 0.01
Num of Std Step Trials= 20
Max Error Tol= 0.3
Flow Tol Ratio= 0.001
Split Flow NTrial= 30
Split Flow Tol= 0.02
Split Flow Ratio= 0.02
Log Output Level= 0
Friction Slope Method= 1
Unsteady Friction Slope Method= 2
Unsteady Bridges Friction Slope Method= 1
Parabolic Critical Depth
Global Vel Dist=  1 , 1 , 1
Global Log Level= 0
CheckData=True
Encroach Param= -1, 0, 0, 0
BEGIN DESCRIPTION:
Multiple Run
END DESCRIPTION:

--- UNT0162 IN SAND CR.f01 (steady flow) ---

Flow Title=Multiple
Number of Profiles=7
Profile Names=10-year,25-year,50-year,1pct_min,100-year,1pct_plu,500-year
River Rch & RM= UNT0162 IN SAND ,Reach-1,6750
     928    1259    1529    1354    1831    2476    2617
River Rch & RM= UNT0162 IN SAND ,Reach-1,3676
    1128    1547    1891    1684    2278    3081    3298
Boundary for River Rch & Prof#=UNT0162 IN SAND ,Reach-1,1
Up Type=0
Dn Type=3
Dn Slope=0.005
Boundary for River Rch & Prof#=UNT0162 IN SAND ,Reach-1,2
Up Type=0
Dn Type=3
Dn Slope=0.005
Boundary for River Rch & Prof#=UNT0162 IN SAND ,Reach-1,3
Up Type=0
Dn Type=3
Dn Slope=0.005
Boundary for River Rch & Prof#=UNT0162 IN SAND ,Reach-1,4
Up Type=0
Dn Type=3
Dn Slope=0.005
Boundary for River Rch & Prof#=UNT0162 IN SAND ,Reach-1,5
Up Type=0
Dn Type=3
Dn Slope=0.005
Boundary for River Rch & Prof#=UNT0162 IN SAND ,Reach-1,6
Up Type=0
Dn Type=3
Dn Slope=0.005
Boundary for River Rch & Prof#=UNT0162 IN SAND ,Reach-1,7
Up Type=0
Dn Type=3
Dn Slope=0.005

--- UNT0162 IN SAND CR.g01 (geometry) ---

Geom Title=Existing Conditions

River Reach=UNT0162 IN SAND ,Reach-1
Reach XY= 30
      3555307.60     10526833.93      3555446.99     10526724.56
      3555561.95     10526462.78      3555526.01     10526331.01
      3555671.85     10526203.41      3555580.70     10526162.26
      3555601.27     10526058.09      3555707.83     10525996.16
      3555622.05     10525872.27      3555793.04     10525875.94
      3555987.55     10525593.46      3556153.53     10525648.57
      3556255.79     10525551.05      3556673.67     10525527.28
      3556775.40     10525204.22      3556641.54     10524922.97
      3556686.33     10524828.70      3556514.46     10524593.80
      3556253.44     10524558.38      3556164.32     10524422.46
      3556256.55     10524374.04      3556273.59     10524202.25
      3556569.84     10523725.78      3556775.77     10523640.93
      3556844.97     10523755.64      3557005.01     10523716.55
      3556997.37     10523503.51      3557112.15     10523392.93
      3557279.92     10523396.26      3557222.11     10523111.64

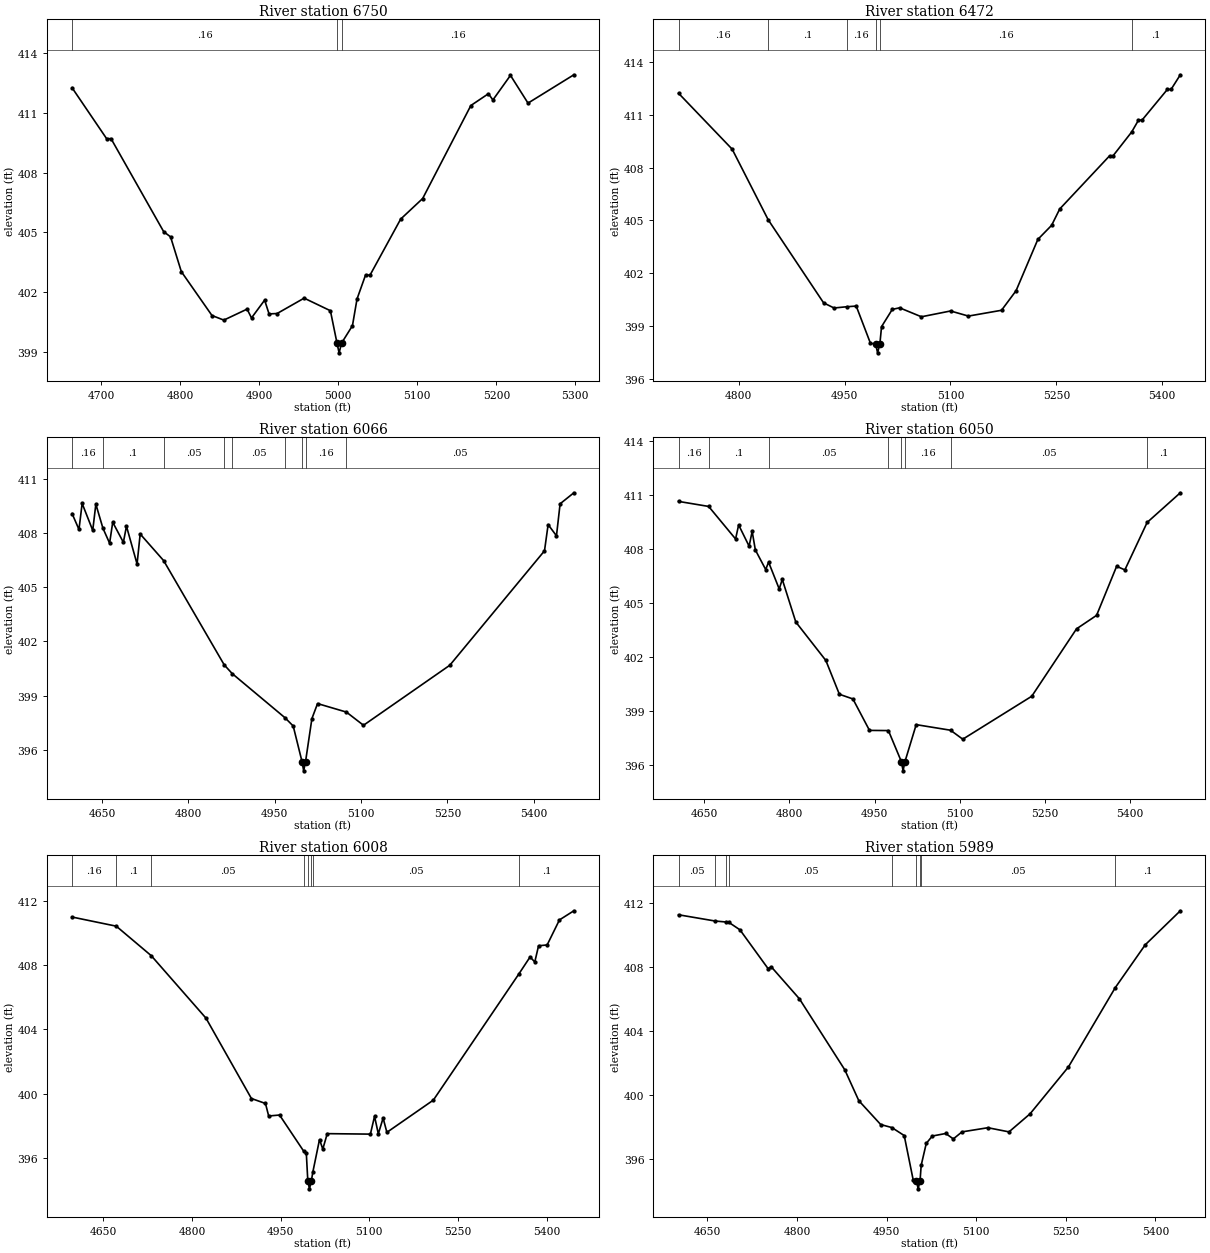
Type RM Length L Ch R = 1,6750,278,278,278
BEGIN DESCRIPTION:
UNT0162 IN SAND CR 10.0
END DESCRIPTION:
XS GIS Cut Line= 2
      3555613.02     10526948.07      3555047.87     10526658.98
#Sta/Elev= 30
  4663.3  412.25  4707.0  409.70  4712.6  409.70  4779.2  405.04  4787.9  404.78
  4801.5  403.04  4840.3  400.84  4855.3  400.61  4884.7  401.16  4890.3  400.72
  4906.9  401.61  4912.5  400.92  4922.7  400.94  4956.9  401.71  4990.1  401.08
  4998.4  399.47  5001.1  398.97  5004.4  399.47  5018.0  400.33  5023.8  401.67
  5034.6  402.87  5040.2  402.86  5079.0  405.67  5106.8  406.70  5167.8  411.36
  5190.0  411.95  5195.7  411.64  5217.9  412.87  5240.1  411.48  5298.1  412.90
#Mann=3,-1,0
  4663.3    0.16       0  4998.4    0.07       0  5004.4    0.16       0
Bank Sta=4998.4,5004.4
Exp/Cntr=0.3,0.1

Type RM Length L Ch R = 1,6472,406,406,406
BEGIN DESCRIPTION:
UNT0162 IN SAND CR 10.1
END DESCRIPTION:
XS GIS Cut Line= 2
      3555745.81     10526677.22      3555056.40     10526502.92
#Sta/Elev= 30
  4714.6  412.23  4790.6  409.05  4841.6  405.04  4920.2  400.31  4935.0  400.02
  4952.9  400.09  4966.4  400.13  4986.6  398.01  4993.9  397.97  4996.7  397.47
  4999.9  397.97  5002.3  398.96  5017.5  399.94  5027.9  400.03  5058.8  399.52
  5100.1  399.85  5125.4  399.56  5172.3  399.89  5192.9  401.00  5223.8  403.92
  5243.3  404.72  5254.8  405.65  5325.4  408.67  5330.5  408.68  5356.8  410.03
  5366.4  410.70  5371.6  410.71  5407.4  412.45  5412.6  412.45  5425.7  413.28
#Mann=6,-1,0
  4714.6    0.16       0  4841.6     0.1       0  4952.9    0.16       0
  4993.9    0.07       0  4999.9    0.16       0  5356.8     0.1       0
Bank Sta=4993.9,4999.9
Exp/Cntr=0.3,0.1

Type RM Length L Ch R = 1,6066,16,16,16
BEGIN DESCRIPTION:
UNT0162 IN SAND CR 9.2
END DESCRIPTION:
XS GIS Cut Line= 3
      3555966.85     10526461.84      3555538.23     10526283.88
      3555212.75     10526038.68
#Sta/Elev= 30
  4598.1  409.07  4610.1  408.19  4615.6  409.63  4634.0  408.14  4639.4  409.59
  4651.7  408.26  4663.3  407.43  4668.7  408.59  4687.2  407.48  4692.6  408.37
  4711.0  406.28  4716.4  407.94  4757.1  406.47  4862.4  400.70  4876.2  400.22
  4967.8  397.78  4982.2  397.32  4997.6  395.34  5000.4  394.84  5003.6  395.34
  5014.7  397.73  5024.5  398.56  5074.6  398.09  5104.3  397.36  5254.2  400.68
  5418.7  407.01  5425.0  408.46  5439.5  407.84  5445.8  409.61  5469.7  410.22
#Mann=9,-1,0
  4598.1    0.16       0  4651.7     0.1       0  4757.1    0.05       0
  4862.4     0.1       0  4876.2    0.05       0  4967.8    0.16       0
  4997.6    0.07       0  5003.6    0.16       0  5074.6    0.05       0
Bank Sta=4997.6,5003.6
Exp/Cntr=0.3,0.1

Type RM Length L Ch R = 1,6050,42,42,42
BEGIN DESCRIPTION:
UNT0162 IN SAND CR 9.0
END DESCRIPTION:
XS GIS Cut Line= 3
      3555966.81     10526446.63      3555552.34     10526273.03
      3555209.48     10526007.20
#Sta/Elev= 30
  4604.9  410.64  4657.9  410.36  4705.3  408.55  4710.7  409.33  4729.1  408.15
  4734.5  408.97  4740.1  407.94  4758.3  406.85  4763.4  407.26  4782.1  405.77
  4787.5  406.30  4811.3  403.93  4864.2  401.79  4888.0  399.91  4911.8  399.65
  4941.0  397.90  4974.3  397.89  4997.3  396.15  5000.1  395.65  5003.3  396.15
  5023.2  398.22  5083.6  397.91  5105.2  397.41  5226.6  399.80  5305.4  403.55
  5340.7  404.30  5376.0  407.03  5390.5  406.83  5429.7  409.47  5488.1  411.12
#Mann=8,-1,0
  4604.9    0.16       0  4657.9     0.1       0  4763.4    0.05       0
  4974.3    0.16       0  4997.3    0.07       0  5003.3    0.16       0
  5083.6    0.05       0  5429.7     0.1       0
Bank Sta=4997.3,5003.3
Exp/Cntr=0.3,0.1

Type RM Length L Ch R = 1,6008,19,19,19
BEGIN DESCRIPTION:
UNT0162 IN SAND CR 9.1
END DESCRIPTION:
XS GIS Cut Line= 4
      3555988.53     10526413.00      3555651.08     10526271.94
      3555570.78     10526231.80      3555261.50     10525988.71
#Sta/Elev= 30
  4597.1  411.00  4671.9  410.43  4731.1  408.59  4823.6  404.70  4900.5  399.69
  4924.3  399.38  4929.7  398.60  4948.1  398.66  4988.9  396.41  4993.4  396.27
  4995.9  394.56  4998.7  394.06  5001.9  394.56  5004.5  395.12  5015.7  397.13
  5021.3  396.54  5028.8  397.50  5101.8  397.47  5108.8  398.58  5115.2  397.49
  5123.3  398.47  5129.7  397.58  5208.3  399.59  5353.1  407.46  5371.9  408.51
  5379.9  408.20  5386.3  409.21  5400.8  409.26  5421.6  410.82  5446.0  411.39
#Mann=8,-1,0
  4597.1    0.16       0  4671.9     0.1       0  4731.1    0.05       0
  4988.9    0.16       0  4995.9    0.07       0  5001.9    0.16       0
  5004.5    0.05       0  5353.1     0.1       0
Bank Sta=4995.9,5001.9
Exp/Cntr=0.3,0.1

Type RM Length L Ch R = 1,5989,601,601,601
BEGIN DESCRIPTION:
UNT0162 IN SAND CR 9.3
END DESCRIPTION:
XS GIS Cut Line= 3
      3555992.87     10526396.73      3555575.12     10526216.60
      3555271.28     10525980.04
#Sta/Elev= 30
  4601.7  411.24  4662.9  410.85  4680.7  410.79  4686.1  410.76  4704.5  410.30
  4751.5  407.88  4756.9  407.99  4804.0  405.99  4880.0  401.55  4903.5  399.62
  4940.1  398.13  4958.8  397.94  4979.5  397.44  4994.6  394.65  5000.0  394.61
  5002.8  394.11  5006.0  394.61  5007.9  395.58  5016.4  396.95  5026.5  397.41
  5049.0  397.57  5061.7  397.23  5076.2  397.67  5119.6  397.93  5154.9  397.67
  5190.2  398.80  5254.4  401.73  5332.7  406.68  5382.9  409.36  5441.7  411.49
#Mann=9,-1,0
  4601.7    0.05       0  4662.9    0.16       0  4680.7     0.1       0
  4686.1    0.05       0  4958.8    0.16       0  5000.0    0.07       0
  5006.0    0.16       0  5007.9    0.05       0  5332.7     0.1       0
Bank Sta=5000,5006
Exp/Cntr=0.3,0.1

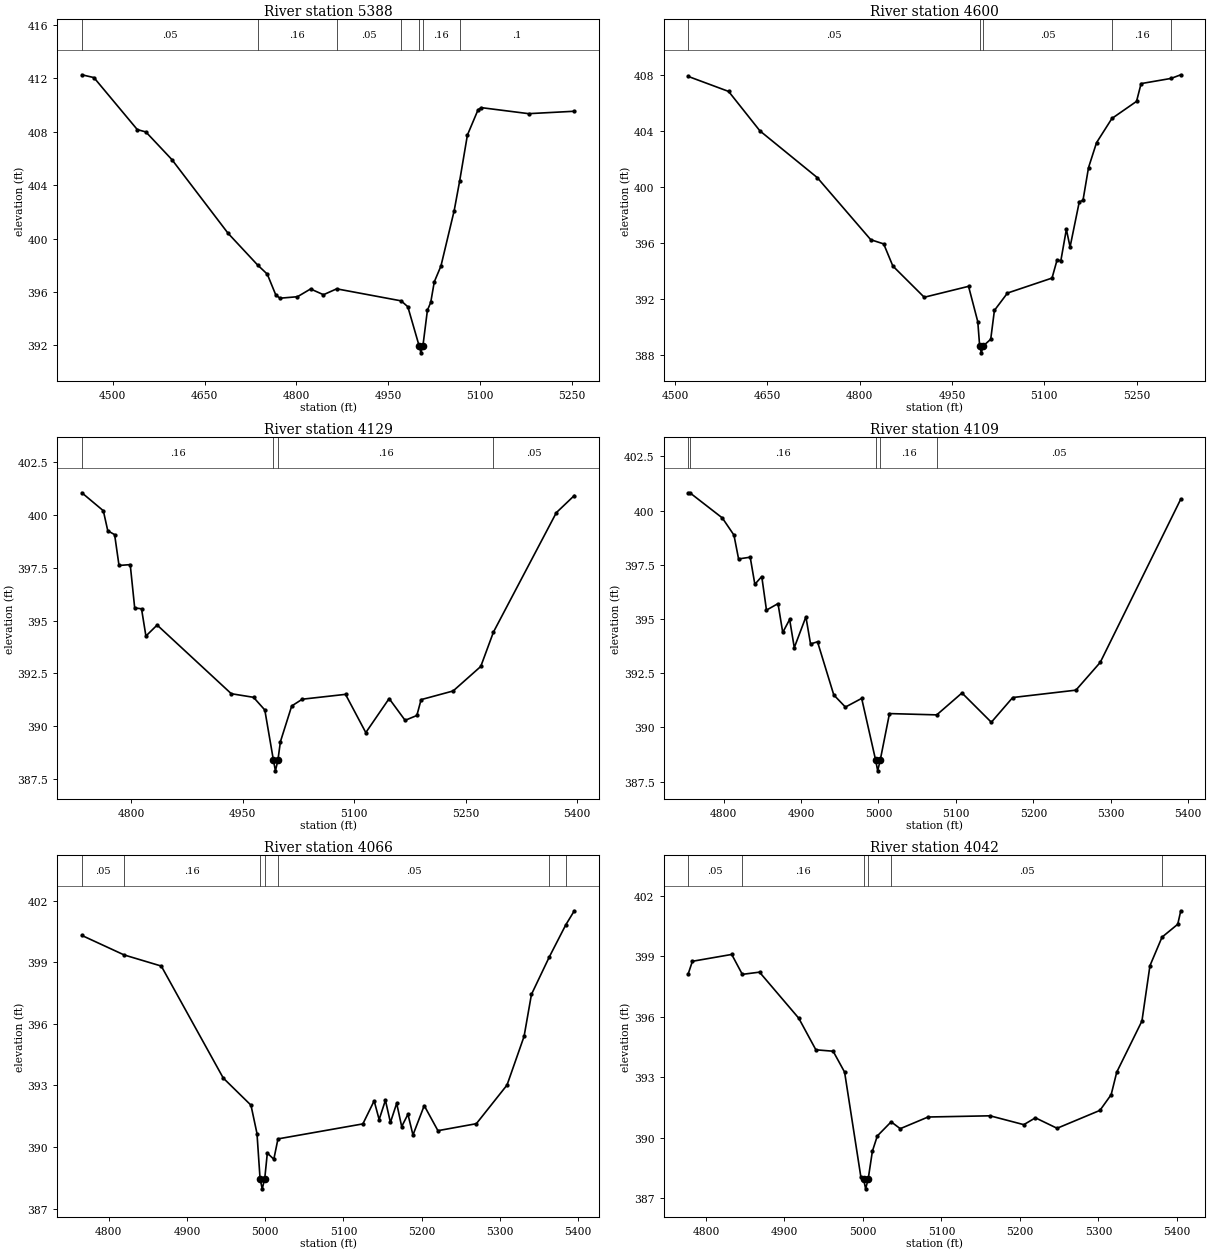
Type RM Length L Ch R = 1,5388,788,788,788
BEGIN DESCRIPTION:
UNT0162 IN SAND CR 8.0
END DESCRIPTION:
XS GIS Cut Line= 3
      3556042.57     10526219.07      3555749.57     10525939.10
      3555380.68     10525787.20
#Sta/Elev= 30
  4449.5  412.26  4469.2  412.05  4540.0  408.16  4554.1  407.98  4596.6  405.91
  4688.4  400.39  4736.6  398.02  4752.3  397.34  4766.4  395.76  4773.3  395.54
  4801.6  395.65  4823.0  396.23  4844.1  395.80  4865.6  396.24  4970.9  395.34
  4981.8  394.90  5000.4  391.95  5003.2  391.45  5006.4  391.95  5013.8  394.64
  5019.2  395.22  5025.0  396.76  5035.9  397.95  5057.5  402.09  5066.4  404.30
  5079.1  407.75  5096.5  409.64  5101.9  409.80  5179.1  409.35  5253.7  409.53
#Mann=7,-1,0
  4449.5    0.05       0  4736.6    0.16       0  4865.6    0.05       0
  4970.9    0.16       0  5000.4    0.07       0  5006.4    0.16       0
  5066.4     0.1       0
Bank Sta=5000.4,5006.4
Exp/Cntr=0.3,0.1

Type RM Length L Ch R = 1,4600,471,471,471
BEGIN DESCRIPTION:
UNT0162 IN SAND CR 6.0
END DESCRIPTION:
XS GIS Cut Line= 2
      3556433.18     10526041.69      3555986.17     10525378.11
#Sta/Elev= 30
  4521.7  407.87  4587.2  406.80  4638.1  403.98  4731.1  400.65  4818.1  396.21
  4839.1  395.91  4854.0  394.33  4905.0  392.10  4977.0  392.88  4992.0  390.35
  4995.0  388.63  4997.7  388.13  5001.0  388.63  5013.0  389.10  5019.0  391.16
  5040.2  392.40  5112.6  393.47  5120.9  394.78  5126.9  394.70  5135.9  396.95
  5141.9  395.69  5156.9  398.92  5162.9  399.02  5171.9  401.36  5184.9  403.14
  5209.9  404.87  5249.9  406.09  5257.3  407.36  5306.0  407.73  5321.8  407.99
#Mann=5,-1,0
  4521.7    0.05       0  4995.0   0.035       0  5001.0    0.05       0
  5209.9    0.16       0  5306.0    0.05       0
Bank Sta=4995,5001
Exp/Cntr=0.3,0.1

Type RM Length L Ch R = 1,4129,20,20,20
BEGIN DESCRIPTION:
UNT0162 IN SAND CR 5.3
END DESCRIPTION:
XS GIS Cut Line= 3
      3556733.53     10525789.96      3556563.40     10525529.56
      3556259.60     10525352.48
#Sta/Elev= 30
  4733.5  401.05  4762.4  400.20  4768.4  399.25  4777.6  399.07  4783.5  397.61
  4798.6  397.65  4804.6  395.60  4813.8  395.56  4819.7  394.27  4834.8  394.79
  4934.6  391.54  4964.5  391.37  4979.7  390.77  4991.3  388.39  4994.0  387.89
  4997.3  388.39  5000.7  389.27  5015.9  390.96  5030.1  391.28  5088.3  391.51
  5115.6  389.70  5147.0  391.31  5168.5  390.28  5184.3  390.51  5190.0  391.26
  5233.1  391.67  5270.3  392.83  5287.4  394.46  5372.0  400.11  5396.2  400.92
#Mann=4,-1,0
  4733.5    0.16       0  4991.3    0.07       0  4997.3    0.16       0
  5287.4    0.05       0
Bank Sta=4991.3,4997.3
Exp/Cntr=0.3,0.1

Type RM Length L Ch R = 1,4109,43,43,43
BEGIN DESCRIPTION:
UNT0162 IN SAND CR 5.0
END DESCRIPTION:
XS GIS Cut Line= 3
      3556742.22     10525762.20      3556554.72     10525484.42
      3556290.84     10525340.33
#Sta/Elev= 30
  4754.5  400.82  4756.5  400.82  4798.4  399.66  4813.4  398.87  4819.4  397.77
  4834.4  397.85  4840.4  396.60  4849.3  396.96  4855.4  395.41  4870.3  395.71
  4876.4  394.38  4885.3  394.98  4891.3  393.68  4906.3  395.10  4912.3  393.85
  4921.3  393.95  4942.3  391.50  4957.3  390.94  4978.3  391.34  4996.3  388.50
  4999.0  388.00  5002.3  388.50  5014.2  390.64  5075.2  390.58  5107.8  391.59
  5145.7  390.24  5173.3  391.38  5254.9  391.72  5286.3  393.00  5390.3  400.53
#Mann=5,-1,0
  4754.5    0.05       0  4756.5    0.16       0  4996.3    0.07       0
  5002.3    0.16       0  5075.2    0.05       0
Bank Sta=4996.3,5002.3
Exp/Cntr=0.3,0.1

Type RM Length L Ch R = 1,4066,24,24,24
BEGIN DESCRIPTION:
UNT0162 IN SAND CR 5.1
END DESCRIPTION:
XS GIS Cut Line= 4
      3556785.61     10525730.92      3556580.77     10525456.64
      3556492.22     10525385.46      3556333.24     10525316.34
#Sta/Elev= 30
  4765.7  400.30  4819.8  399.35  4867.2  398.81  4946.4  393.36  4981.8  392.04
  4989.5  390.66  4993.4  388.47  4996.2  387.97  4999.4  388.47  5002.7  389.71
  5011.0  389.41  5016.3  390.40  5124.8  391.13  5139.2  392.25  5145.6  391.34
  5153.6  392.28  5160.0  391.20  5168.0  392.13  5174.4  391.00  5182.4  391.60
  5188.8  390.59  5203.2  392.02  5220.7  390.80  5269.8  391.14  5309.0  393.02
  5330.8  395.39  5340.2  397.43  5363.1  399.26  5384.0  400.81  5395.0  401.50
#Mann=7,-1,0
  4765.7    0.05       0  4819.8    0.16       0  4993.4    0.07       0
  4999.4    0.16       0  5016.3    0.05       0  5363.1     0.1       0
  5384.0    0.05       0
Bank Sta=4993.4,4999.4
Exp/Cntr=0.3,0.1

Type RM Length L Ch R = 1,4042,366,366,366
BEGIN DESCRIPTION:
UNT0162 IN SAND CR 5.2
END DESCRIPTION:
XS GIS Cut Line= 4
      3556799.50     10525711.82      3556589.45     10525430.60
      3556485.28     10525357.68      3556345.90     10525304.34
#Sta/Elev= 30
  4777.5  398.15  4782.7  398.76  4832.8  399.10  4846.3  398.11  4868.2  398.22
  4918.2  395.93  4940.0  394.36  4962.0  394.29  4976.6  393.25  4997.4  388.02
  5000.7  387.95  5003.4  387.45  5006.7  387.95  5012.0  389.32  5018.3  390.08
  5035.9  390.78  5047.5  390.44  5082.9  391.02  5161.9  391.08  5204.9  390.64
  5219.7  390.98  5247.3  390.46  5301.9  391.35  5316.2  392.13  5323.3  393.25
  5355.4  395.79  5365.6  398.54  5381.0  399.96  5401.0  400.60  5404.9  401.27
#Mann=6,-1,0
  4777.5    0.05       0  4846.3    0.16       0  5000.7    0.07       0
  5006.7    0.16       0  5035.9    0.05       0  5381.0     0.1       0
Bank Sta=5000.7,5006.7
Exp/Cntr=0.3,0.1

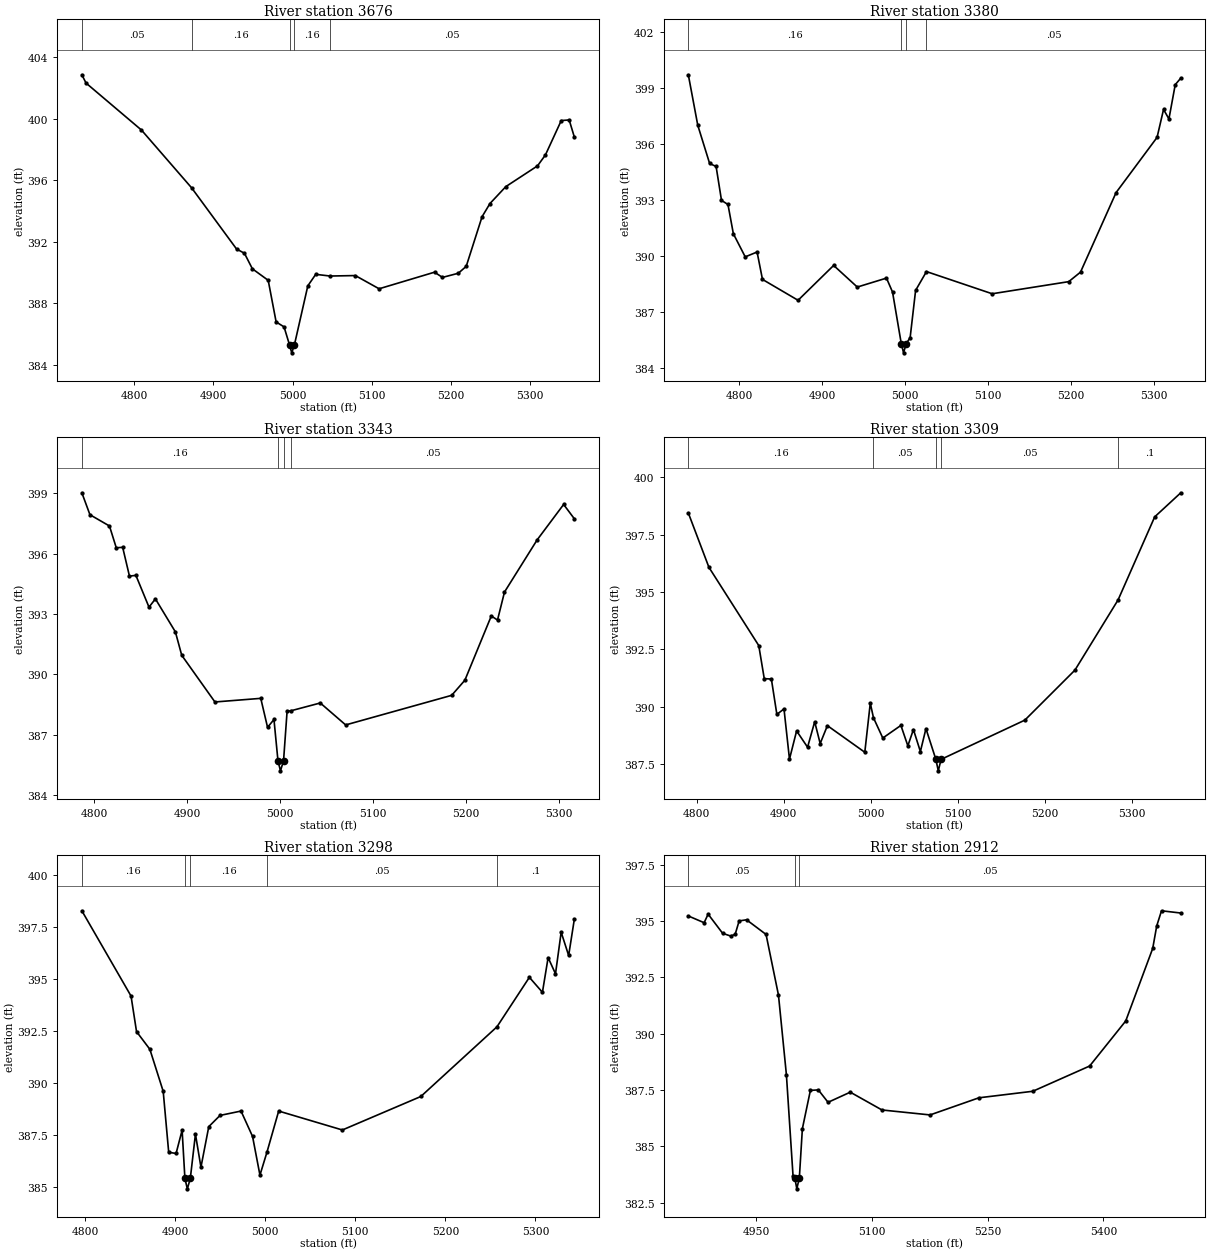
Type RM Length L Ch R = 1,3676,296,296,296
BEGIN DESCRIPTION:
UNT0162 IN SAND CR 4.0
END DESCRIPTION:
XS GIS Cut Line= 2
      3557037.37     10525239.63      3556415.59     10525244.83
#Sta/Elev= 30
  4733.8  402.87  4739.1  402.33  4809.1  399.27  4872.4  395.51  4929.1  391.53
  4939.1  391.25  4949.1  390.24  4969.1  389.49  4979.1  386.78  4989.1  386.46
  4996.1  385.27  4998.8  384.77  5002.1  385.27  5019.1  389.13  5029.1  389.88
  5047.2  389.77  5079.1  389.80  5109.1  388.94  5179.1  390.02  5189.1  389.68
  5209.1  389.95  5219.1  390.40  5239.1  393.63  5249.1  394.49  5269.1  395.59
  5309.1  396.94  5319.1  397.65  5339.1  399.89  5349.1  399.93  5355.6  398.82
#Mann=5,-1,0
  4733.8    0.05       0  4872.4    0.16       0  4996.1    0.07       0
  5002.1    0.16       0  5047.2    0.05       0
Bank Sta=4996.1,5002.1
Exp/Cntr=0.3,0.1

Type RM Length L Ch R = 1,3380,37,37,37
BEGIN DESCRIPTION:
UNT0162 IN SAND CR 3.5
END DESCRIPTION:
XS GIS Cut Line= 2
      3556909.97     10524822.75      3556457.01     10525206.56
#Sta/Elev= 30
  4738.9  399.73  4750.3  397.02  4764.6  394.97  4772.4  394.81  4778.9  392.99
  4786.7  392.77  4793.2  391.20  4807.5  389.96  4821.8  390.22  4828.3  388.75
  4871.2  387.63  4914.1  389.50  4942.6  388.34  4977.8  388.82  4985.1  388.07
  4995.6  385.31  4998.4  384.81  5001.6  385.31  5006.3  385.62  5012.9  388.16
  5026.0  389.17  5105.2  387.98  5197.5  388.63  5211.7  389.14  5254.6  393.41
  5304.0  396.37  5311.8  397.87  5318.3  397.36  5325.9  399.20  5332.6  399.55
#Mann=4,-1,0
  4738.9    0.16       0  4995.6    0.07       0  5001.6    0.16       0
  5026.0    0.05       0
Bank Sta=4995.6,5001.6
Exp/Cntr=0.3,0.1

Type RM Length L Ch R = 1,3343,34,34,34
BEGIN DESCRIPTION:
UNT0162 IN SAND CR 3.4
END DESCRIPTION:
XS GIS Cut Line= 3
      3556826.62     10524814.09      3556628.73     10525025.87
      3556449.92     10525185.58
#Sta/Elev= 30
  4786.8  399.02  4795.5  397.93  4816.5  397.37  4823.8  396.29  4830.7  396.31
  4838.0  394.88  4844.9  394.92  4859.0  393.34  4865.9  393.75  4887.4  392.11
  4894.2  390.95  4929.9  388.63  4979.2  388.81  4986.5  387.37  4993.4  387.76
  4997.7  385.71  5000.4  385.21  5003.7  385.71  5007.5  388.16  5012.2  388.20
  5043.2  388.58  5070.5  387.49  5184.5  388.96  5198.7  389.71  5227.1  392.90
  5233.8  392.70  5241.3  394.09  5276.4  396.68  5304.9  398.44  5316.4  397.73
#Mann=4,-1,0
  4786.8    0.16       0  4997.7    0.07       0  5003.7    0.16       0
  5012.2    0.05       0
Bank Sta=4997.7,5003.7
Exp/Cntr=0.3,0.1

Type RM Length L Ch R = 1,3309,11,11,11
BEGIN DESCRIPTION:
UNT0162 IN SAND CR 3.2
END DESCRIPTION:
XS GIS Cut Line= 3
      3556786.70     10524782.83      3556666.92     10524939.07
      3556378.69     10525169.99
#Sta/Elev= 30
  4790.3  398.45  4814.0  396.08  4871.3  392.67  4877.6  391.23  4885.8  391.21
  4892.1  389.67  4900.3  389.91  4906.6  387.72  4914.8  388.95  4927.4  388.24
  4935.6  389.35  4941.9  388.40  4950.2  389.18  4993.2  388.02  4999.5  390.16
  5003.2  389.52  5013.9  388.64  5034.7  389.19  5042.7  388.30  5049.1  389.01
  5057.1  388.05  5063.5  389.05  5074.9  387.71  5077.7  387.21  5080.9  387.71
  5177.2  389.42  5234.8  391.60  5284.4  394.66  5326.5  398.28  5356.5  399.33
#Mann=5,-1,0
  4790.3    0.16       0  5003.2    0.05       0  5074.9    0.07       0
  5080.9    0.05       0  5284.4     0.1       0
Bank Sta=5074.9,5080.9
Exp/Cntr=0.3,0.1

Type RM Length L Ch R = 1,3298,386,386,386
BEGIN DESCRIPTION:
UNT0162 IN SAND CR 3.3
END DESCRIPTION:
XS GIS Cut Line= 3
      3556771.09     10524775.86      3556666.92     10524925.18
      3556377.51     10525147.00
#Sta/Elev= 30
  4796.5  398.27  4851.1  394.17  4857.2  392.46  4872.0  391.61  4886.8  389.59
  4892.9  386.66  4901.1  386.60  4907.8  387.72  4910.9  385.40  4913.6  384.90
  4916.9  385.40  4922.6  387.53  4928.7  385.94  4937.4  387.89  4949.9  388.43
  4973.2  388.64  4986.0  387.42  4994.2  385.56  5001.9  386.65  5015.0  388.64
  5085.7  387.73  5172.8  389.34  5257.3  392.69  5293.3  395.07  5307.8  394.35
  5314.1  396.02  5322.3  395.24  5328.6  397.24  5336.9  396.12  5343.2  397.86
#Mann=5,-1,0
  4796.5    0.16       0  4910.9    0.07       0  4916.9    0.16       0
  5001.9    0.05       0  5257.3     0.1       0
Bank Sta=4910.9,4916.9
Exp/Cntr=0.3,0.1

Type RM Length L Ch R = 1,2912,805,805,805
BEGIN DESCRIPTION:
UNT0162 IN SAND CR 3.1
END DESCRIPTION:
XS GIS Cut Line= 2
      3556675.08     10524600.87      3556057.91     10524764.93
#Sta/Elev= 30
  4861.8  395.23  4882.3  394.93  4887.5  395.31  4906.3  394.46  4916.6  394.34
  4922.5  394.41  4927.7  395.01  4937.3  395.06  4962.6  394.41  4978.7  391.72
  4989.0  388.18  4997.6  383.69  4999.8  383.62  5002.5  383.12  5005.8  383.62
  5009.7  385.79  5020.1  387.49  5030.4  387.51  5043.0  386.96  5071.8  387.41
  5112.9  386.62  5175.3  386.40  5238.6  387.16  5308.5  387.45  5382.2  388.57
  5429.0  390.57  5464.0  393.79  5469.2  394.79  5475.4  395.46  5500.4  395.36
#Mann=3,-1,0
  4861.8    0.05       0  4999.8   0.035       0  5005.8    0.05       0
Bank Sta=4999.8,5005.8
Exp/Cntr=0.3,0.1

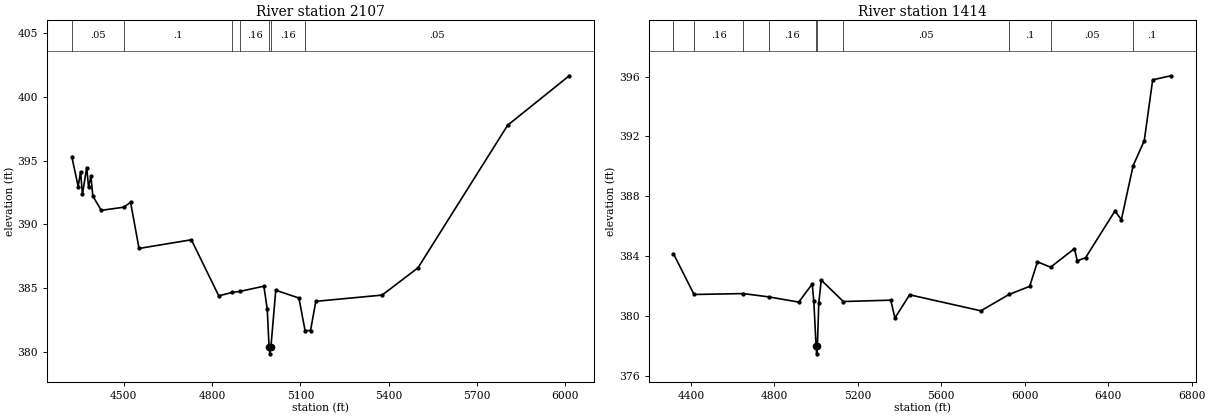
Type RM Length L Ch R = 1,2107,693,693,693
BEGIN DESCRIPTION:
UNT0162 IN SAND CR 3.0
END DESCRIPTION:
XS GIS Cut Line= 4
      3556825.98     10524578.43      3556372.40     10524218.18
      3556053.39     10524129.20      3555286.10     10524263.59
#Sta/Elev= 30
  4323.7  395.29  4345.2  392.96  4353.3  394.12  4359.7  392.34  4374.1  394.45
  4380.5  392.90  4388.5  393.78  4394.9  392.21  4423.7  391.09  4500.8  391.34
  4523.1  391.73  4551.9  388.10  4729.7  388.78  4822.7  384.38  4868.1  384.65
  4894.9  384.73  4975.9  385.14  4987.3  383.34  4993.7  380.33  4996.4  379.83
  4999.7  380.33  5016.3  384.82  5095.0  384.21  5115.8  381.66  5134.4  381.66
  5152.4  383.95  5377.6  384.44  5499.4  386.58  5804.0  397.77  6013.1  401.65
#Mann=7,-1,0
  4323.7    0.05       0  4500.8     0.1       0  4868.1    0.05       0
  4894.9    0.16       0  4993.7    0.07       0  4999.7    0.16       0
  5115.8    0.05       0
Bank Sta=4993.7,4999.7
Exp/Cntr=0.3,0.1

Type RM Length L Ch R = 1,1414,0,0,0
BEGIN DESCRIPTION:
UNT0162 IN SAND CR 1.0
END DESCRIPTION:
XS GIS Cut Line= 3
      3556932.31     10524307.19      3556621.97     10523547.60
      3555065.47     10523404.53
#Sta/Elev= 30
  4316.6  384.18  4415.3  381.46  4650.5  381.52  4773.2  381.30  4917.1  380.95
  4981.5  382.16  4989.2  381.01  5000.2  378.00  5002.9  377.50  5006.2  378.00
  5013.2  380.92  5024.8  382.42  5130.5  380.99  5357.9  381.08  5378.0  379.89
  5448.3  381.44  5789.7  380.37  5925.9  381.47  6023.7  382.00  6060.9  383.64
  6123.7  383.28  6238.4  384.52  6251.7  383.70  6291.9  383.92  6432.4  387.03
  6463.1  386.45  6519.5  390.05  6573.0  391.73  6613.2  395.78  6700.2  396.05
#Mann=10,-1,0
  4316.6    0.05       0  4415.3    0.16       0  4650.5    0.05       0
  4773.2    0.16       0  5000.2    0.07       0  5006.2    0.16       0
  5130.5    0.05       0  5925.9     0.1       0  6123.7    0.05       0
  6519.5     0.1       0
Bank Sta=5000.2,5006.2
Exp/Cntr=0.3,0.1

Chan Stop Cuts=-1