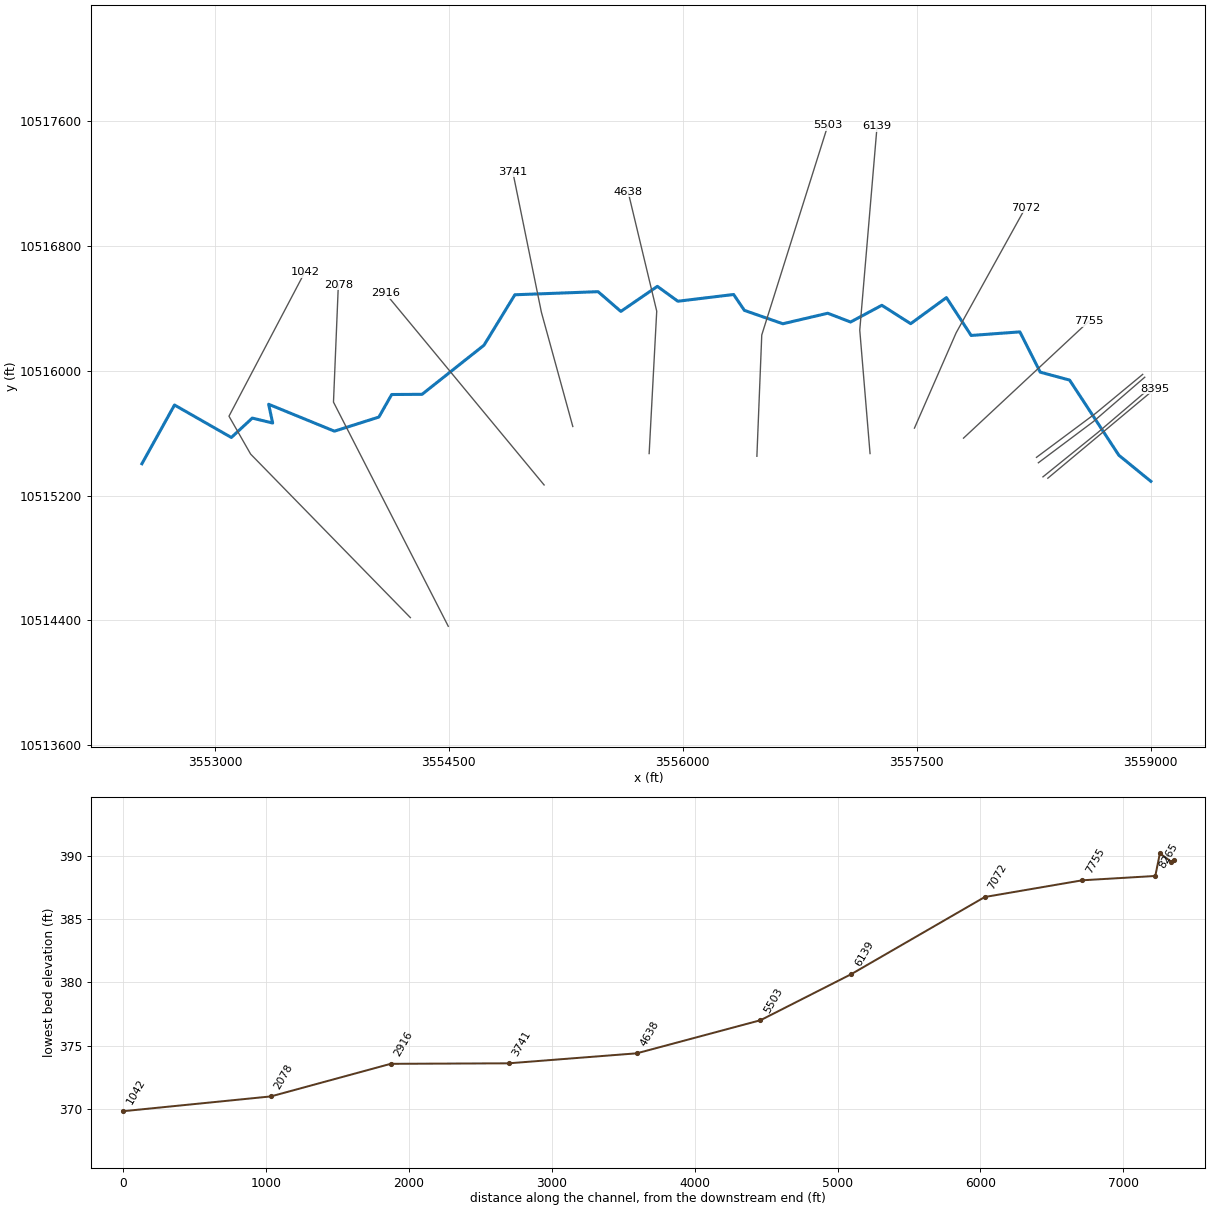
--- UNT0163 IN SAND CR.prj (project) ---

Proj Title=UNT0163 IN SAND CR Base Level Engineering
Current Plan=p01
Default Exp/Contr=0.3,0.1
English Units
Geom File=g01
Flow File=f01
Plan File=p01
Y Axis Title=Elevation
X Axis Title(PF)=Main Channel Distance
X Axis Title(XS)=Station
BEGIN DESCRIPTION:
UNT0163 IN SAND CR
END DESCRIPTION:
DSS Export Rating Curves= 0
DSS Export Rating Curve Sorted= 0
DSS Export Volume Flow Curves= 0
DXF OffsetX= 0
DXF OffsetY= 0
DXF ScaleX= 1
DXF ScaleY= 10

--- UNT0163 IN SAND CR.p01 (plan) ---

Plan Title=Multiple Run
Short Identifier=Multiple
Geom File=g01
Flow File=f01
Subcritical Flow
K Sum by GR= 0
Std Step Tol= 0.01
Critical Tol= 0.01
Num of Std Step Trials= 20
Max Error Tol= 0.3
Flow Tol Ratio= 0.001
Split Flow NTrial= 30
Split Flow Tol= 0.02
Split Flow Ratio= 0.02
Log Output Level= 0
Friction Slope Method= 1
Unsteady Friction Slope Method= 2
Unsteady Bridges Friction Slope Method= 1
Parabolic Critical Depth
Global Vel Dist=  1 , 1 , 1
Global Log Level= 0
CheckData=True
Encroach Param= -1, 0, 0, 0
BEGIN DESCRIPTION:
Multiple Run
END DESCRIPTION:

--- UNT0163 IN SAND CR.f01 (steady flow) ---

Flow Title=Multiple
Number of Profiles=7
Profile Names=10-year,25-year,50-year,1pct_min,100-year,1pct_plu,500-year
River Rch & RM= UNT0163 IN SAND ,Reach-1,8395
    1447    2022    2503    2257    3052    4128    4528
Boundary for River Rch & Prof#=UNT0163 IN SAND ,Reach-1,1
Up Type=0
Dn Type=3
Dn Slope=0.005
Boundary for River Rch & Prof#=UNT0163 IN SAND ,Reach-1,2
Up Type=0
Dn Type=3
Dn Slope=0.005
Boundary for River Rch & Prof#=UNT0163 IN SAND ,Reach-1,3
Up Type=0
Dn Type=3
Dn Slope=0.005
Boundary for River Rch & Prof#=UNT0163 IN SAND ,Reach-1,4
Up Type=0
Dn Type=3
Dn Slope=0.005
Boundary for River Rch & Prof#=UNT0163 IN SAND ,Reach-1,5
Up Type=0
Dn Type=3
Dn Slope=0.005
Boundary for River Rch & Prof#=UNT0163 IN SAND ,Reach-1,6
Up Type=0
Dn Type=3
Dn Slope=0.005
Boundary for River Rch & Prof#=UNT0163 IN SAND ,Reach-1,7
Up Type=0
Dn Type=3
Dn Slope=0.005

--- UNT0163 IN SAND CR.g01 (geometry) ---

Geom Title=Existing Conditions
Program Version=4.10

River Reach=UNT0163 IN SAND ,Reach-1
Reach XY= 30
      3559002.11     10515291.64       3558796.9     10515458.89
      3558481.01     10515940.91      3558292.63     10515991.82
      3558162.17     10516250.07      3557849.66     10516227.09
      3557691.05     10516469.85      3557461.83     10516302.61
      3557277.07     10516420.62      3557076.33     10516313.34
      3556930.29     10516369.61      3556642.01      10516302.2
      3556395.57     10516387.87      3556326.44     10516489.77
      3555968.84     10516446.55      3555837.45     10516541.98
      3555603.19     10516381.31      3555457.23      10516507.9
       3554923.5     10516488.07      3554725.77     10516164.78
      3554328.51     10515849.66      3554133.58     10515848.42
      3554051.48     10515703.78      3553766.27     10515613.32
      3553344.44     10515785.82      3553370.48     10515665.51
      3553239.75     10515697.28      3553105.38      10515572.8
      3552740.79     10515781.13      3552531.97      10515404.6

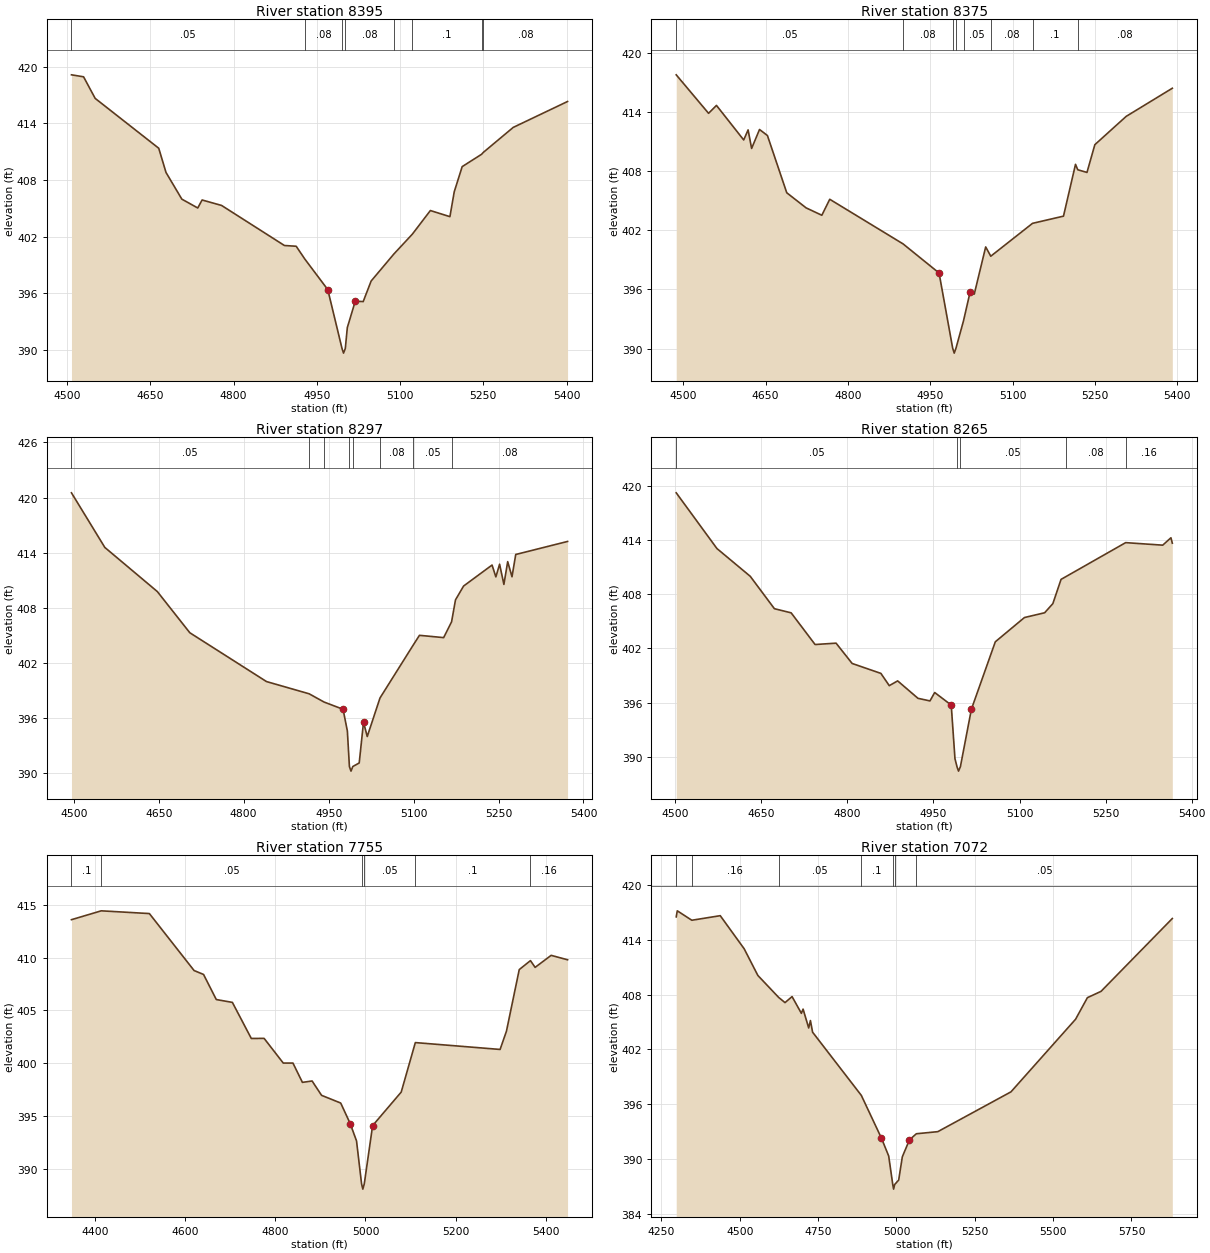
Type RM Length L Ch R = 1 ,8395    ,20,20,20
BEGIN DESCRIPTION:
UNT0163 IN SAND CR 16.2
END DESCRIPTION:
XS GIS Cut Line= 2
      3558341.44     10515311.74      3559027.21     10515884.66
#Sta/Elev= 30
  4508.1  419.16  4529.9  418.95  4550.8  416.66  4665.3  411.37  4678.4   408.8
  4706.9  405.97  4735.6  405.03  4743.4  405.88  4778.5   405.3  4891.7  401.05
  4912.9  400.97  4928.6   399.6  4969.8  396.37  4995.4  390.13  4998.2  389.63
  5001.4  390.13    5005  392.34  5019.3  395.14  5033.6   395.1  5047.9  397.28
  5089.2  400.17  5122.1  402.25  5154.6  404.76  5189.8  404.11  5197.6  406.75
  5211.9  409.42  5246.9  410.73  5249.8  410.92  5303.8  413.58  5401.7  416.33
#Mann= 8 ,-1 , 0
  4508.1     .05       0  4928.6     .08       0  4995.4     .03       0
  5001.4     .08       0  5089.2     .08       0  5122.1      .1       0
  5246.9     .05       0  5249.8     .08       0
Bank Sta=4969.8,5019.3
XS Rating Curve= 0 ,0
Exp/Cntr=0.3,0.1

Type RM Length L Ch R = 1 ,8375    ,78,78,78
BEGIN DESCRIPTION:
UNT0163 IN SAND CR 16.0
END DESCRIPTION:
XS GIS Cut Line= 3
      3558310.21     10515320.44      3558662.65     10515605.17
      3559005.25     10515897.58
#Sta/Elev= 30
  4487.3  417.74  4546.2  413.84  4560.6  414.64  4610.2  411.14  4618.2  412.16
  4624.6  410.28    4639   412.2  4653.4  411.59  4688.6  405.79  4723.8  404.26
  4752.5  403.51  4766.9  405.13  4900.4  400.61    4966  397.66  4990.8  390.04
  4993.6  389.54  4996.8  390.04  5010.5  392.81  5022.4   395.7  5030.1  395.52
  5050.9   400.3  5060.2  399.36  5136.2  402.69  5192.6  403.42  5214.5  408.67
  5218.6  408.12  5235.4  407.85  5249.7  410.66  5306.8  413.53  5390.8  416.38
#Mann= 8 ,-1 , 0
  4487.3     .05       0  4900.4     .08       0  4990.8     .07       0
  4996.8     .08       0  5010.5     .05       0  5060.2     .08       0
  5136.2      .1       0  5218.6     .08       0
Bank Sta=4966,5022.4
XS Rating Curve= 0 ,0
Exp/Cntr=0.3,0.1

Type RM Length L Ch R = 1 ,8297    ,32,32,32
BEGIN DESCRIPTION:
UNT0163 IN SAND CR 16.1
END DESCRIPTION:
XS GIS Cut Line= 3
      3558280.72     10515410.73      3558633.14     10515674.61
      3558962.99     10515959.33
#Sta/Elev= 30
  4495.9  420.51  4554.8  414.56  4647.5  409.75  4704.9  405.26  4840.3  399.94
  4915.5  398.61  4941.9  397.71  4975.5  396.92  4983.1  394.55  4986.7  390.68
  4989.5  390.18  4992.7  390.68    5004  391.07  5011.6  395.51  5018.2  393.95
  5040.7  398.15  5099.2   403.9  5110.4  404.98  5153.1  404.73  5167.1  406.45
    5174  408.84  5188.3  410.35  5238.6  412.64  5245.3  411.35  5251.9  412.73
  5259.5  410.53  5266.2  413.01  5273.8  411.36  5280.4  413.79  5371.9  415.21
#Mann= 8 ,-1 , 0
  4495.9     .05       0  4915.5     .08       0  4941.9     .05       0
  4986.7     .03       0  4992.7     .05       0  5040.7     .08       0
  5099.2     .05       0  5167.1     .08       0
Bank Sta=4975.5,5011.6
XS Rating Curve= 0 ,0
Exp/Cntr=0.3,0.1

Type RM Length L Ch R = 1 ,8265    ,510,510,510
BEGIN DESCRIPTION:
UNT0163 IN SAND CR 16.3
END DESCRIPTION:
XS GIS Cut Line= 3
      3558268.59     10515445.47      3558648.76     10515728.43
      3558949.74     10515977.52
#Sta/Elev= 30
  4501.7  419.24  4572.6  413.07  4630.7  409.99  4672.8   406.4    4702  405.94
  4743.7  402.43  4780.3  402.58  4808.3  400.33  4858.4  399.23    4873  397.87
  4887.6   398.4    4923  396.47  4943.9  396.18  4952.2  397.11    4981  395.72
  4987.5  389.78    4991   388.9  4993.7   388.4    4997   388.9  5016.1  395.25
  5057.8  402.73  5108.6  405.42  5143.8  405.95  5158.1  406.96  5172.4  409.65
  5180.5  409.94    5285  413.72  5349.6  413.44  5363.9  414.26  5366.3  413.66
#Mann= 5 ,-1 , 0
  4501.7     .05       0    4991     .03       0    4997     .05       0
  5180.5     .08       0    5285     .16       0
Bank Sta=4981,5016.1
XS Rating Curve= 0 ,0
Exp/Cntr=0.3,0.1

Type RM Length L Ch R = 1 ,7755    ,683,683,683
BEGIN DESCRIPTION:
UNT0163 IN SAND CR 15.0
END DESCRIPTION:
XS GIS Cut Line= 2
      3557800.65     10515568.69      3558605.76     10516319.54
#Sta/Elev= 30
  4347.5   413.6  4413.6  414.44  4520.4  414.18  4619.6  408.78  4640.6  408.41
  4668.9  406.03  4704.6  405.76  4746.6  402.34    4775  402.35  4817.5  400.01
    4839  400.01    4860  398.18  4881.5  398.31  4902.5  396.95    4945  396.22
    4966  394.28  4980.1  392.63  4991.3  388.56  4994.1  388.06  4997.3  388.56
  5015.8  394.08  5079.3  397.26  5110.6  401.95  5298.7   401.3  5312.8  403.03
  5341.2  408.87  5366.1  409.72  5376.4  409.08    5412  410.22  5448.4   409.8
#Mann= 6 ,-1 , 0
  4347.5      .1       0  4413.6     .05       0  4991.3     .03       0
  4997.3     .05       0  5110.6      .1       0  5366.1     .16       0
Bank Sta=4966,5015.8
XS Rating Curve= 0 ,0
Exp/Cntr=0.3,0.1

Type RM Length L Ch R = 1 ,7072    ,933,933,933
BEGIN DESCRIPTION:
UNT0163 IN SAND CR 13.0
END DESCRIPTION:
XS GIS Cut Line= 3
      3557486.03     10515632.96      3557753.39     10516244.07
      3558197.48     10517045.52
#Sta/Elev= 30
  4297.1  416.49  4300.5  417.15  4346.9  416.12  4437.6  416.62    4514     413
  4557.6  410.09    4624  407.69  4644.3  407.12  4666.8  407.78  4696.5  405.95
    4702  406.41  4719.9  404.35  4725.4  405.16  4732.3  403.89  4887.9  396.98
  4952.2   392.3  4975.2  390.36  4988.2  387.24  4990.9  386.74  4994.2  387.24
  5007.1  387.73  5018.7  390.27  5041.4  392.12  5063.5  392.79    5132  393.02
  5365.5  397.37  5571.6   405.3  5609.4  407.66  5652.9  408.35  5880.4  416.31
#Mann= 7 ,-1 , 0
  4297.1     .05       0  4346.9     .16       0    4624     .05       0
  4887.9      .1       0  4988.2     .07       0  4994.2      .1       0
  5063.5     .05       0
Bank Sta=4952.2,5041.4
XS Rating Curve= 0 ,0
Exp/Cntr=0.3,0.1

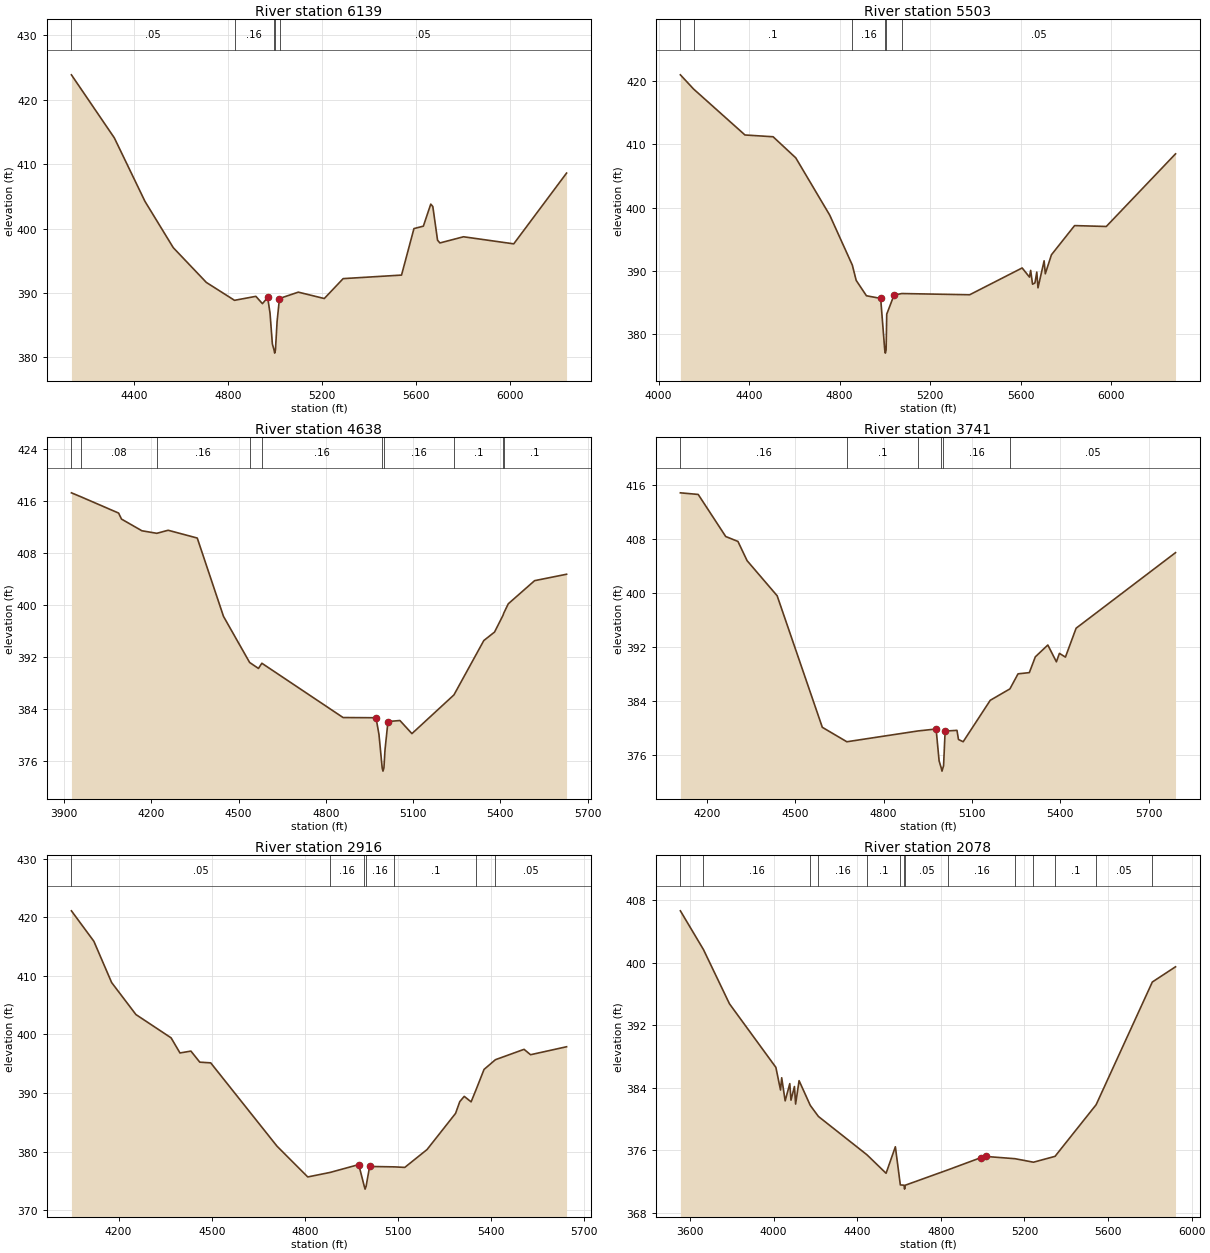
Type RM Length L Ch R = 1 ,6139    ,636,636,636
BEGIN DESCRIPTION:
UNT0163 IN SAND CR 11.0
END DESCRIPTION:
XS GIS Cut Line= 3
      3557201.31     10515469.77      3557135.34     10516261.44
      3557246.28     10517568.52
#Sta/Elev= 30
  4134.8  423.88  4317.3  414.09  4447.8  404.22  4568.2  397.03  4708.7  391.64
  4828.6  388.86  4919.4  389.48  4947.3  388.34  4969.6   389.3  4979.6  386.88
  4989.6  382.07  4996.7  381.16  4999.4  380.66  5002.7  381.16  5009.7  385.59
  5019.7  389.14  5021.2  389.16    5100  390.13  5210.4  389.14  5290.7  392.23
    5539  392.78  5591.8     400  5631.9  400.38  5663.3   403.8  5672.1  403.43
  5692.2   398.2  5702.2  397.77  5802.6  398.73  6016.3  397.63    6241  408.62
#Mann= 5 ,-1 , 0
  4134.8     .05       0  4828.6     .16       0  4996.7     .07       0
  5002.7     .16       0  5021.2     .05       0
Bank Sta=4969.6,5019.7
XS Rating Curve= 0 ,0
Exp/Cntr=0.3,0.1

Type RM Length L Ch R = 1 ,5503    ,865,865,865
BEGIN DESCRIPTION:
UNT0163 IN SAND CR 10.0
END DESCRIPTION:
XS GIS Cut Line= 3
      3556475.61      10515452.4      3556506.86     10516230.19
      3556930.49     10517573.98
#Sta/Elev= 30
  4096.3  420.97  4154.5  418.73  4381.6  411.47  4505.9  411.19    4606  407.86
  4756.1  398.81    4856  390.91  4872.9  388.51  4918.2  386.08  4981.1  385.66
  4999.1  377.52  5001.8  377.02  5005.1  377.52  5007.9  383.18  5040.3  386.19
  5074.4  386.43  5374.4  386.24  5606.1  390.47  5638.5  389.03  5643.7  390.09
  5652.1   387.9  5662.6   388.1  5670.8  389.82  5676.1  387.33  5703.2   391.6
  5708.4  389.55  5735.5  392.55  5837.8  397.16  5977.8  397.02  6283.7  408.49
#Mann= 6 ,-1 , 0
  4096.3     .05       0  4154.5      .1       0    4856     .16       0
  4999.1     .07       0  5005.1     .16       0  5074.4     .05       0
Bank Sta=4981.1,5040.3
XS Rating Curve= 0 ,0
Exp/Cntr=0.3,0.1

Type RM Length L Ch R = 1 ,4638    ,897,897,897
BEGIN DESCRIPTION:
UNT0163 IN SAND CR 8.0
END DESCRIPTION:
XS GIS Cut Line= 3
      3555784.64     10515469.72      3555833.25     10516382.96
      3555649.66     10517148.52
#Sta/Elev= 30
  3925.6  417.31  3957.7  416.71  4087.7  414.19  4097.8  413.26  4167.9  411.46
  4219.1  411.07    4258  411.54  4358.1  410.34  4448.3  398.26  4538.1  391.16
  4568.4  390.24  4580.2  391.04  4859.3  382.67  4972.5  382.64  4982.7  380.04
  4993.7  374.91  4996.4  374.41  4999.7  374.91  5003.3  377.64  5013.6  382.06
  5054.7  382.21  5095.9  380.19  5240.3  386.16    5343  394.54  5379.9  395.85
  5409.1  398.44  5411.4  398.75    5427   400.2  5517.5  403.77  5627.4  404.76
#Mann= 10 ,-1 , 0
  3925.6      .1       0  3957.7     .08       0  4219.1     .16       0
  4538.1      .1       0  4580.2     .16       0  4993.7     .07       0
  4999.7     .16       0  5240.3      .1       0  5409.1     .05       0
  5411.4      .1       0
Bank Sta=4972.5,5013.6
XS Rating Curve= 0 ,0
Exp/Cntr=0.3,0.1

Type RM Length L Ch R = 1 ,3741    ,825,825,825
BEGIN DESCRIPTION:
UNT0163 IN SAND CR 6.0
END DESCRIPTION:
XS GIS Cut Line= 3
      3555295.07     10515643.34      3555093.67     10516376.02
      3554909.86     10517277.72
#Sta/Elev= 30
  4110.8  414.84  4171.3   414.6  4264.6  408.37  4306.1  407.64  4337.2  404.79
  4439.2  399.59  4592.4  380.11  4675.6  377.97    4917  379.57  4978.5  379.86
  4988.7  375.14  4995.7  374.12  4998.5  373.62  5001.7  374.12  5003.8   374.4
  5009.1  379.55  5049.3  379.66  5054.4  378.31  5070.3  377.97  5162.2  384.11
  5228.9   385.8  5256.5  388.03  5294.8  388.21  5315.2  390.55  5357.6   392.3
  5386.7  389.81  5396.9  391.06  5417.3  390.51  5453.6  394.79  5790.9  405.98
#Mann= 6 ,-1 , 0
  4110.8     .16       0  4675.6      .1       0    4917     .16       0
  4995.7     .07       0  5001.7     .16       0  5228.9     .05       0
Bank Sta=4978.5,5009.1
XS Rating Curve= 0 ,0
Exp/Cntr=0.3,0.1

Type RM Length L Ch R = 1 ,2916    ,838,838,838
BEGIN DESCRIPTION:
UNT0163 IN SAND CR 4.0
END DESCRIPTION:
XS GIS Cut Line= 2
      3555111.04     10515268.37      3554094.05     10516497.09
#Sta/Elev= 30
    4048   421.1  4120.3   415.9  4177.6  408.85  4255.8  403.39  4369.1  399.41
  4397.7  396.83  4432.9  397.15  4461.5  395.26  4496.7  395.14  4710.3  380.91
  4809.3  375.66  4882.1  376.44  4973.5  377.77  4991.3  374.08    4994  373.58
  4997.3  374.08  5008.6  377.45  5088.2  377.38  5121.9  377.29  5193.6  380.34
  5285.4  386.51    5299  388.52  5313.4  389.42  5335.5  388.48  5352.1  390.64
  5377.2  394.02  5413.8  395.68  5506.1  397.45    5527  396.53    5643  397.89
#Mann= 7 ,-1 , 0
    4048     .05       0  4882.1     .16       0  4991.3     .07       0
  4997.3     .16       0  5088.2      .1       0  5352.1     .16       0
  5413.8     .05       0
Bank Sta=4973.5,5008.6
XS Rating Curve= 0 ,0
Exp/Cntr=0.3,0.1

Type RM Length L Ch R = 1 ,2078    ,1036,1036,1036
BEGIN DESCRIPTION:
UNT0163 IN SAND CR 2.0
END DESCRIPTION:
XS GIS Cut Line= 3
      3554496.44     10514362.15      3553760.34     10515799.63
      3553791.59     10516553.09
#Sta/Elev= 30
  3553.8  406.67  3664.3   401.7  3788.6  394.76  4010.7  386.61  4032.9  383.71
  4038.5  385.28  4055.1  382.32  4077.3  384.53  4082.9  382.41  4099.5  384.16
  4105.1  381.91  4121.7  384.91  4175.3  381.74  4214.3  380.32  4446.5  375.41
    4538  373.04  4582.4  376.44  4606.2  371.55  4623.8  371.51  4626.5  371.01
  4629.8  371.51  4835.1  373.49  4991.3  375.04  5013.8   375.2  5154.5  374.91
  5243.2  374.46  5346.4  375.21  5543.1  381.83  5811.9  397.55  5922.9   399.5
#Mann= 14 ,-1 , 0
  3553.8     .05       0  3664.3     .16       0  4175.3      .1       0
  4214.3     .16       0  4446.5      .1       0  4606.2     .05       0
  4623.8     .07       0  4629.8     .05       0  4835.1     .16       0
  5154.5      .1       0  5243.2     .16       0  5346.4      .1       0
  5543.1     .05       0  5811.9     .16       0
Bank Sta=4991.3,5013.8
XS Rating Curve= 0 ,0
Exp/Cntr=0.3,0.1

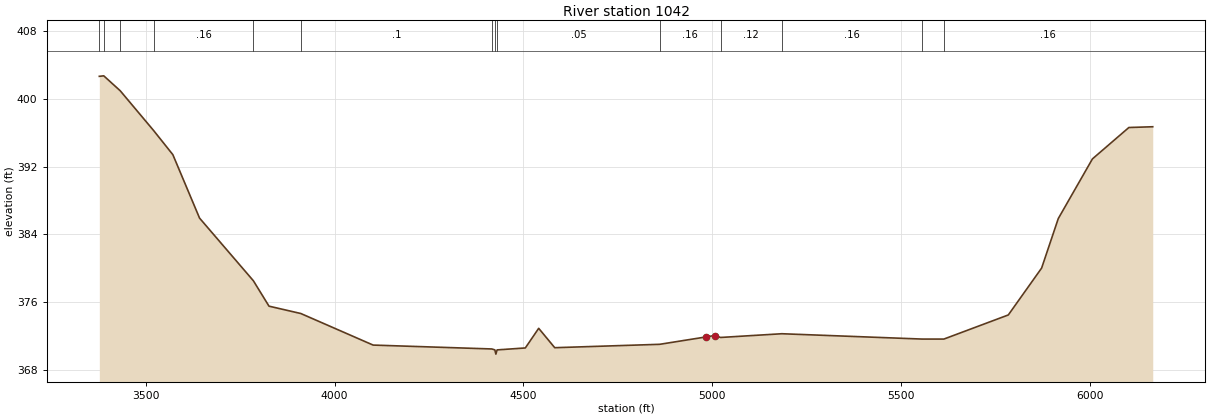
Type RM Length L Ch R = 1 ,1042    ,0,0,0
BEGIN DESCRIPTION:
UNT0163 IN SAND CR 1.0
END DESCRIPTION:
XS GIS Cut Line= 4
       3554253.4     10514417.67      3553229.09      10515466.3
       3553090.2     10515709.35      3553576.33       10516633.
#Sta/Elev= 30
  3376.8  402.68  3388.5  402.74    3432  400.98  3520.6  396.27  3571.5  393.42
  3642.2  385.92  3784.8  378.51  3826.1  375.51  3910.4  374.64  4101.8  370.91
  4416.3  370.45  4424.2  370.34  4426.9  369.84  4430.2  370.34  4504.9  370.57
  4540.3  372.89  4582.8   370.6  4860.7     371  4984.5  371.88  5006.1  372.04
  5022.1  371.81  5184.3  372.25  5555.5  371.62  5613.3  371.62  5783.9  374.47
  5872.1  380.01  5916.3  385.87  6006.7  392.92  6103.2  396.63  6166.4  396.72
#Mann= 14 ,-1 , 0
  3376.8      .1       0  3388.5     .05       0    3432      .1       0
  3520.6     .16       0  3784.8     .05       0  3910.4      .1       0
  4416.3     .05       0  4424.2     .07       0  4430.2     .05       0
  4860.7     .16       0  5022.1     .12       0  5184.3     .16       0
  5555.5      .1       0  5613.3     .16       0
Bank Sta=4984.5,5006.1
XS Rating Curve= 0 ,0
Exp/Cntr=0.3,0.1

Chan Stop Cuts=-1
Use User Specified Reach Order=0
Composite Channel Slope=5