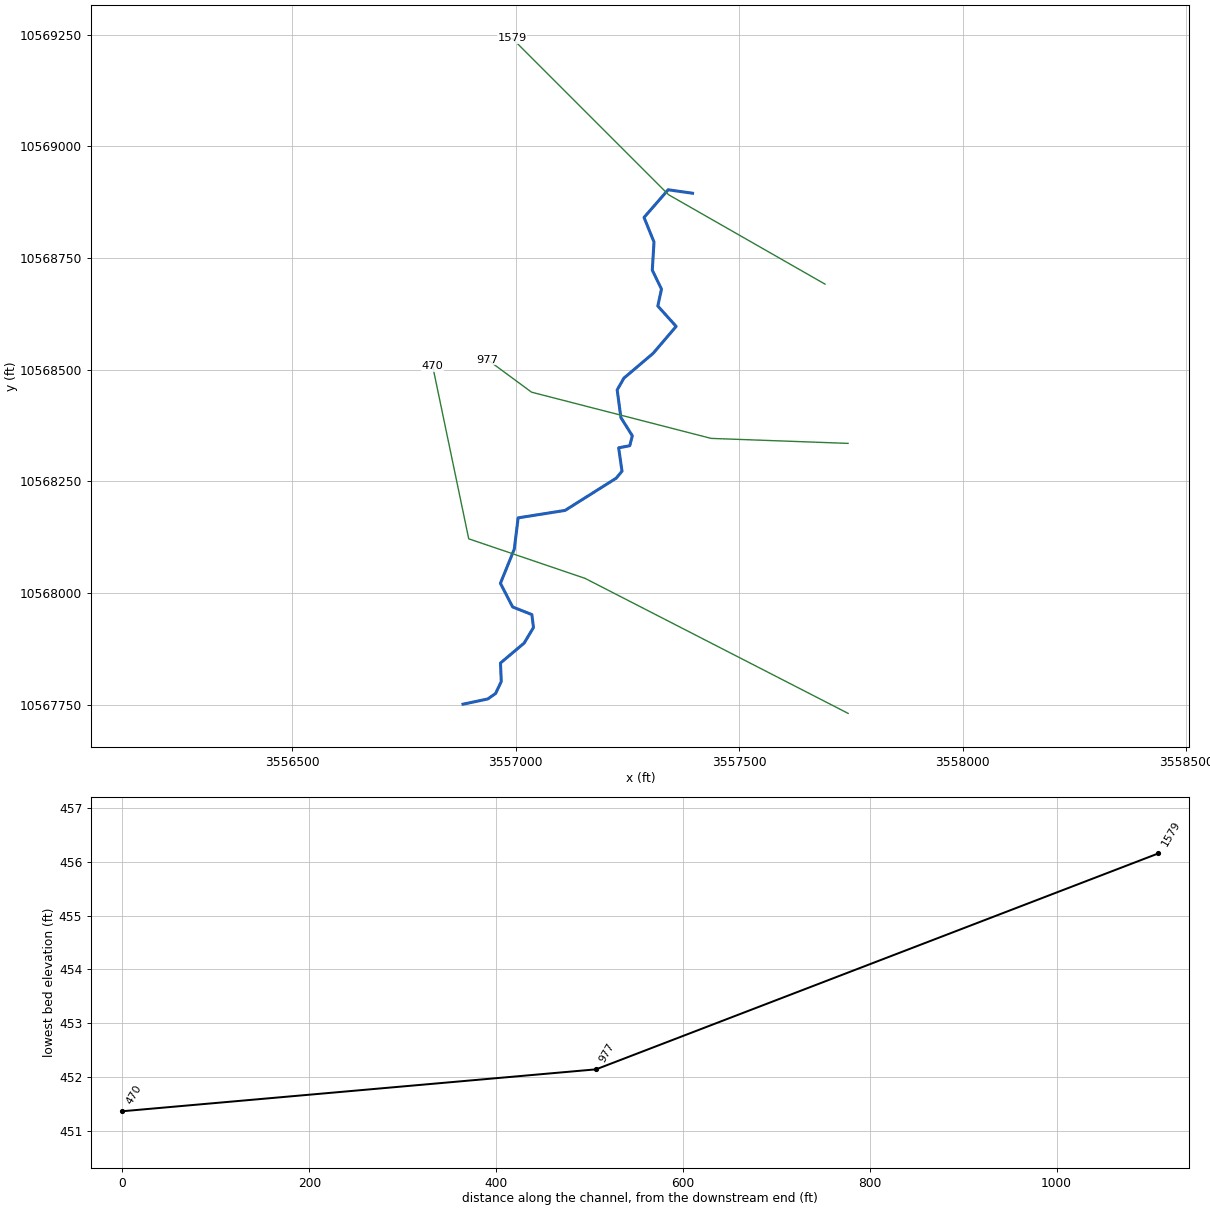
--- UNT01637 IN SAND CR.prj (project) ---

Proj Title=UNT01637 IN SAND CR Base Level Engineering
Current Plan=p01
Default Exp/Contr=0.3,0.1
English Units
Geom File=g01
Flow File=f01
Plan File=p01
BEGIN DESCRIPTION:
UNT01637 IN SAND CR
END DESCRIPTION:

--- UNT01637 IN SAND CR.p01 (plan) ---

Plan Title=Multiple Run
Short Identifier=Multiple
Geom File=g01
Flow File=f01
Subcritical Flow
K Sum by GR= 0
Std Step Tol= 0.01
Critical Tol= 0.01
Num of Std Step Trials= 20
Max Error Tol= 0.3
Flow Tol Ratio= 0.001
Split Flow NTrial= 30
Split Flow Tol= 0.02
Split Flow Ratio= 0.02
Log Output Level= 0
Friction Slope Method= 1
Unsteady Friction Slope Method= 2
Unsteady Bridges Friction Slope Method= 1
Parabolic Critical Depth
Global Vel Dist=  1 , 1 , 1
Global Log Level= 0
CheckData=True
Encroach Param= -1, 0, 0, 0
BEGIN DESCRIPTION:
Multiple Run
END DESCRIPTION:

--- UNT01637 IN SAND CR.f01 (steady flow) ---

Flow Title=Multiple
Number of Profiles=7
Profile Names=10-year,25-year,50-year,1pct_min,100-year,1pct_plu,500-year
River Rch & RM= UNT01637 IN SAND,Reach-1,1579
     411     531     624     536     725     981     975
Boundary for River Rch & Prof#=UNT01637 IN SAND,Reach-1,1
Up Type=0
Dn Type=3
Dn Slope=0.005
Boundary for River Rch & Prof#=UNT01637 IN SAND,Reach-1,2
Up Type=0
Dn Type=3
Dn Slope=0.005
Boundary for River Rch & Prof#=UNT01637 IN SAND,Reach-1,3
Up Type=0
Dn Type=3
Dn Slope=0.005
Boundary for River Rch & Prof#=UNT01637 IN SAND,Reach-1,4
Up Type=0
Dn Type=3
Dn Slope=0.005
Boundary for River Rch & Prof#=UNT01637 IN SAND,Reach-1,5
Up Type=0
Dn Type=3
Dn Slope=0.005
Boundary for River Rch & Prof#=UNT01637 IN SAND,Reach-1,6
Up Type=0
Dn Type=3
Dn Slope=0.005
Boundary for River Rch & Prof#=UNT01637 IN SAND,Reach-1,7
Up Type=0
Dn Type=3
Dn Slope=0.005

--- UNT01637 IN SAND CR.g01 (geometry) ---

Geom Title=Existing Conditions

River Reach=UNT01637 IN SAND,Reach-1
Reach XY= 30
      3557395.69     10568895.02      3557341.13     10568902.76
      3557287.16     10568840.85      3557309.47     10568785.94
      3557305.64     10568722.90      3557326.23     10568680.46
      3557317.97     10568642.65      3557359.05     10568597.07
      3557307.37     10568536.61      3557242.21     10568481.36
      3557227.04     10568454.92      3557235.42     10568393.00
      3557260.94     10568352.25      3557255.29     10568330.12
      3557230.34     10568325.34      3557237.87     10568273.04
      3557224.69     10568257.25      3557110.54     10568185.30
      3557005.45     10568168.64      3556996.79     10568098.50
      3556965.81     10568022.14      3556993.13     10567969.20
      3557036.17     10567952.26      3557039.78     10567923.24
      3557018.91     10567888.38      3556965.97     10567843.79
      3556967.67     10567802.31      3556954.92     10567775.50
      3556937.47     10567763.40      3556882.11     10567751.64

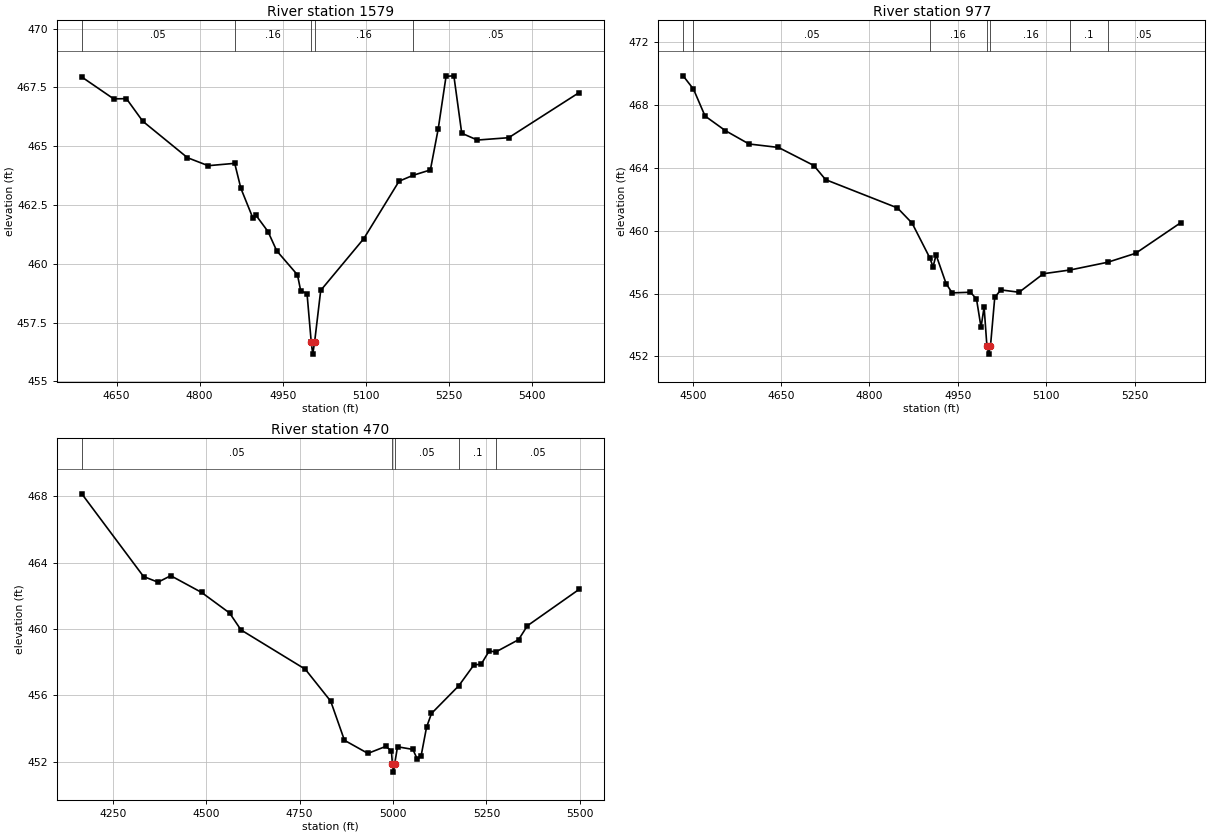
Type RM Length L Ch R = 1,1579,602,602,602
BEGIN DESCRIPTION:
UNT01637 IN SAND CR 3.0
END DESCRIPTION:
XS GIS Cut Line= 3
      3557692.11     10568691.64      3557342.11     10568891.64
      3556992.10     10569241.65
#Sta/Elev= 30
  4587.2  467.94  4644.8  467.01  4667.8  467.02  4697.3  466.06  4778.0  464.51
  4815.4  464.17  4863.3  464.27  4874.4  463.21  4896.0  461.95  4901.8  462.06
  4923.4  461.37  4939.2  460.55  4976.6  459.53  4982.4  458.86  4993.9  458.73
  5001.5  456.66  5004.2  456.16  5007.5  456.66  5018.6  458.87  5096.4  461.07
  5160.0  463.51  5185.2  463.76  5216.6  463.99  5230.7  465.73  5244.9  467.97
  5259.0  467.99  5273.2  465.55  5301.4  465.26  5358.0  465.36  5485.3  467.28
#Mann=5,-1,0
  4587.2    0.05       0  4863.3    0.16       0  5001.5    0.07       0
  5007.5    0.16       0  5185.2    0.05       0
Bank Sta=5001.5,5007.5
Exp/Cntr=0.3,0.1

Type RM Length L Ch R = 1,977,507,507,507
BEGIN DESCRIPTION:
UNT01637 IN SAND CR 2.0
END DESCRIPTION:
XS GIS Cut Line= 4
      3557743.79     10568335.27      3557437.30     10568346.44
      3557035.50     10568449.85      3556936.79     10568522.59
#Sta/Elev= 30
  4483.7  469.86  4501.3  469.01  4520.9  467.30  4555.4  466.37  4595.5  465.52
  4645.5  465.30  4705.5  464.15  4725.5  463.25  4847.4  461.45  4872.3  460.48
  4902.2  458.28  4907.9  457.70  4913.0  458.46  4930.0  456.63  4940.3  456.04
  4971.3  456.08  4981.6  455.65  4989.3  453.85  4994.5  455.14  4999.3  452.64
  5002.0  452.14  5005.3  452.64  5012.6  455.76  5022.9  456.23  5053.9  456.08
  5095.2  457.26  5140.8  457.50  5204.3  457.99  5251.7  458.56  5327.9  460.50
#Mann=7,-1,0
  4483.7     0.1       0  4501.3    0.05       0  4902.2    0.16       0
  4999.3    0.07       0  5005.3    0.16       0  5140.8     0.1       0
  5204.3    0.05       0
Bank Sta=4999.3,5005.3
Exp/Cntr=0.3,0.1

Type RM Length L Ch R = 1,470,0,0,0
BEGIN DESCRIPTION:
UNT01637 IN SAND CR 1.0
END DESCRIPTION:
XS GIS Cut Line= 4
      3557743.82     10567731.11      3557155.29     10568033.19
      3556894.88     10568121.73      3556814.36     10568507.33
#Sta/Elev= 30
  4167.5  468.15  4332.7  463.16  4371.4  462.82  4405.5  463.21  4488.0  462.20
  4562.8  460.96  4593.3  459.94  4765.2  457.57  4833.3  455.64  4870.1  453.28
  4932.8  452.49  4980.3  452.91  4995.6  452.65  4998.4  451.86  5001.1  451.36
  5004.4  451.86  5012.0  452.89  5053.1  452.73  5064.8  452.15  5075.3  452.36
  5089.7  454.07  5102.9  454.90  5175.9  456.57  5216.4  457.83  5235.8  457.87
  5257.2  458.67  5274.9  458.61  5335.8  459.35  5359.4  460.19  5498.0  462.39
#Mann=5,-1,0
  4167.5    0.05       0  4998.4    0.03       0  5004.4    0.05       0
  5175.9     0.1       0  5274.9    0.05       0
Bank Sta=4998.4,5004.4
Exp/Cntr=0.3,0.1

Chan Stop Cuts=-1