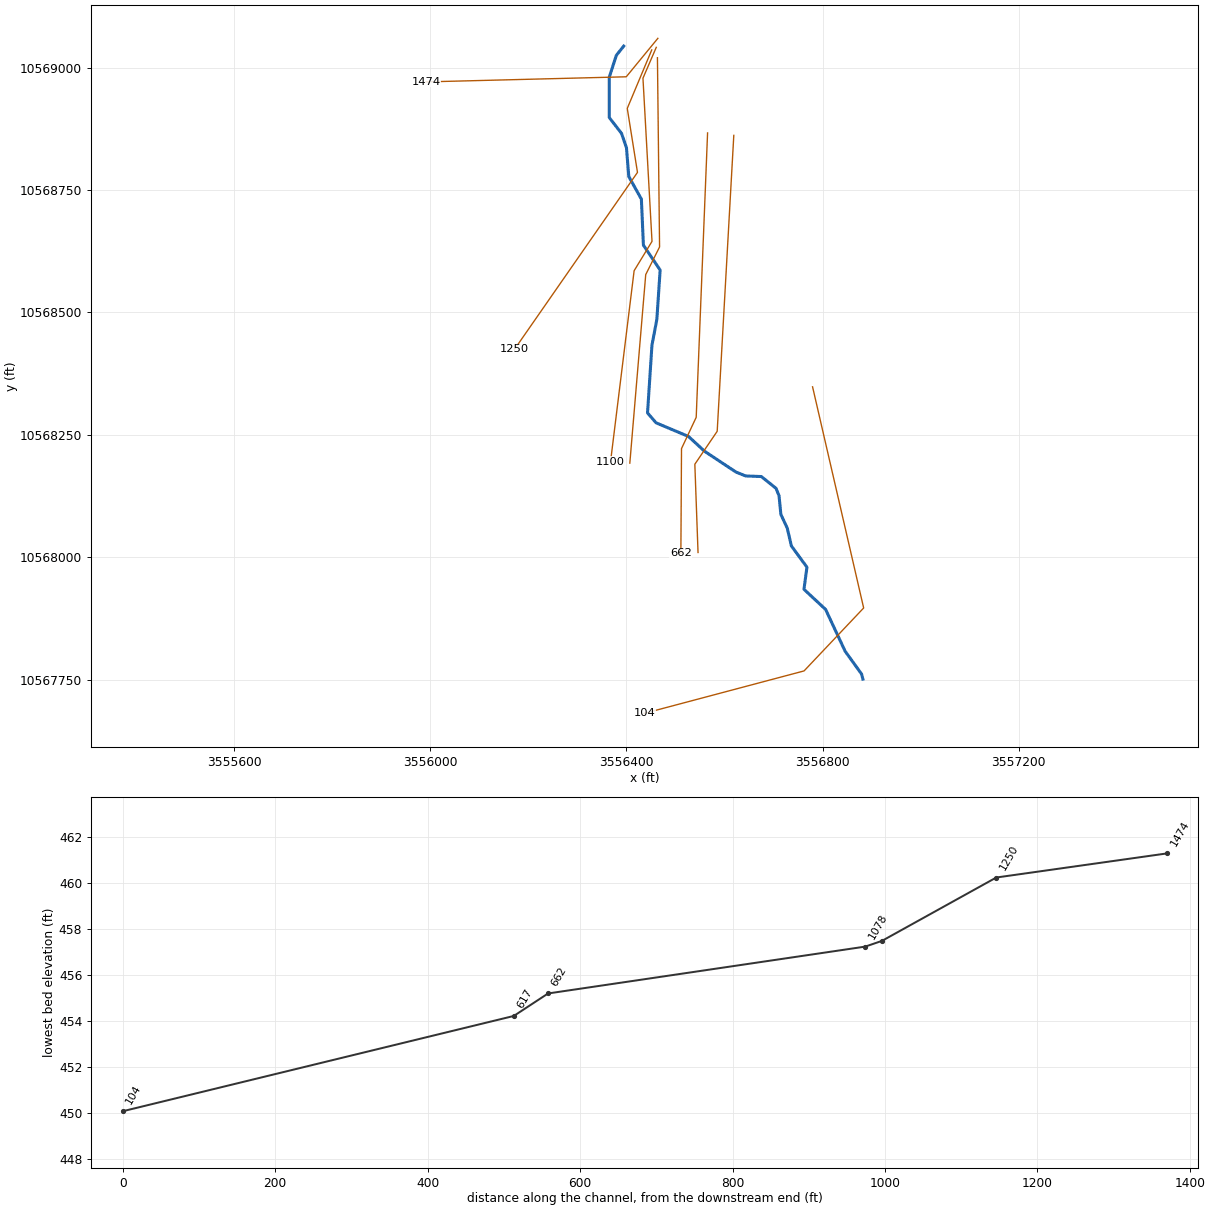
--- UNT01638 IN SAND CR.prj (project) ---

Proj Title=UNT01638 IN SAND CR Base Level Engineering
Current Plan=p01
Default Exp/Contr=0.3,0.1
English Units
Geom File=g01
Flow File=f01
Plan File=p01
BEGIN DESCRIPTION:
UNT01638 IN SAND CR
END DESCRIPTION:

--- UNT01638 IN SAND CR.p01 (plan) ---

Plan Title=Multiple Run
Short Identifier=Multiple
Geom File=g01
Flow File=f01
Subcritical Flow
K Sum by GR= 0
Std Step Tol= 0.01
Critical Tol= 0.01
Num of Std Step Trials= 20
Max Error Tol= 0.3
Flow Tol Ratio= 0.001
Split Flow NTrial= 30
Split Flow Tol= 0.02
Split Flow Ratio= 0.02
Log Output Level= 0
Friction Slope Method= 1
Unsteady Friction Slope Method= 2
Unsteady Bridges Friction Slope Method= 1
Parabolic Critical Depth
Global Vel Dist=  1 , 1 , 1
Global Log Level= 0
CheckData=True
Encroach Param= -1, 0, 0, 0
BEGIN DESCRIPTION:
Multiple Run
END DESCRIPTION:

--- UNT01638 IN SAND CR.f01 (steady flow) ---

Flow Title=Multiple
Number of Profiles=7
Profile Names=10-year,25-year,50-year,1pct_min,100-year,1pct_plu,500-year
River Rch & RM= UNT01638 IN SAND,Reach-1,1474
     313     397     460     391     528     715     694
Boundary for River Rch & Prof#=UNT01638 IN SAND,Reach-1,1
Up Type=0
Dn Type=3
Dn Slope=0.005
Boundary for River Rch & Prof#=UNT01638 IN SAND,Reach-1,2
Up Type=0
Dn Type=3
Dn Slope=0.005
Boundary for River Rch & Prof#=UNT01638 IN SAND,Reach-1,3
Up Type=0
Dn Type=3
Dn Slope=0.005
Boundary for River Rch & Prof#=UNT01638 IN SAND,Reach-1,4
Up Type=0
Dn Type=3
Dn Slope=0.005
Boundary for River Rch & Prof#=UNT01638 IN SAND,Reach-1,5
Up Type=0
Dn Type=3
Dn Slope=0.005
Boundary for River Rch & Prof#=UNT01638 IN SAND,Reach-1,6
Up Type=0
Dn Type=3
Dn Slope=0.005
Boundary for River Rch & Prof#=UNT01638 IN SAND,Reach-1,7
Up Type=0
Dn Type=3
Dn Slope=0.005

--- UNT01638 IN SAND CR.g01 (geometry) ---

Geom Title=Existing Conditions

River Reach=UNT01638 IN SAND,Reach-1
Reach XY= 30
      3556394.49     10569043.71      3556379.50     10569024.98
      3556365.06     10568980.27      3556365.05     10568897.88
      3556390.05     10568865.58      3556400.10     10568836.27
      3556404.89     10568777.48      3556430.51     10568731.42
      3556434.68     10568637.38      3556468.77     10568586.61
      3556462.07     10568485.93      3556452.08     10568433.16
      3556443.06     10568294.96      3556460.42     10568274.82
      3556526.66     10568246.93      3556559.19     10568216.83
      3556623.29     10568174.35      3556643.08     10568166.35
      3556675.14     10568165.12      3556704.92     10568141.17
      3556711.20     10568125.98      3556714.89     10568087.91
      3556727.93     10568059.88      3556736.37     10568023.41
      3556768.08     10567980.10      3556762.01     10567935.01
      3556806.15     10567893.81      3556846.00     10567808.48
      3556879.43     10567762.07      3556882.11     10567751.64

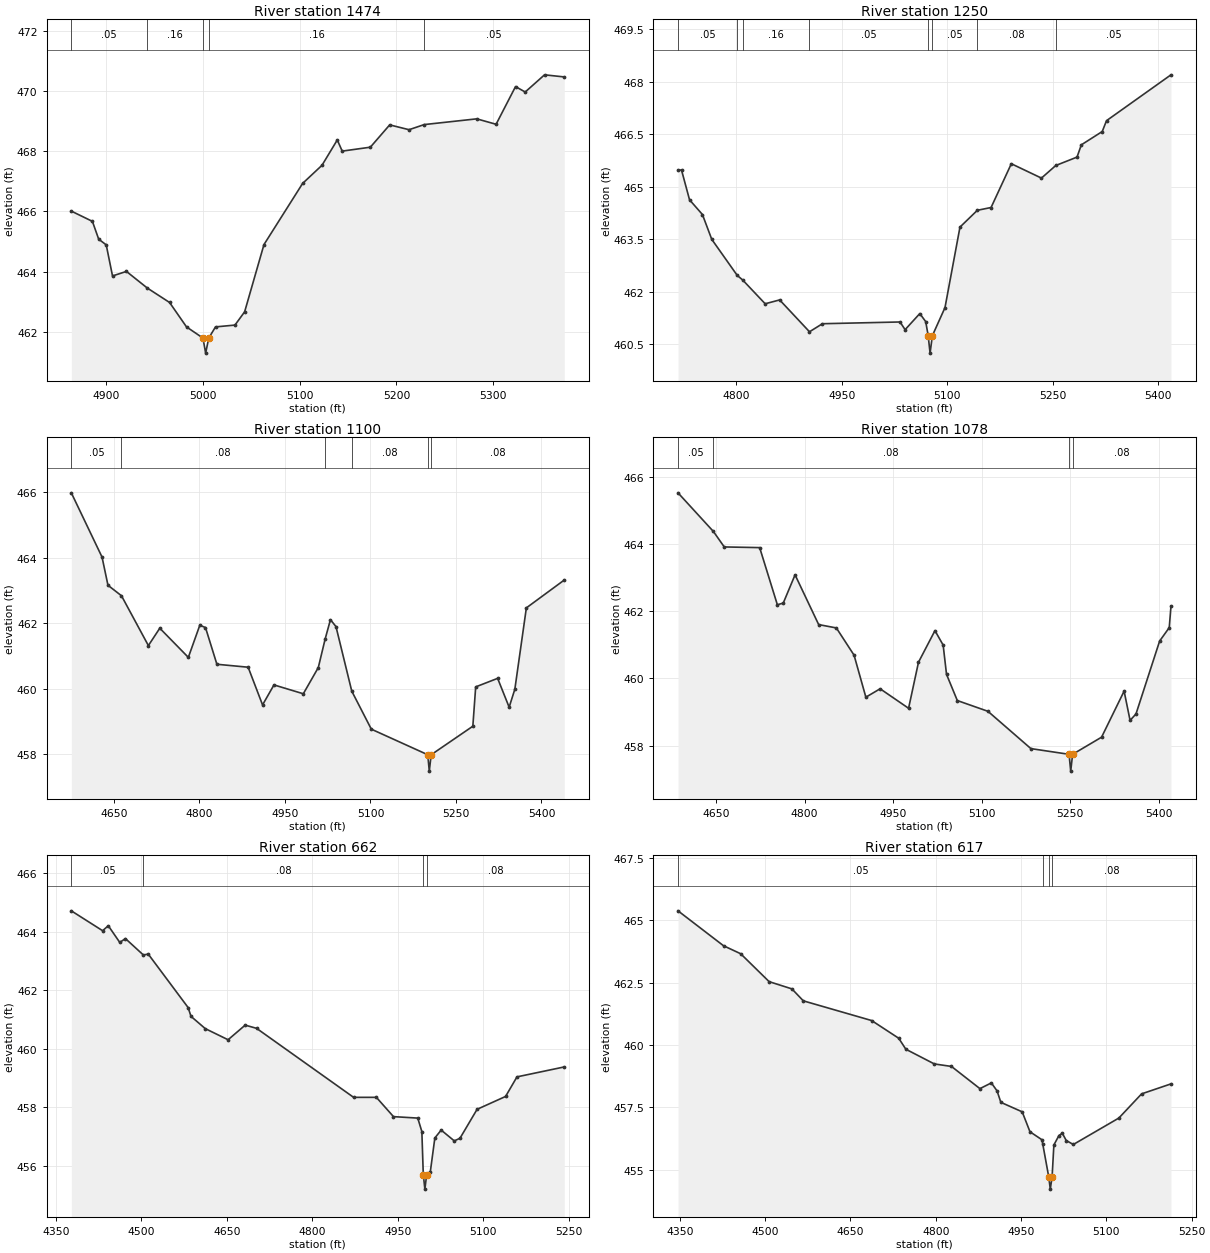
Type RM Length L Ch R = 1,1474,224,224,224
BEGIN DESCRIPTION:
UNT01638 IN SAND CR 2.2
END DESCRIPTION:
XS GIS Cut Line= 3
      3556464.13     10569059.58      3556399.68     10568981.09
      3555991.67     10568970.68
#Sta/Elev= 30
  4863.8  466.01  4885.6  465.67  4892.1  465.08  4899.9  464.89  4906.4  463.86
  4920.8  464.01  4942.3  463.46  4965.4  462.98  4982.9  462.17  4999.9  461.80
  5002.7  461.30  5005.9  461.80  5012.9  462.17  5033.0  462.23  5043.0  462.67
  5063.0  464.90  5103.0  466.93  5123.0  467.53  5138.8  468.37  5143.9  468.00
  5173.0  468.13  5193.0  468.87  5213.0  468.71  5228.7  468.88  5283.0  469.07
  5303.0  468.89  5323.1  470.14  5333.1  469.96  5353.1  470.53  5373.5  470.46
#Mann=5,-1,0
  4863.8    0.05       0  4942.3    0.16       0  4999.9    0.07       0
  5005.9    0.16       0  5228.7    0.05       0
Bank Sta=4999.9,5005.9
Exp/Cntr=0.3,0.1

Type RM Length L Ch R = 1,1250,150,150,150
BEGIN DESCRIPTION:
UNT01638 IN SAND CR 2.11
END DESCRIPTION:
XS GIS Cut Line= 4
      3556451.66     10569035.93      3556401.76     10568916.60
      3556422.59     10568785.96      3556172.20     10568425.29
#Sta/Elev= 30
  4717.2  465.48  4722.2  465.48  4733.6  464.63  4751.9  464.21  4765.2  463.50
  4801.4  462.47  4809.1  462.34  4841.1  461.66  4861.7  461.77  4904.1  460.86
  4922.5  461.09  5032.8  461.14  5040.0  460.92  5060.9  461.38  5069.3  461.15
  5072.8  460.75  5075.5  460.25  5078.8  460.75  5096.7  461.55  5118.0  463.85
  5142.7  464.33  5162.2  464.41  5191.0  465.66  5233.8  465.25  5254.2  465.61
  5284.4  465.85  5290.5  466.20  5320.2  466.58  5326.3  466.89  5417.9  468.20
#Mann=8,-1,0
  4717.2    0.05       0  4801.4    0.08       0  4809.1    0.16       0
  4904.1    0.05       0  5072.8    0.04       0  5078.8    0.05       0
  5142.7    0.08       0  5254.2    0.05       0
Bank Sta=5072.8,5078.8
Exp/Cntr=0.3,0.1

Type RM Length L Ch R = 1,1100,22,22,22
BEGIN DESCRIPTION:
UNT01638 IN SAND CR 2.1
END DESCRIPTION:
XS GIS Cut Line= 5
      3556460.88     10569041.16      3556433.76     10568978.22
      3556452.20     10568645.14      3556415.74     10568585.24
      3556367.69     10568195.64
#Sta/Elev= 30
  4575.2  465.98  4629.1  464.02  4639.5  463.16  4663.2  462.84  4710.4  461.32
  4730.4  461.85  4780.5  460.96  4800.6  461.94  4810.6  461.87  4830.6  460.75
  4885.4  460.66  4910.7  459.51  4930.7  460.12  4982.2  459.85  5008.5  460.65
  5020.5  461.52  5029.8  462.11  5039.5  461.90  5067.2  459.93  5101.5  458.77
  5200.5  457.99  5203.2  457.49  5206.5  457.99  5279.6  458.86  5284.6  460.06
  5323.1  460.32  5343.3  459.44  5353.3  459.99  5373.5  462.47  5440.0  463.32
#Mann=6,-1,0
  4575.2    0.05       0  4663.2    0.08       0  5020.5    0.05       0
  5067.2    0.08       0  5200.5    0.07       0  5206.5    0.08       0
Bank Sta=5200.5,5206.5
Exp/Cntr=0.3,0.1

Type RM Length L Ch R = 1,1078,416,416,416
BEGIN DESCRIPTION:
UNT01638 IN SAND CR 2.0
END DESCRIPTION:
XS GIS Cut Line= 4
      3556463.27     10569020.00      3556467.61     10568633.74
      3556439.39     10568577.32      3556406.97     10568192.55
#Sta/Elev= 30
  4585.3  465.52  4645.3  464.37  4663.7  463.91  4723.7  463.89  4753.7  462.19
  4763.7  462.24  4783.7  463.08  4823.7  461.60  4853.7  461.50  4883.7  460.69
  4903.7  459.44  4927.9  459.69  4976.1  459.11  4992.9  460.48  5020.8  461.42
  5034.7  460.99  5040.4  460.12  5058.7  459.34  5110.6  459.02  5183.4  457.91
  5248.1  457.74  5250.9  457.24  5254.1  457.74  5303.2  458.25  5341.4  459.62
  5351.5  458.75  5361.5  458.94  5401.6  461.11  5417.9  461.51  5420.8  462.14
#Mann=4,-1,0
  4585.3    0.05       0  4645.3    0.08       0  5248.1    0.07       0
  5254.1    0.08       0
Bank Sta=5248.1,5254.1
Exp/Cntr=0.3,0.1

Type RM Length L Ch R = 1,662,45,45,45
BEGIN DESCRIPTION:
UNT01638 IN SAND CR 2.3
END DESCRIPTION:
XS GIS Cut Line= 4
      3556565.48     10568866.53      3556542.30     10568286.02
      3556512.35     10568222.22      3556511.05     10568008.67
#Sta/Elev= 30
  4376.9  464.72  4431.8  464.04  4441.8  464.21  4461.9  463.64  4471.9  463.77
  4503.3  463.21  4511.9  463.24  4581.9  461.41  4586.9  461.11  4612.0  460.69
  4652.0  460.31  4682.0  460.81  4702.0  460.70  4872.2  458.34  4912.2  458.34
  4942.2  457.68  4984.8  457.63  4992.0  457.17  4994.5  455.70  4997.3  455.20
  5000.5  455.70  5006.9  455.80  5014.8  456.95  5025.9  457.22  5048.9  456.85
  5058.9  456.94  5088.9  457.93  5138.9  458.37  5158.9  459.04  5241.9  459.38
#Mann=4,-1,0
  4376.9    0.05       0  4503.3    0.08       0  4994.5    0.07       0
  5000.5    0.08       0
Bank Sta=4994.5,5000.5
Exp/Cntr=0.3,0.1

Type RM Length L Ch R = 1,617,513,513,513
BEGIN DESCRIPTION:
UNT01638 IN SAND CR 2.4
END DESCRIPTION:
XS GIS Cut Line= 4
      3556618.95     10568861.56      3556585.10     10568257.52
      3556539.52     10568190.25      3556546.04     10568010.11
#Sta/Elev= 30
  4347.0  465.38  4427.0  463.98  4457.1  463.66  4507.2  462.54  4547.2  462.25
  4567.3  461.77  4687.4  460.98  4735.0  460.27  4747.5  459.83  4797.6  459.24
  4827.7  459.14  4877.7  458.25  4897.8  458.48  4907.8  458.16  4914.5  457.70
  4952.0  457.32  4965.7  456.52  4986.7  456.20  4988.3  456.01  4998.6  454.72
  5001.4  454.22  5004.6  454.72  5007.7  455.99  5016.6  456.37  5022.6  456.46
  5029.4  456.17  5041.9  456.01  5121.9  457.07  5161.9  458.04  5213.5  458.44
#Mann=4,-1,0
  4347.0    0.05       0  4988.3    0.08       0  4998.6    0.07       0
  5004.6    0.08       0
Bank Sta=4998.6,5004.6
Exp/Cntr=0.3,0.1

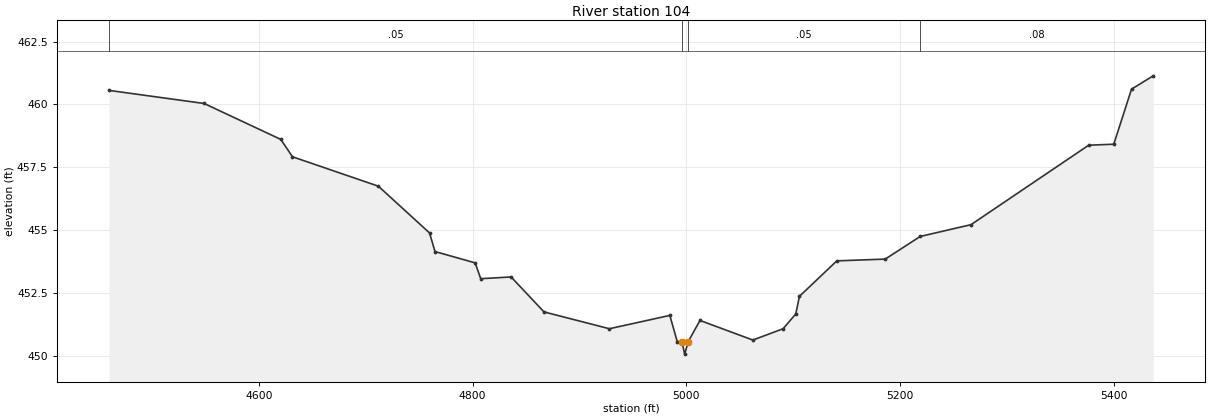
Type RM Length L Ch R = 1,104,0,0,0
BEGIN DESCRIPTION:
UNT01638 IN SAND CR 1.0
END DESCRIPTION:
XS GIS Cut Line= 4
      3556779.54     10568348.24      3556883.71     10567896.84
      3556762.18     10567768.37      3556436.41     10567681.73
#Sta/Elev= 30
  4459.8  460.56  4548.7  460.04  4620.5  458.61  4631.4  457.92  4711.8  456.75
  4759.7  454.89  4764.8  454.15  4802.4  453.70  4807.6  453.07  4836.0  453.14
  4866.8  451.75  4928.0  451.08  4984.6  451.61  4991.5  450.57  4995.8  450.57
  4998.5  450.07  5001.8  450.57  5012.8  451.41  5062.3  450.63  5090.6  451.08
  5102.5  451.67  5105.9  452.37  5140.9  453.78  5186.2  453.85  5218.9  454.75
  5266.5  455.22  5376.6  458.38  5400.1  458.42  5416.7  460.61  5437.0  461.14
#Mann=4,-1,0
  4459.8    0.05       0  4995.8    0.03       0  5001.8    0.05       0
  5218.9    0.08       0
Bank Sta=4995.8,5001.8
Exp/Cntr=0.3,0.1

Chan Stop Cuts=-1