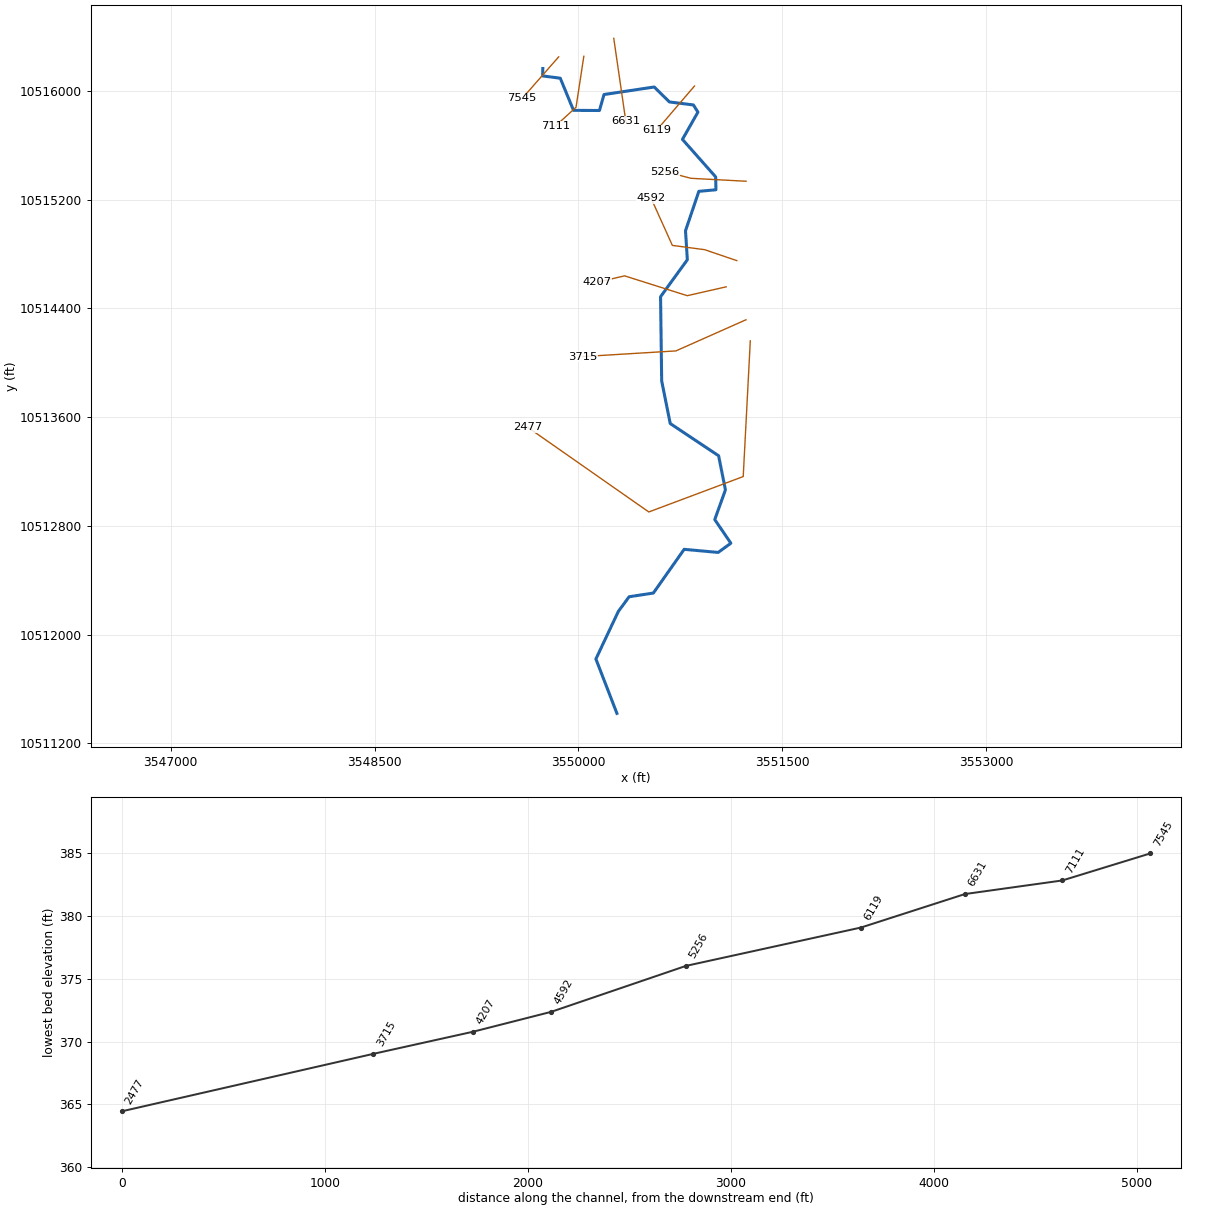
--- UNT0164 IN SAND CR.prj (project) ---

Proj Title=UNT0164 IN SAND CR Base Level Engineering
Current Plan=p01
Default Exp/Contr=0.3,0.1
English Units
Geom File=g01
Flow File=f01
Plan File=p01
BEGIN DESCRIPTION:
UNT0164 IN SAND CR
END DESCRIPTION:

--- UNT0164 IN SAND CR.p01 (plan) ---

Plan Title=Multiple Run
Short Identifier=Multiple
Geom File=g01
Flow File=f01
Subcritical Flow
K Sum by GR= 0
Std Step Tol= 0.01
Critical Tol= 0.01
Num of Std Step Trials= 20
Max Error Tol= 0.3
Flow Tol Ratio= 0.001
Split Flow NTrial= 30
Split Flow Tol= 0.02
Split Flow Ratio= 0.02
Log Output Level= 0
Friction Slope Method= 1
Unsteady Friction Slope Method= 2
Unsteady Bridges Friction Slope Method= 1
Parabolic Critical Depth
Global Vel Dist=  1 , 1 , 1
Global Log Level= 0
CheckData=True
Encroach Param= -1, 0, 0, 0
BEGIN DESCRIPTION:
Multiple Run
END DESCRIPTION:

--- UNT0164 IN SAND CR.f01 (steady flow) ---

Flow Title=Multiple
Number of Profiles=7
Profile Names=10-year,25-year,50-year,1pct_min,100-year,1pct_plu,500-year
River Rch & RM= UNT0164 IN SAND ,Reach-1,7545
     554     731     869     756    1023    1383    1409
River Rch & RM= UNT0164 IN SAND ,Reach-1,4207
     883    1195    1447    1278    1728    2337    2459
Boundary for River Rch & Prof#=UNT0164 IN SAND ,Reach-1,1
Up Type=0
Dn Type=3
Dn Slope=0.005
Boundary for River Rch & Prof#=UNT0164 IN SAND ,Reach-1,2
Up Type=0
Dn Type=3
Dn Slope=0.005
Boundary for River Rch & Prof#=UNT0164 IN SAND ,Reach-1,3
Up Type=0
Dn Type=3
Dn Slope=0.005
Boundary for River Rch & Prof#=UNT0164 IN SAND ,Reach-1,4
Up Type=0
Dn Type=3
Dn Slope=0.005
Boundary for River Rch & Prof#=UNT0164 IN SAND ,Reach-1,5
Up Type=0
Dn Type=3
Dn Slope=0.005
Boundary for River Rch & Prof#=UNT0164 IN SAND ,Reach-1,6
Up Type=0
Dn Type=3
Dn Slope=0.005
Boundary for River Rch & Prof#=UNT0164 IN SAND ,Reach-1,7
Up Type=0
Dn Type=3
Dn Slope=0.005

--- UNT0164 IN SAND CR.g01 (geometry) ---

Geom Title=Existing Conditions

River Reach=UNT0164 IN SAND ,Reach-1
Reach XY= 30
      3549737.51     10516164.00      3549736.55     10516109.57
      3549866.10     10516092.81      3549963.42     10515856.36
      3550154.39     10515855.25      3550187.91     10515972.71
      3550557.10     10516028.20      3550669.33     10515918.01
      3550845.16     10515896.08      3550878.72     10515843.22
      3550764.87     10515642.81      3551009.34     10515366.62
      3551011.22     10515272.18      3550885.50     10515260.66
      3550787.33     10514970.61      3550800.90     10514757.20
      3550603.80     10514485.61      3550612.03     10513866.02
      3550675.08     10513552.56      3551030.80     10513315.57
      3551080.99     10513064.52      3551002.51     10512846.01
      3551121.11     10512672.11      3551027.62     10512604.30
      3550777.47     10512627.26      3550550.91     10512305.64
      3550372.52     10512278.30      3550293.09     10512170.23
      3550128.16     10511820.51      3550282.74     10511420.46

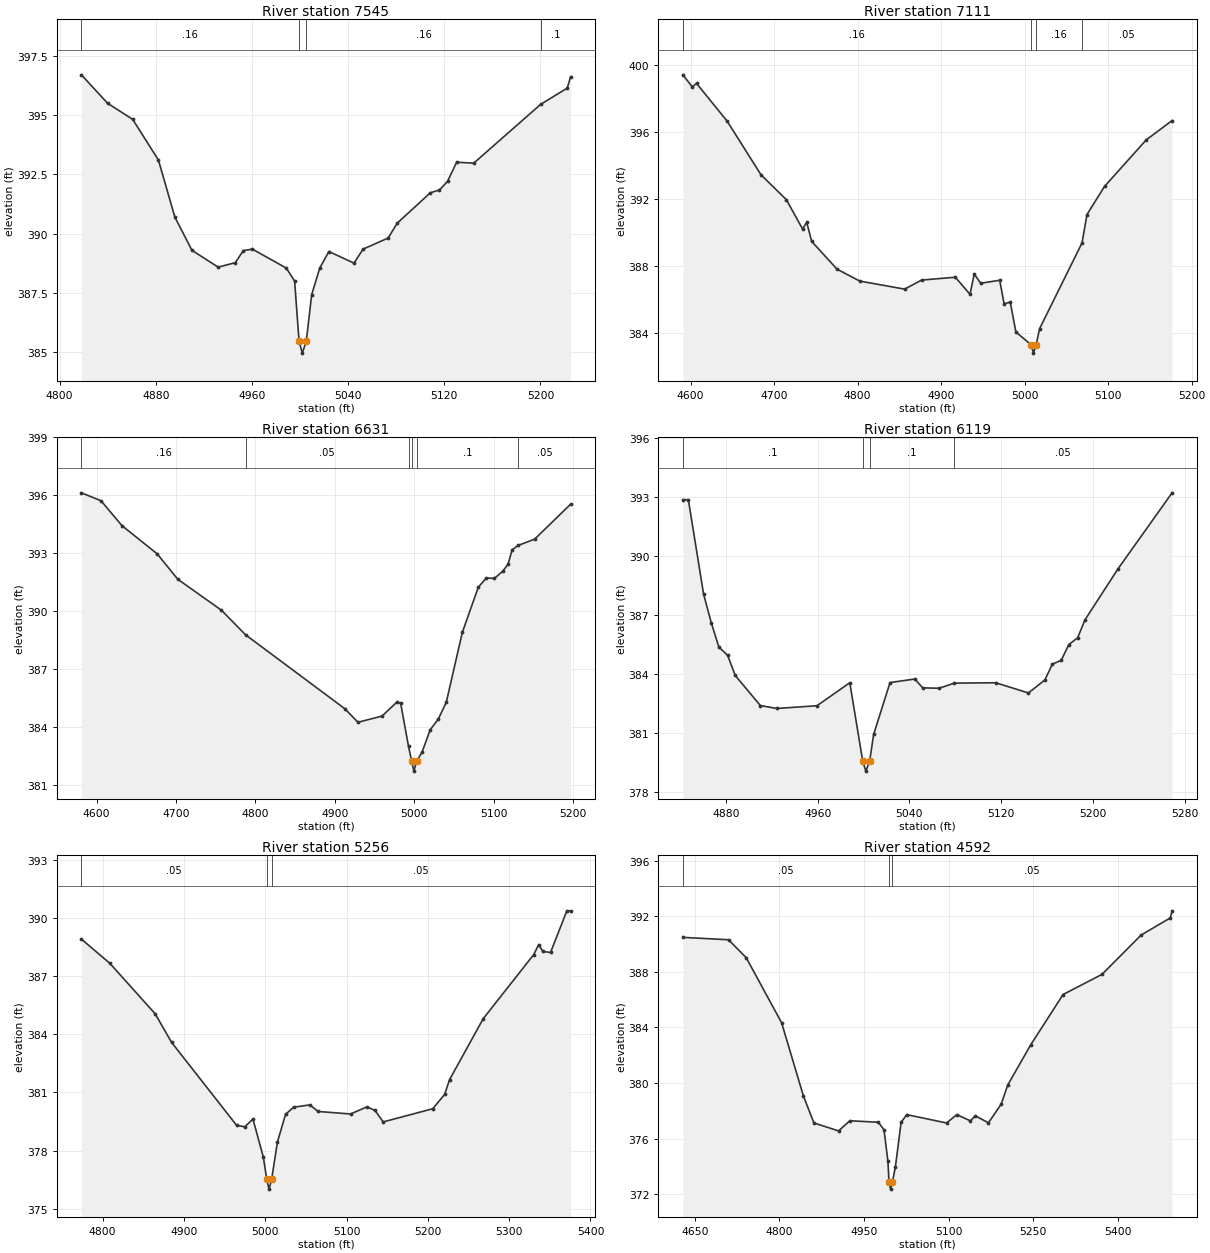
Type RM Length L Ch R = 1,7545,434,434,434
BEGIN DESCRIPTION:
UNT0691 IN SAND CR 6.0
END DESCRIPTION:
XS GIS Cut Line= 2
      3549854.28     10516249.80      3549585.90     10515943.82
#Sta/Elev= 30
  4818.1  396.70  4839.9  395.50  4860.8  394.82  4882.2  393.10  4895.9  390.69
  4910.1  389.29  4931.9  388.58  4946.2  388.77  4952.8  389.28  4960.4  389.34
  4988.6  388.54  4995.5  387.99  4999.2  385.45  5001.9  384.95  5005.2  385.45
  5009.7  387.42  5016.4  388.54  5024.0  389.24  5044.9  388.75  5052.4  389.34
  5073.3  389.81  5080.9  390.44  5108.4  391.72  5116.0  391.84  5122.7  392.20
  5130.3  393.01  5144.5  392.97  5200.1  395.45  5222.3  396.14  5225.1  396.62
#Mann=4,-1,0
  4818.1    0.16       0  4999.2    0.07       0  5005.2    0.16       0
  5200.1     0.1       0
Bank Sta=4999.2,5005.2
Exp/Cntr=0.3,0.1

Type RM Length L Ch R = 1,7111,480,480,480
BEGIN DESCRIPTION:
UNT0691 IN SAND CR 5.01
END DESCRIPTION:
XS GIS Cut Line= 3
      3550039.38     10516254.12      3549982.09     10515879.17
      3549829.78     10515739.88
#Sta/Elev= 30
  4590.8  399.41  4602.1  398.69  4607.2  398.90  4643.9  396.64  4684.4  393.44
  4714.7  391.96  4734.1  390.21  4739.1  390.61  4745.0  389.47  4775.4  387.81
  4802.6  387.10  4856.3  386.62  4876.6  387.16  4917.0  387.33  4934.6  386.31
  4939.6  387.52  4947.4  386.97  4970.1  387.15  4975.4  385.75  4982.8  385.84
  4989.5  384.06  5007.7  383.30  5010.5  382.80  5013.7  383.30  5017.9  384.26
  5068.7  389.38  5074.6  391.07  5095.6  392.75  5145.6  395.53  5176.5  396.68
#Mann=4,-1,0
  4590.8    0.16       0  5007.7    0.07       0  5013.7    0.16       0
  5068.7    0.05       0
Bank Sta=5007.7,5013.7
Exp/Cntr=0.3,0.1

Type RM Length L Ch R = 1,6631,512,512,512
BEGIN DESCRIPTION:
UNT0691 IN SAND CR 5.0
END DESCRIPTION:
XS GIS Cut Line= 2
      3550259.60     10516386.09      3550348.14     10515776.78
#Sta/Elev= 30
  4580.9  396.13  4605.6  395.72  4632.0  394.43  4676.3  392.97  4702.1  391.66
  4757.2  390.05  4787.5  388.78  4912.5  384.95  4929.0  384.25  4959.3  384.57
  4977.6  385.28  4982.7  385.24  4992.6  383.00  4996.7  382.22  4999.4  381.72
  5002.7  382.22  5009.8  382.72  5019.9  383.86  5030.0  384.41  5040.1  385.28
  5060.3  388.90  5080.5  391.25  5090.6  391.72  5100.7  391.70  5110.9  392.06
  5117.9  392.43  5123.0  393.18  5130.8  393.41  5151.3  393.73  5196.6  395.54
#Mann=6,-1,0
  4580.9    0.16       0  4787.5    0.05       0  4992.6     0.1       0
  4996.7    0.07       0  5002.7     0.1       0  5130.8    0.05       0
Bank Sta=4996.7,5002.7
Exp/Cntr=0.3,0.1

Type RM Length L Ch R = 1,6119,863,863,863
BEGIN DESCRIPTION:
UNT0691 IN SAND CR 3.0
END DESCRIPTION:
XS GIS Cut Line= 2
      3550853.38     10516035.36      3550575.90     10515711.21
#Sta/Elev= 30
  4842.4  392.88  4847.2  392.88  4860.5  388.07  4867.2  386.61  4873.8  385.38
  4881.5  384.95  4888.1  383.93  4910.0  382.40  4924.3  382.25  4959.4  382.39
  4988.0  383.56  4999.3  379.56  5002.0  379.06  5005.3  379.56  5008.8  380.93
  5023.1  383.57  5044.7  383.75  5051.6  383.30  5065.9  383.28  5079.2  383.54
  5115.3  383.56  5143.8  383.04  5158.1  383.70  5164.7  384.51  5172.4  384.70
  5179.0  385.50  5186.7  385.85  5193.2  386.77  5221.8  389.35  5269.1  393.23
#Mann=4,-1,0
  4842.4     0.1       0  4999.3    0.07       0  5005.3     0.1       0
  5079.2    0.05       0
Bank Sta=4999.3,5005.3
Exp/Cntr=0.3,0.1

Type RM Length L Ch R = 1,5256,664,664,664
BEGIN DESCRIPTION:
UNT0691 IN SAND CR 2.0
END DESCRIPTION:
XS GIS Cut Line= 3
      3551232.81     10515334.81      3550827.02     10515356.51
      3550638.18     10515406.43
#Sta/Elev= 30
  4773.9  388.92  4808.9  387.67  4864.7  385.06  4884.8  383.59  4964.9  379.30
  4974.9  379.23  4984.9  379.63  4997.7  377.66  5001.9  376.51  5004.7  376.01
  5007.9  376.51  5015.0  378.44  5025.0  379.87  5035.0  380.24  5055.0  380.36
  5065.0  380.02  5105.1  379.89  5125.1  380.26  5135.1  380.07  5145.1  379.48
  5206.0  380.16  5220.7  380.90  5226.7  381.66  5268.1  384.81  5330.2  388.12
  5336.3  388.63  5341.5  388.28  5350.9  388.23  5371.0  390.38  5375.6  390.38
#Mann=3,-1,0
  4773.9    0.05       0  5001.9    0.03       0  5007.9    0.05       0
Bank Sta=5001.9,5007.9
Exp/Cntr=0.3,0.1

Type RM Length L Ch R = 1,4592,385,385,385
BEGIN DESCRIPTION:
UNT0691 IN SAND CR 1.0
END DESCRIPTION:
XS GIS Cut Line= 4
      3551164.71     10514750.84      3550927.74     10514831.57
      3550690.76     10514862.82      3550535.06     10515207.94
#Sta/Elev= 30
  4628.6  390.47  4709.6  390.30  4741.0  389.01  4803.7  384.34  4842.6  379.05
  4861.1  377.12  4904.8  376.55  4925.0  377.28  4975.4  377.17  4985.5  376.63
  4992.4  374.37  4994.4  372.86  4997.2  372.36  5000.4  372.86  5005.7  373.96
  5015.8  377.16  5025.8  377.72  5096.4  377.12  5114.8  377.72  5138.6  377.27
  5147.6  377.63  5170.8  377.13  5193.5  378.48  5204.9  379.84  5245.6  382.73
  5303.2  386.36  5372.3  387.81  5441.7  390.64  5493.4  391.87  5496.6  392.38
#Mann=3,-1,0
  4628.6    0.05       0  4994.4    0.03       0  5000.4    0.05       0
Bank Sta=4994.4,5000.4
Exp/Cntr=0.3,0.1

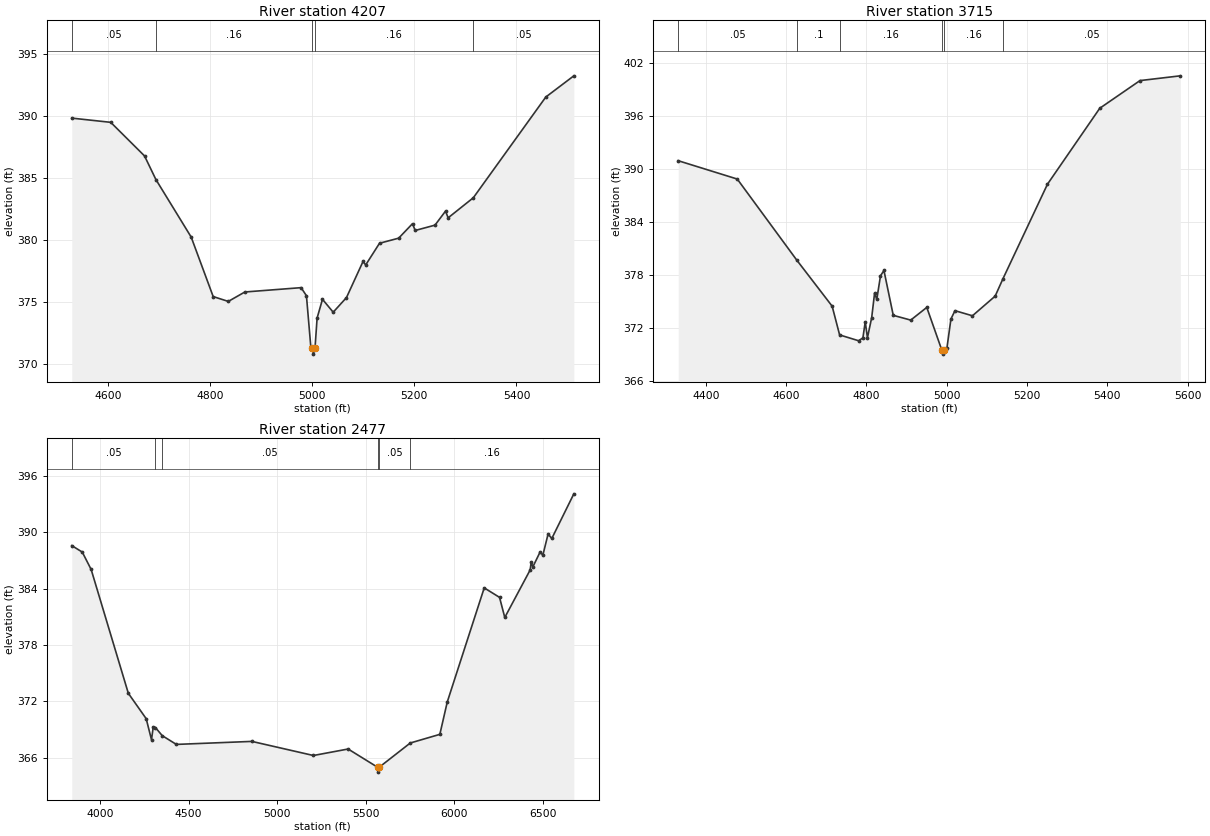
Type RM Length L Ch R = 1,4207,492,492,492
BEGIN DESCRIPTION:
UNT0164 IN SAND CR 3.0
END DESCRIPTION:
XS GIS Cut Line= 4
      3551086.55     10514558.12      3550800.13     10514493.03
      3550339.19     10514638.86      3550138.68     10514591.98
#Sta/Elev= 30
  4529.2  389.81  4605.5  389.47  4671.7  386.76  4693.9  384.86  4763.0  380.22
  4806.1  375.42  4835.7  375.03  4868.1  375.79  4978.2  376.14  4988.7  375.49
  4997.3  371.35  4999.5  371.28  5002.3  370.78  5005.5  371.28  5009.6  373.69
  5020.1  375.20  5041.1  374.16  5067.1  375.34  5099.5  378.25  5104.7  377.97
  5131.8  379.72  5169.3  380.13  5196.4  381.30  5201.6  380.75  5240.4  381.18
  5261.0  382.31  5266.2  381.77  5315.5  383.39  5457.4  391.51  5512.3  393.22
#Mann=5,-1,0
  4529.2    0.05       0  4693.9    0.16       0  4999.5    0.07       0
  5005.5    0.16       0  5315.5    0.05       0
Bank Sta=4999.5,5005.5
Exp/Cntr=0.3,0.1

Type RM Length L Ch R = 1,3715,1238,1238,1238
BEGIN DESCRIPTION:
UNT0164 IN SAND CR 2.0
END DESCRIPTION:
XS GIS Cut Line= 3
      3551232.41     10514315.93      3550716.80     10514086.78
      3550031.90     10514045.11
#Sta/Elev= 30
  4331.4  390.96  4478.4  388.88  4627.0  379.66  4714.7  374.46  4733.3  371.20
  4780.4  370.54  4791.3  370.86  4797.1  372.68  4802.6  370.88  4813.2  373.16
  4820.4  375.94  4825.9  375.23  4835.1  377.90  4843.7  378.51  4866.9  373.42
  4910.4  372.88  4950.4  374.32  4987.5  369.52  4990.3  369.02  4993.5  369.52
  5000.5  369.68  5010.5  373.00  5020.6  373.95  5064.1  373.37  5120.7  375.60
  5140.1  377.57  5251.0  388.30  5381.2  396.91  5481.4  400.05  5581.8  400.59
#Mann=6,-1,0
  4331.4    0.05       0  4627.0     0.1       0  4733.3    0.16       0
  4987.5    0.07       0  4993.5    0.16       0  5140.1    0.05       0
Bank Sta=4987.5,4993.5
Exp/Cntr=0.3,0.1

Type RM Length L Ch R = 1,2477,0,0,0
BEGIN DESCRIPTION:
UNT0164 IN SAND CR 1.1
END DESCRIPTION:
XS GIS Cut Line= 4
      3551263.96     10514160.75      3551211.87     10513162.46
      3550517.43     10512902.04      3549623.66     10513526.81
#Sta/Elev= 30
  3841.6  388.57  3900.8  387.88  3950.9  386.03  4160.6  372.85  4261.3  370.15
  4291.3  367.91  4301.3  369.28  4313.6  369.20  4352.0  368.34  4431.5  367.41
  4857.4  367.73  5204.5  366.23  5400.3  366.92  5568.2  364.96  5570.9  364.46
  5574.2  364.96  5750.8  367.56  5917.6  368.48  5959.5  371.93  6167.9  384.07
  6254.3  383.06  6283.9  380.92  6427.0  385.98  6433.1  386.85  6441.8  386.29
  6483.6  387.91  6498.5  387.54  6528.1  389.80  6549.1  389.33  6673.4  394.08
#Mann=6,-1,0
  3841.6    0.05       0  4313.6    0.16       0  4352.0    0.05       0
  5568.2    0.03       0  5574.2    0.05       0  5750.8    0.16       0
Bank Sta=5568.2,5574.2
Exp/Cntr=0.3,0.1

Chan Stop Cuts=-1