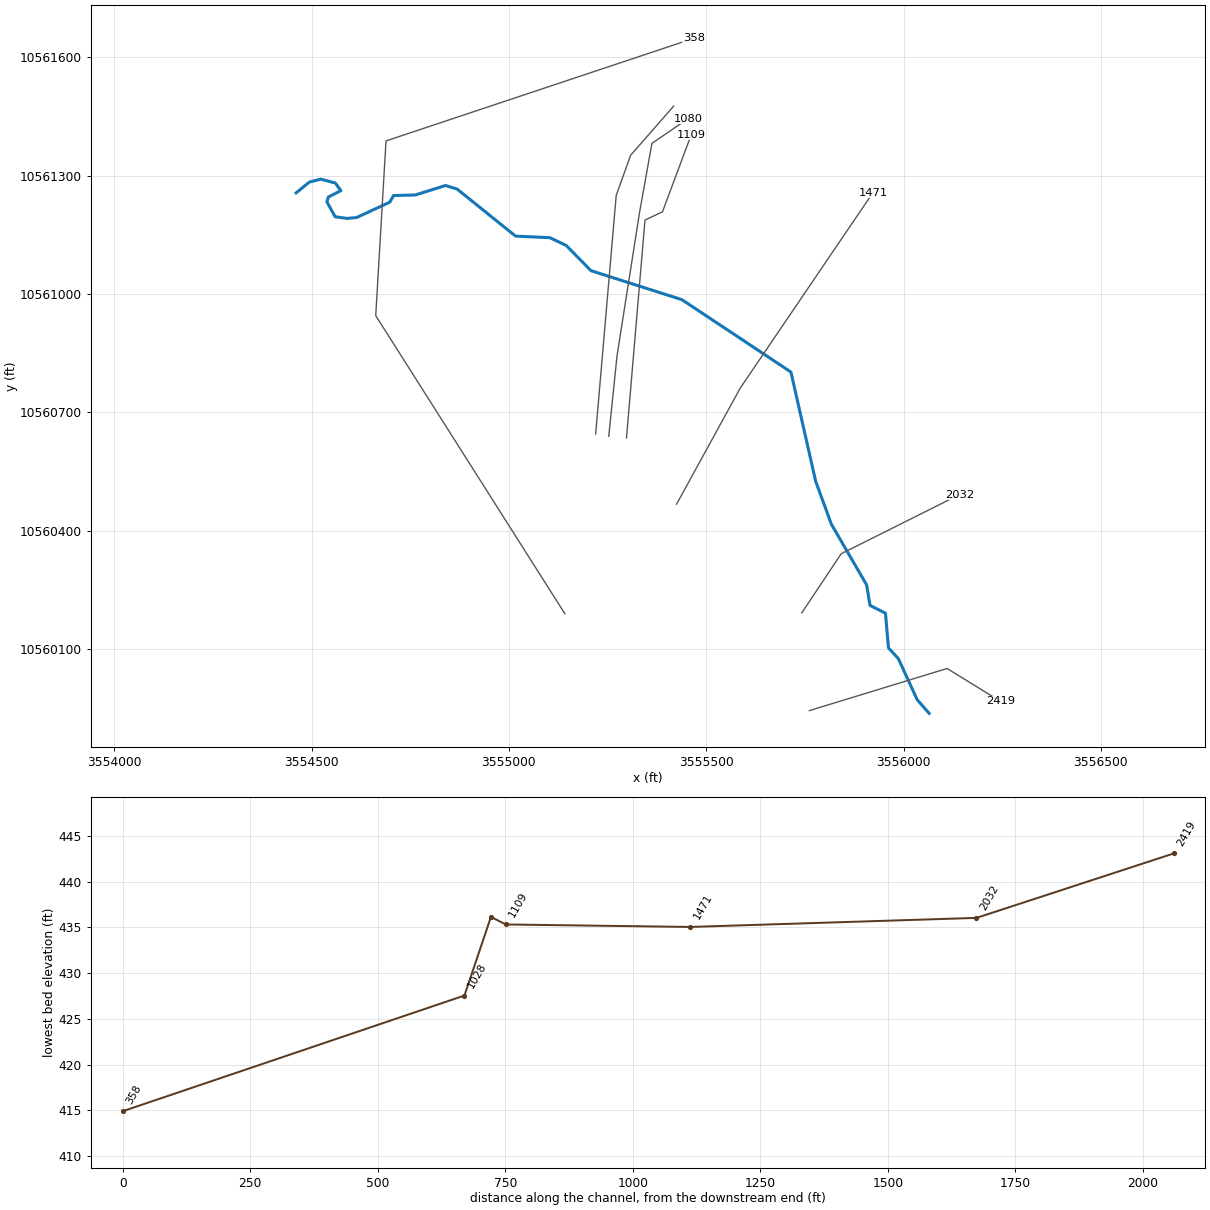
--- UNT01643 IN SAND CR.prj (project) ---

Proj Title=UNT01643 IN SAND CR Base Level Engineering
Current Plan=p01
Default Exp/Contr=0.3,0.1
English Units
Geom File=g01
Flow File=f01
Plan File=p01
BEGIN DESCRIPTION:
UNT01643 IN SAND CR
END DESCRIPTION:

--- UNT01643 IN SAND CR.p01 (plan) ---

Plan Title=Multiple Run
Short Identifier=Multiple
Geom File=g01
Flow File=f01
Subcritical Flow
K Sum by GR= 0
Std Step Tol= 0.01
Critical Tol= 0.01
Num of Std Step Trials= 20
Max Error Tol= 0.3
Flow Tol Ratio= 0.001
Split Flow NTrial= 30
Split Flow Tol= 0.02
Split Flow Ratio= 0.02
Log Output Level= 0
Friction Slope Method= 1
Unsteady Friction Slope Method= 2
Unsteady Bridges Friction Slope Method= 1
Parabolic Critical Depth
Global Vel Dist=  1 , 1 , 1
Global Log Level= 0
CheckData=True
Encroach Param= -1, 0, 0, 0
BEGIN DESCRIPTION:
Multiple Run
END DESCRIPTION:

--- UNT01643 IN SAND CR.f01 (steady flow) ---

Flow Title=Multiple
Number of Profiles=7
Profile Names=10-year,25-year,50-year,1pct_min,100-year,1pct_plu,500-year
River Rch & RM= UNT01643 IN SAND,Reach-1,2419
     328     420     491     421     569     770     760
Boundary for River Rch & Prof#=UNT01643 IN SAND,Reach-1,1
Up Type=0
Dn Type=3
Dn Slope=0.005
Boundary for River Rch & Prof#=UNT01643 IN SAND,Reach-1,2
Up Type=0
Dn Type=3
Dn Slope=0.005
Boundary for River Rch & Prof#=UNT01643 IN SAND,Reach-1,3
Up Type=0
Dn Type=3
Dn Slope=0.005
Boundary for River Rch & Prof#=UNT01643 IN SAND,Reach-1,4
Up Type=0
Dn Type=3
Dn Slope=0.005
Boundary for River Rch & Prof#=UNT01643 IN SAND,Reach-1,5
Up Type=0
Dn Type=3
Dn Slope=0.005
Boundary for River Rch & Prof#=UNT01643 IN SAND,Reach-1,6
Up Type=0
Dn Type=3
Dn Slope=0.005
Boundary for River Rch & Prof#=UNT01643 IN SAND,Reach-1,7
Up Type=0
Dn Type=3
Dn Slope=0.005

--- UNT01643 IN SAND CR.g01 (geometry) ---

Geom Title=Existing Conditions

River Reach=UNT01643 IN SAND,Reach-1
Reach XY= 30
      3556064.96     10559937.14      3556034.57     10559971.87
      3555986.83     10560076.03      3555961.87     10560103.16
      3555954.28     10560191.05      3555915.22     10560210.58
      3555906.54     10560262.66      3555817.11     10560416.64
      3555777.41     10560525.25      3555714.70     10560802.13
      3555438.32     10560985.53      3555208.14     10561058.88
      3555145.21     10561122.90      3555103.97     10561142.43
      3555016.91     10561146.51      3554868.61     10561265.88
      3554839.44     10561274.74      3554762.88     10561250.78
      3554707.67     10561249.22      3554698.30     10561232.55
      3554613.92     10561193.49      3554589.44     10561191.41
      3554559.75     10561195.57      3554538.92     10561233.07
      3554542.57     10561245.57      3554574.34     10561261.72
      3554560.27     10561280.99      3554523.30     10561290.88
      3554494.65     10561283.59      3554460.80     10561255.99

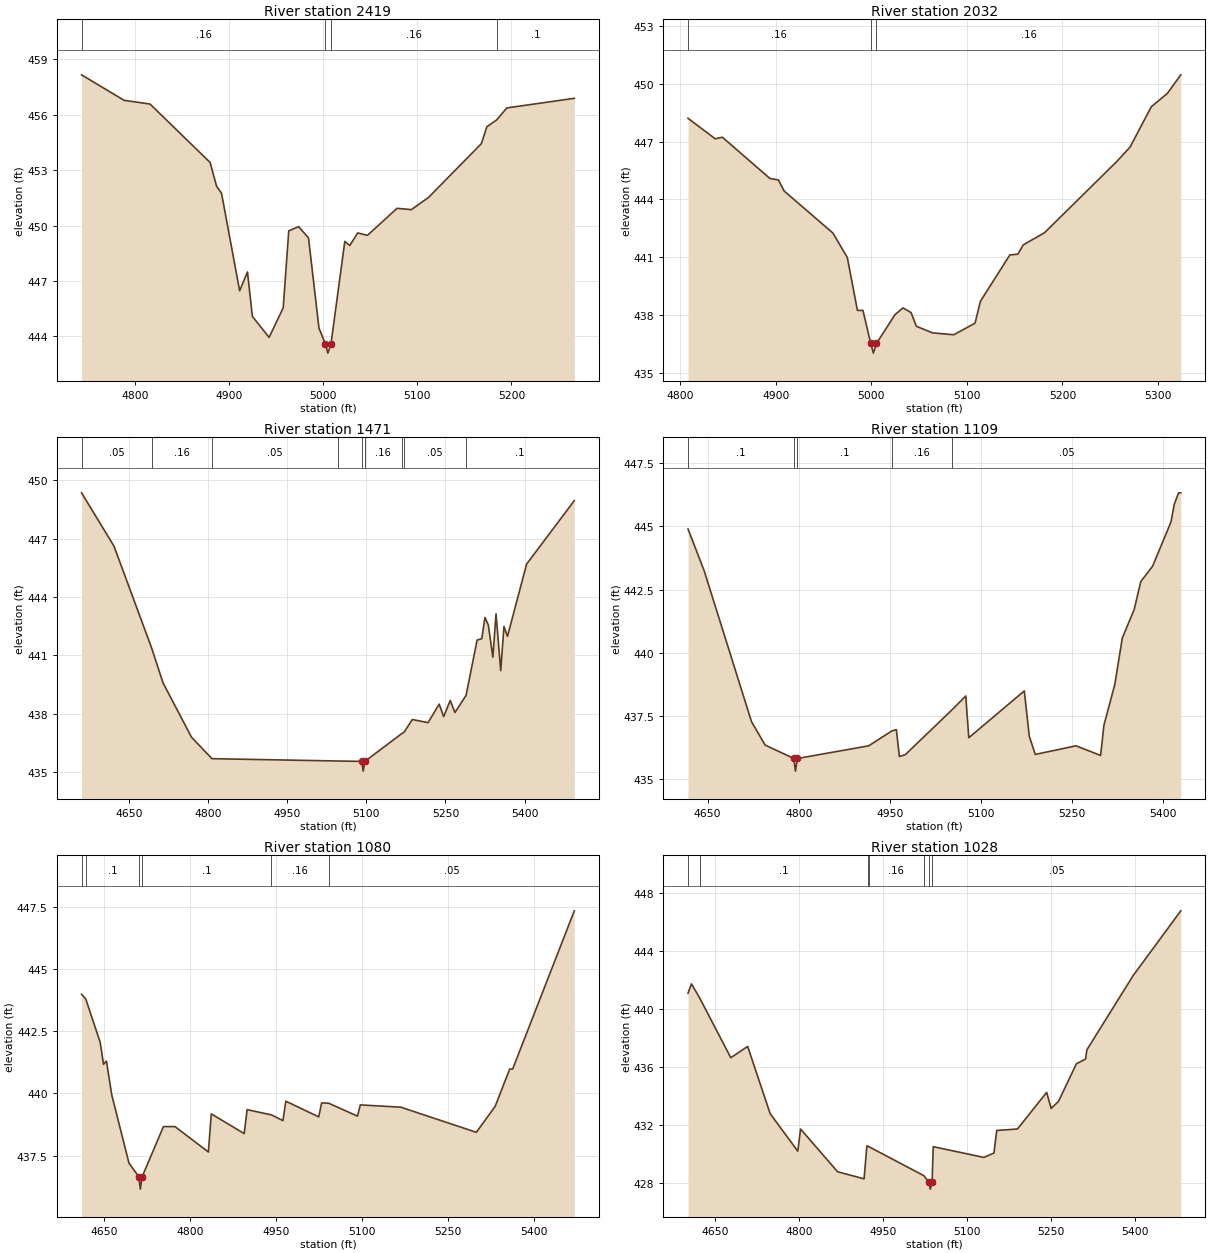
Type RM Length L Ch R = 1,2419,387,387,387
BEGIN DESCRIPTION:
UNT01643 IN SAND CR 4.1
END DESCRIPTION:
XS GIS Cut Line= 3
      3555761.40     10559944.13      3556110.37     10560050.90
      3556245.75     10559967.59
#Sta/Elev= 30
  4743.0  458.15  4788.3  456.77  4815.8  456.57  4879.7  453.41  4886.6  452.12
  4891.8  451.75  4911.1  446.47  4919.4  447.49  4924.6  445.09  4942.4  443.95
  4957.4  445.55  4963.3  449.71  4973.8  449.94  4984.3  449.33  4995.4  444.46
  5002.2  443.60  5004.9  443.10  5008.2  443.60  5022.9  449.14  5028.2  448.92
  5036.6  449.60  5047.0  449.47  5078.4  450.93  5093.7  450.86  5111.9  451.52
  5168.1  454.43  5173.9  455.34  5184.3  455.71  5195.2  456.36  5266.9  456.88
#Mann=4,-1,0
  4743.0    0.16       0  5002.2    0.07       0  5008.2    0.16       0
  5184.3     0.1       0
Bank Sta=5002.2,5008.2
Exp/Cntr=0.3,0.1

Type RM Length L Ch R = 1,2032,561,561,561
BEGIN DESCRIPTION:
UNT01643 IN SAND CR 4.0
END DESCRIPTION:
XS GIS Cut Line= 3
      3555742.12     10560191.66      3555842.11     10560341.64
      3556142.14     10560491.66
#Sta/Elev= 30
  4808.1  448.20  4836.6  447.14  4844.1  447.22  4893.7  445.09  4902.7  445.01
  4908.7  444.44  4959.8  442.26  4974.8  441.00  4985.4  438.26  4991.2  438.26
  4999.3  436.55  5002.1  436.05  5005.3  436.55  5024.7  438.04  5033.1  438.39
  5041.5  438.15  5047.1  437.44  5063.8  437.10  5086.2  437.00  5108.5  437.60
  5114.1  438.73  5144.9  441.13  5153.3  441.17  5158.9  441.65  5181.2  442.28
  5256.7  445.96  5270.7  446.71  5293.0  448.80  5309.8  449.49  5323.8  450.45
#Mann=3,-1,0
  4808.1    0.16       0  4999.3    0.07       0  5005.3    0.16       0
Bank Sta=4999.3,5005.3
Exp/Cntr=0.3,0.1

Type RM Length L Ch R = 1,1471,362,362,362
BEGIN DESCRIPTION:
UNT01643 IN SAND CR 3.0
END DESCRIPTION:
XS GIS Cut Line= 3
      3555424.97     10560467.36      3555586.43     10560761.63
      3555922.36     10561256.41
#Sta/Elev= 30
  4560.5  449.35  4622.0  446.61  4693.2  441.39  4714.9  439.59  4768.9  436.80
  4807.6  435.70  5045.5  435.58  5091.4  435.56  5094.1  435.06  5097.4  435.56
  5167.3  436.99  5171.7  437.06  5187.2  437.71  5217.1  437.55  5238.1  438.50
  5246.7  437.86  5259.1  438.69  5268.0  438.07  5289.1  438.95  5310.0  441.79
  5318.9  441.86  5324.9  442.95  5331.3  442.56  5339.9  440.91  5345.9  443.14
  5354.8  440.22  5360.9  442.49  5367.6  441.98  5403.8  445.69  5494.2  448.95
#Mann=9,-1,0
  4560.5    0.05       0  4693.2    0.16       0  4807.6    0.05       0
  5045.5    0.16       0  5091.4   0.033       0  5097.4    0.16       0
  5167.3     0.1       0  5171.7    0.05       0  5289.1     0.1       0
Bank Sta=5091.4,5097.4
Exp/Cntr=0.3,0.1

Type RM Length L Ch R = 1,1109,29,29,29
BEGIN DESCRIPTION:
UNT01643 IN SAND CR 2.1
END DESCRIPTION:
XS GIS Cut Line= 4
      3555298.04     10560635.12      3555344.92     10561187.19
      3555389.19     10561208.02      3555462.12     10561403.37
#Sta/Elev= 30
  4617.7  444.90  4644.3  443.25  4722.2  437.29  4744.7  436.36  4791.9  435.83
  4794.6  435.33  4797.9  435.83  4915.3  436.33  4953.5  436.92  4960.8  436.97
  4965.8  435.91  4975.5  435.98  5052.3  437.75  5075.1  438.30  5080.1  436.65
  5171.5  438.50  5179.7  436.71  5189.6  435.99  5256.6  436.33  5297.2  435.95
  5302.6  437.14  5320.6  438.76  5332.9  440.59  5352.5  441.72  5363.3  442.82
  5382.8  443.43  5413.1  445.18  5418.4  445.87  5425.6  446.33  5429.2  446.33
#Mann=5,-1,0
  4617.7     0.1       0  4791.9    0.07       0  4797.9     0.1       0
  4953.5    0.16       0  5052.3    0.05       0
Bank Sta=4791.9,4797.9
Exp/Cntr=0.3,0.1

Type RM Length L Ch R = 1,1080,52,52,52
BEGIN DESCRIPTION:
UNT01643 IN SAND CR 2.0
END DESCRIPTION:
XS GIS Cut Line= 5
      3555253.10     10560639.25      3555273.93     10560842.36
      3555331.22     10561206.94      3555362.47     10561381.42
      3555453.61     10561443.92
#Sta/Elev= 30
  4610.2  443.98  4617.6  443.79  4642.8  442.05  4648.6  441.17  4653.7  441.30
  4662.9  439.95  4693.0  437.21  4710.1  436.66  4712.9  436.16  4716.1  436.66
  4753.3  438.67  4773.4  438.67  4831.8  437.65  4836.9  439.18  4894.4  438.39
  4899.5  439.35  4942.0  439.14  4962.1  438.91  4967.1  439.69  5024.6  439.06
  5029.7  439.62  5041.9  439.61  5092.3  439.09  5097.3  439.54  5167.9  439.45
  5300.0  438.44  5332.9  439.48  5358.3  440.98  5363.5  440.98  5471.2  447.33
#Mann=6,-1,0
  4610.2    0.05       0  4617.6     0.1       0  4710.1    0.07       0
  4716.1     0.1       0  4942.0    0.16       0  5041.9    0.05       0
Bank Sta=4710.1,4716.1
Exp/Cntr=0.3,0.1

Type RM Length L Ch R = 1,1028,670,670,670
BEGIN DESCRIPTION:
UNT01643 IN SAND CR 2.2
END DESCRIPTION:
XS GIS Cut Line= 4
      3555219.92     10560645.53      3555272.00     10561249.69
      3555308.46     10561351.25      3555417.50     10561475.87
#Sta/Elev= 30
  4601.3  441.08  4607.4  441.73  4622.6  440.72  4677.7  436.63  4707.8  437.41
  4748.0  432.77  4797.3  430.18  4802.3  431.71  4868.4  428.76  4915.7  428.27
  4920.7  430.55  4923.3  430.51  4923.6  430.50  5022.4  428.49  5031.1  428.06
  5033.9  427.56  5037.1  428.06  5039.2  430.49  5129.4  429.75  5147.6  430.05
  5152.6  431.61  5189.6  431.71  5241.7  434.24  5249.7  433.13  5262.9  433.62
  5294.8  436.21  5311.2  436.54  5313.6  437.18  5396.0  442.29  5481.2  446.77
#Mann=7,-1,0
  4601.3    0.05       0  4622.6     0.1       0  4923.3    0.05       0
  4923.6    0.16       0  5022.4    0.05       0  5031.1    0.07       0
  5037.1    0.05       0
Bank Sta=5031.1,5037.1
Exp/Cntr=0.3,0.1

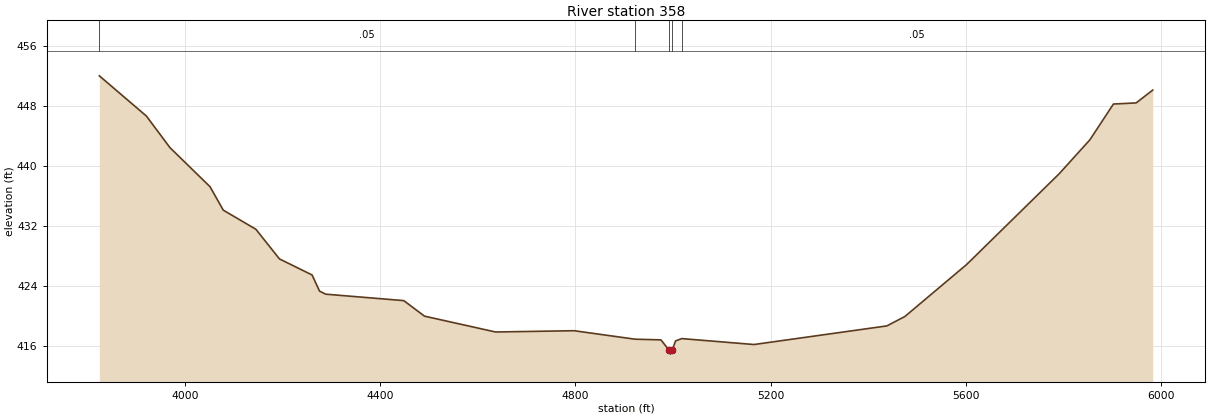
Type RM Length L Ch R = 1,358,0,0,0
BEGIN DESCRIPTION:
UNT01643 IN SAND CR 1.0
END DESCRIPTION:
XS GIS Cut Line= 4
      3555141.78     10560189.80      3554662.63     10560945.00
      3554688.67     10561387.71      3555468.53     10561647.66
#Sta/Elev= 30
  3823.7  452.00  3920.2  446.64  3968.5  442.43  4050.7  437.22  4077.8  434.10
  4144.7  431.55  4193.0  427.60  4259.9  425.46  4275.2  423.31  4287.8  422.90
  4448.0  422.04  4490.4  419.97  4636.1  417.86  4797.1  418.03  4922.1  416.90
  4975.2  416.81  4992.2  415.41  4994.9  414.91  4998.2  415.41  5005.2  416.67
  5017.8  416.98  5166.0  416.19  5438.4  418.67  5475.3  419.92  5601.8  426.84
  5791.5  438.93  5854.7  443.47  5903.0  448.24  5949.6  448.39  5983.6  450.10
#Mann=5,-1,0
  3823.7    0.05       0  4922.1    0.16       0  4992.2    0.07       0
  4998.2    0.16       0  5017.8    0.05       0
Bank Sta=4992.2,4998.2
Exp/Cntr=0.3,0.1

Chan Stop Cuts=-1