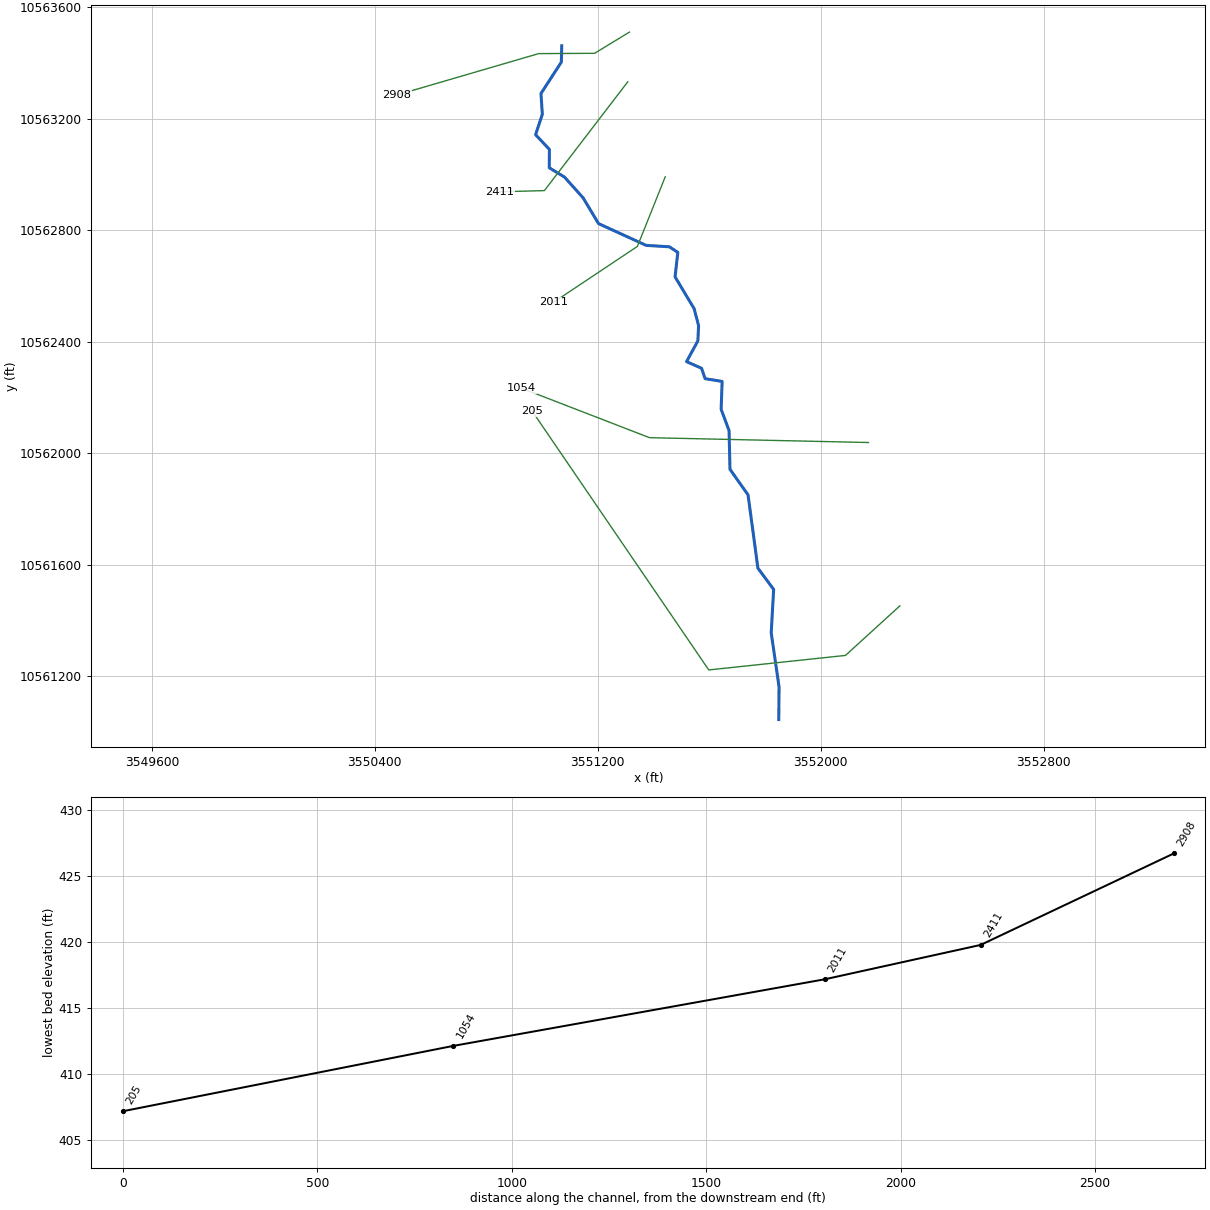
--- UNT01647 IN SAND CR.prj (project) ---

Proj Title=UNT01647 IN SAND CR Base Level Engineering
Current Plan=p01
Default Exp/Contr=0.3,0.1
English Units
Geom File=g01
Flow File=f01
Plan File=p01
BEGIN DESCRIPTION:
UNT01647 IN SAND CR
END DESCRIPTION:

--- UNT01647 IN SAND CR.p01 (plan) ---

Plan Title=Multiple Run
Short Identifier=Multiple
Geom File=g01
Flow File=f01
Subcritical Flow
K Sum by GR= 0
Std Step Tol= 0.01
Critical Tol= 0.01
Num of Std Step Trials= 20
Max Error Tol= 0.3
Flow Tol Ratio= 0.001
Split Flow NTrial= 30
Split Flow Tol= 0.02
Split Flow Ratio= 0.02
Log Output Level= 0
Friction Slope Method= 1
Unsteady Friction Slope Method= 2
Unsteady Bridges Friction Slope Method= 1
Parabolic Critical Depth
Global Vel Dist=  1 , 1 , 1
Global Log Level= 0
CheckData=True
Encroach Param= -1, 0, 0, 0
BEGIN DESCRIPTION:
Multiple Run
END DESCRIPTION:

--- UNT01647 IN SAND CR.f01 (steady flow) ---

Flow Title=Multiple
Number of Profiles=7
Profile Names=10-year,25-year,50-year,1pct_min,100-year,1pct_plu,500-year
River Rch & RM= UNT01647 IN SAND,Reach-1,2908
     730     981    1184    1044    1411    1909    1997
Boundary for River Rch & Prof#=UNT01647 IN SAND,Reach-1,1
Up Type=0
Dn Type=3
Dn Slope=0.005
Boundary for River Rch & Prof#=UNT01647 IN SAND,Reach-1,2
Up Type=0
Dn Type=3
Dn Slope=0.005
Boundary for River Rch & Prof#=UNT01647 IN SAND,Reach-1,3
Up Type=0
Dn Type=3
Dn Slope=0.005
Boundary for River Rch & Prof#=UNT01647 IN SAND,Reach-1,4
Up Type=0
Dn Type=3
Dn Slope=0.005
Boundary for River Rch & Prof#=UNT01647 IN SAND,Reach-1,5
Up Type=0
Dn Type=3
Dn Slope=0.005
Boundary for River Rch & Prof#=UNT01647 IN SAND,Reach-1,6
Up Type=0
Dn Type=3
Dn Slope=0.005
Boundary for River Rch & Prof#=UNT01647 IN SAND,Reach-1,7
Up Type=0
Dn Type=3
Dn Slope=0.005

--- UNT01647 IN SAND CR.g01 (geometry) ---

Geom Title=Existing Conditions

River Reach=UNT01647 IN SAND,Reach-1
Reach XY= 30
      3551070.68     10563461.58      3551069.38     10563403.18
      3550996.20     10563290.32      3551001.08     10563215.90
      3550976.88     10563142.62      3551026.47     10563089.78
      3551026.02     10563023.91      3551080.79     10562990.39
      3551147.76     10562915.50      3551202.69     10562823.61
      3551373.66     10562745.45      3551457.00     10562740.37
      3551487.19     10562720.31      3551477.35     10562632.61
      3551545.74     10562518.42      3551561.77     10562457.26
      3551559.14     10562402.86      3551518.52     10562328.21
      3551572.23     10562304.70      3551585.15     10562267.13
      3551646.26     10562257.37      3551642.63     10562157.31
      3551671.01     10562081.17      3551674.43     10561941.90
      3551739.14     10561850.44      3551774.61     10561587.26
      3551831.06     10561511.13      3551822.26     10561355.81
      3551850.39     10561161.26      3551849.50     10561044.06

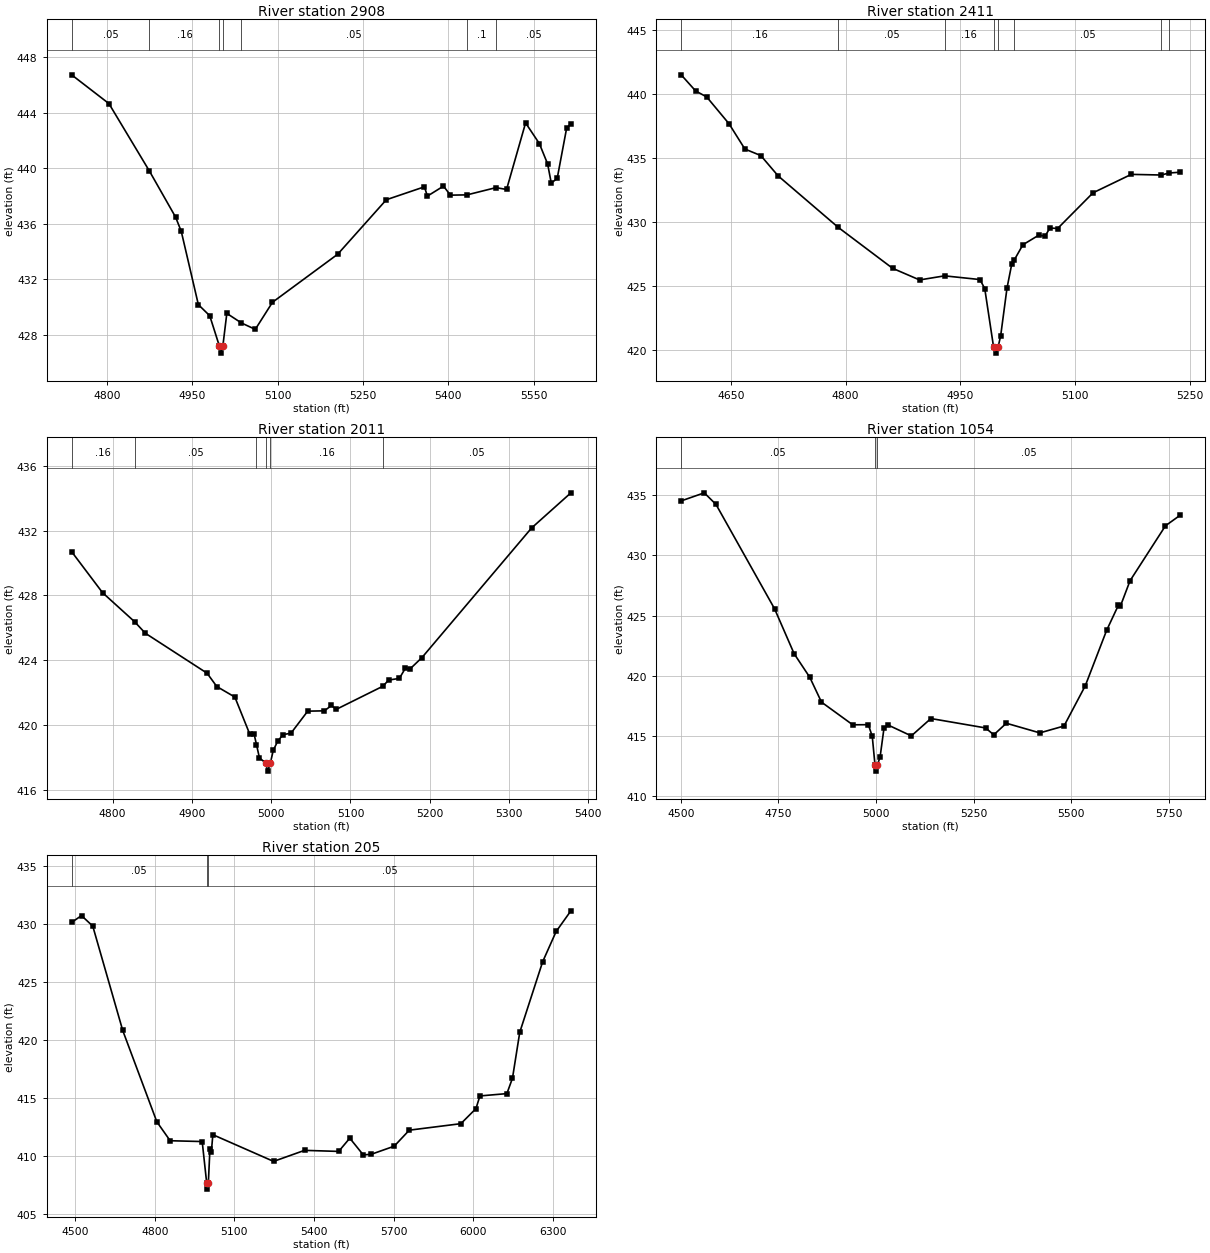
Type RM Length L Ch R = 1,2908,497,497,497
BEGIN DESCRIPTION:
UNT01647 IN SAND CR 2.1
END DESCRIPTION:
XS GIS Cut Line= 4
      3551313.37     10563510.55      3551188.56     10563434.57
      3550987.82     10563433.49      3550478.95     10563284.84
#Sta/Elev= 30
  4738.3  446.73  4803.8  444.66  4875.0  439.80  4920.9  436.49  4930.9  435.46
  4960.9  430.19  4980.9  429.39  4997.9  427.20  5000.6  426.70  5003.9  427.20
  5010.9  429.56  5036.6  428.87  5060.9  428.41  5091.1  430.36  5205.7  433.82
  5291.1  437.74  5358.0  438.67  5363.2  438.00  5391.5  438.72  5403.7  438.07
  5432.8  438.09  5483.6  438.61  5502.3  438.48  5535.7  443.27  5559.9  441.78
  5574.4  440.32  5580.8  438.94  5591.2  439.27  5607.8  442.89  5615.3  443.21
#Mann=7,-1,0
  4738.3    0.05       0  4875.0    0.16       0  4997.9    0.07       0
  5003.9    0.16       0  5036.6    0.05       0  5432.8     0.1       0
  5483.6    0.05       0
Bank Sta=4997.9,5003.9
Exp/Cntr=0.3,0.1

Type RM Length L Ch R = 1,2411,400,400,400
BEGIN DESCRIPTION:
UNT01647 IN SAND CR 2.0
END DESCRIPTION:
XS GIS Cut Line= 3
      3551307.89     10563332.58      3551008.43     10562941.98
      3550847.87     10562937.64
#Sta/Elev= 30
  4585.0  441.51  4603.9  440.25  4618.4  439.78  4647.5  437.69  4668.3  435.71
  4689.1  435.20  4711.8  433.61  4790.3  429.59  4861.4  426.39  4896.7  425.48
  4929.4  425.80  4975.6  425.51  4981.9  424.81  4993.4  420.26  4996.2  419.76
  4999.4  420.26  5002.7  421.10  5011.0  424.84  5017.3  426.75  5020.8  427.07
  5031.8  428.23  5052.6  428.98  5060.8  428.90  5067.1  429.54  5077.2  429.50
  5123.5  432.29  5173.5  433.73  5212.6  433.68  5223.3  433.84  5237.8  433.90
#Mann=8,-1,0
  4585.0    0.16       0  4790.3    0.05       0  4929.4    0.16       0
  4993.4    0.07       0  4999.4    0.16       0  5020.8    0.05       0
  5212.6    0.16       0  5223.3    0.05       0
Bank Sta=4993.4,4999.4
Exp/Cntr=0.3,0.1

Type RM Length L Ch R = 1,2011,957,957,957
BEGIN DESCRIPTION:
UNT01647 IN SAND CR 1.0
END DESCRIPTION:
XS GIS Cut Line= 3
      3551442.09     10562991.60      3551342.11     10562741.64
      3551042.08     10562541.63
#Sta/Elev= 30
  4748.3  430.70  4787.3  428.17  4827.9  426.37  4841.2  425.67  4919.2  423.20
  4931.4  422.38  4954.2  421.73  4973.1  419.43  4978.5  419.44  4981.5  418.79
  4985.2  417.98  4993.0  417.66  4995.7  417.16  4999.0  417.66  5002.7  418.45
  5008.1  418.99  5014.8  419.41  5025.0  419.50  5046.1  420.86  5067.1  420.88
  5076.1  421.21  5082.1  420.97  5141.0  422.40  5148.2  422.78  5161.7  422.88
  5169.2  423.50  5175.3  423.47  5190.3  424.17  5328.5  432.16  5378.1  434.33
#Mann=6,-1,0
  4748.3    0.16       0  4827.9    0.05       0  4981.5    0.16       0
  4993.0    0.07       0  4999.0    0.16       0  5141.0    0.05       0
Bank Sta=4993,4999
Exp/Cntr=0.3,0.1

Type RM Length L Ch R = 1,1054,849,849,849
BEGIN DESCRIPTION:
UNT01647 IN SAND CR 3.1
END DESCRIPTION:
XS GIS Cut Line= 3
      3552171.20     10562038.12      3551385.60     10562055.48
      3550926.35     10562233.11
#Sta/Elev= 30
  4501.1  434.50  4560.2  435.17  4590.2  434.21  4740.3  425.55  4790.3  421.83
  4830.3  419.88  4860.3  417.82  4940.3  415.94  4980.3  415.95  4990.3  414.98
  4997.3  412.60  5000.1  412.10  5003.3  412.60  5010.3  413.26  5020.3  415.66
  5030.3  415.93  5090.3  415.02  5140.4  416.46  5280.4  415.68  5301.4  415.11
  5333.5  416.07  5419.3  415.27  5481.2  415.84  5535.7  419.18  5590.3  423.77
  5620.2  425.84  5625.6  425.78  5650.2  427.88  5741.0  432.44  5779.3  433.33
#Mann=3,-1,0
  4501.1    0.05       0  4997.3    0.03       0  5003.3    0.05       0
Bank Sta=4997.3,5003.3
Exp/Cntr=0.3,0.1

Type RM Length L Ch R = 1,205,0,0,0
BEGIN DESCRIPTION:
UNT01647 IN SAND CR 3.0
END DESCRIPTION:
XS GIS Cut Line= 4
      3552284.04     10561452.18      3552088.73     10561274.23
      3551598.28     10561222.15      3550964.61     10562150.95
#Sta/Elev= 30
  4486.6  430.13  4523.8  430.72  4566.3  429.81  4679.2  420.82  4807.8  412.95
  4858.0  411.32  4978.7  411.25  4995.8  407.65  4998.6  407.15  5001.8  407.65
  5008.0  410.65  5013.0  410.31  5018.9  411.84  5247.8  409.54  5364.4  410.49
  5493.1  410.40  5535.0  411.54  5585.8  410.10  5615.7  410.15  5702.4  410.85
  5759.3  412.23  5953.7  412.79  6010.6  414.09  6025.5  415.18  6127.1  415.38
  6148.2  416.71  6175.6  420.66  6261.9  426.74  6312.8  429.35  6368.4  431.13
#Mann=3,-1,0
  4486.6    0.05       0  4995.8    0.03       0  5001.8    0.05       0
Bank Sta=4995.8,5001.8
Exp/Cntr=0.3,0.1

Chan Stop Cuts=-1