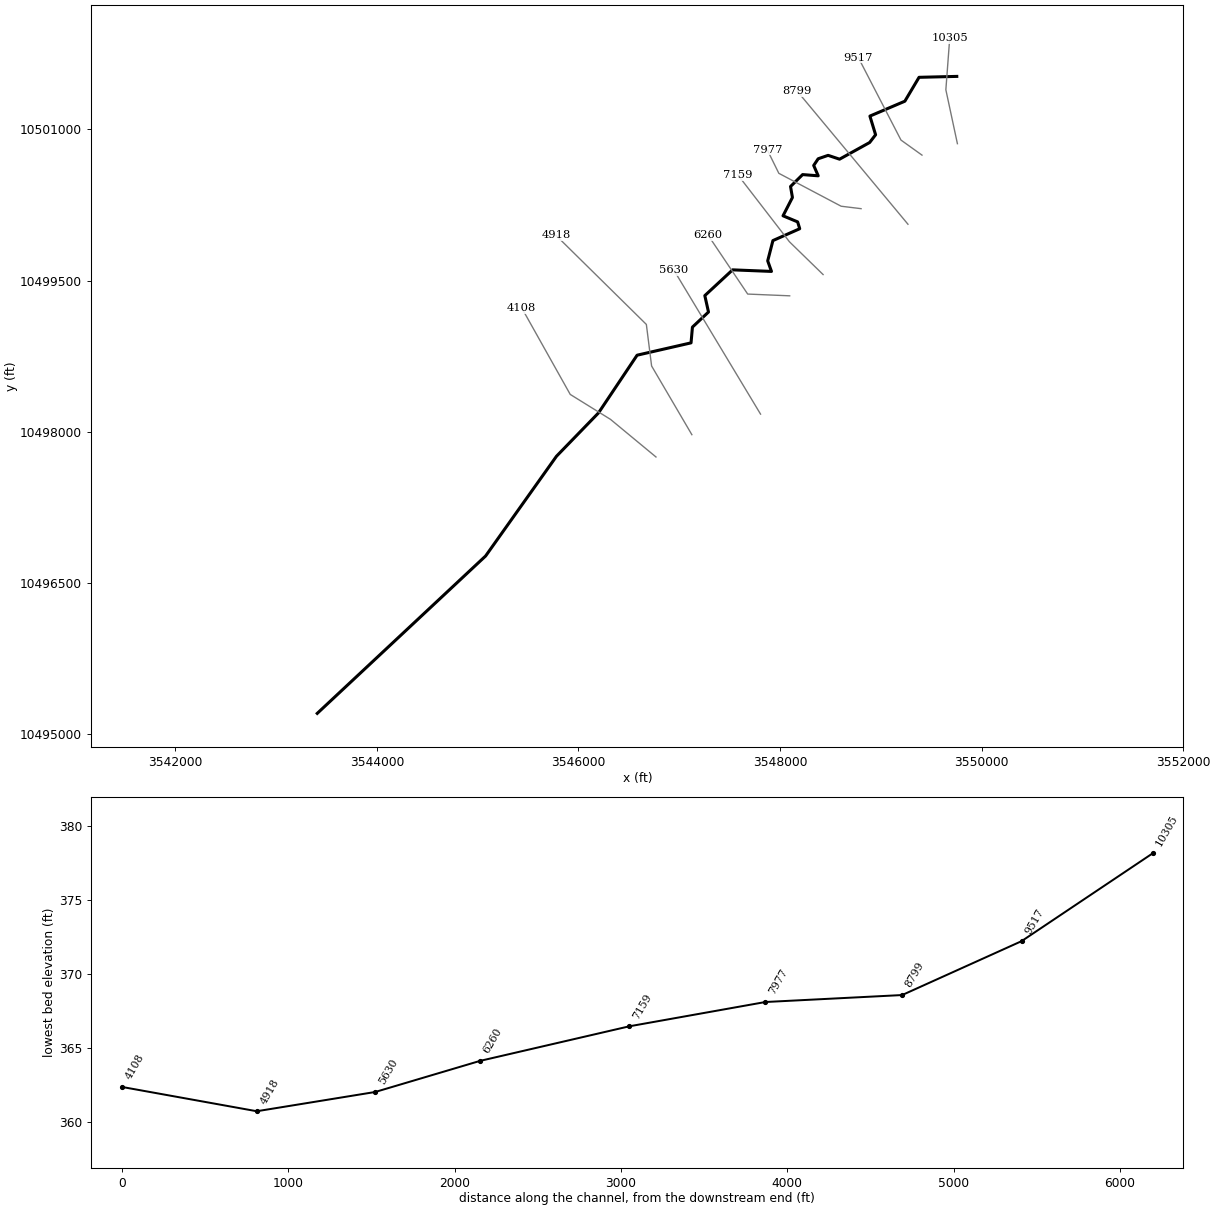
--- UNT0166 IN SAND CR.prj (project) ---

Proj Title=UNT0166 IN SAND CR Base Level Engineering
Current Plan=p01
Default Exp/Contr=0.3,0.1
English Units
Geom File=g01
Flow File=f01
Plan File=p01
BEGIN DESCRIPTION:
UNT0166 IN SAND CR
END DESCRIPTION:

--- UNT0166 IN SAND CR.p01 (plan) ---

Plan Title=Multiple Run
Short Identifier=Multiple
Geom File=g01
Flow File=f01
Subcritical Flow
K Sum by GR= 0
Std Step Tol= 0.01
Critical Tol= 0.01
Num of Std Step Trials= 20
Max Error Tol= 0.3
Flow Tol Ratio= 0.001
Split Flow NTrial= 30
Split Flow Tol= 0.02
Split Flow Ratio= 0.02
Log Output Level= 0
Friction Slope Method= 1
Unsteady Friction Slope Method= 2
Unsteady Bridges Friction Slope Method= 1
Parabolic Critical Depth
Global Vel Dist=  1 , 1 , 1
Global Log Level= 0
CheckData=True
Encroach Param= -1, 0, 0, 0
BEGIN DESCRIPTION:
Multiple Run
END DESCRIPTION:

--- UNT0166 IN SAND CR.f01 (steady flow) ---

Flow Title=Multiple
Number of Profiles=7
Profile Names=10-year,25-year,50-year,1pct_min,100-year,1pct_plu,500-year
River Rch & RM= UNT0166 IN SAND ,Reach-1,10305
    1361    1889    2327    2088    2824    3819    4148
Boundary for River Rch & Prof#=UNT0166 IN SAND ,Reach-1,1
Up Type=0
Dn Type=3
Dn Slope=0.005
Boundary for River Rch & Prof#=UNT0166 IN SAND ,Reach-1,2
Up Type=0
Dn Type=3
Dn Slope=0.005
Boundary for River Rch & Prof#=UNT0166 IN SAND ,Reach-1,3
Up Type=0
Dn Type=3
Dn Slope=0.005
Boundary for River Rch & Prof#=UNT0166 IN SAND ,Reach-1,4
Up Type=0
Dn Type=3
Dn Slope=0.005
Boundary for River Rch & Prof#=UNT0166 IN SAND ,Reach-1,5
Up Type=0
Dn Type=3
Dn Slope=0.005
Boundary for River Rch & Prof#=UNT0166 IN SAND ,Reach-1,6
Up Type=0
Dn Type=3
Dn Slope=0.005
Boundary for River Rch & Prof#=UNT0166 IN SAND ,Reach-1,7
Up Type=0
Dn Type=3
Dn Slope=0.005

--- UNT0166 IN SAND CR.g01 (geometry) ---

Geom Title=Existing Conditions

River Reach=UNT0166 IN SAND ,Reach-1
Reach XY= 30
      3549753.65     10501525.33      3549379.33     10501516.22
      3549238.56     10501279.18      3548891.83     10501131.53
      3548948.27     10500946.37      3548889.07     10500869.37
      3548590.78     10500704.07      3548477.05     10500742.03
      3548378.49     10500708.16      3548334.10     10500641.80
      3548378.88     10500539.09      3548224.18     10500551.17
      3548104.39     10500432.94      3548123.14     10500324.09
      3548029.91     10500142.32      3548174.70     10500081.90
      3548195.54     10500014.20      3547929.57     10499896.49
      3547877.73     10499695.42      3547915.23     10499590.56
      3547529.49     10499606.10      3547253.98     10499350.58
      3547290.36     10499187.63      3547131.13     10499037.97
      3547117.24     10498881.72      3546582.10     10498759.33
      3546198.84     10498186.41      3545782.17     10497756.72
      3545079.05     10496767.14      3543408.72     10495205.81

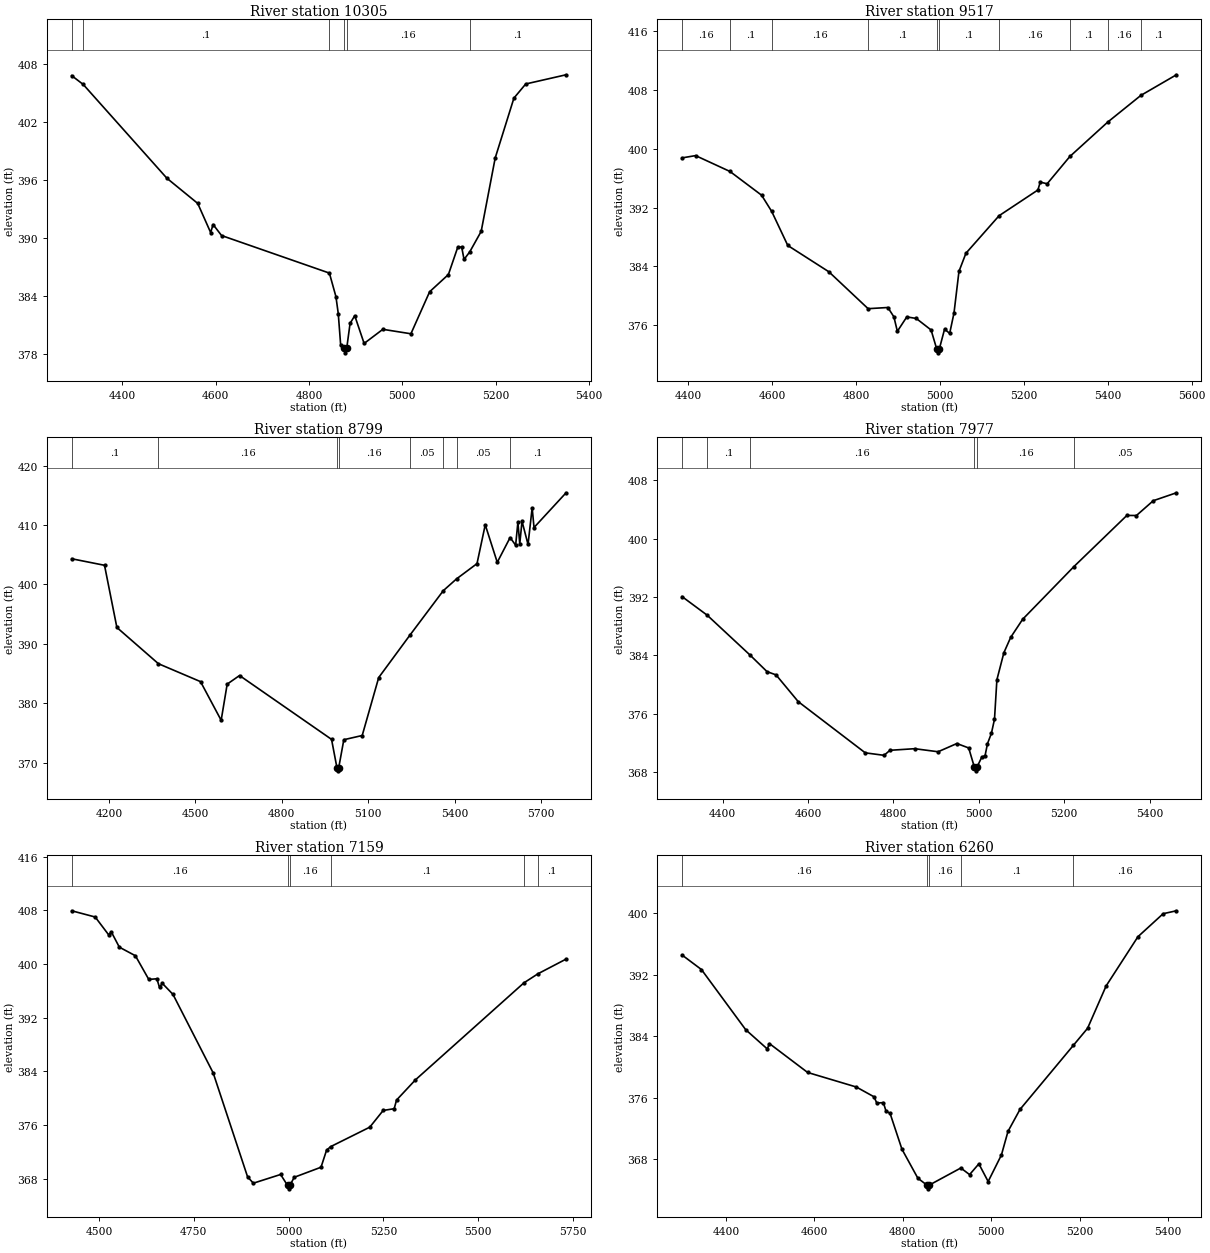
Type RM Length L Ch R = 1,10305,788,788,788
BEGIN DESCRIPTION:
UNT0166 IN SAND CR 22.0
END DESCRIPTION:
XS GIS Cut Line= 3
      3549759.93     10500857.75      3549645.33     10501392.52
      3549683.53     10501902.98
#Sta/Elev= 30
  4291.8  406.81  4316.5  405.90  4495.7  396.21  4561.7  393.61  4589.4  390.60
  4594.6  391.43  4612.8  390.29  4843.7  386.41  4857.7  383.98  4862.7  382.23
  4867.9  378.94  4874.9  378.67  4877.7  378.17  4880.9  378.67  4888.0  381.21
  4898.0  382.01  4918.1  379.14  4958.2  380.60  5018.3  380.14  5058.4  384.48
  5098.6  386.26  5118.6  389.08  5127.0  389.11  5132.1  387.82  5144.4  388.61
  5168.8  390.72  5198.8  398.30  5238.9  404.49  5264.2  405.95  5350.6  406.90
#Mann=6,-1,0
  4291.8    0.16       0  4316.5     0.1       0  4843.7    0.16       0
  4874.9    0.07       0  4880.9    0.16       0  5144.4     0.1       0
Bank Sta=4874.9,4880.9
Exp/Cntr=0.3,0.1

Type RM Length L Ch R = 1,9517,718,718,718
BEGIN DESCRIPTION:
UNT0166 IN SAND CR 21.0
END DESCRIPTION:
XS GIS Cut Line= 3
      3549408.47     10500744.27      3549200.11     10500893.60
      3548776.82     10501712.41
#Sta/Elev= 30
  4385.6  398.77  4417.9  399.08  4499.9  396.92  4575.2  393.69  4599.3  391.48
  4637.6  386.85  4735.5  383.27  4829.0  378.25  4876.1  378.41  4890.5  377.13
  4898.7  375.17  4921.2  377.13  4943.7  376.92  4979.1  375.35  4992.6  372.74
  4995.4  372.24  4998.6  372.74  5011.2  375.46  5023.4  374.89  5033.7  377.67
  5045.5  383.32  5062.1  385.79  5141.1  390.90  5233.6  394.40  5239.2  395.47
  5255.7  395.25  5309.8  398.96  5400.2  403.65  5478.9  407.27  5563.7  410.08
#Mann=10,-1,0
  4385.6    0.16       0  4499.9     0.1       0  4599.3    0.16       0
  4829.0     0.1       0  4992.6    0.07       0  4998.6     0.1       0
  5141.1    0.16       0  5309.8     0.1       0  5400.2    0.16       0
  5478.9     0.1       0
Bank Sta=4992.6,4998.6
Exp/Cntr=0.3,0.1

Type RM Length L Ch R = 1,8799,822,822,822
BEGIN DESCRIPTION:
UNT0166 IN SAND CR 19.0
END DESCRIPTION:
XS GIS Cut Line= 2
      3549269.43     10500058.51      3548171.92     10501377.26
#Sta/Elev= 30
  4070.6  404.31  4184.5  403.21  4227.4  392.74  4371.5  386.64  4517.7  383.62
  4589.3  377.11  4610.2  383.20  4653.1  384.65  4972.4  373.90  4991.2  369.10
  4994.0  368.60  4997.2  369.10  5015.0  373.84  5078.8  374.55  5136.1  384.31
  5244.1  391.43  5360.3  398.94  5406.4  400.93  5477.2  403.49  5505.8  410.03
  5547.5  403.71  5592.1  407.88  5611.3  406.59  5619.1  410.45  5625.6  406.83
  5633.4  410.63  5654.3  406.72  5668.6  412.87  5675.1  409.57  5786.3  415.42
#Mann=8,-1,0
  4070.6     0.1       0  4371.5    0.16       0  4991.2    0.07       0
  4997.2    0.16       0  5244.1    0.05       0  5360.3     0.1       0
  5406.4    0.05       0  5592.1     0.1       0
Bank Sta=4991.2,4997.2
Exp/Cntr=0.3,0.1

Type RM Length L Ch R = 1,7977,818,818,818
BEGIN DESCRIPTION:
UNT0166 IN SAND CR 17.0
END DESCRIPTION:
XS GIS Cut Line= 4
      3548804.27     10500213.04      3548606.36     10500237.35
      3547988.30     10500563.74      3547873.71     10500796.40
#Sta/Elev= 30
  4305.0  392.05  4364.0  389.49  4464.1  384.03  4504.0  381.75  4525.2  381.30
  4577.1  377.63  4734.1  370.60  4778.1  370.26  4791.9  370.95  4849.8  371.17
  4904.6  370.75  4948.6  371.88  4976.3  371.27  4989.6  368.63  4992.4  368.13
  4995.6  368.63  5006.8  370.00  5014.6  370.21  5020.3  371.86  5029.4  373.27
  5036.7  375.21  5042.3  380.63  5058.7  384.35  5074.6  386.45  5102.7  388.94
  5222.9  396.18  5346.7  403.19  5369.1  403.18  5408.5  405.21  5462.7  406.30
#Mann=6,-1,0
  4305.0    0.16       0  4364.0     0.1       0  4464.1    0.16       0
  4989.6    0.07       0  4995.6    0.16       0  5222.9    0.05       0
Bank Sta=4989.6,4995.6
Exp/Cntr=0.3,0.1

Type RM Length L Ch R = 1,7159,899,899,899
BEGIN DESCRIPTION:
UNT0166 IN SAND CR 16.0
END DESCRIPTION:
XS GIS Cut Line= 3
      3548427.44     10499559.35      3548093.23     10499884.88
      3547581.97     10500547.78
#Sta/Elev= 30
  4427.9  407.92  4489.9  406.99  4525.2  404.35  4532.4  404.77  4553.5  402.50
  4595.9  401.22  4631.2  397.69  4652.5  397.79  4659.5  396.49  4666.7  397.12
  4695.0  395.46  4801.0  383.76  4891.7  368.28  4906.9  367.33  4978.8  368.63
  4997.2  366.99  5000.0  366.49  5003.2  366.99  5014.7  368.21  5085.4  369.71
  5099.9  372.23  5110.5  372.77  5214.0  375.68  5249.3  378.17  5278.3  378.43
  5284.6  379.72  5334.4  382.73  5620.4  397.18  5657.7  398.54  5731.6  400.72
#Mann=6,-1,0
  4427.9    0.16       0  4997.2    0.07       0  5003.2    0.16       0
  5110.5     0.1       0  5620.4    0.16       0  5657.7     0.1       0
Bank Sta=4997.2,5003.2
Exp/Cntr=0.3,0.1

Type RM Length L Ch R = 1,6260,630,630,630
BEGIN DESCRIPTION:
UNT0166 IN SAND CR 14.0
END DESCRIPTION:
XS GIS Cut Line= 3
      3548095.99     10499348.46      3547679.28     10499365.82
      3547287.86     10499947.75
#Sta/Elev= 30
  4300.8  394.55  4344.7  392.66  4444.8  384.84  4493.6  382.34  4498.6  383.03
  4584.9  379.28  4695.0  377.39  4735.3  376.11  4741.3  375.30  4756.3  375.36
  4762.3  374.24  4771.3  373.98  4798.3  369.30  4834.3  365.53  4854.5  364.65
  4857.2  364.15  4860.5  364.65  4931.5  366.86  4951.3  366.00  4972.3  367.40
  4993.3  365.10  5023.3  368.55  5038.2  371.62  5065.3  374.47  5186.0  382.80
  5218.2  385.02  5260.2  390.53  5332.2  396.93  5389.2  399.92  5419.2  400.30
#Mann=5,-1,0
  4300.8    0.16       0  4854.5    0.07       0  4860.5    0.16       0
  4931.5     0.1       0  5186.0    0.16       0
Bank Sta=4854.5,4860.5
Exp/Cntr=0.3,0.1

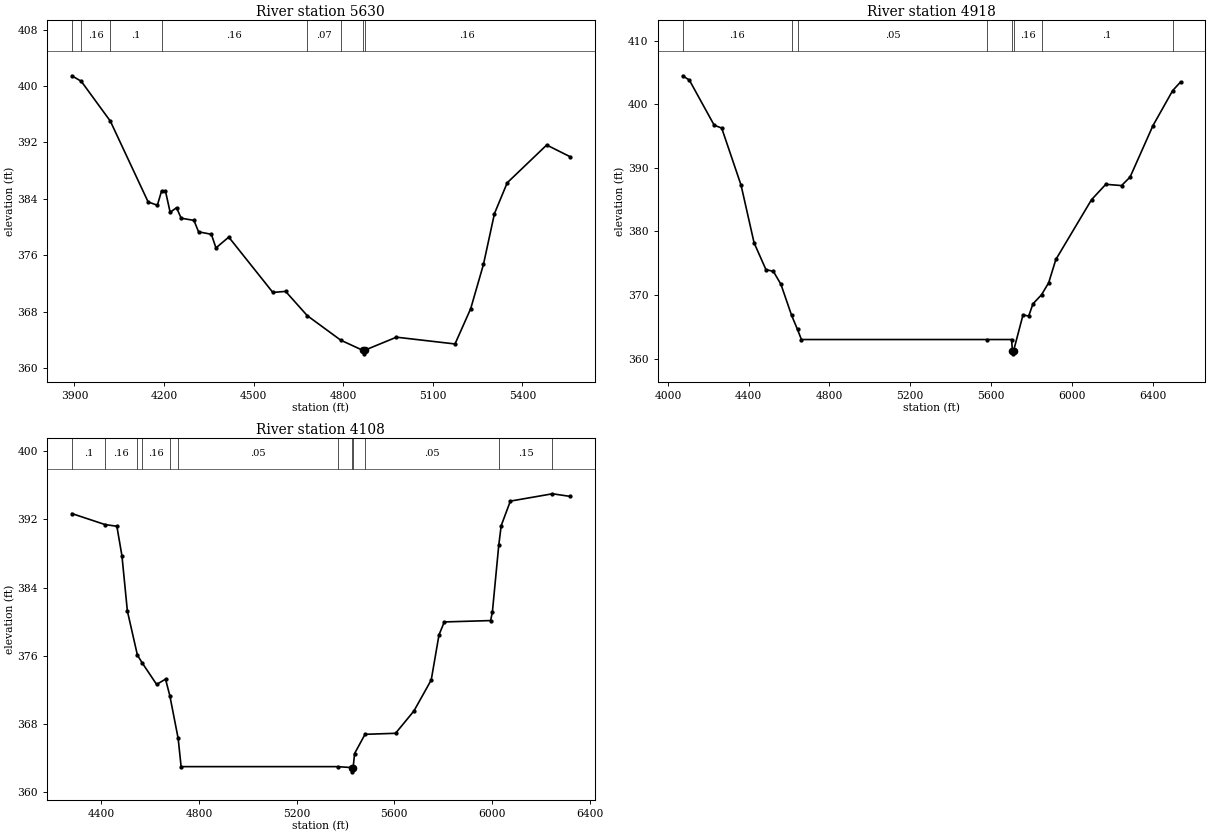
Type RM Length L Ch R = 1,5630,712,712,712
BEGIN DESCRIPTION:
UNT0166 IN SAND CR 12.0
END DESCRIPTION:
XS GIS Cut Line= 2
      3547806.77     10498174.82      3546947.39     10499602.76
#Sta/Elev= 30
  3891.6  401.45  3923.0  400.67  4020.3  395.03  4146.8  383.58  4177.8  383.10
  4192.0  385.15  4205.0  385.10  4220.6  382.10  4241.9  382.76  4257.5  381.27
  4300.2  380.96  4315.7  379.34  4358.5  378.99  4374.0  377.06  4416.8  378.59
  4564.4  370.75  4607.1  370.90  4679.6  367.46  4791.5  363.99  4865.3  362.55
  4868.0  362.05  4871.3  362.55  4978.1  364.41  5174.2  363.45  5226.7  368.45
  5269.4  374.72  5306.3  381.93  5349.0  386.29  5481.1  391.64  5558.2  390.01
#Mann=8,-1,0
  3891.6     0.1       0  3923.0    0.16       0  4020.3     0.1       0
  4192.0    0.16       0  4679.6    0.07       0  4791.5    0.16       0
  4865.3    0.07       0  4871.3    0.16       0
Bank Sta=4865.3,4871.3
Exp/Cntr=0.3,0.1

Type RM Length L Ch R = 1,4918,810,810,810
BEGIN DESCRIPTION:
UNT0166 IN SAND CR 10.0
END DESCRIPTION:
XS GIS Cut Line= 4
      3547125.37     10497970.78      3546726.04     10498652.24
      3546673.96     10499064.57      3545776.34     10499949.17
#Sta/Elev= 30
  4073.0  404.46  4106.1  403.78  4229.1  396.69  4266.3  396.24  4362.1  387.27
  4426.6  378.21  4485.2  374.00  4522.4  373.70  4559.5  371.69  4612.1  366.83
  4641.7  364.58  4661.1  363.00  5582.0  363.00  5702.0  363.00  5706.0  361.25
  5708.8  360.75  5712.0  361.25  5758.5  366.86  5786.8  366.70  5808.0  368.62
  5850.2  370.03  5885.8  371.93  5921.2  375.58  6097.9  384.98  6168.6  387.40
  6246.5  387.20  6288.9  388.54  6402.1  396.62  6499.6  402.12  6538.7  403.48
#Mann=8,-1,0
  4073.0    0.16       0  4612.1    0.07       0  4641.7    0.05       0
  5582.0    0.16       0  5706.0   0.033       0  5712.0    0.16       0
  5850.2     0.1       0  6499.6    0.16       0
Bank Sta=5706,5712
Exp/Cntr=0.3,0.1

Type RM Length L Ch R = 1,4108,0,0,0
BEGIN DESCRIPTION:
UNT0166 IN SAND CR 1.0
END DESCRIPTION:
XS GIS Cut Line= 4
      3546769.44     10497749.47      3546318.06     10498122.73
      3545918.75     10498370.12      3545437.84     10499227.96
#Sta/Elev= 30
  4279.7  392.68  4415.5  391.39  4464.0  391.19  4484.8  387.72  4507.0  381.25
  4548.1  376.08  4568.1  375.15  4626.8  372.64  4663.3  373.26  4680.7  371.34
  4715.0  366.31  4727.1  363.00  5367.6  363.00  5425.6  362.89  5428.4  362.39
  5431.6  362.89  5437.6  364.54  5480.3  366.79  5605.3  366.91  5680.6  369.53
  5751.4  373.16  5783.3  378.46  5805.0  379.97  5994.5  380.13  6001.8  381.11
  6027.9  388.94  6037.9  391.26  6075.5  394.14  6248.0  395.00  6318.6  394.70
#Mann=12,-1,0
  4279.7     0.1       0  4415.5    0.16       0  4548.1     0.1       0
  4568.1    0.16       0  4680.7    0.07       0  4715.0    0.05       0
  5367.6     0.1       0  5425.6   0.033       0  5431.6     0.1       0
  5480.3    0.05       0  6027.9    0.15       0  6248.0     0.1       0
Bank Sta=5425.6,5431.6
Exp/Cntr=0.3,0.1

Chan Stop Cuts=-1