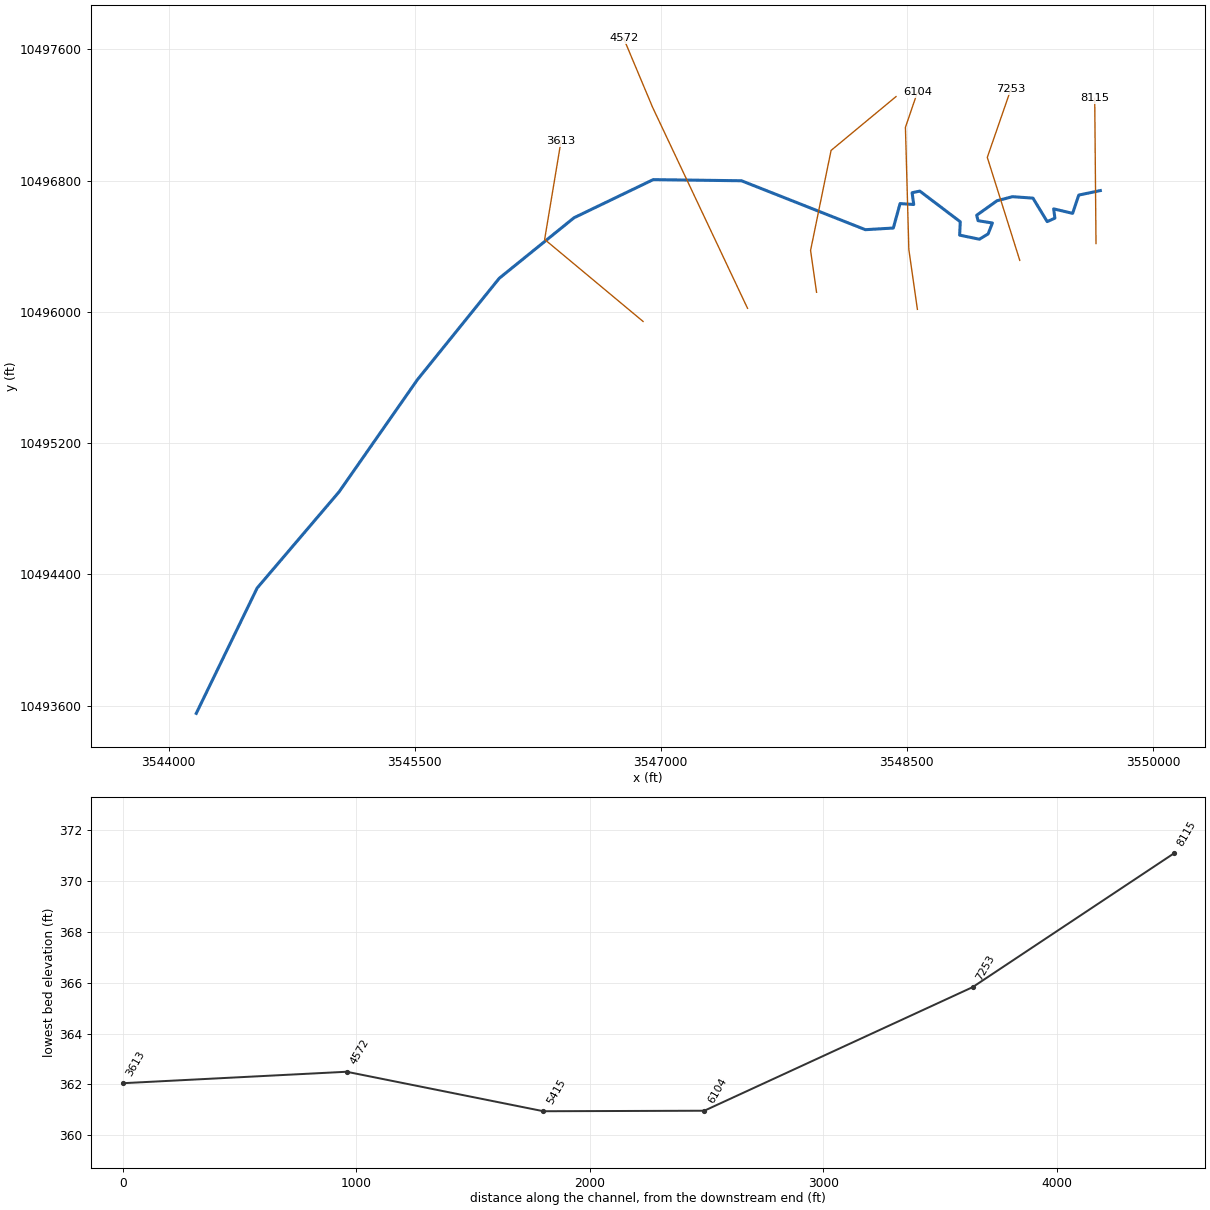
--- UNT0167 IN SAND CR.prj (project) ---

Proj Title=UNT0167 IN SAND CR Base Level Engineering
Current Plan=p01
Default Exp/Contr=0.3,0.1
English Units
Geom File=g01
Flow File=f01
Plan File=p01
BEGIN DESCRIPTION:
UNT0167 IN SAND CR
END DESCRIPTION:

--- UNT0167 IN SAND CR.p01 (plan) ---

Plan Title=Multiple Run
Short Identifier=Multiple
Geom File=g01
Flow File=f01
Subcritical Flow
K Sum by GR= 0
Std Step Tol= 0.01
Critical Tol= 0.01
Num of Std Step Trials= 20
Max Error Tol= 0.3
Flow Tol Ratio= 0.001
Split Flow NTrial= 30
Split Flow Tol= 0.02
Split Flow Ratio= 0.02
Log Output Level= 0
Friction Slope Method= 1
Unsteady Friction Slope Method= 2
Unsteady Bridges Friction Slope Method= 1
Parabolic Critical Depth
Global Vel Dist=  1 , 1 , 1
Global Log Level= 0
CheckData=True
Encroach Param= -1, 0, 0, 0
BEGIN DESCRIPTION:
Multiple Run
END DESCRIPTION:

--- UNT0167 IN SAND CR.f01 (steady flow) ---

Flow Title=Multiple
Number of Profiles=7
Profile Names=10-year,25-year,50-year,1pct_min,100-year,1pct_plu,500-year
River Rch & RM= UNT0167 IN SAND ,Reach-1,8115
     964    1320    1613    1438    1944    2629    2817
Boundary for River Rch & Prof#=UNT0167 IN SAND ,Reach-1,1
Up Type=0
Dn Type=3
Dn Slope=0.005
Boundary for River Rch & Prof#=UNT0167 IN SAND ,Reach-1,2
Up Type=0
Dn Type=3
Dn Slope=0.005
Boundary for River Rch & Prof#=UNT0167 IN SAND ,Reach-1,3
Up Type=0
Dn Type=3
Dn Slope=0.005
Boundary for River Rch & Prof#=UNT0167 IN SAND ,Reach-1,4
Up Type=0
Dn Type=3
Dn Slope=0.005
Boundary for River Rch & Prof#=UNT0167 IN SAND ,Reach-1,5
Up Type=0
Dn Type=3
Dn Slope=0.005
Boundary for River Rch & Prof#=UNT0167 IN SAND ,Reach-1,6
Up Type=0
Dn Type=3
Dn Slope=0.005
Boundary for River Rch & Prof#=UNT0167 IN SAND ,Reach-1,7
Up Type=0
Dn Type=3
Dn Slope=0.005

--- UNT0167 IN SAND CR.g01 (geometry) ---

Geom Title=Existing Conditions

River Reach=UNT0167 IN SAND ,Reach-1
Reach XY= 30
      3549678.86     10496739.18      3549547.49     10496711.79
      3549509.99     10496600.33      3549394.37     10496627.76
      3549402.01     10496571.17      3549355.13     10496549.98
      3549268.33     10496693.04      3549144.02     10496702.07
      3549049.43     10496677.31      3548925.31     10496588.87
      3548933.71     10496555.78      3549021.05     10496541.42
      3548994.92     10496475.02      3548941.99     10496442.71
      3548821.35     10496467.65      3548825.19     10496549.07
      3548578.66     10496736.05      3548531.78     10496726.16
      3548541.68     10496654.28      3548458.34     10496660.01
      3548417.24     10496510.92      3548246.84     10496500.82
      3547492.07     10496799.00      3546953.87     10496805.94
      3546471.24     10496573.59      3546015.51     10496204.67
      3545516.37     10495586.18      3545038.94     10494902.58
      3544539.81     10494316.65      3544168.85     10493552.91

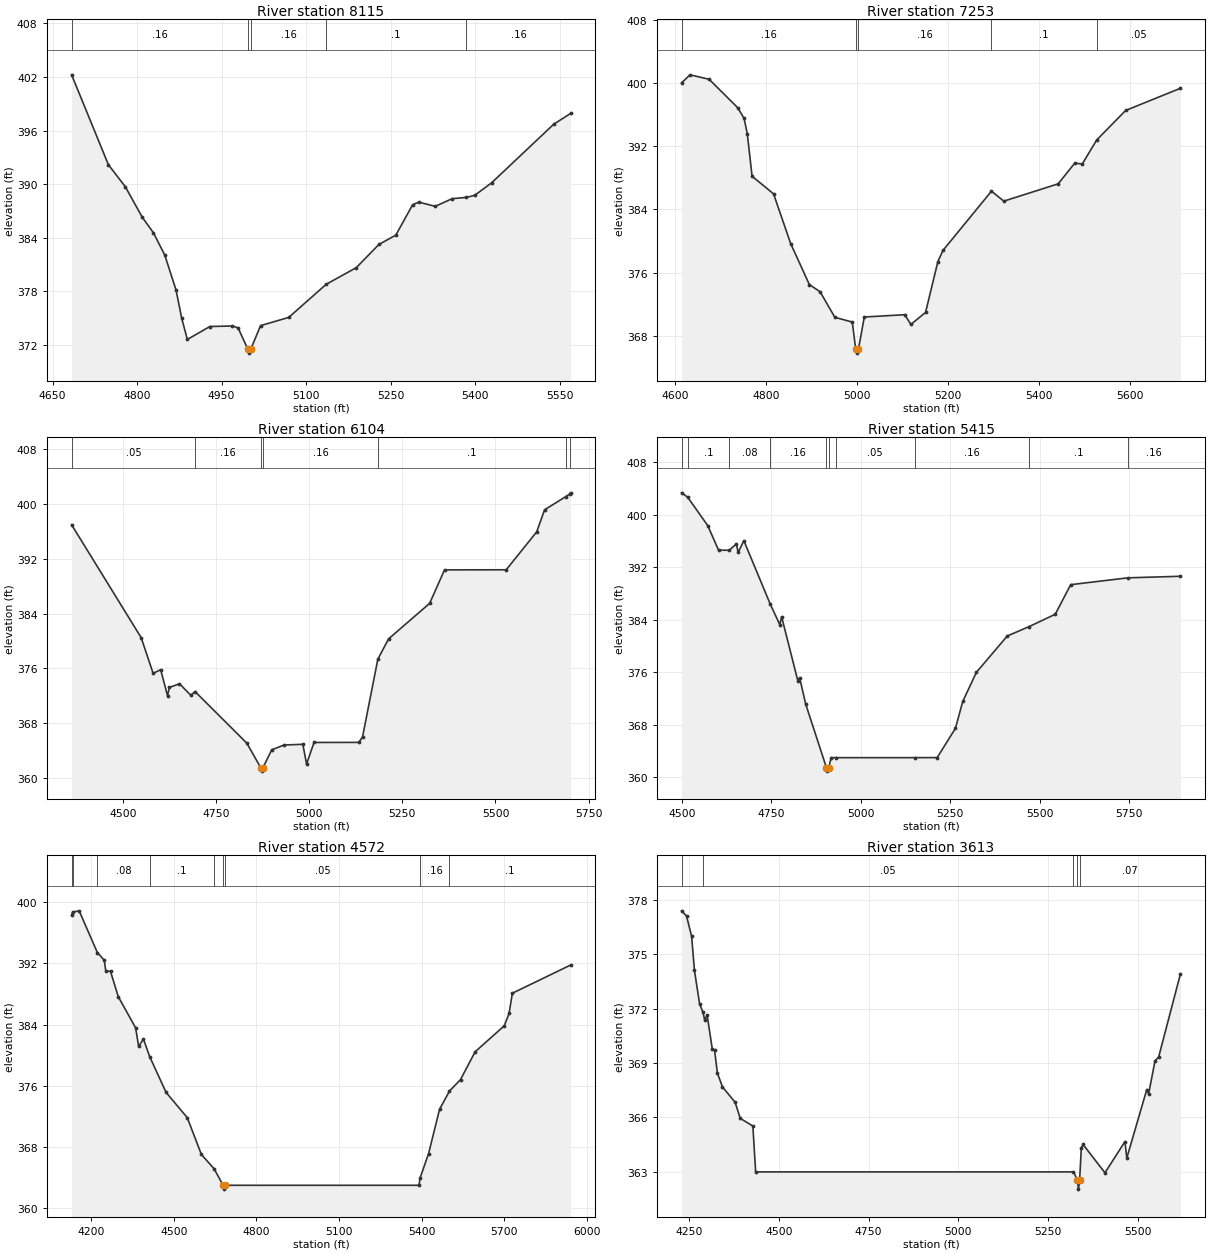
Type RM Length L Ch R = 1,8115,862,862,862
BEGIN DESCRIPTION:
UNT0167 IN SAND CR 10.0
END DESCRIPTION:
XS GIS Cut Line= 2
      3549652.51     10496416.30      3549644.70     10497301.76
#Sta/Elev= 30
  4683.9  402.24  4749.2  392.17  4779.2  389.71  4809.2  386.30  4829.2  384.54
  4849.2  382.06  4869.3  378.13  4879.3  374.98  4889.3  372.60  4929.3  374.05
  4969.3  374.11  4979.3  373.90  4996.3  371.57  4999.0  371.07  5002.3  371.57
  5019.3  374.15  5069.3  375.07  5135.6  378.77  5189.3  380.65  5229.3  383.24
  5259.3  384.28  5289.3  387.70  5300.4  387.98  5329.3  387.51  5359.3  388.37
  5384.4  388.51  5399.3  388.74  5429.3  390.14  5539.3  396.69  5569.4  397.91
#Mann=5,-1,0
  4683.9    0.16       0  4996.3    0.07       0  5002.3    0.16       0
  5135.6     0.1       0  5384.4    0.16       0
Bank Sta=4996.3,5002.3
Exp/Cntr=0.3,0.1

Type RM Length L Ch R = 1,7253,1149,1149,1149
BEGIN DESCRIPTION:
UNT0167 IN SAND CR 9.0
END DESCRIPTION:
XS GIS Cut Line= 3
      3549187.89     10496313.90      3548989.98     10496941.48
      3549133.22     10497355.56
#Sta/Elev= 30
  4614.1  400.01  4632.7  401.03  4674.6  400.47  4737.6  396.86  4751.5  395.51
  4758.5  393.57  4769.0  388.20  4816.2  385.97  4853.8  379.68  4894.8  374.50
  4918.5  373.58  4950.9  370.35  4989.2  369.75  4996.7  366.32  4999.4  365.82
  5002.7  366.32  5015.6  370.39  5104.5  370.68  5117.9  369.45  5150.2  370.97
  5177.3  377.41  5188.4  378.81  5295.0  386.31  5322.2  385.05  5441.6  387.24
  5478.1  389.86  5494.5  389.75  5526.3  392.79  5589.8  396.52  5710.3  399.33
#Mann=5,-1,0
  4614.1    0.16       0  4996.7    0.07       0  5002.7    0.16       0
  5295.0     0.1       0  5526.3    0.05       0
Bank Sta=4996.7,5002.7
Exp/Cntr=0.3,0.1

Type RM Length L Ch R = 1,6104,689,689,689
BEGIN DESCRIPTION:
UNT0167 IN SAND CR 7.0
END DESCRIPTION:
XS GIS Cut Line= 4
      3548563.95     10496015.15      3548511.86     10496379.77
      3548491.02     10497124.56      3548563.70     10497337.39
#Sta/Elev= 30
  4362.9  396.98  4549.5  380.48  4581.6  375.26  4601.8  375.80  4620.2  372.00
  4625.2  373.20  4652.3  373.74  4682.6  372.06  4694.0  372.60  4833.1  365.05
  4870.2  361.47  4872.9  360.97  4876.2  361.47  4899.7  364.09  4933.2  364.79
  4983.2  364.89  4993.2  362.00  5013.2  365.16  5133.3  365.17  5143.3  365.96
  5184.4  377.34  5213.3  380.31  5323.3  385.49  5363.3  390.39  5528.7  390.40
  5610.6  395.95  5631.7  399.17  5688.9  401.11  5699.1  401.49  5701.2  401.65
#Mann=7,-1,0
  4362.9    0.05       0  4694.0    0.16       0  4870.2    0.07       0
  4876.2    0.16       0  5184.4     0.1       0  5688.9    0.16       0
  5699.1     0.1       0
Bank Sta=4870.2,4876.2
Exp/Cntr=0.3,0.1

Type RM Length L Ch R = 1,5415,843,843,843
BEGIN DESCRIPTION:
UNT0167 IN SAND CR 5.0
END DESCRIPTION:
XS GIS Cut Line= 4
      3547949.36     10496119.36      3547912.90     10496374.56
      3548037.90     10496983.93      3548433.73     10497312.06
#Sta/Elev= 30
  4499.0  403.31  4516.0  402.65  4572.0  398.33  4602.3  394.59  4632.1  394.56
  4652.1  395.54  4657.1  394.23  4673.0  396.03  4746.6  386.39  4773.4  383.25
  4778.5  384.45  4823.8  374.71  4828.9  375.17  4845.7  371.17  4903.9  361.45
  4906.7  360.95  4909.9  361.45  4917.1  363.00  4930.3  363.00  5150.2  363.00
  5213.2  363.01  5264.2  367.46  5284.6  371.55  5322.8  375.99  5409.1  381.52
  5470.2  382.95  5543.2  384.83  5586.2  389.33  5746.0  390.37  5893.0  390.61
#Mann=10,-1,0
  4499.0    0.16       0  4516.0     0.1       0  4632.1    0.08       0
  4746.6    0.16       0  4903.9   0.033       0  4909.9    0.16       0
  4930.3    0.05       0  5150.2    0.16       0  5470.2     0.1       0
  5746.0    0.16       0
Bank Sta=4903.9,4909.9
Exp/Cntr=0.3,0.1

Type RM Length L Ch R = 1,4572,959,959,959
BEGIN DESCRIPTION:
UNT0167 IN SAND CR 3.0
END DESCRIPTION:
XS GIS Cut Line= 3
      3547528.68     10496021.64      3546950.57     10497245.56
      3546773.65     10497667.05
#Sta/Elev= 30
  4129.1  398.27  4132.4  398.71  4156.5  398.87  4222.5  393.42  4247.5  392.42
  4253.1  391.03  4270.3  390.95  4298.6  387.64  4361.4  383.58  4372.4  381.15
  4389.7  382.12  4412.6  379.80  4471.9  375.15  4549.0  371.83  4600.1  367.03
  4646.1  365.17  4679.1  363.00  4681.8  362.50  4685.1  363.00  5389.9  363.00
  5394.3  364.00  5424.6  367.13  5464.6  372.93  5500.6  375.32  5540.7  376.82
  5593.7  380.45  5699.6  383.85  5717.0  385.48  5728.7  388.10  5939.8  391.78
#Mann=9,-1,0
  4129.1    0.16       0  4132.4     0.1       0  4222.5    0.08       0
  4412.6     0.1       0  4646.1    0.05       0  4679.1   0.033       0
  4685.1    0.05       0  5394.3    0.16       0  5500.6     0.1       0
Bank Sta=4679.1,4685.1
Exp/Cntr=0.3,0.1

Type RM Length L Ch R = 1,3613,0,0,0
BEGIN DESCRIPTION:
UNT0167 IN SAND CR 1.0
END DESCRIPTION:
XS GIS Cut Line= 3
      3546892.12     10495941.63      3546292.11     10496441.64
      3546392.10     10497041.62
#Sta/Elev= 30
  4229.3  377.39  4243.0  377.11  4257.3  375.98  4265.1  374.11  4279.4  372.27
  4288.9  371.79  4293.8  371.36  4300.3  371.66  4314.6  369.80  4321.1  369.72
  4328.9  368.46  4343.2  367.68  4378.4  366.84  4392.7  365.95  4427.8  365.53
  4435.6  363.00  5320.7  363.00  5331.8  362.55  5334.5  362.05  5337.8  362.55
  5342.4  364.30  5347.4  364.51  5408.3  362.95  5464.0  364.67  5469.1  363.76
  5524.8  367.54  5529.9  367.30  5547.7  369.12  5557.8  369.33  5618.6  373.92
#Mann=5,-1,0
  4229.3     0.1       0  4288.9    0.05       0  5320.7    0.07       0
  5331.8   0.033       0  5337.8    0.07       0
Bank Sta=5331.8,5337.8
Exp/Cntr=0.3,0.1

Chan Stop Cuts=-1