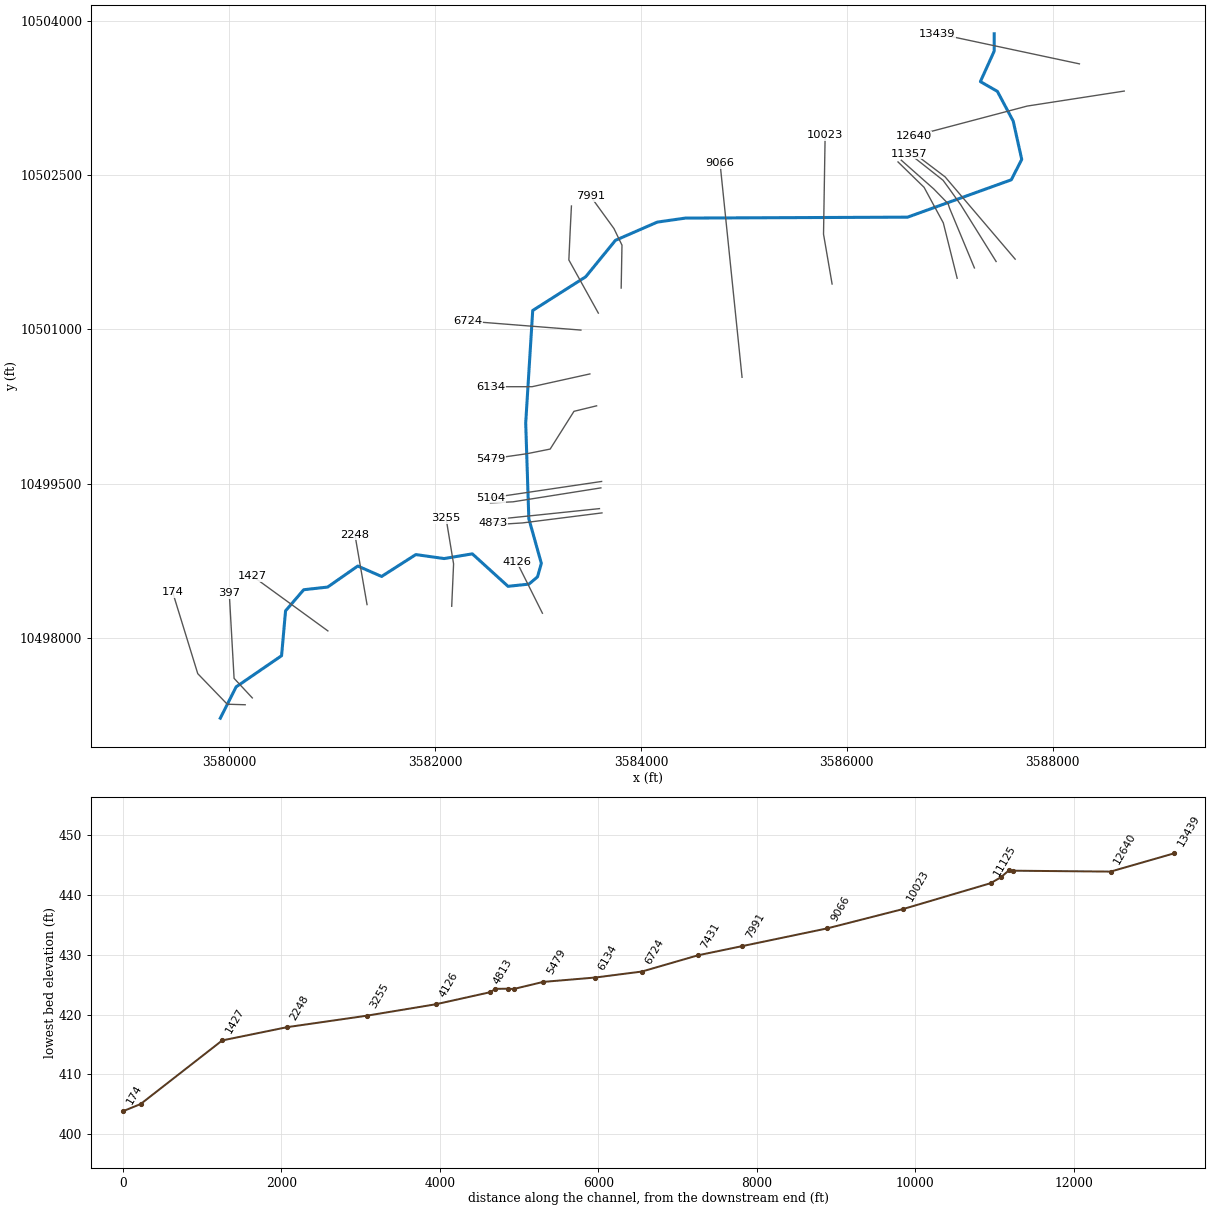
--- UNT0168 IN SAND CR.prj (project) ---

Proj Title=UNT0168 IN SAND CR Base Level Engineering
Current Plan=p01
Default Exp/Contr=0.3,0.1
English Units
Geom File=g01
Flow File=f01
Plan File=p01
Y Axis Title=Elevation
X Axis Title(PF)=Main Channel Distance
X Axis Title(XS)=Station
BEGIN DESCRIPTION:
UNT0168 IN SAND CR
END DESCRIPTION:
DSS Export Rating Curves= 0
DSS Export Rating Curve Sorted= 0
DSS Export Volume Flow Curves= 0
DXF OffsetX= 0
DXF OffsetY= 0
DXF ScaleX= 1
DXF ScaleY= 10

--- UNT0168 IN SAND CR.p01 (plan) ---

Plan Title=Multiple Run
Short Identifier=Multiple
Geom File=g01
Flow File=f01
Subcritical Flow
K Sum by GR= 0
Std Step Tol= 0.01
Critical Tol= 0.01
Num of Std Step Trials= 20
Max Error Tol= 0.3
Flow Tol Ratio= 0.001
Split Flow NTrial= 30
Split Flow Tol= 0.02
Split Flow Ratio= 0.02
Log Output Level= 0
Friction Slope Method= 1
Unsteady Friction Slope Method= 2
Unsteady Bridges Friction Slope Method= 1
Parabolic Critical Depth
Global Vel Dist=  1 , 1 , 1
Global Log Level= 0
CheckData=True
Encroach Param= -1, 0, 0, 0
BEGIN DESCRIPTION:
Multiple Run
END DESCRIPTION:

--- UNT0168 IN SAND CR.f01 (steady flow) ---

Flow Title=Multiple
Number of Profiles=7
Profile Names=10-year,25-year,50-year,1pct_min,100-year,1pct_plu,500-year
River Rch & RM= UNT0168 IN SAND ,Reach-1,13439
    1873    2664    3338    3046    4119    5571    6259
River Rch & RM= UNT0168 IN SAND ,Reach-1,6724
    3331    4862    6198    5742    7766   10502   12171
River Rch & RM= UNT0168 IN SAND ,Reach-1,2248
    3604    5272    6730    6243    8442   11417   13264
Boundary for River Rch & Prof#=UNT0168 IN SAND ,Reach-1,1
Up Type=0
Dn Type=3
Dn Slope=0.005
Boundary for River Rch & Prof#=UNT0168 IN SAND ,Reach-1,2
Up Type=0
Dn Type=3
Dn Slope=0.005
Boundary for River Rch & Prof#=UNT0168 IN SAND ,Reach-1,3
Up Type=0
Dn Type=3
Dn Slope=0.005
Boundary for River Rch & Prof#=UNT0168 IN SAND ,Reach-1,4
Up Type=0
Dn Type=3
Dn Slope=0.005
Boundary for River Rch & Prof#=UNT0168 IN SAND ,Reach-1,5
Up Type=0
Dn Type=3
Dn Slope=0.005
Boundary for River Rch & Prof#=UNT0168 IN SAND ,Reach-1,6
Up Type=0
Dn Type=3
Dn Slope=0.005
Boundary for River Rch & Prof#=UNT0168 IN SAND ,Reach-1,7
Up Type=0
Dn Type=3
Dn Slope=0.005

--- UNT0168 IN SAND CR.g01 (geometry) ---

Geom Title=Existing Conditions
Program Version=4.10

River Reach=UNT0168 IN SAND ,Reach-1
Reach XY= 30
      3587431.88      10503871.7      3587432.11      10503704.2
      3587297.62     10503407.32      3587462.98     10503312.27
      3587616.63     10503023.21      3587699.45     10502650.97
      3587597.89      10502453.1      3586590.35      10502090.2
      3584431.28     10502081.08      3584157.84     10502042.02
      3583751.59     10501864.94      3583462.53     10501510.77
      3582947.77     10501183.25      3582879.59     10500088.78
      3582909.97     10499159.96       3583031.6     10498726.26
       3582994.3     10498594.91      3582910.91     10498524.56
      3582707.83     10498503.13      3582360.84     10498818.79
      3582087.11     10498772.91      3581811.61      10498811.4
      3581479.36     10498598.91      3581247.82     10498700.16
      3580955.06     10498495.86      3580722.77     10498470.06
      3580546.18     10498264.63      3580507.43     10497828.77
      3580065.77     10497525.89      3579912.11     10497221.64

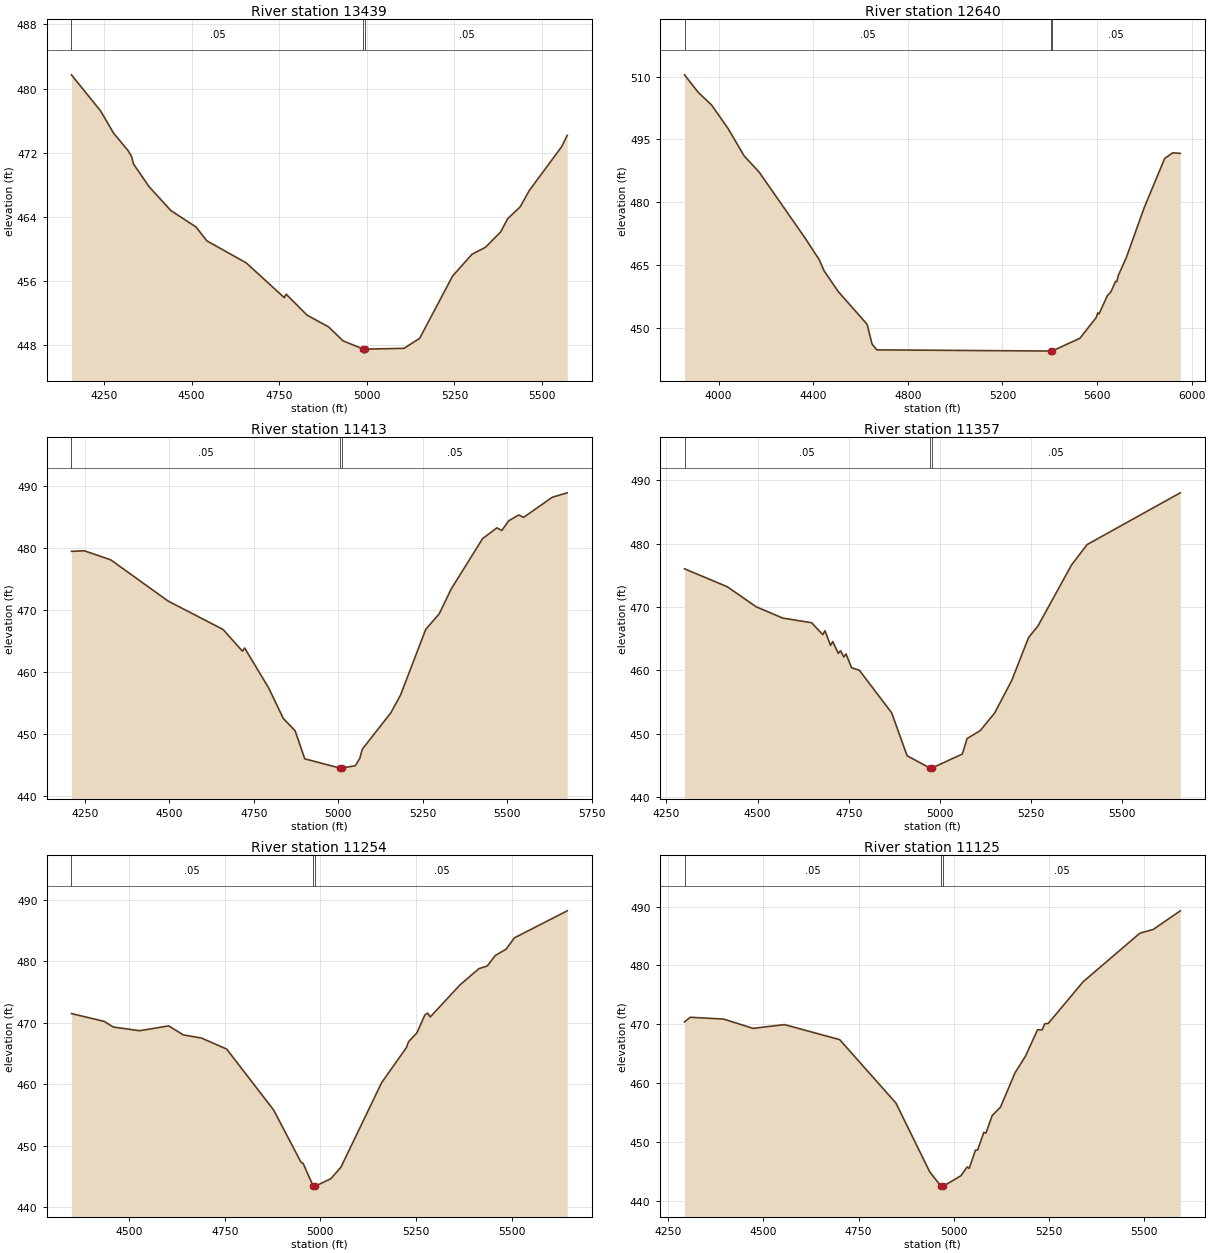
Type RM Length L Ch R = 1 ,13439   ,799,799,799
BEGIN DESCRIPTION:
UNT0168 IN SAND CR 28.0
END DESCRIPTION:
XS GIS Cut Line= 2
      3588259.85     10503579.67      3586876.14     10503874.63
#Sta/Elev= 30
    4157  481.71    4240  477.21  4277.4  474.41  4318.3  472.26  4328.5  471.51
    4334  470.58  4378.4  467.74    4441  464.74  4512.6  462.69  4543.2  460.97
  4655.7  458.21  4764.5  453.86  4769.7   454.3  4829.5  451.67  4890.9  450.21
  4931.8  448.47  4990.1  447.43  4992.9  446.93  4996.1  447.43  5106.2  447.53
  5150.7  448.78  5244.7  456.56  5299.9  459.28  5338.6  460.16  5381.7  462.07
  5402.1  463.74  5437.7  465.22  5463.5  467.25  5555.5   472.7  5571.8  474.14
#Mann= 3 ,-1 , 0
    4157     .05       0  4990.1    .033       0  4996.1     .05       0
Bank Sta=4990.1,4996.1
XS Rating Curve= 0 ,0
Exp/Cntr=0.3,0.1

Type RM Length L Ch R = 1 ,12640   ,1227,1227,1227
BEGIN DESCRIPTION:
UNT0168 IN SAND CR 26.0
END DESCRIPTION:
XS GIS Cut Line= 3
      3588695.34     10503315.44       3587752.6      10503169.6
      3586648.42     10502877.93
#Sta/Elev= 30
    3856  510.47  3914.2  506.26  3970.6  503.24  4040.4  497.61  4108.5  491.05
  4171.5   487.2  4365.2  471.47  4425.9  466.21  4446.2  463.57  4507.1  458.54
  4628.2  450.78  4648.5  446.11  4668.8  444.67    5404  444.39  5406.8  443.89
    5410  444.39  5527.8  447.45  5596.5  452.41  5603.2  453.53  5608.3  453.24
  5643.4  457.61  5658.6  458.56  5678.5  461.06  5683.7  460.98  5689.6  462.42
    5724  466.76  5799.3  478.66  5886.1  490.47  5920.1  491.81    5952  491.68
#Mann= 3 ,-1 , 0
    3856     .05       0    5404    .033       0    5410     .05       0
Bank Sta=5404,5410
XS Rating Curve= 0 ,0
Exp/Cntr=0.3,0.1

Type RM Length L Ch R = 1 ,11413   ,56,56,56
BEGIN DESCRIPTION:
UNT0168 IN SAND CR 25.0
END DESCRIPTION:
XS GIS Cut Line= 3
      3587635.65     10501682.09      3586954.65     10502481.71
      3586622.61     10502733.46
#Sta/Elev= 30
  4210.3  479.42  4248.4  479.51  4326.4  478.06  4496.6  471.41  4659.1  466.84
  4716.2  463.35  4722.8  463.86  4794.2   457.4    4837  452.53  4872.1  450.54
  4900.7  446.02  5004.2  444.54    5007  444.04  5010.2  444.54  5050.1  444.91
  5063.5  446.09  5070.9  447.57  5155.4  453.43    5184  456.28  5258.7  466.87
  5298.5  469.36  5333.9  473.35  5426.9  481.47  5469.1   483.2  5483.7  482.78
  5504.5  484.35  5533.6  485.27  5548.2  484.89  5633.5  488.14  5677.3  488.84
#Mann= 3 ,-1 , 0
  4210.3     .05       0  5004.2     .03       0  5010.2     .05       0
Bank Sta=5004.2,5010.2
XS Rating Curve= 0 ,0
Exp/Cntr=0.3,0.1

Type RM Length L Ch R = 1 ,11357   ,103,103,103
BEGIN DESCRIPTION:
UNT0168 IN SAND CR 25.01
END DESCRIPTION:
XS GIS Cut Line= 5
      3587450.51     10501659.16      3587106.78     10502210.11
       3586992.2     10502370.27      3586934.91      10502448.4
      3586608.05     10502706.23
#Sta/Elev= 30
  4299.6  476.03  4416.9   473.2    4496  470.04  4569.1  468.25  4648.2  467.52
  4678.8  465.64  4684.7  466.26  4700.1  463.94    4706  464.55  4721.3  462.68
  4727.2   463.1  4736.6  462.11  4742.5   462.6  4757.9  460.41  4779.1  460.02
  4867.6  453.31  4910.1  446.52  4972.5   444.6  4975.2   444.1  4978.5   444.6
  5061.5   446.8  5074.4  449.24  5110.7   450.5  5149.9  453.26  5197.2  458.44
  5242.8  465.15  5268.9  467.02    5361  476.64  5403.5  479.85  5659.1  488.02
#Mann= 3 ,-1 , 0
  4299.6     .05       0  4972.5     .03       0  4978.5     .05       0
Bank Sta=4972.5,4978.5
XS Rating Curve= 0 ,0
Exp/Cntr=0.3,0.1

Type RM Length L Ch R = 1 ,11254   ,129,129,129
BEGIN DESCRIPTION:
UNT0168 IN SAND CR 23.0
END DESCRIPTION:
XS GIS Cut Line= 5
      3587239.59     10501596.84      3586997.41     10502178.86
      3586984.39     10502220.53      3586845.06     10502363.76
      3586528.69     10502643.68
#Sta/Elev= 30
  4349.2   471.5  4434.7  470.23  4458.5  469.31  4527.7  468.71  4603.5   469.5
  4641.7  468.03  4689.4  467.51  4755.2  465.72    4878  455.79  4949.5   447.3
  4954.9  447.13  4981.2  443.43  4983.9  442.93  4987.2  443.43  5027.5  444.63
  5053.9  446.51  5160.1  460.24  5225.2  465.98  5230.6  466.92  5252.3  468.34
  5273.2  471.26  5280.4  471.58  5287.4  470.95  5365.2  476.17  5414.6  478.81
  5436.3  479.24  5457.2  480.94  5485.7  481.98  5507.4  483.82  5645.5  488.22
#Mann= 3 ,-1 , 0
  4349.2     .05       0  4981.2     .03       0  4987.2     .05       0
Bank Sta=4981.2,4987.2
XS Rating Curve= 0 ,0
Exp/Cntr=0.3,0.1

Type RM Length L Ch R = 1 ,11125   ,1102,1102,1102
BEGIN DESCRIPTION:
UNT0168 IN SAND CR 23.01
END DESCRIPTION:
XS GIS Cut Line= 4
      3587071.84     10501496.48      3586937.29     10502034.66
      3586750.66     10502379.72      3586497.17     10502626.76
#Sta/Elev= 30
  4293.4  470.38  4308.4  471.18    4396  470.87  4473.3  469.29  4555.8  469.93
  4700.7  467.37  4848.2  456.59    4937  444.88  4966.4  442.45  4969.1  441.95
  4972.4  442.45  5018.8  444.23    5035  445.72  5040.7  445.49  5056.9  448.59
  5062.6  448.59  5078.8   451.6  5084.5  451.49  5100.7  454.45  5122.5  455.88
  5160.6  461.71  5188.2  464.57  5219.9  469.05  5231.9  469.04  5238.7  470.07
  5247.9  470.13  5339.7  477.23  5488.4  485.48  5523.6  486.12  5594.4  489.28
#Mann= 3 ,-1 , 0
  4293.4     .05       0  4966.4     .03       0  4972.4     .05       0
Bank Sta=4966.4,4972.4
XS Rating Curve= 0 ,0
Exp/Cntr=0.3,0.1

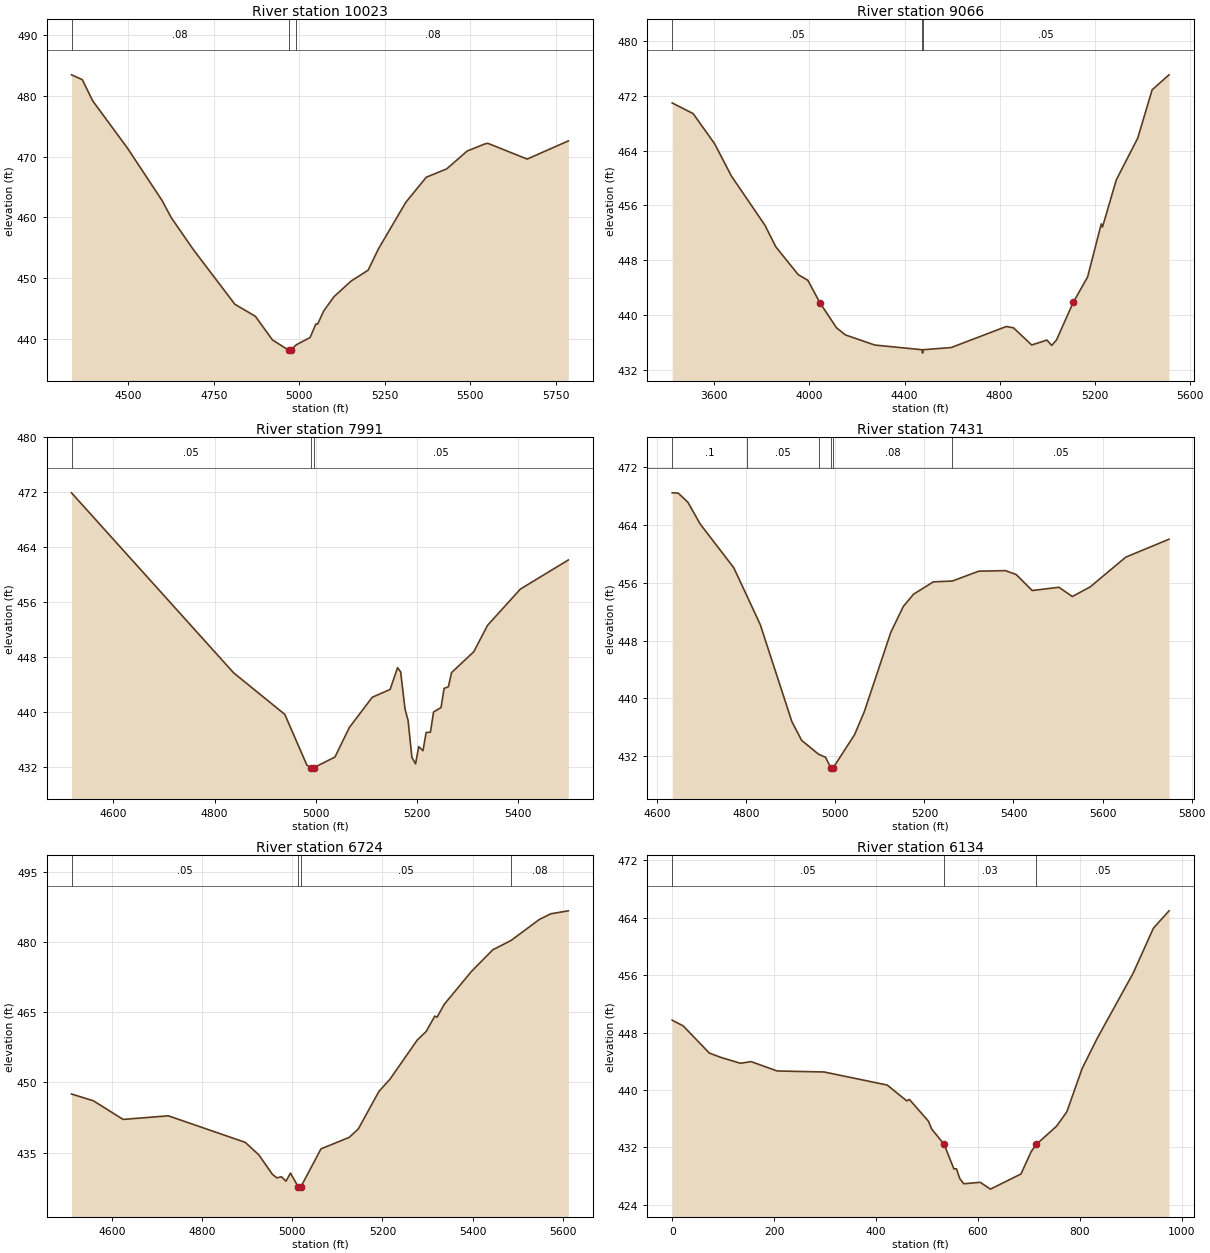
Type RM Length L Ch R = 1 ,10023   ,957,957,957
BEGIN DESCRIPTION:
UNT0168 IN SAND CR 21.0
END DESCRIPTION:
XS GIS Cut Line= 3
      3585856.77     10501440.46      3585773.44     10501924.81
      3585789.05     10502887.52
#Sta/Elev= 30
  4333.2  483.46  4364.8  482.67  4395.3  479.17  4496.8  471.41  4598.2  462.78
  4624.8  459.98  4689.8  454.69  4811.3  445.69  4871.5   443.7  4921.5  439.81
  4968.5  438.14  4971.3  437.64  4974.5  438.14  4991.5  439.02  5031.5  440.21
  5048.7  442.45  5053.7  442.42  5071.5  444.59  5101.5  446.93  5151.5   449.5
  5201.5   451.3  5231.6   454.8  5311.6  462.46  5371.6   466.6  5431.6  467.98
  5491.6  470.92  5541.6  472.05  5551.6  472.19  5667.1  469.59  5787.5  472.58
#Mann= 3 ,-1 , 0
  4333.2     .08       0  4968.5     .06       0  4991.5     .08       0
Bank Sta=4968.5,4974.5
XS Rating Curve= 0 ,0
Exp/Cntr=0.3,0.1

Type RM Length L Ch R = 1 ,9066    ,1075,1075,1075
BEGIN DESCRIPTION:
UNT0168 IN SAND CR 19.0
END DESCRIPTION:
XS GIS Cut Line= 2
      3584981.77     10500534.17      3584768.23     10502612.33
#Sta/Elev= 30
  3423.2  470.96  3511.1  469.41  3601.6     465    3672  460.29  3812.7  453.12
  3859.1  449.93  3953.2  445.87  3993.7  445.05  4043.9  441.79  4114.3   438.1
  4151.6  437.07  4275.1  435.59  4473.2  434.91  4475.9  434.41  4479.2  434.91
  4596.8  435.23    4828   438.3  4858.2  438.11  4934.9   435.6  4998.9  436.32
    5019  435.54  5039.1  436.33  5109.5  441.83  5169.8  445.53  5227.4  453.29
  5232.5  452.83  5290.5  459.72  5380.9  465.84  5441.2  472.88  5512.3  475.07
#Mann= 3 ,-1 , 0
  3423.2     .05       0  4473.2     .03       0  4479.2     .05       0
Bank Sta=4043.9,5109.5
XS Rating Curve= 0 ,0
Exp/Cntr=0.3,0.1

Type RM Length L Ch R = 1 ,7991    ,560,560,560
BEGIN DESCRIPTION:
UNT0168 IN SAND CR 17.0
END DESCRIPTION:
XS GIS Cut Line= 4
      3583807.29     10501401.34       3583815.1     10501818.04
      3583736.98      10501979.5      3583510.44     10502291.97
#Sta/Elev= 30
    4517  471.94  4837.4  445.75  4938.6   439.7  4982.2  432.33  4989.9  431.94
  4992.7  431.44  4995.9  431.94  5037.8  433.49  5066.2  437.79  5111.4  442.18
  5146.8  443.33  5161.5  446.49  5167.7  445.87  5176.2  440.51  5182.4  438.79
  5189.9  433.42  5197.1   432.5  5203.3     435  5211.8  434.42    5218  437.06
  5226.5  437.11  5232.7  440.05  5247.4  440.69  5253.5  443.48    5262  443.72
  5268.2  445.77  5312.3  448.83  5339.4  452.66  5404.3  457.93  5499.1  462.17
#Mann= 3 ,-1 , 0
    4517     .05       0  4989.9     .03       0  4995.9     .05       0
Bank Sta=4989.9,4995.9
XS Rating Curve= 0 ,0
Exp/Cntr=0.3,0.1

Type RM Length L Ch R = 1 ,7431    ,707,707,707
BEGIN DESCRIPTION:
UNT0168 IN SAND CR 15.0
END DESCRIPTION:
XS GIS Cut Line= 4
      3583585.32     10501157.83      3583298.88      10501674.3
       3583311.9     10501960.75      3583323.96     10502198.51
#Sta/Elev= 30
  4633.8  468.47  4647.3  468.43  4669.1  467.16  4696.5  464.16  4772.1  458.08
  4801.6  454.18  4831.6  450.19  4902.5  436.76  4924.3  434.17  4962.6  432.23
  4978.1  431.82  4989.6   430.4  4992.4   429.9  4995.6   430.4  5043.3  434.96
    5065  438.13  5124.6  449.14  5152.7  452.73  5175.6  454.42    5220  456.13
    5263  456.25  5321.8  457.61  5381.9  457.69  5406.2  457.14    5442  454.93
    5502  455.38  5532.1   454.1  5572.1  455.43  5652.2  459.56  5749.2  462.04
#Mann= 6 ,-1 , 0
  4633.8      .1       0  4801.6     .05       0  4962.6     .08       0
  4989.6     .07       0  4995.6     .08       0    5263     .05       0
Bank Sta=4989.6,4995.6
XS Rating Curve= 0 ,0
Exp/Cntr=0.3,0.1

Type RM Length L Ch R = 1 ,6724    ,590,590,590
BEGIN DESCRIPTION:
UNT0168 IN SAND CR 14.0
END DESCRIPTION:
XS GIS Cut Line= 2
       3583416.1     10500992.87      3582318.02     10501079.67
#Sta/Elev= 30
  4510.7  447.53  4559.2  446.09    4625   442.1  4725.4  442.87  4895.9  437.19
    4926  434.52  4956.1  430.36  4966.1   429.6  4976.1  429.83  4986.2  428.89
  4996.2  430.61  5013.3  427.69    5016  427.19  5019.3  427.69  5063.8   435.8
  5126.6  438.27  5146.7  440.08  5192.4  448.11  5216.9  450.72  5277.1  459.06
  5297.1  460.92  5316.1  464.19  5321.1  463.96  5337.3  466.74  5397.5  473.76
  5444.7  478.38  5484.9  480.35  5547.9  484.86  5573.4  486.08  5612.2  486.71
#Mann= 4 ,-1 , 0
  4510.7     .05       0  5013.3     .03       0  5019.3     .05       0
  5484.9     .08       0
Bank Sta=5013.3,5019.3
XS Rating Curve= 0 ,0
Exp/Cntr=0.3,0.1

Type RM Length L Ch R = 1 ,6134    ,655,655,655
BEGIN DESCRIPTION:
UNT0168 IN SAND CR 13.0
END DESCRIPTION:
XS GIS Cut Line= 3
      3583503.18     10500566.83      3582941.58     10500442.68
      3582541.58     10500442.68
#Sta/Elev= 30
       0  449.72    21.6  448.93    72.8  445.15      96  444.53   134.2  443.72
   154.7  443.96   205.9  442.65   298.1  442.51     422  440.69   460.5  438.48
   465.6  438.68   502.9  435.66   509.3  434.57   533.7  432.43   552.9  429.01
     558  429.02   564.4  427.66   572.3  426.94   604.6  427.14   624.6  426.19
   684.6   428.3   704.6  431.42   714.6  432.41   754.6  434.97   774.6  436.96
   804.6  442.99   834.6  447.25   904.6  456.25   944.6  462.55   975.2  464.96
#Mann= 3 , 0 , 0
       0     .05       0   533.7     .03       0   714.6     .05       0
Bank Sta=533.7,714.6
XS Rating Curve= 0 ,0
Exp/Cntr=0.3,0.1

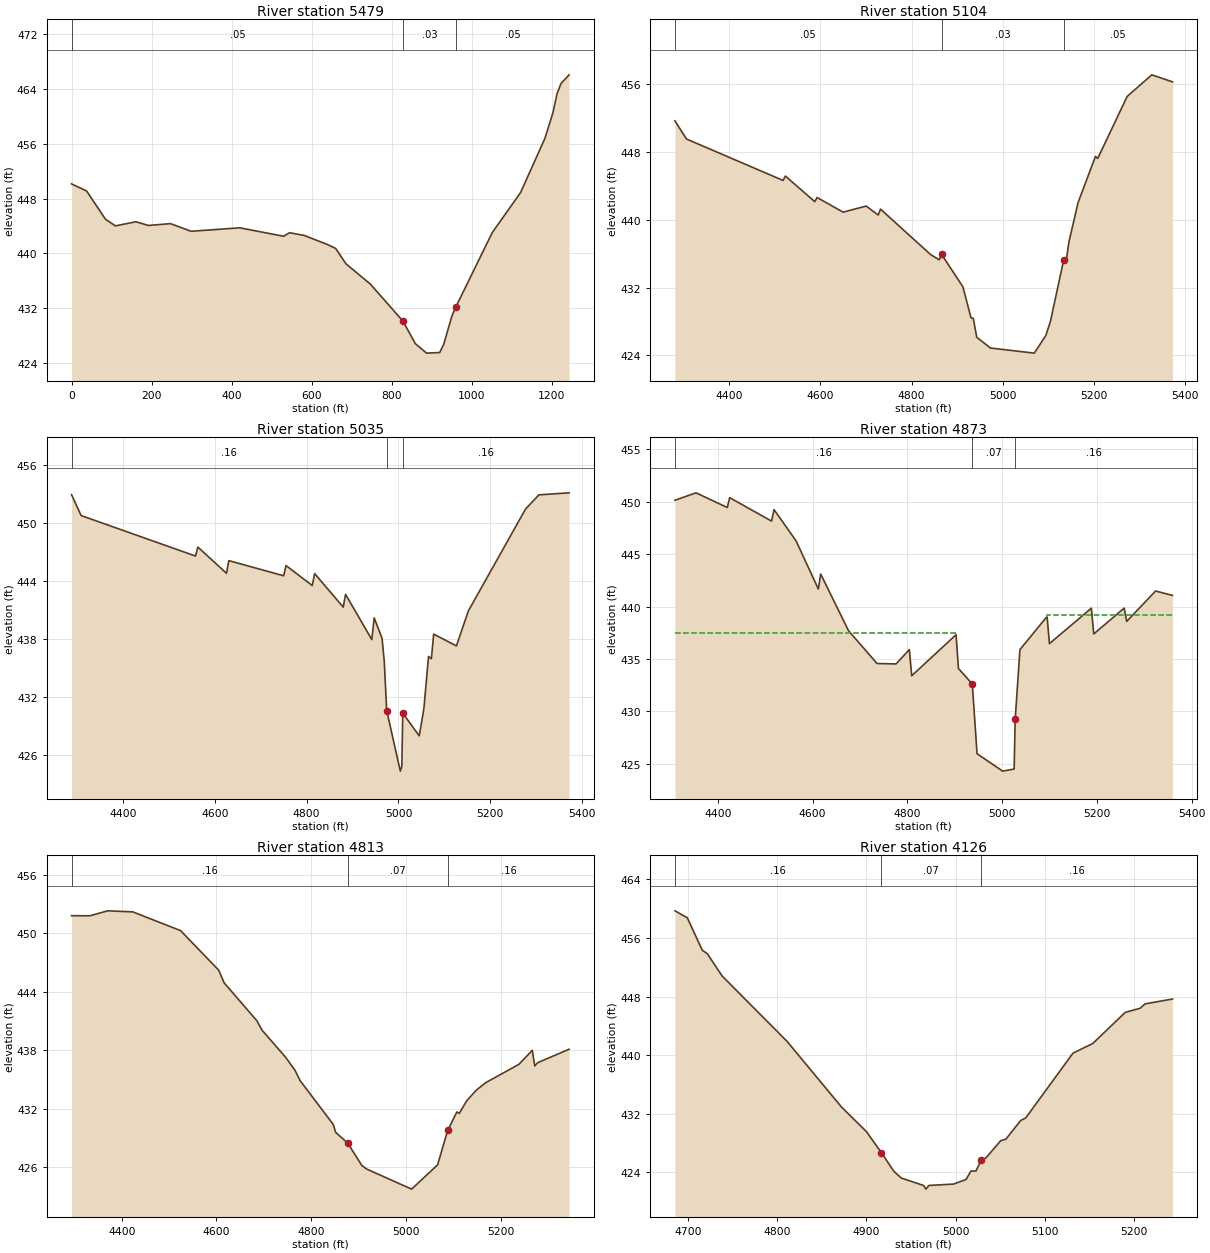
Type RM Length L Ch R = 1 ,5479    ,375,375,375
BEGIN DESCRIPTION:
UNT0168 IN SAND CR 12.0
END DESCRIPTION:
XS GIS Cut Line= 5
       3583568.6     10500256.98      3583348.63     10500203.41
      3583117.25     10499836.67      3582892.11     10499791.64
      3582542.11     10499741.64
#Sta/Elev= 30
       0  450.13    37.6   449.1    84.9  444.97   109.6  444.01   161.1  444.61
   191.9  444.07   247.1  444.34   298.9  443.22   420.1  443.73   529.6   442.5
   544.8  443.01   581.3  442.62     639   441.3     660  440.72   685.7  438.48
   746.9  435.51   828.4   430.1     859  426.84   887.1  425.46   919.9  425.55
     930  426.75   950.2  430.84   960.3   432.2  1051.3  443.04    1122  448.87
  1182.6  456.74  1202.8  460.49  1212.9  463.25    1223  464.76  1243.2  466.03
#Mann= 3 , 0 , 0
       0     .05       0   828.4     .03       0   960.3     .05       0
Bank Sta=828.4,960.3
XS Rating Curve= 0 ,0
Exp/Cntr=0.3,0.1

Type RM Length L Ch R = 1 ,5104    ,69,69,69
BEGIN DESCRIPTION:
UNT0168 IN SAND CR 11.3
END DESCRIPTION:
XS GIS Cut Line= 2
      3583617.15     10499522.05       3582537.2     10499362.31
#Sta/Elev= 30
  4280.8  451.67  4306.1  449.53  4518.1  444.64  4523.1  445.16  4587.6  442.14
  4592.7  442.63  4649.8   440.9  4700.4  441.62  4726.7  440.56  4731.8  441.26
  4841.9  435.89  4860.8  435.28  4865.8  435.92  4912.6   432.1  4930.3  428.45
  4935.4  428.37    4943  426.14  4973.3  424.87  5069.2  424.27  5094.6  426.35
  5104.7  428.02  5133.9   435.3    5139  435.03  5145.2  437.37  5165.4  442.04
  5203.5  447.48  5208.5  447.24    5273  454.55  5327.1   457.1  5372.5  456.27
#Mann= 3 , 0 , 0
  4280.8     .05       0  4865.8     .03       0  5133.9     .05       0
Bank Sta=4865.8,5133.9
XS Rating Curve= 0 ,0
Exp/Cntr=0.3,0.1

Type RM Length L Ch R = 1 ,5035    ,162,162,162
BEGIN DESCRIPTION:
UNT0168 IN SAND CR 11.2
END DESCRIPTION:
XS GIS Cut Line= 3
      3583610.16     10499459.54        3582756.     10499324.12
      3582537.27     10499313.71
#Sta/Elev= 30
  4287.9  452.91  4308.8  450.75    4558  446.56  4563.1  447.49  4625.4  444.78
  4630.5  446.09    4750  444.52  4755.1  445.58  4812.3  443.51  4817.4  444.75
  4879.7  441.28  4884.8   442.6    4942  437.92  4947.1  440.17  4964.3  438.05
 4969.09  435.68  4974.4  430.58  5004.1  424.32  5007.3  424.82  5009.4  430.31
  5045.3  427.97  5055.4  430.79  5065.5  436.18  5071.7  435.94  5076.7  438.49
  5126.3  437.27  5152.2  440.88  5276.8  451.42  5305.9  452.89  5371.7   453.1
#Mann= 3 , 0 , 0
  4287.9     .16       0  4974.4     .07       0  5009.4     .16       0
Bank Sta=4974.4,5009.4
XS Rating Curve= 0 ,0
Exp/Cntr=0.3,0.1

Type RM Length L Ch R = 1 ,4873    ,60,60,60
BEGIN DESCRIPTION:
UNT0168 IN SAND CR 11.0
END DESCRIPTION:
XS GIS Cut Line= 3
      3583596.32     10499258.15      3582662.25     10499160.93
      3582558.05     10499122.72
#Sta/Elev= 30
  4309.5  450.15    4354  450.86    4420  449.46    4425   450.4  4513.5  448.16
  4518.6  449.26  4565.1  446.28  4612.1  441.68  4617.1  443.11  4675.7  437.71
    4736  434.57  4776.2  434.53  4804.2   435.9  4809.2   433.4  4902.8  437.32
  4907.8   434.1  4937.1  432.61  4947.1  425.96  5001.1   424.3 5025.36   424.5
  5027.6  429.24  5037.6   435.9  5094.9  439.06  5099.9  436.47  5188.4  439.85
  5193.4  437.39  5257.6  439.86  5262.9  438.59  5323.9  441.49  5359.6  441.07
#Mann= 3 , 0 , 0
  4309.5     .16       0  4937.1     .07       0  5027.6     .16       0
#XS Ineff= 2 , 0
         4902.81  437.45 5094.94          439.19
Permanent Ineff=
       F       F
Bank Sta=4937.1,5027.6
XS Rating Curve= 0 ,0
Exp/Cntr=0.3,0.1

Type RM Length L Ch R = 1 ,4813    ,687,687,687
BEGIN DESCRIPTION:
UNT0168 IN SAND CR 11.1
END DESCRIPTION:
XS GIS Cut Line= 3
      3583620.58     10499216.48      3582849.75     10499119.26
      3582576.23     10499101.95
#Sta/Elev= 30
  4293.9   451.8  4332.7  451.79  4370.3   452.3  4423.4  452.19  4524.2  450.27
  4604.8  446.21  4616.1  444.92  4685.5  441.02  4696.4  440.05  4745.9  437.29
  4766.1  435.93  4776.7  434.88  4846.7  430.39  4851.9  429.57    4877  428.49
  4907.2  426.17  4917.3  425.81  5012.2  423.75  5067.1  426.24  5088.5  429.78
  5107.9  431.67  5112.9  431.51  5128.6  432.81  5148.6  433.89  5168.7  434.67
  5238.8  436.55  5267.2  437.99  5272.3  436.39  5278.9  436.73  5344.9   438.1
#Mann= 3 , 0 , 0
  4293.9     .16       0    4877     .07       0  5088.5     .16       0
Bank Sta=4877,5088.5
XS Rating Curve= 0 ,0
Exp/Cntr=0.3,0.1

Type RM Length L Ch R = 1 ,4126    ,871,871,871
BEGIN DESCRIPTION:
UNT0168 IN SAND CR 9.0
END DESCRIPTION:
XS GIS Cut Line= 3
      3583042.09     10498241.67      3582892.11     10498541.64
       3582792.1     10498741.65
#Sta/Elev= 30
  4684.8  459.69  4698.7  458.74  4715.5  454.32  4721.1  453.85  4737.9  450.79
  4810.5  441.92    4872  432.92    4900  429.57  4916.8   426.7  4930.7  424.17
  4939.1  423.24  4964.1  422.23  4966.8  421.73  4970.1  422.23  4997.8  422.42
  5011.8  423.04  5017.4   424.2    5023   424.2  5028.6  425.64  5034.2  425.99
  5050.9  428.35  5056.5  428.53  5073.3   431.1  5078.9  431.44    5132  440.28
  5154.3   441.6  5190.7  445.84  5207.5   446.4    5213     447  5243.8  447.66
#Mann= 3 , 0 , 0
  4684.8     .16       0  4916.8     .07       0  5028.6     .16       0
Bank Sta=4916.8,5028.6
XS Rating Curve= 0 ,0
Exp/Cntr=0.3,0.1

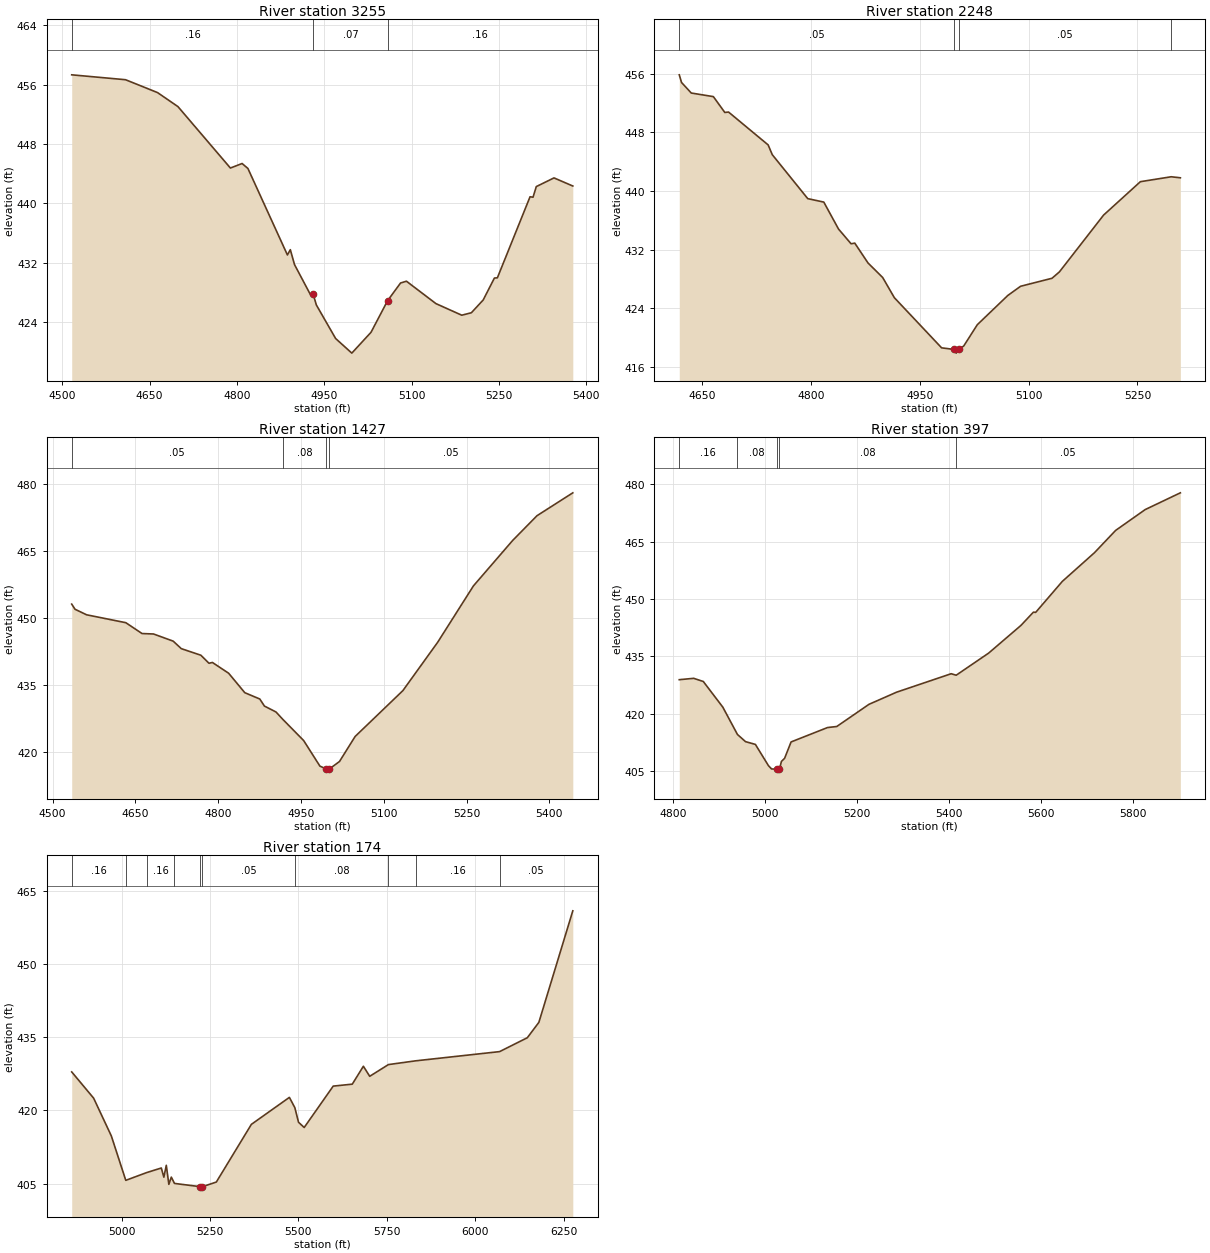
Type RM Length L Ch R = 1 ,3255    ,1007,1007,1007
BEGIN DESCRIPTION:
UNT0168 IN SAND CR 7.0
END DESCRIPTION:
XS GIS Cut Line= 3
      3582160.59     10498309.38      3582178.82     10498720.82
      3582105.91     10499163.51
#Sta/Elev= 30
  4516.4  457.32  4608.8  456.66  4663.7  454.93  4698.8  453.04  4788.9  444.76
    4809  445.37    4819   444.7  4886.8  433.05  4891.8  433.76    4899  431.75
  4926.2  427.72  4931.2  427.72  4936.5  426.31  4969.6  421.79  4997.4  419.82
  5030.4  422.63  5058.8  426.88  5081.1  429.27  5091.2  429.51  5141.9  426.49
  5186.2  424.93  5202.7  425.26    5223  426.98  5242.3  429.94  5247.4  429.97
  5303.5  440.89  5308.6  440.83  5314.2  442.26  5344.6  443.43  5376.9  442.34
#Mann= 3 , 0 , 0
  4516.4     .16       0  4931.2     .07       0  5058.8     .16       0
Bank Sta=4931.2,5058.8
XS Rating Curve= 0 ,0
Exp/Cntr=0.3,0.1

Type RM Length L Ch R = 1 ,2248    ,821,821,821
BEGIN DESCRIPTION:
UNT0168 IN SAND CR 5.0
END DESCRIPTION:
XS GIS Cut Line= 2
      3581337.94     10498325.36      3581219.88      10499005.9
#Sta/Elev= 30
  4618.4  455.82  4621.5  454.78  4634.9  453.34  4665.4  452.85  4681.2  450.69
  4686.3  450.75  4740.9  446.27  4746.6  444.94  4795.5  438.95  4817.6  438.48
  4837.9  434.81  4855.2   432.8  4860.3  432.89  4878.5  430.19  4898.8   428.2
  4914.9  425.45    4980  418.62  4997.3   418.4  5000.1   417.9  5003.3   418.4
  5010.5  418.87  5029.2  421.77  5071.3  425.76  5088.9  427.01  5132.2   428.1
  5142.4  428.97  5203.3  436.71    5254  441.26  5296.5  441.93  5309.1  441.79
#Mann= 4 ,-1 , 0
  4618.4     .05       0  4997.3    .035       0  5003.3     .05       0
  5296.5     .08       0
Bank Sta=4997.3,5003.3
XS Rating Curve= 0 ,0
Exp/Cntr=0.3,0.1

Type RM Length L Ch R = 1 ,1427    ,1030,1030,1030
BEGIN DESCRIPTION:
UNT0168 IN SAND CR 3.0
END DESCRIPTION:
XS GIS Cut Line= 2
      3580957.44     10498069.79      3580223.08     10498603.64
#Sta/Elev= 30
  4534.6  453.09  4540.6  451.94  4561.5   450.7  4632.6  448.93    4662   446.5
  4682.8   446.4  4718.4   444.8  4733.1  443.12  4768.6  441.64  4783.3  439.84
  4789.5  440.02  4818.9  437.61  4848.2  433.25  4875.3  431.84  4883.8  430.25
  4904.7  428.93  4916.9   427.3  4954.9  422.52  4984.3   416.8  4995.6  416.18
  4998.4  415.68  5001.6  416.18  5019.8  417.84  5048.1  423.44  5134.6  433.71
  5197.6  444.53  5262.5  457.18  5333.6  467.36  5377.6  472.89  5442.5  478.02
#Mann= 4 ,-1 , 0
  4534.6     .05       0  4916.9     .08       0  4995.6     .03       0
  5001.6     .05       0
Bank Sta=4995.6,5001.6
XS Rating Curve= 0 ,0
Exp/Cntr=0.3,0.1

Type RM Length L Ch R = 1 ,397     ,223,223,223
BEGIN DESCRIPTION:
UNT0168 IN SAND CR 1.0
END DESCRIPTION:
XS GIS Cut Line= 3
      3580223.09     10497418.74      3580046.01     10497608.84
      3579999.21     10498438.12
#Sta/Elev= 30
  4813.5  428.92  4844.8  429.28  4865.8  428.45  4908.3  421.75  4940.1  414.62
  4957.6  412.75  4979.1  412.03  5007.5  406.49  5014.3  405.62  5025.5  405.55
  5028.2  405.05  5031.5  405.55  5035.8  407.58  5042.7  408.39  5056.8  412.67
  5136.2  416.43  5156.2   416.7  5226.3  422.49  5286.4  425.66  5405.2  430.48
  5416.1  430.09  5486.8  435.87  5556.9  443.08  5584.1  446.55  5589.1   446.5
    5647  454.58  5717.1  462.09    5763  467.89  5827.3  473.33  5903.9  477.71
#Mann= 5 ,-1 , 0
  4813.5     .16       0  4940.1     .08       0  5025.5     .07       0
  5031.5     .08       0  5416.1     .05       0
Bank Sta=5025.5,5031.5
XS Rating Curve= 0 ,0
Exp/Cntr=0.3,0.1

Type RM Length L Ch R = 1 ,174     ,0,0,0
BEGIN DESCRIPTION:
UNT0168 IN SAND CR 1.01
END DESCRIPTION:
XS GIS Cut Line= 4
      3580154.03     10497352.33      3579979.52     10497357.54
      3579693.06     10497654.42      3579448.58     10498447.66
#Sta/Elev= 30
    4859  427.87    4921  422.49    4971  414.76  5011.9  405.65  5070.6  407.23
  5112.4  408.18  5119.6   406.3  5126.5  408.73  5133.7  404.83  5140.7  406.31
  5149.6  405.02  5222.6  404.35  5225.3  403.85  5228.6  404.35    5268   405.3
  5367.1  417.12  5474.6  422.65    5490  420.55  5500.5  417.55  5516.5  416.48
  5598.6  424.96  5652.5  425.36  5683.9  429.03  5701.8  426.97  5754.7  429.37
  5831.7  430.14  6069.2  432.03  6147.5  434.87  6180.2  438.02  6276.2  460.88
#Mann= 10 ,-1 , 0
    4859     .16       0  5011.9     .05       0  5070.6     .16       0
  5149.6     .05       0  5222.6     .07       0  5228.6     .05       0
    5490     .08       0  5754.7     .05       0  5831.7     .16       0
  6069.2     .05       0
Bank Sta=5222.6,5228.6
XS Rating Curve= 0 ,0
Exp/Cntr=0.3,0.1

Chan Stop Cuts=-1
Use User Specified Reach Order=0
Composite Channel Slope=5