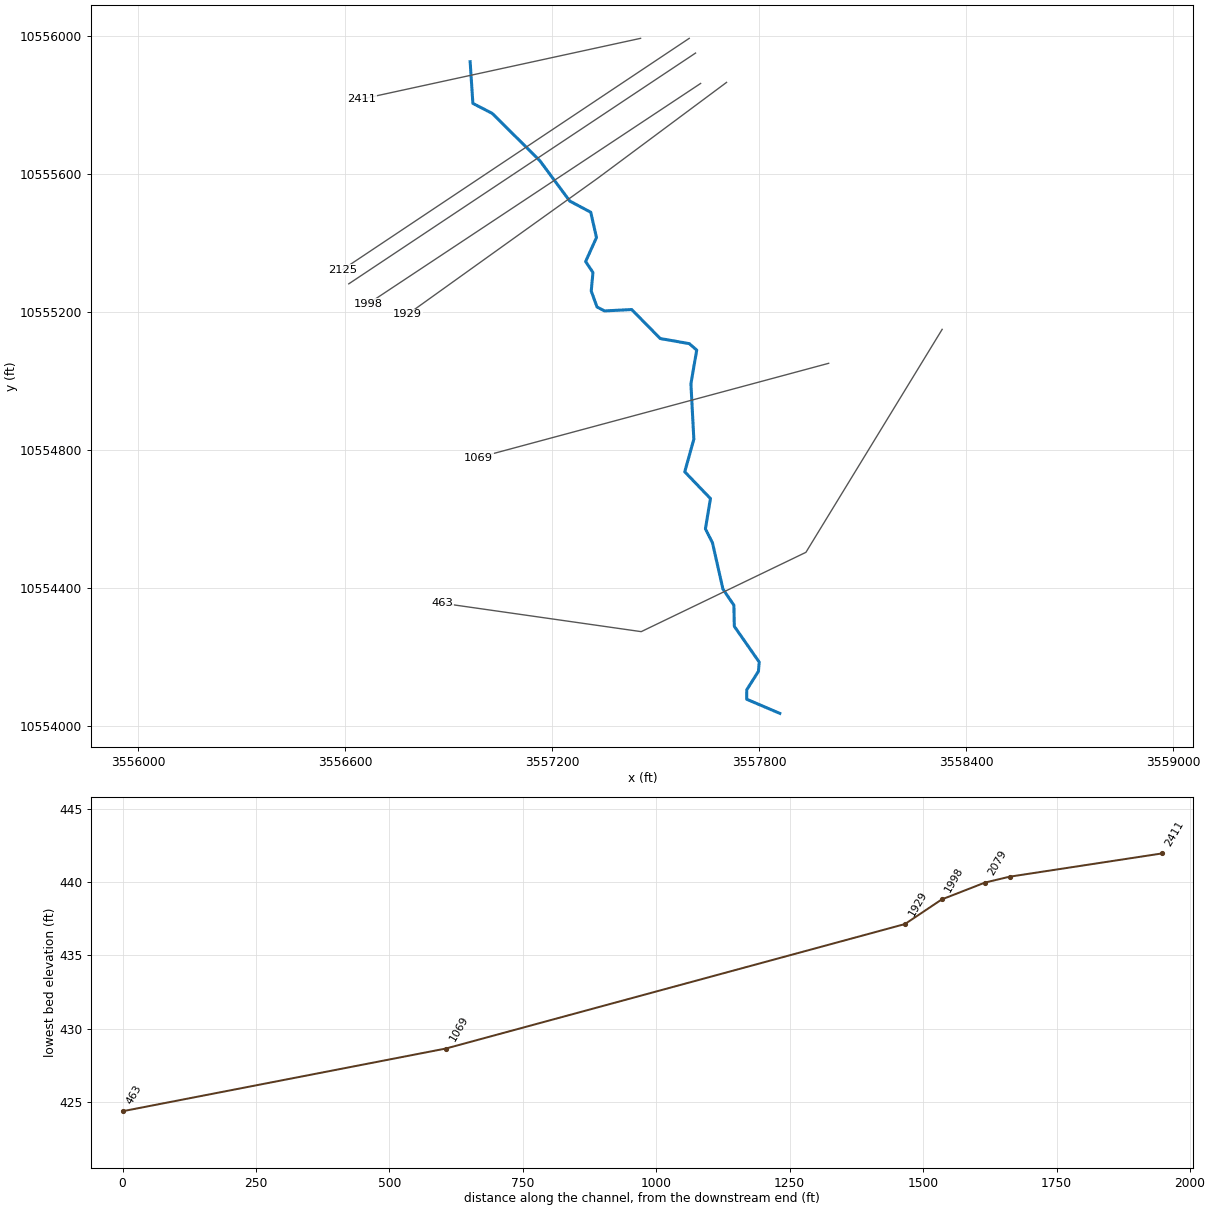
--- UNT01688 IN SAND CR.prj (project) ---

Proj Title=UNT01688 IN SAND CR Base Level Engineering
Current Plan=p01
Default Exp/Contr=0.3,0.1
English Units
Geom File=g01
Flow File=f01
Plan File=p01
BEGIN DESCRIPTION:
UNT01688 IN SAND CR
END DESCRIPTION:

--- UNT01688 IN SAND CR.p01 (plan) ---

Plan Title=Multiple Run
Short Identifier=Multiple
Geom File=g01
Flow File=f01
Subcritical Flow
K Sum by GR= 0
Std Step Tol= 0.01
Critical Tol= 0.01
Num of Std Step Trials= 20
Max Error Tol= 0.3
Flow Tol Ratio= 0.001
Split Flow NTrial= 30
Split Flow Tol= 0.02
Split Flow Ratio= 0.02
Log Output Level= 0
Friction Slope Method= 1
Unsteady Friction Slope Method= 2
Unsteady Bridges Friction Slope Method= 1
Parabolic Critical Depth
Global Vel Dist=  1 , 1 , 1
Global Log Level= 0
CheckData=True
Encroach Param= -1, 0, 0, 0
BEGIN DESCRIPTION:
Multiple Run
END DESCRIPTION:

--- UNT01688 IN SAND CR.f01 (steady flow) ---

Flow Title=Multiple
Number of Profiles=7
Profile Names=10-year,25-year,50-year,1pct_min,100-year,1pct_plu,500-year
River Rch & RM= UNT01688 IN SAND,Reach-1,2411
     327     417     485     415     561     758     743
Boundary for River Rch & Prof#=UNT01688 IN SAND,Reach-1,1
Up Type=0
Dn Type=3
Dn Slope=0.005
Boundary for River Rch & Prof#=UNT01688 IN SAND,Reach-1,2
Up Type=0
Dn Type=3
Dn Slope=0.005
Boundary for River Rch & Prof#=UNT01688 IN SAND,Reach-1,3
Up Type=0
Dn Type=3
Dn Slope=0.005
Boundary for River Rch & Prof#=UNT01688 IN SAND,Reach-1,4
Up Type=0
Dn Type=3
Dn Slope=0.005
Boundary for River Rch & Prof#=UNT01688 IN SAND,Reach-1,5
Up Type=0
Dn Type=3
Dn Slope=0.005
Boundary for River Rch & Prof#=UNT01688 IN SAND,Reach-1,6
Up Type=0
Dn Type=3
Dn Slope=0.005
Boundary for River Rch & Prof#=UNT01688 IN SAND,Reach-1,7
Up Type=0
Dn Type=3
Dn Slope=0.005

--- UNT01688 IN SAND CR.g01 (geometry) ---

Geom Title=Existing Conditions

River Reach=UNT01688 IN SAND,Reach-1
Reach XY= 30
      3556962.11     10555926.64      3556970.04     10555805.87
      3557025.88     10555777.06      3557164.03     10555639.94
      3557250.84     10555522.63      3557311.72     10555490.17
      3557328.35     10555416.70      3557296.87     10555347.31
      3557318.13     10555315.51      3557313.13     10555261.86
      3557329.89     10555215.47      3557351.69     10555204.02
      3557430.41     10555208.06      3557513.15     10555123.95
      3557597.46     10555109.09      3557618.84     10555090.47
      3557602.10     10554992.61      3557610.54     10554831.89
      3557584.20     10554737.45      3557658.67     10554659.93
      3557644.12     10554572.03      3557664.66     10554531.22
      3557694.92     10554397.28      3557726.65     10554350.47
      3557727.88     10554289.38      3557800.00     10554185.73
      3557797.83     10554159.02      3557763.93     10554105.18
      3557763.80     10554077.90      3557859.81     10554036.91

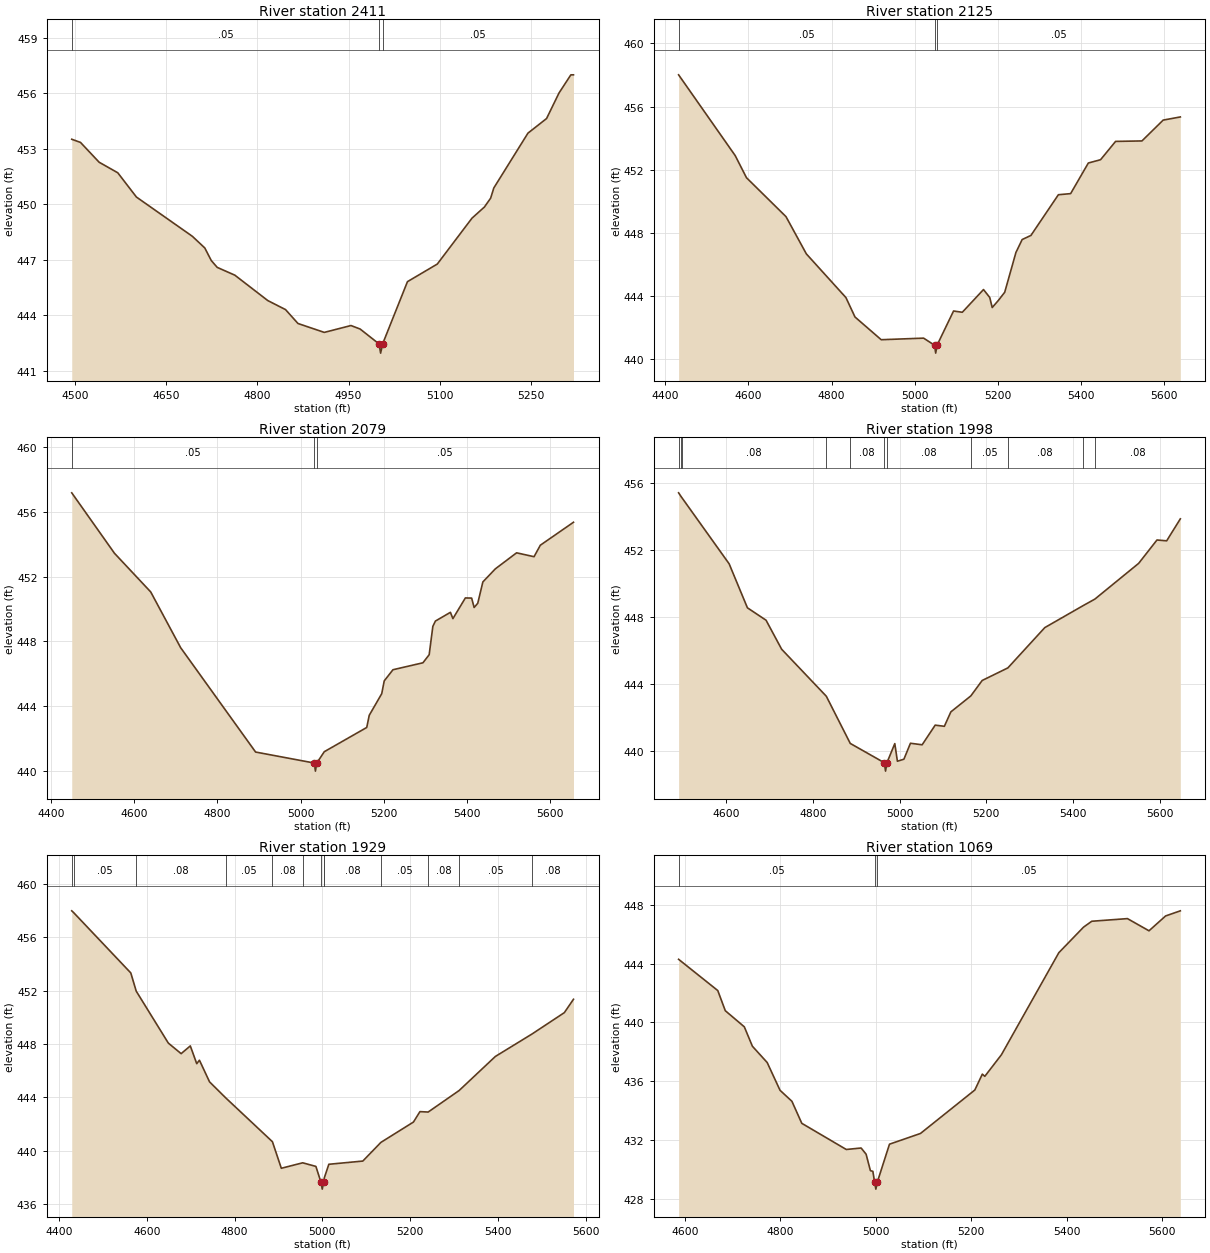
Type RM Length L Ch R = 1,2411,286,286,286
BEGIN DESCRIPTION:
UNT01688 IN SAND CR 5.3
END DESCRIPTION:
XS GIS Cut Line= 2
      3557456.19     10555994.54      3556648.81     10555818.74
#Sta/Elev= 30
  4494.2  453.51  4508.6  453.34  4539.3  452.27  4570.0  451.70  4600.7  450.39
  4692.8  448.27  4713.3  447.64  4724.0  446.96  4733.8  446.59  4762.8  446.17
  4817.0  444.80  4846.3  444.31  4866.8  443.56  4910.1  443.08  4954.1  443.45
  4969.2  443.26  5000.2  442.46  5002.9  441.96  5006.2  442.46  5047.1  445.82
  5096.2  446.77  5153.4  449.25  5173.8  449.85  5184.1  450.33  5189.3  450.88
  5245.5  453.84  5276.2  454.63  5296.7  456.01  5316.2  456.99  5320.5  456.99
#Mann=3,-1,0
  4494.2    0.05       0  5000.2    0.03       0  5006.2    0.05       0
Bank Sta=5000.2,5006.2
Exp/Cntr=0.3,0.1

Type RM Length L Ch R = 1,2125,46,46,46
BEGIN DESCRIPTION:
UNT01688 IN SAND CR 5.4
END DESCRIPTION:
XS GIS Cut Line= 2
      3557597.19     10555994.52      3556592.41     10555323.94
#Sta/Elev= 30
  4431.8  458.01  4568.1  452.89  4595.2  451.49  4690.4  449.02  4739.4  446.66
  4834.7  443.89  4856.5  442.66  4919.6  441.22  5021.7  441.32  5048.1  440.87
  5050.8  440.37  5054.1  440.87  5093.8  443.04  5114.9  442.96  5165.9  444.40
  5180.9  443.90  5186.9  443.26  5202.0  443.72  5217.0  444.23  5244.0  446.75
  5259.0  447.57  5280.1  447.83  5346.2  450.41  5375.7  450.48  5418.3  452.42
  5447.8  452.63  5483.9  453.79  5547.4  453.82  5598.5  455.14  5639.8  455.34
#Mann=3,-1,0
  4431.8    0.05       0  5048.1    0.03       0  5054.1    0.05       0
Bank Sta=5048.1,5054.1
Exp/Cntr=0.3,0.1

Type RM Length L Ch R = 1,2079,81,81,81
BEGIN DESCRIPTION:
UNT01688 IN SAND CR 5.1
END DESCRIPTION:
XS GIS Cut Line= 2
      3557615.52     10555951.86      3556610.34     10555282.60
#Sta/Elev= 30
  4449.4  457.18  4552.3  453.44  4639.5  451.05  4711.6  447.60  4891.9  441.15
  5033.2  440.47  5035.9  439.97  5039.2  440.47  5057.2  441.17  5159.4  442.67
  5165.4  443.42  5195.5  444.76  5201.5  445.55  5222.5  446.24  5294.7  446.67
  5309.7  447.17  5318.5  448.92  5324.7  449.25  5360.8  449.79  5366.8  449.40
  5396.8  450.68  5411.9  450.67  5417.9  450.09  5426.6  450.35  5438.9  451.67
  5469.0  452.48  5520.1  453.47  5562.1  453.23  5577.2  453.94  5657.0  455.36
#Mann=3,-1,0
  4449.4    0.05       0  5033.2    0.03       0  5039.2    0.05       0
Bank Sta=5033.2,5039.2
Exp/Cntr=0.3,0.1

Type RM Length L Ch R = 1,1998,69,69,69
BEGIN DESCRIPTION:
UNT01688 IN SAND CR 5.2
END DESCRIPTION:
XS GIS Cut Line= 2
      3557630.25     10555863.73      3556665.82     10555224.39
#Sta/Elev= 30
  4490.4  455.40  4494.8  455.23  4498.0  455.11  4607.0  451.17  4649.1  448.55
  4692.1  447.81  4728.1  446.08  4831.1  443.28  4886.3  440.47  4964.9  439.32
  4967.7  438.82  4970.9  439.32  4989.0  440.46  4995.0  439.41  5010.0  439.53
  5025.1  440.48  5052.1  440.39  5082.2  441.56  5103.3  441.49  5118.3  442.35
  5164.3  443.30  5190.5  444.22  5249.8  444.97  5334.9  447.37  5422.0  448.66
  5450.5  449.07  5551.5  451.20  5593.6  452.59  5616.0  452.54  5647.5  453.85
#Mann=11,-1,0
  4490.4    0.08       0  4494.8    0.05       0  4498.0    0.08       0
  4831.1    0.05       0  4886.3    0.08       0  4964.9    0.07       0
  4970.9    0.08       0  5164.3    0.05       0  5249.8    0.08       0
  5422.0    0.05       0  5450.5    0.08       0
Bank Sta=4964.9,4970.9
Exp/Cntr=0.3,0.1

Type RM Length L Ch R = 1,1929,860,860,860
BEGIN DESCRIPTION:
UNT01688 IN SAND CR 5.0
END DESCRIPTION:
XS GIS Cut Line= 3
      3557705.39     10555866.81      3557332.13     10555589.03
      3556780.91     10555194.06
#Sta/Elev= 30
  4429.1  457.97  4433.3  457.84  4563.7  453.32  4576.0  451.96  4649.2  448.07
  4678.4  447.28  4699.3  447.86  4713.9  446.53  4720.1  446.79  4743.1  445.17
  4780.3  443.96  4886.4  440.69  4906.7  438.70  4955.4  439.11  4985.5  438.84
  4997.2  437.64  5000.0  437.14  5003.2  437.64  5004.8  438.00  5015.0  439.00
  5092.4  439.24  5133.7  440.64  5207.8  442.16  5222.6  442.94  5241.4  442.91
  5311.9  444.52  5394.5  447.07  5478.0  448.75  5551.7  450.35  5572.5  451.35
#Mann=13,-1,0
  4429.1    0.08       0  4433.3    0.05       0  4576.0    0.08       0
  4780.3    0.05       0  4886.4    0.08       0  4955.4    0.05       0
  4997.2    0.03       0  5003.2    0.05       0  5004.8    0.08       0
  5133.7    0.05       0  5241.4    0.08       0  5311.9    0.05       0
  5478.0    0.08       0
Bank Sta=4997.2,5003.2
Exp/Cntr=0.3,0.1

Type RM Length L Ch R = 1,1069,606,606,606
BEGIN DESCRIPTION:
UNT01688 IN SAND CR 2.0
END DESCRIPTION:
XS GIS Cut Line= 2
      3558001.36     10555052.12      3556986.40     10554778.86
#Sta/Elev= 30
  4586.7  444.30  4668.8  442.17  4684.5  440.80  4724.4  439.70  4741.3  438.38
  4772.3  437.27  4799.2  435.38  4824.1  434.63  4844.8  433.13  4938.0  431.35
  4969.1  431.45  4979.5  431.03  4988.5  429.91  4993.7  429.86  4997.2  429.15
  4999.9  428.65  5003.2  429.15  5028.5  431.71  5093.4  432.44  5207.3  435.40
  5223.0  436.48  5228.2  436.33  5263.0  437.80  5383.3  444.75  5435.1  446.49
  5452.3  446.89  5527.0  447.07  5572.2  446.24  5606.9  447.25  5637.8  447.60
#Mann=3,-1,0
  4586.7    0.05       0  4997.2    0.03       0  5003.2    0.05       0
Bank Sta=4997.2,5003.2
Exp/Cntr=0.3,0.1

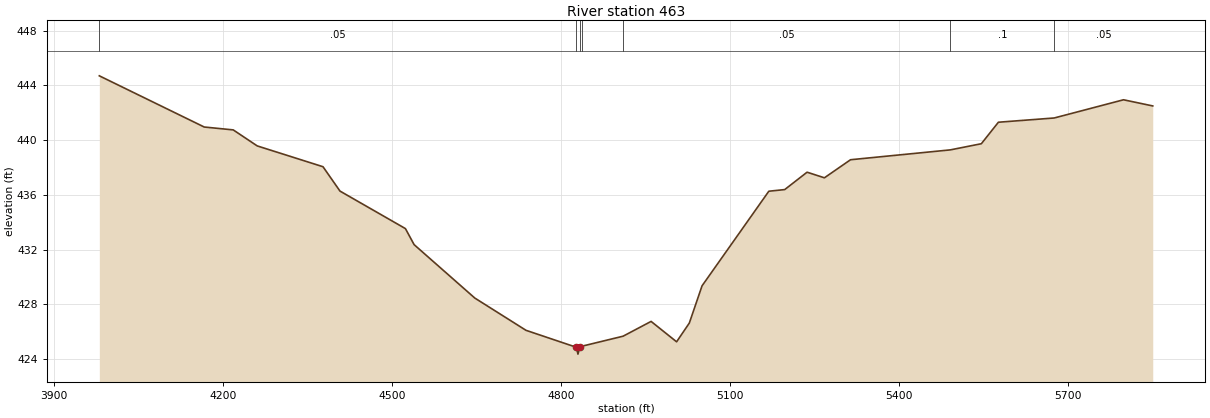
Type RM Length L Ch R = 1,463,0,0,0
BEGIN DESCRIPTION:
UNT01688 IN SAND CR 1.0
END DESCRIPTION:
XS GIS Cut Line= 4
      3558330.38     10555150.64      3557935.43     10554503.96
      3557458.00     10554273.93      3556880.76     10554356.39
#Sta/Elev= 30
  3980.5  444.70  4166.8  440.96  4218.3  440.75  4260.9  439.58  4377.7  438.06
  4407.9  436.28  4524.1  433.54  4539.5  432.37  4647.2  428.47  4738.2  426.11
  4827.7  424.87  4830.5  424.37  4833.7  424.87  4837.7  424.95  4910.7  425.68
  4960.4  426.76  5005.7  425.27  5028.3  426.64  5050.9  429.36  5169.5  436.27
  5197.7  436.39  5237.4  437.66  5268.2  437.25  5314.6  438.57  5491.8  439.29
  5546.9  439.74  5577.2  441.31  5676.3  441.62  5799.4  442.95  5851.3  442.50
#Mann=7,-1,0
  3980.5    0.05       0  4827.7   0.035       0  4833.7    0.05       0
  4837.7     0.1       0  4910.7    0.05       0  5491.8     0.1       0
  5676.3    0.05       0
Bank Sta=4827.7,4833.7
Exp/Cntr=0.3,0.1

Chan Stop Cuts=-1