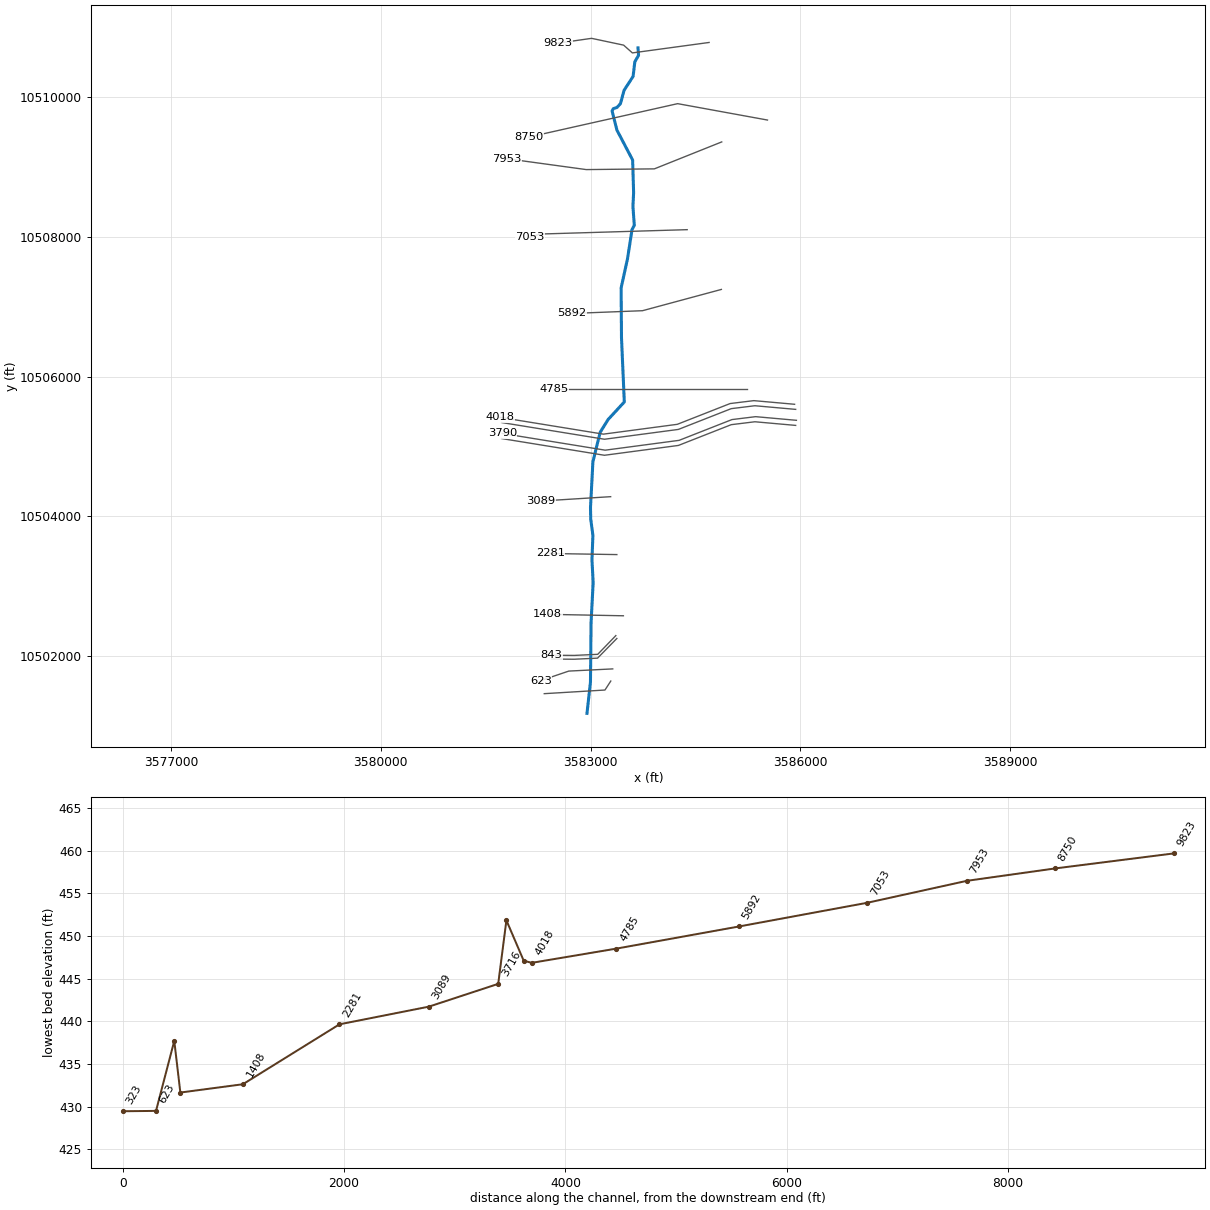
--- UNT0169 IN SAND CR.prj (project) ---

Proj Title=UNT0169 IN SAND CR Base Level Engineering
Current Plan=p01
Default Exp/Contr=0.3,0.1
English Units
Geom File=g01
Flow File=f01
Plan File=p01
BEGIN DESCRIPTION:
UNT0169 IN SAND CR
END DESCRIPTION:

--- UNT0169 IN SAND CR.p01 (plan) ---

Plan Title=Multiple Run
Short Identifier=Multiple
Geom File=g01
Flow File=f01
Subcritical Flow
K Sum by GR= 0
Std Step Tol= 0.01
Critical Tol= 0.01
Num of Std Step Trials= 20
Max Error Tol= 0.3
Flow Tol Ratio= 0.001
Split Flow NTrial= 30
Split Flow Tol= 0.02
Split Flow Ratio= 0.02
Log Output Level= 0
Friction Slope Method= 1
Unsteady Friction Slope Method= 2
Unsteady Bridges Friction Slope Method= 1
Parabolic Critical Depth
Global Vel Dist=  1 , 1 , 1
Global Log Level= 0
CheckData=True
Encroach Param= -1, 0, 0, 0
BEGIN DESCRIPTION:
Multiple Run
END DESCRIPTION:

--- UNT0169 IN SAND CR.f01 (steady flow) ---

Flow Title=Multiple
Number of Profiles=7
Profile Names=10-year,25-year,50-year,1pct_min,100-year,1pct_plu,500-year
River Rch & RM= UNT0169 IN SAND ,Reach-1,9823
    1767    2508    3139    2862    3871    5235    5872
Boundary for River Rch & Prof#=UNT0169 IN SAND ,Reach-1,1
Up Type=0
Dn Type=3
Dn Slope=0.005
Boundary for River Rch & Prof#=UNT0169 IN SAND ,Reach-1,2
Up Type=0
Dn Type=3
Dn Slope=0.005
Boundary for River Rch & Prof#=UNT0169 IN SAND ,Reach-1,3
Up Type=0
Dn Type=3
Dn Slope=0.005
Boundary for River Rch & Prof#=UNT0169 IN SAND ,Reach-1,4
Up Type=0
Dn Type=3
Dn Slope=0.005
Boundary for River Rch & Prof#=UNT0169 IN SAND ,Reach-1,5
Up Type=0
Dn Type=3
Dn Slope=0.005
Boundary for River Rch & Prof#=UNT0169 IN SAND ,Reach-1,6
Up Type=0
Dn Type=3
Dn Slope=0.005
Boundary for River Rch & Prof#=UNT0169 IN SAND ,Reach-1,7
Up Type=0
Dn Type=3
Dn Slope=0.005

--- UNT0169 IN SAND CR.g01 (geometry) ---

Geom Title=Existing Conditions

River Reach=UNT0169 IN SAND ,Reach-1
Reach XY= 30
      3583677.04     10510699.77      3583685.37     10510593.78
      3583631.98     10510500.03      3583607.24     10510291.69
      3583478.34     10510092.47      3583426.25     10509901.07
      3583375.47     10509846.38      3583324.69     10509830.76
      3583306.46     10509796.90      3583376.17     10509523.33
      3583600.55     10509095.79      3583614.66     10508629.21
      3583604.89     10508431.72      3583624.42     10508161.54
      3583592.11     10508100.78      3583527.20     10507683.28
      3583436.05     10507266.61      3583441.26     10506555.67
      3583481.50     10505635.56      3583251.53     10505387.48
      3583136.94     10505203.45      3583032.78     10504783.32
      3582998.05     10504127.07      3583001.53     10503960.40
      3583032.78     10503727.76      3583018.89     10503380.54
      3583036.25     10503054.15      3583006.37     10502485.34
      3582997.68     10501632.47      3582947.77     10501183.25

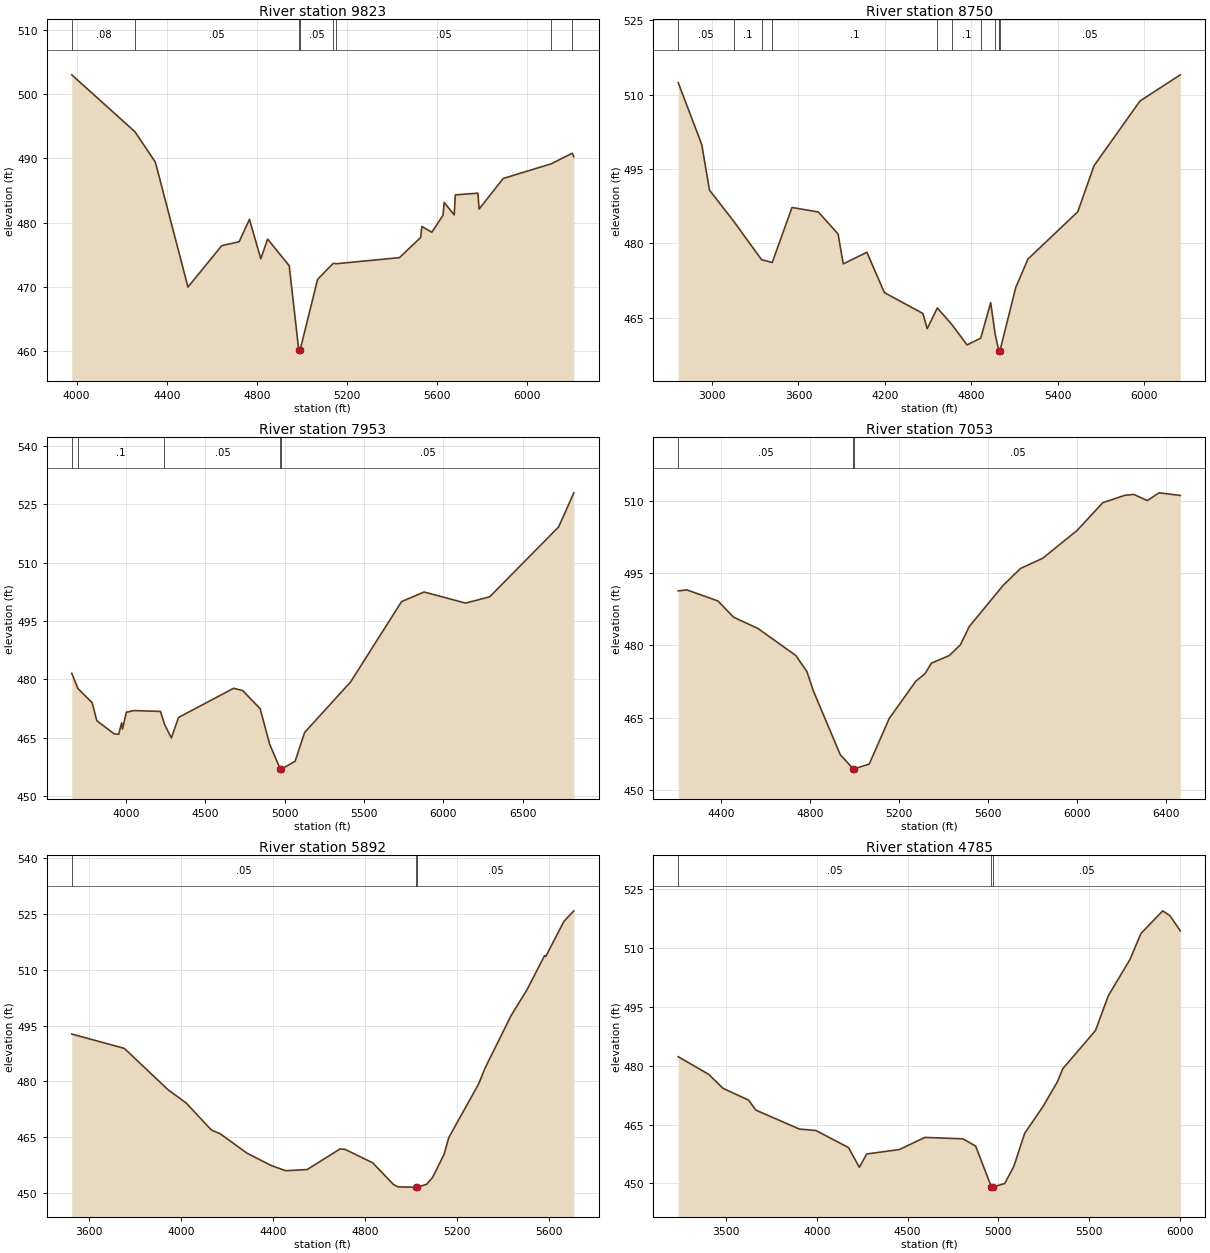
Type RM Length L Ch R = 1,9823,1073,1073,1073
BEGIN DESCRIPTION:
UNT0169 IN SAND CR 21.0
END DESCRIPTION:
XS GIS Cut Line= 5
      3584694.08     10510776.85      3583596.81     10510627.54
      3583471.81     10510738.65      3583013.48     10510835.87
      3582531.59     10510766.54
#Sta/Elev= 30
  3978.4  503.02  4259.5  494.14  4349.8  489.41  4494.6  469.97  4644.4  476.41
  4721.9  477.03  4767.6  480.51  4818.0  474.37  4848.3  477.44  4944.2  473.29
  4986.6  460.18  4989.4  459.68  4992.6  460.18  5070.3  471.17  5139.9  473.67
  5152.1  473.60  5433.9  474.55  5528.1  477.69  5533.2  479.40  5577.7  478.51
  5627.4  481.15  5632.5  483.15  5677.0  481.21  5682.1  484.33  5782.4  484.59
  5787.5  482.11  5894.7  486.88  6107.7  489.16  6201.2  490.81  6208.4  490.27
#Mann=8,-1,0
  3978.4    0.08       0  4259.5    0.05       0  4986.6    0.03       0
  4992.6    0.05       0  5139.9    0.07       0  5152.1    0.05       0
  6107.7     0.1       0  6201.2    0.05       0
Bank Sta=4986.6,4992.6
Exp/Cntr=0.3,0.1

Type RM Length L Ch R = 1,8750,797,797,797
BEGIN DESCRIPTION:
UNT0169 IN SAND CR 19.0
END DESCRIPTION:
XS GIS Cut Line= 3
      3585529.04     10509667.44      3584244.31     10509901.82
      3582117.57     10509424.39
#Sta/Elev= 30
  2765.5  512.39  2929.1  499.91  2982.4  490.75  3150.9  484.47  3343.7  476.75
  3418.0  476.17  3555.3  487.25  3738.2  486.35  3875.4  481.91  3911.0  475.90
  4075.1  478.23  4196.7  470.11  4464.3  465.90  4493.9  462.84  4564.2  467.02
  4664.7  463.70  4770.6  459.57  4865.6  460.94  4934.6  468.09  4966.0  461.71
  4989.6  458.60  4993.1  458.42  4995.8  457.92  4999.1  458.42  5108.8  471.14
  5193.4  476.87  5539.3  486.39  5652.2  495.67  5970.9  508.70  6251.1  513.97
#Mann=11,-1,0
  2765.5    0.05       0  3150.9     0.1       0  3343.7    0.05       0
  3418.0     0.1       0  4564.2    0.08       0  4664.7     0.1       0
  4865.6    0.05       0  4966.0     0.1       0  4989.6    0.05       0
  4993.1    0.03       0  4999.1    0.05       0
Bank Sta=4993.1,4999.1
Exp/Cntr=0.3,0.1

Type RM Length L Ch R = 1,7953,900,900,900
BEGIN DESCRIPTION:
UNT0169 IN SAND CR 16.0
END DESCRIPTION:
XS GIS Cut Line= 4
      3584874.81     10509354.84      3583911.29     10508969.43
      3582937.33     10508959.02      3581796.94     10509115.24
#Sta/Elev= 30
  3658.9  481.58  3697.6  477.69  3787.2  474.03  3816.8  469.41  3924.5  466.07
  3954.1  465.92  3973.0  468.84  3978.4  467.26  4002.6  471.58  4049.5  472.01
  4218.0  471.79  4242.9  468.52  4286.5  464.98  4331.1  470.23  4678.4  477.73
  4735.8  477.14  4845.8  472.47  4905.8  463.35  4972.8  456.97  4975.6  456.47
  4978.8  456.97  5065.9  459.01  5125.9  466.40  5415.9  479.39  5736.5  499.98
  5878.5  502.44  6140.2  499.59  6291.6  501.21  6725.6  519.13  6821.7  527.89
#Mann=5,-1,0
  3658.9    0.05       0  3697.6     0.1       0  4242.9    0.05       0
  4972.8    0.03       0  4978.8    0.05       0
Bank Sta=4972.8,4978.8
Exp/Cntr=0.3,0.1

Type RM Length L Ch R = 1,7053,1161,1161,1161
BEGIN DESCRIPTION:
UNT0169 IN SAND CR 14.0
END DESCRIPTION:
XS GIS Cut Line= 3
      3584380.67     10508100.01      3582281.66     10508037.51
      3582130.61     10507990.63
#Sta/Elev= 30
  4207.3  491.34  4245.9  491.55  4385.9  489.25  4456.0  485.88  4566.0  483.53
  4736.1  477.92  4786.1  474.58  4816.1  470.45  4936.2  457.30  4993.9  454.40
  4996.6  453.90  4999.9  454.40  5066.2  455.36  5156.3  464.84  5276.3  472.61
  5316.4  474.11  5346.4  476.34  5426.4  477.91  5476.4  480.14  5516.4  483.95
  5668.0  492.45  5746.5  495.99  5846.6  498.12  6001.1  503.89  6116.7  509.66
  6216.8  511.21  6256.8  511.37  6317.2  510.10  6369.6  511.71  6465.4  511.17
#Mann=3,-1,0
  4207.3    0.05       0  4993.9    0.03       0  4999.9    0.05       0
Bank Sta=4993.9,4999.9
Exp/Cntr=0.3,0.1

Type RM Length L Ch R = 1,5892,1107,1107,1107
BEGIN DESCRIPTION:
UNT0169 IN SAND CR 12.0
END DESCRIPTION:
XS GIS Cut Line= 3
      3584869.60     10507245.47      3583741.64     10506941.17
      3582728.99     10506901.73
#Sta/Elev= 30
  3525.9  492.72  3754.1  488.88  3943.3  477.84  4023.1  474.22  4132.5  466.99
  4172.4  465.91  4286.9  460.78  4393.3  457.43  4455.5  456.06  4548.7  456.37
  4691.4  461.89  4713.7  461.78  4833.8  458.17  4923.9  452.36  4943.9  451.71
  5021.0  451.62  5023.7  451.12  5027.0  451.62  5068.3  452.43  5094.0  454.28
  5144.1  460.51  5164.1  464.94  5294.2  479.37  5321.8  483.59  5434.3  497.60
  5504.3  504.64  5580.4  513.77  5585.4  513.51  5664.5  522.95  5707.6  525.77
#Mann=3,-1,0
  3525.9    0.05       0  5021.0    0.03       0  5027.0    0.05       0
Bank Sta=5021,5027
Exp/Cntr=0.3,0.1

Type RM Length L Ch R = 1,4785,767,767,767
BEGIN DESCRIPTION:
UNT0169 IN SAND CR 10.0
END DESCRIPTION:
XS GIS Cut Line= 2
      3585239.45     10505823.60      3582475.45     10505823.60
#Sta/Elev= 30
  3237.5  482.29  3404.8  477.81  3484.8  474.21  3624.8  471.23  3664.8  468.68
  3904.8  463.84  3994.8  463.49  4174.8  459.13  4234.8  454.08  4274.8  457.49
  4454.8  458.62  4594.8  461.72  4804.8  461.36  4874.8  459.51  4961.8  449.03
  4964.6  448.53  4967.8  449.03  5034.8  449.97  5084.8  454.31  5144.8  462.77
  5244.8  469.54  5324.8  475.88  5354.8  479.24  5534.8  488.99  5604.8  497.81
  5724.8  507.13  5784.8  513.71  5904.8  519.49  5944.8  518.23  6001.5  514.39
#Mann=3,-1,0
  3237.5    0.05       0  4961.8    0.03       0  4967.8    0.05       0
Bank Sta=4961.8,4967.8
Exp/Cntr=0.3,0.1

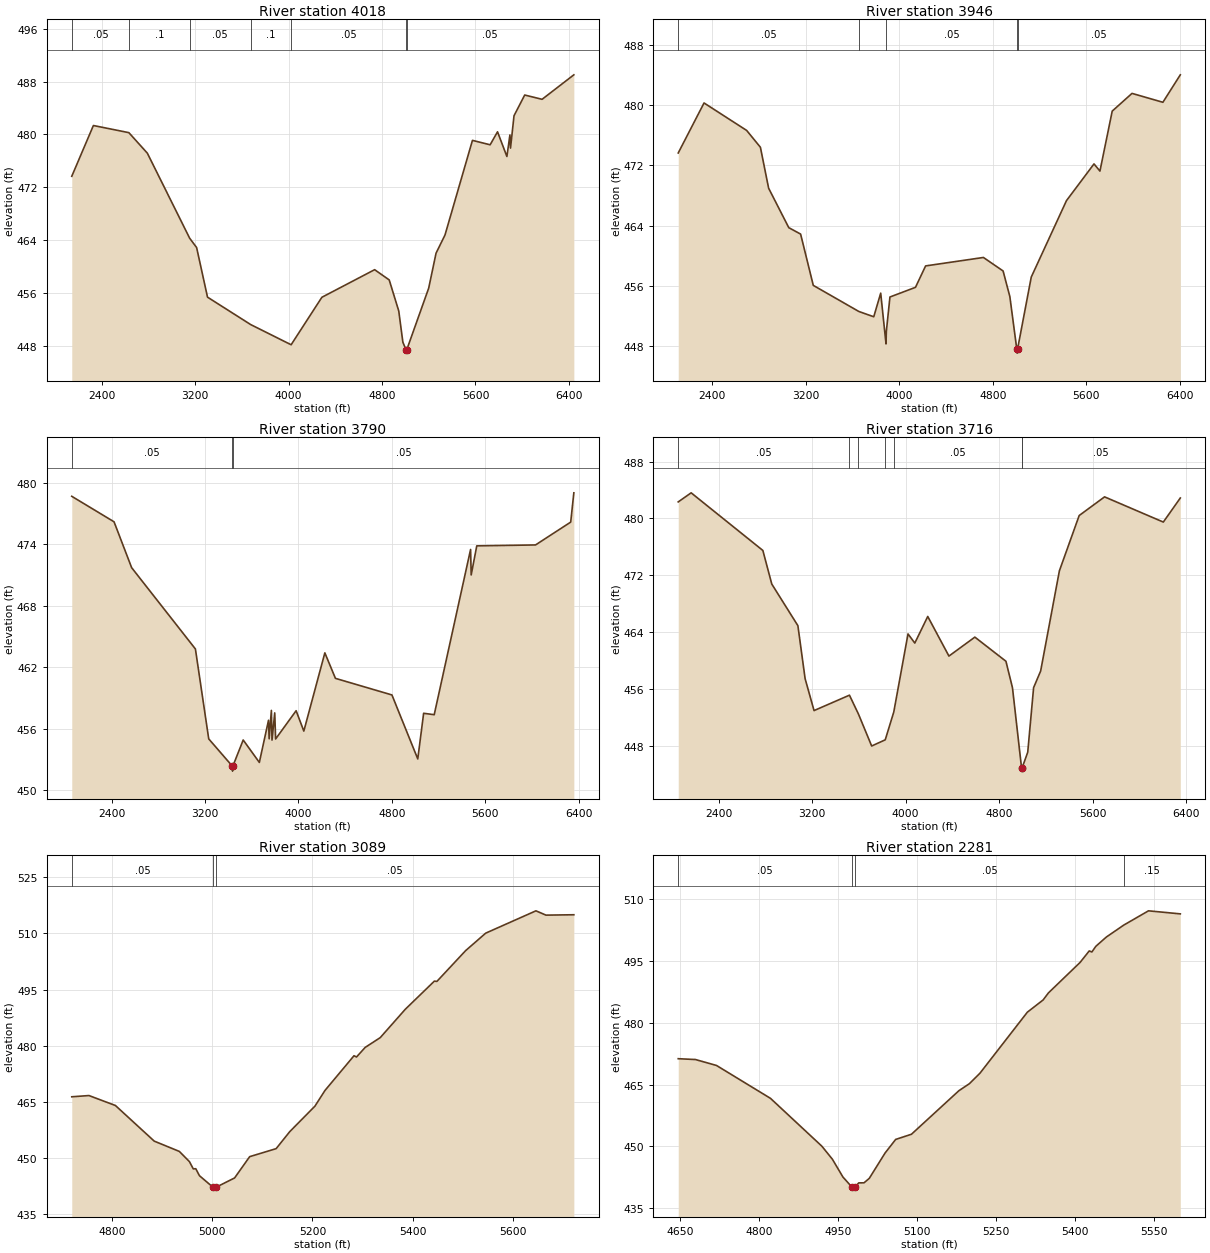
Type RM Length L Ch R = 1,4018,72,72,72
BEGIN DESCRIPTION:
UNT0169 IN SAND CR 8.3
END DESCRIPTION:
XS GIS Cut Line= 6
      3585916.55     10505603.10      3585333.21     10505655.18
      3584994.67     10505613.52      3584239.46     10505316.64
      3583182.17     10505176.02      3581708.23     10505415.60
#Sta/Elev= 30
  2143.3  473.65  2328.5  481.34  2632.2  480.26  2790.5  477.15  3152.8  464.27
  3212.5  462.85  3305.7  455.34  3675.9  451.18  4021.7  448.13  4285.0  455.32
  4736.8  459.50  4861.6  457.95  4943.3  453.25  4978.5  448.52  5005.7  447.36
  5008.4  446.86  5011.7  447.36  5199.6  456.70  5262.7  462.00  5339.2  464.75
  5574.4  479.09  5725.8  478.42  5789.1  480.39  5869.3  476.65  5895.2  479.91
  5900.3  477.92  5930.3  482.82  6021.8  485.96  6170.6  485.31  6442.6  489.02
#Mann=7,-1,0
  2143.3    0.05       0  2632.2     0.1       0  3152.8    0.05       0
  3675.9     0.1       0  4021.7    0.05       0  5005.7    0.03       0
  5011.7    0.05       0
Bank Sta=5005.7,5011.7
Exp/Cntr=0.3,0.1

Type RM Length L Ch R = 1,3946,156,156,156
BEGIN DESCRIPTION:
UNT0169 IN SAND CR 8.2
END DESCRIPTION:
XS GIS Cut Line= 6
      3585932.16     10505530.18      3585348.83     10505582.27
      3585010.29     10505540.60      3584255.08     10505243.73
      3583197.79     10505103.10      3581725.51     10505342.38
#Sta/Elev= 30
  2108.3  473.65  2329.2  480.28  2693.9  476.64  2811.6  474.41  2882.1  468.98
  3054.6  463.75  3155.9  462.90  3264.3  456.10  3654.4  452.64  3781.9  451.94
  3841.4  455.07  3886.9  448.34  3889.6  449.99  3920.5  454.56  4139.0  455.84
  4225.7  458.68  4720.6  459.80  4889.0  458.01  4946.8  454.62  5006.5  447.62
  5009.2  447.12  5012.5  447.62  5130.1  457.20  5431.4  467.33  5667.1  472.20
  5718.0  471.25  5823.1  479.20  5992.5  481.55  6256.8  480.37  6405.9  484.01
#Mann=5,-1,0
  2108.3    0.05       0  3654.4     0.1       0  3889.6    0.05       0
  5006.5    0.03       0  5012.5    0.05       0
Bank Sta=5006.5,5012.5
Exp/Cntr=0.3,0.1

Type RM Length L Ch R = 1,3790,74,74,74
BEGIN DESCRIPTION:
UNT0169 IN SAND CR 8.1
END DESCRIPTION:
XS GIS Cut Line= 6
      3585942.59     10505373.93      3585359.25     10505426.02
      3585020.71     10505384.35      3584265.50     10505087.48
      3583208.21     10504946.85      3581735.64     10505186.18
#Sta/Elev= 30
  2059.5  478.68  2421.4  476.19  2572.0  471.71  3117.9  463.77  3231.9  454.99
  3433.0  452.34  3435.8  451.84  3439.0  452.34  3527.0  454.88  3665.2  452.69
  3743.8  456.81  3749.2  455.00  3768.2  457.77  3773.6  454.87  3796.9  457.53
  3804.5  454.98  3980.1  457.74  4046.0  455.75  4226.0  463.39  4316.6  460.90
  4800.2  459.28  5021.4  453.03  5071.6  457.49  5162.1  457.35  5473.5  473.49
  5478.6  471.00  5526.5  473.84  6029.4  473.93  6330.5  476.16  6357.4  479.02
#Mann=3,-1,0
  2059.5    0.05       0  3433.0    0.03       0  3439.0    0.05       0
Bank Sta=3433,3439
Exp/Cntr=0.3,0.1

Type RM Length L Ch R = 1,3716,627,627,627
BEGIN DESCRIPTION:
UNT0169 IN SAND CR 8.0
END DESCRIPTION:
XS GIS Cut Line= 6
      3585932.15     10505301.02      3585348.83     10505353.10
      3585010.29     10505311.43      3584255.08     10505014.56
      3583197.79     10504873.93      3581725.50     10505113.21
#Sta/Elev= 30
  2053.3  482.33  2163.8  483.61  2777.7  475.49  2853.9  470.76  3077.6  464.89
  3139.3  457.43  3215.8  452.93  3518.8  455.10  3596.2  452.43  3709.0  447.94
  3825.2  448.81  3898.3  452.73  4020.1  463.73  4078.3  462.44  4189.1  466.19
  4370.4  460.61  4592.4  463.28  4858.3  459.88  4914.3  456.15  4991.7  444.90
  4994.4  444.40  4997.7  444.90  5044.9  447.06  5095.1  456.16  5155.4  458.50
  5315.9  472.62  5485.3  480.41  5702.6  483.04  6205.5  479.49  6350.9  482.88
#Mann=7,-1,0
  2053.3    0.05       0  3518.8     0.1       0  3596.2    0.05       0
  3825.2     0.1       0  3898.3    0.05       0  4991.7    0.03       0
  4997.7    0.05       0
Bank Sta=4991.7,4997.7
Exp/Cntr=0.3,0.1

Type RM Length L Ch R = 1,3089,808,808,808
BEGIN DESCRIPTION:
UNT0169 IN SAND CR 7.0
END DESCRIPTION:
XS GIS Cut Line= 2
      3583286.30     10504281.94      3582286.65     10504219.46
#Sta/Elev= 30
  4719.9  466.39  4754.2  466.72  4807.0  464.06  4884.4  454.55  4934.5  451.80
  4954.6  449.08  4962.3  447.14  4967.3  447.18  4974.6  445.32  5001.7  442.23
  5004.4  441.73  5007.7  442.23  5044.7  444.71  5074.8  450.40  5127.6  452.54
  5154.9  457.10  5205.0  463.89  5225.1  468.09  5282.9  477.35  5288.0  477.02
  5305.2  479.57  5335.3  482.19  5385.4  489.78  5443.3  497.28  5448.3  497.20
  5505.6  505.42  5545.7  510.09  5645.9  516.05  5665.9  514.90  5721.5  515.00
#Mann=3,-1,0
  4719.9    0.05       0  5001.7    0.03       0  5007.7    0.05       0
Bank Sta=5001.7,5007.7
Exp/Cntr=0.3,0.1

Type RM Length L Ch R = 1,2281,873,873,873
BEGIN DESCRIPTION:
UNT0169 IN SAND CR 5.0
END DESCRIPTION:
XS GIS Cut Line= 2
      3583374.80     10503453.81      3582421.73     10503469.43
#Sta/Elev= 30
  4647.2  471.26  4679.9  471.06  4719.9  469.62  4822.4  461.65  4919.9  450.06
  4939.9  446.90  4959.9  442.59  4976.9  440.16  4979.7  439.66  4982.9  440.16
  4989.9  441.17  4999.9  441.19  5009.9  442.27  5039.9  448.41  5060.0  451.70
  5090.0  452.96  5180.0  463.50  5200.0  465.21  5220.0  467.74  5310.0  482.53
  5340.0  485.50  5350.0  487.20  5410.0  494.57  5427.5  497.37  5432.5  497.12
  5440.0  498.49  5460.0  500.74  5493.0  503.63  5540.0  507.09  5600.4  506.35
#Mann=4,-1,0
  4647.2    0.05       0  4976.9    0.03       0  4982.9    0.05       0
  5493.0    0.15       0
Bank Sta=4976.9,4982.9
Exp/Cntr=0.3,0.1

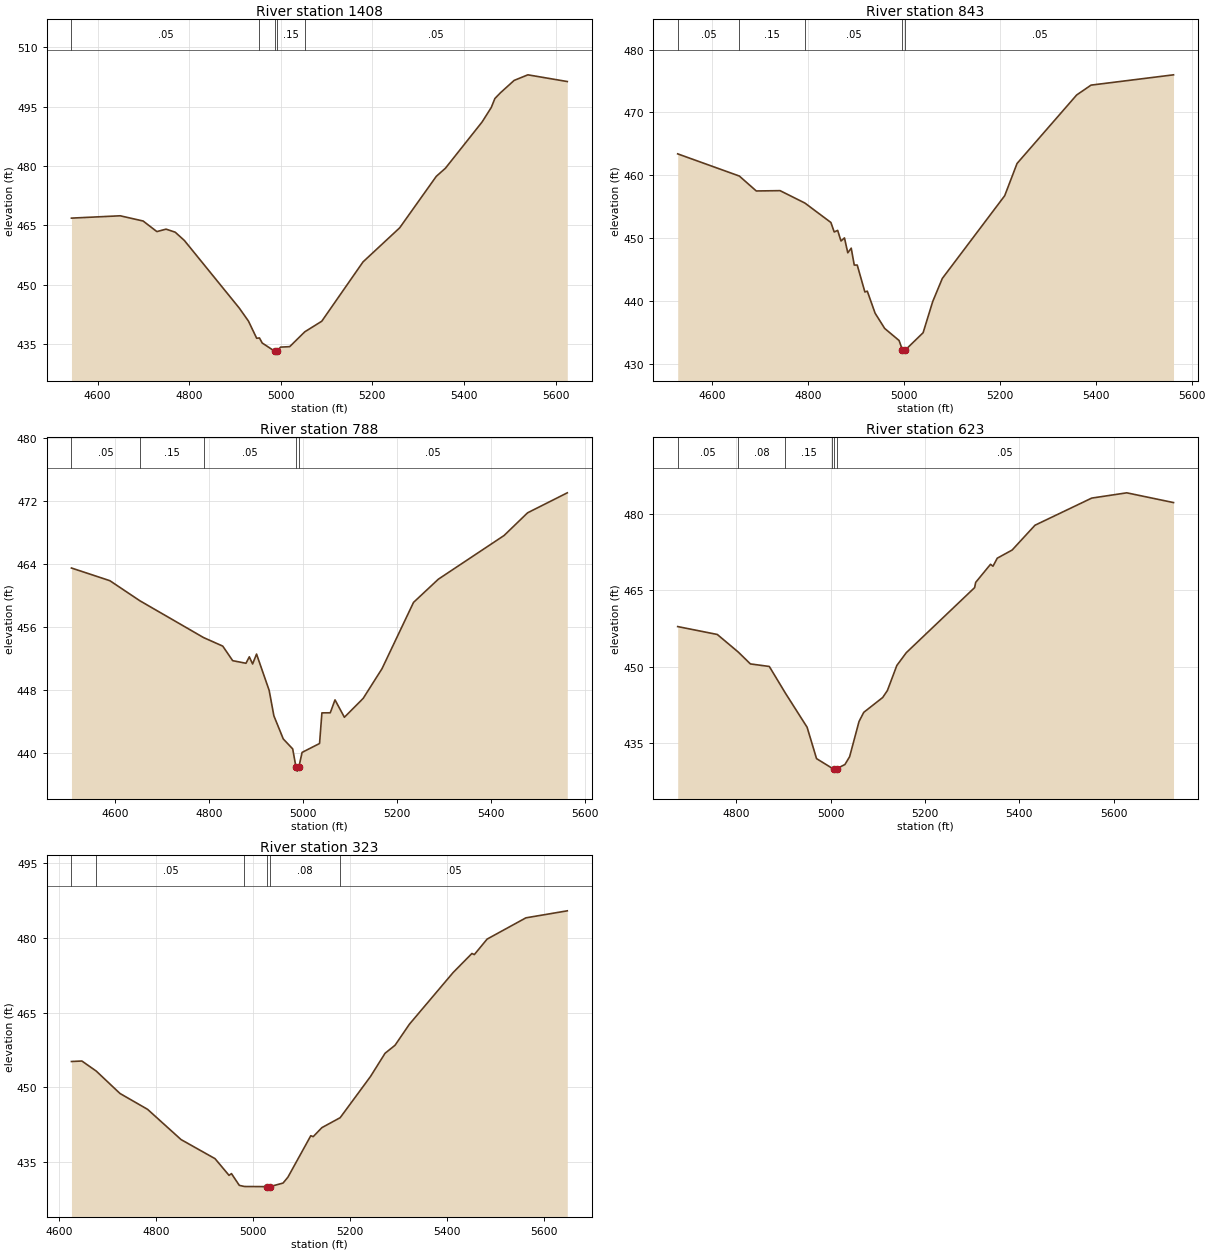
Type RM Length L Ch R = 1,1408,565,565,565
BEGIN DESCRIPTION:
UNT0169 IN SAND CR 3.0
END DESCRIPTION:
XS GIS Cut Line= 2
      3583468.55     10502578.81      3582386.15     10502599.63
#Sta/Elev= 30
  4543.1  466.81  4649.6  467.40  4699.6  466.08  4729.6  463.40  4749.6  464.02
  4769.6  463.25  4789.6  461.16  4909.6  444.03  4929.6  440.74  4947.5  436.41
  4953.6  436.48  4959.6  435.20  4986.6  433.14  4989.4  432.64  4992.6  433.14
  4999.6  434.16  5019.6  434.28  5052.6  438.04  5089.6  440.71  5179.7  455.73
  5259.7  464.35  5339.7  477.39  5359.7  479.45  5439.7  491.15  5459.7  494.81
  5467.6  497.08  5479.7  498.53  5509.7  501.67  5539.7  503.08  5625.7  501.38
#Mann=5,-1,0
  4543.1    0.05       0  4953.6    0.15       0  4986.6    0.07       0
  4992.6    0.15       0  5052.6    0.05       0
Bank Sta=4986.6,4992.6
Exp/Cntr=0.3,0.1

Type RM Length L Ch R = 1,843,55,55,55
BEGIN DESCRIPTION:
UNT0169 IN SAND CR 1.3
END DESCRIPTION:
XS GIS Cut Line= 4
      3583360.23     10502295.24      3583101.61     10502027.67
      3582765.67     10502012.04      3582440.12     10502014.65
#Sta/Elev= 30
  4528.2  463.41  4656.7  459.88  4692.1  457.50  4741.7  457.55  4793.4  455.58
  4847.7  452.48  4854.6  450.97  4861.8  451.22  4868.8  449.53  4876.0  450.02
  4882.9  447.65  4890.1  448.39  4896.4  445.70  4902.6  445.70  4918.6  441.41
  4923.6  441.54  4939.9  438.03  4959.9  435.60  4989.9  433.68  4996.9  432.17
  4999.7  431.67  5002.9  432.17  5040.0  434.92  5060.0  439.88  5080.0  443.56
  5210.2  456.75  5235.9  461.88  5360.2  472.79  5390.2  474.36  5562.2  476.00
#Mann=5,-1,0
  4528.2    0.05       0  4656.7    0.15       0  4793.4    0.05       0
  4996.9    0.03       0  5002.9    0.05       0
Bank Sta=4996.9,5002.9
Exp/Cntr=0.3,0.1

Type RM Length L Ch R = 1,788,165,165,165
BEGIN DESCRIPTION:
UNT0169 IN SAND CR 1.1
END DESCRIPTION:
XS GIS Cut Line= 4
      3583374.98     10502254.43      3583099.01     10501972.98
      3582763.07     10501957.35      3582437.55     10501959.96
#Sta/Elev= 30
  4506.4  463.52  4588.2  461.91  4652.1  459.36  4787.9  454.68  4828.6  453.60
  4849.8  451.75  4878.1  451.42  4885.2  452.24  4892.2  451.33  4900.6  452.59
  4927.5  447.97  4937.5  444.75  4957.5  441.81  4977.6  440.54  4984.6  438.22
  4987.3  437.72  4990.6  438.22  4997.6  440.10  5034.8  441.23  5039.8  445.12
  5057.6  445.13  5067.7  446.77  5087.7  444.56  5127.7  446.96  5167.8  450.73
  5234.9  459.15  5287.8  462.10  5427.8  467.65  5477.8  470.53  5562.4  473.07
#Mann=5,-1,0
  4506.4    0.05       0  4652.1    0.15       0  4787.9    0.05       0
  4984.6    0.03       0  4990.6    0.05       0
Bank Sta=4984.6,4990.6
Exp/Cntr=0.3,0.1

Type RM Length L Ch R = 1,623,300,300,300
BEGIN DESCRIPTION:
UNT0169 IN SAND CR 1.0
END DESCRIPTION:
XS GIS Cut Line= 3
      3583316.05     10501819.25      3582687.55     10501788.00
      3582288.26     10501652.59
#Sta/Elev= 30
  4676.1  457.85  4760.1  456.30  4804.9  452.82  4830.2  450.53  4870.3  450.03
  4903.7  444.91  4950.4  438.12  4970.4  431.97  5002.5  430.14  5007.5  430.02
  5010.2  429.52  5013.5  430.02  5030.5  430.81  5040.5  432.35  5060.5  439.26
  5070.5  441.04  5110.6  443.95  5120.6  445.32  5140.6  450.23  5160.6  452.73
  5305.4  465.48  5307.7  466.51  5339.1  470.05  5344.4  469.68  5353.4  471.25
  5385.0  472.85  5433.4  477.71  5553.7  483.03  5627.9  484.06  5727.0  482.15
#Mann=6,-1,0
  4676.1    0.05       0  4804.9    0.08       0  4903.7    0.15       0
  5002.5    0.05       0  5007.5    0.07       0  5013.5    0.05       0
Bank Sta=5007.5,5013.5
Exp/Cntr=0.3,0.1

Type RM Length L Ch R = 1,323,0,0,0
BEGIN DESCRIPTION:
UNT0169 IN SAND CR 1.2
END DESCRIPTION:
XS GIS Cut Line= 3
      3583288.22     10501645.60      3583204.91     10501517.17
      3582336.96     10501465.09
#Sta/Elev= 30
  4625.0  455.15  4646.5  455.25  4676.2  453.22  4725.1  448.72  4782.0  445.53
  4851.0  439.45  4921.1  435.61  4950.0  432.25  4955.0  432.60  4971.2  430.24
  4981.6  430.01  5028.3  429.98  5031.1  429.48  5034.3  429.98  5061.4  430.70
  5071.4  431.88  5118.6  440.22  5123.6  440.04  5141.5  441.85  5179.2  443.85
  5241.7  452.13  5271.8  456.81  5292.3  458.41  5321.9  462.64  5412.0  473.03
  5450.9  476.88  5455.9  476.66  5482.2  479.77  5562.3  484.05  5647.6  485.46
#Mann=6,-1,0
  4625.0    0.08       0  4676.2    0.05       0  4981.6    0.08       0
  5028.3    0.07       0  5034.3    0.08       0  5179.2    0.05       0
Bank Sta=5028.3,5034.3
Exp/Cntr=0.3,0.1

Chan Stop Cuts=-1