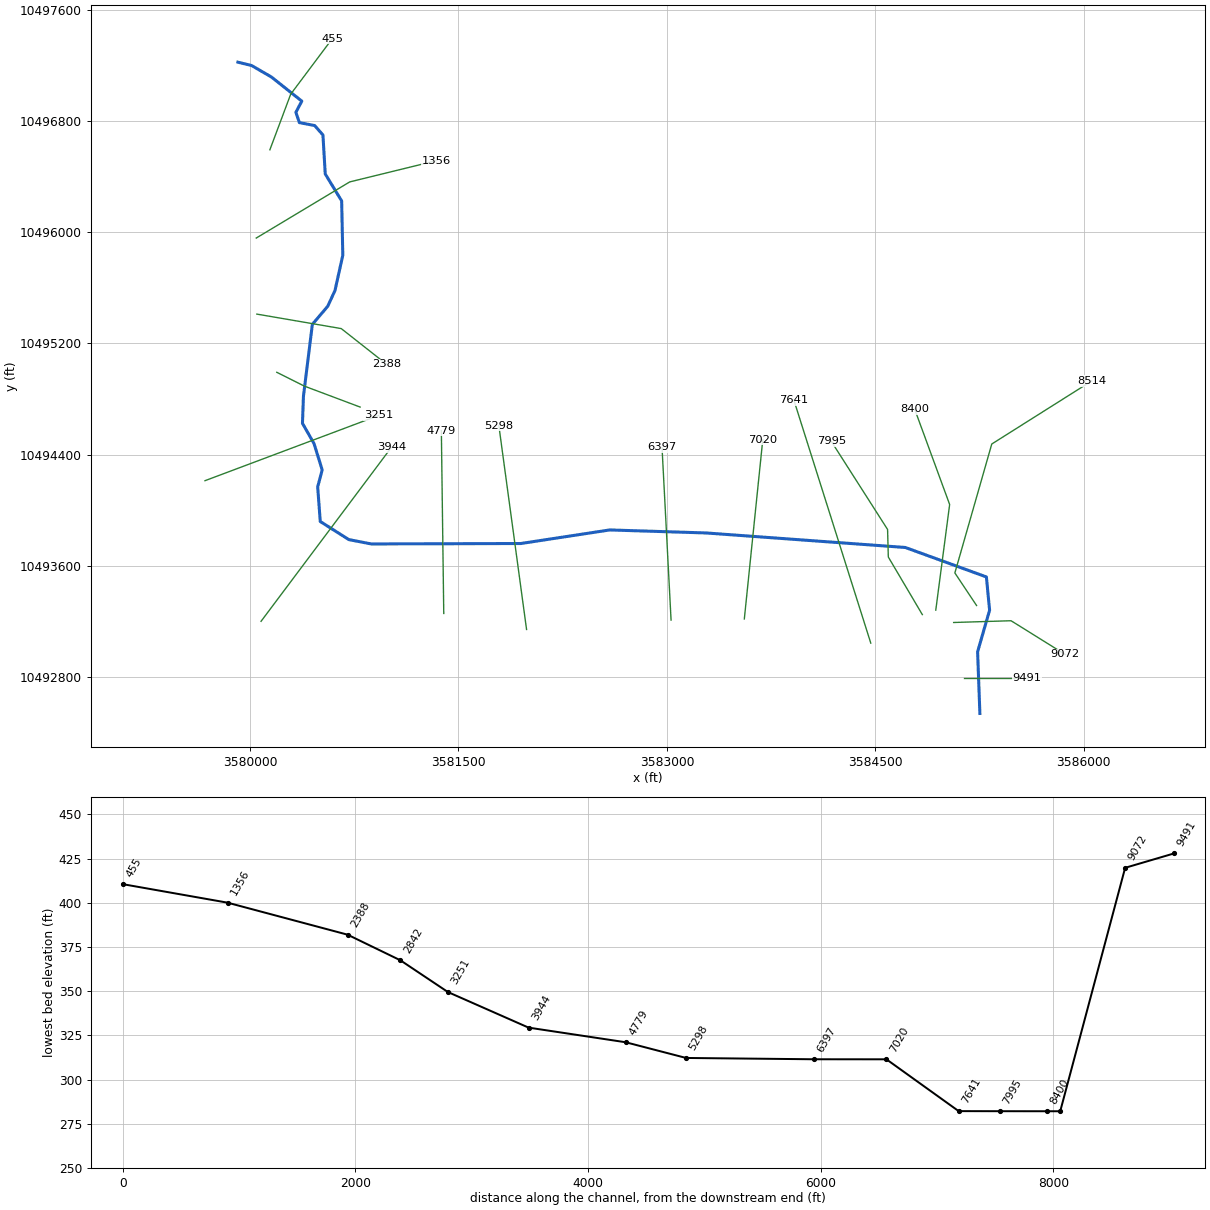
--- UNT0170 IN SAND CR.prj (project) ---

Proj Title=UNT0170 IN SAND CR Base Level Engineering
Current Plan=p01
Default Exp/Contr=0.3,0.1
English Units
Geom File=g01
Flow File=f01
Plan File=p01
BEGIN DESCRIPTION:
UNT0170 IN SAND CR
END DESCRIPTION:

--- UNT0170 IN SAND CR.p01 (plan) ---

Plan Title=Multiple Run
Short Identifier=Multiple
Geom File=g01
Flow File=f01
Subcritical Flow
K Sum by GR= 0
Std Step Tol= 0.01
Critical Tol= 0.01
Num of Std Step Trials= 20
Max Error Tol= 0.3
Flow Tol Ratio= 0.001
Split Flow NTrial= 30
Split Flow Tol= 0.02
Split Flow Ratio= 0.02
Log Output Level= 0
Friction Slope Method= 1
Unsteady Friction Slope Method= 2
Unsteady Bridges Friction Slope Method= 1
Parabolic Critical Depth
Global Vel Dist=  1 , 1 , 1
Global Log Level= 0
CheckData=True
Encroach Param= -1, 0, 0, 0
BEGIN DESCRIPTION:
Multiple Run
END DESCRIPTION:

--- UNT0170 IN SAND CR.f01 (steady flow) ---

Flow Title=Multiple
Number of Profiles=7
Profile Names=10-year,25-year,50-year,1pct_min,100-year,1pct_plu,500-year
River Rch & RM= UNT0170 IN SAND ,Reach-1,9491
    2004    2894    3664    3382    4574    6186    7110
River Rch & RM= UNT0170 IN SAND ,Reach-1,5298
    1939    2737    3411    3091    4181    5654    6270
Boundary for River Rch & Prof#=UNT0170 IN SAND ,Reach-1,1
Up Type=0
Dn Type=3
Dn Slope=0.005
Boundary for River Rch & Prof#=UNT0170 IN SAND ,Reach-1,2
Up Type=0
Dn Type=3
Dn Slope=0.005
Boundary for River Rch & Prof#=UNT0170 IN SAND ,Reach-1,3
Up Type=0
Dn Type=3
Dn Slope=0.005
Boundary for River Rch & Prof#=UNT0170 IN SAND ,Reach-1,4
Up Type=0
Dn Type=3
Dn Slope=0.005
Boundary for River Rch & Prof#=UNT0170 IN SAND ,Reach-1,5
Up Type=0
Dn Type=3
Dn Slope=0.005
Boundary for River Rch & Prof#=UNT0170 IN SAND ,Reach-1,6
Up Type=0
Dn Type=3
Dn Slope=0.005
Boundary for River Rch & Prof#=UNT0170 IN SAND ,Reach-1,7
Up Type=0
Dn Type=3
Dn Slope=0.005

--- UNT0170 IN SAND CR.g01 (geometry) ---

Geom Title=Existing Conditions

River Reach=UNT0170 IN SAND ,Reach-1
Reach XY= 30
      3585253.25     10492538.31      3585236.75     10492981.55
      3585323.22     10493280.98      3585300.02     10493520.09
      3584716.68     10493731.90      3583283.08     10493836.32
      3582588.63     10493858.02      3581948.44     10493760.36
      3580872.04     10493757.31      3580710.59     10493788.56
      3580504.86     10493918.77      3580486.35     10494167.30
      3580518.77     10494289.78      3580460.16     10494478.68
      3580376.83     10494624.51      3580383.77     10494818.96
      3580448.01     10495336.32      3580558.68     10495466.53
      3580610.77     10495579.37      3580667.19     10495833.28
      3580658.90     10496224.17      3580540.79     10496417.90
      3580524.17     10496698.24      3580464.58     10496766.15
      3580354.58     10496787.23      3580329.35     10496861.57
      3580372.11     10496941.64      3580153.21     10497115.16
      3580010.56     10497197.90      3579912.11     10497221.64

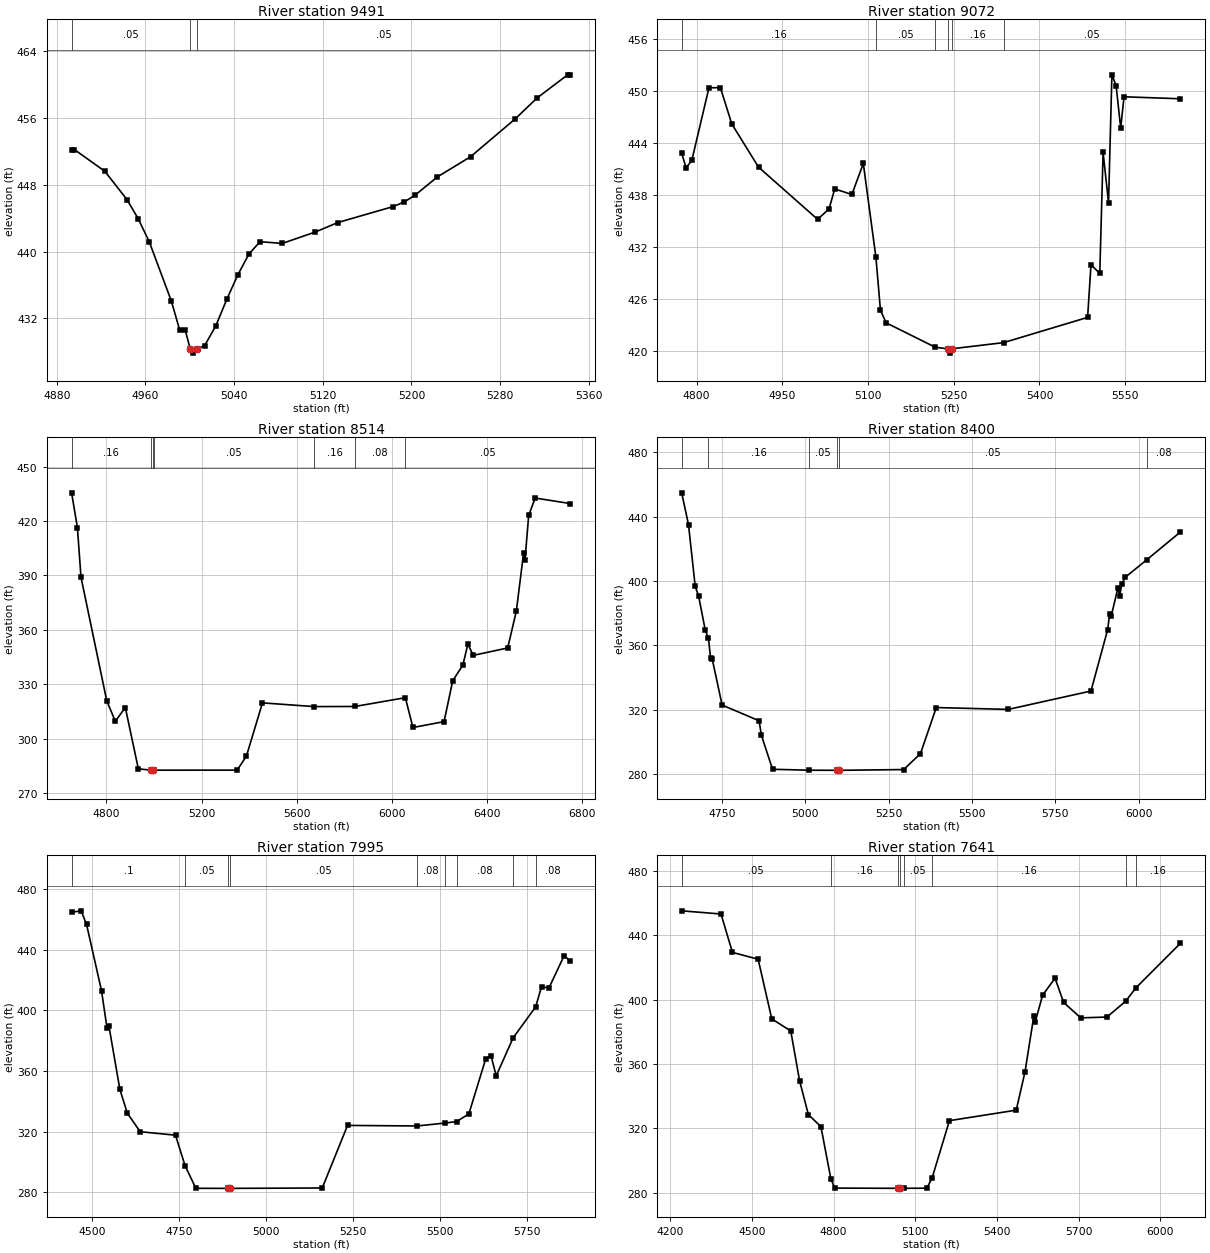
Type RM Length L Ch R = 1,9491,419,419,419
BEGIN DESCRIPTION:
UNT0170 IN SAND CR 21.0
END DESCRIPTION:
XS GIS Cut Line= 3
      3585142.09     10492791.64      3585242.11     10492791.64
      3585592.09     10492791.64
#Sta/Elev= 30
  4893.4  452.19  4895.9  452.19  4923.4  449.59  4943.4  446.20  4953.4  443.94
  4963.4  441.19  4983.4  434.08  4990.9  430.62  4995.9  430.62  5000.4  428.36
  5003.2  427.86  5006.4  428.36  5013.4  428.76  5023.4  431.09  5033.4  434.29
  5043.4  437.22  5053.4  439.71  5063.4  441.18  5083.4  440.97  5113.4  442.34
  5133.4  443.46  5183.4  445.37  5193.4  445.92  5203.4  446.75  5223.4  448.92
  5253.4  451.34  5293.4  455.83  5313.4  458.36  5340.9  461.12  5343.4  461.12
#Mann=3,-1,0
  4893.4    0.05       0  5000.4    0.03       0  5006.4    0.05       0
Bank Sta=5000.4,5006.4
Exp/Cntr=0.3,0.1

Type RM Length L Ch R = 1,9072,558,558,558
BEGIN DESCRIPTION:
UNT0170 IN SAND CR 20.0
END DESCRIPTION:
XS GIS Cut Line= 3
      3585064.43     10493192.48      3585477.70     10493205.11
      3585867.70     10492962.44
#Sta/Elev= 30
  4773.9  442.79  4781.6  441.11  4791.6  441.95  4821.6  450.32  4841.6  450.35
  4861.6  446.16  4908.4  441.18  5011.7  435.17  5031.7  436.36  5041.7  438.67
  5071.7  438.03  5091.7  441.61  5113.8  430.78  5121.7  424.70  5131.7  423.24
  5217.9  420.42  5240.4  420.25  5243.2  419.75  5246.4  420.25  5337.2  420.96
  5484.2  423.87  5490.1  429.93  5505.5  428.94  5511.3  442.87  5520.8  437.09
  5526.7  451.82  5534.1  450.56  5542.1  445.69  5547.9  449.29  5646.7  449.06
#Mann=6,-1,0
  4773.9    0.16       0  5113.8    0.05       0  5217.9    0.16       0
  5240.4    0.07       0  5246.4    0.16       0  5337.2    0.05       0
Bank Sta=5240.4,5246.4
Exp/Cntr=0.3,0.1

Type RM Length L Ch R = 1,8514,114,114,114
BEGIN DESCRIPTION:
UNT0170 IN SAND CR 19.0
END DESCRIPTION:
XS GIS Cut Line= 4
      3585229.41     10493314.52      3585073.18     10493548.86
      3585338.81     10494475.95      3586057.31     10494928.91
#Sta/Elev= 30
  4653.8  435.53  4678.2  416.34  4693.2  389.02  4801.4  320.87  4837.4  309.55
  4879.5  317.14  4934.1  283.34  4987.8  282.56  4990.5  282.06  4993.8  282.56
  5002.0  282.58  5349.1  282.60  5388.1  290.31  5455.6  319.70  5672.2  317.65
  5843.8  317.71  6055.8  322.56  6087.8  306.12  6218.5  309.36  6254.9  331.94
  6297.3  340.48  6318.5  352.14  6341.1  345.90  6485.7  349.97  6522.1  370.31
  6552.7  402.52  6558.6  398.64  6573.9  423.06  6601.2  432.65  6749.2  429.61
#Mann=7,-1,0
  4653.8    0.16       0  4987.8    0.07       0  4993.8    0.16       0
  5002.0    0.05       0  5672.2    0.16       0  5843.8    0.08       0
  6055.8    0.05       0
Bank Sta=4987.8,4993.8
Exp/Cntr=0.3,0.1

Type RM Length L Ch R = 1,8400,405,405,405
BEGIN DESCRIPTION:
UNT0170 IN SAND CR 18.0
END DESCRIPTION:
XS GIS Cut Line= 3
      3584935.71     10493281.36      3585035.54     10494040.91
      3584783.80     10494726.69
#Sta/Elev= 30
  4628.9  454.69  4649.4  434.93  4669.5  396.62  4679.6  390.73  4699.8  369.37
  4709.3  364.47  4715.6  352.13  4720.7  351.43  4750.2  323.05  4861.2  313.29
  4868.0  304.35  4901.5  283.21  5010.5  282.63  5096.1  282.56  5098.9  282.06
  5102.1  282.56  5294.9  283.03  5345.3  292.89  5392.8  321.49  5608.8  320.35
  5856.9  331.75  5907.1  369.87  5912.6  379.22  5917.9  378.43  5937.7  395.57
  5943.1  390.99  5949.7  398.31  5960.3  402.40  6024.3  413.14  6125.5  430.42
#Mann=6,-1,0
  4628.9    0.05       0  4709.3    0.16       0  5010.5    0.05       0
  5096.1    0.07       0  5102.1    0.05       0  6024.3    0.08       0
Bank Sta=5096.1,5102.1
Exp/Cntr=0.3,0.1

Type RM Length L Ch R = 1,7995,354,354,354
BEGIN DESCRIPTION:
UNT0170 IN SAND CR 17.0
END DESCRIPTION:
XS GIS Cut Line= 4
      3584838.82     10493249.36      3584594.02     10493663.45
      3584588.81     10493861.36      3584182.62     10494496.69
#Sta/Elev= 30
  4441.4  464.86  4468.8  465.79  4484.4  456.78  4527.3  413.11  4542.9  388.74
  4548.7  389.61  4580.0  348.02  4601.4  332.24  4638.5  319.99  4739.9  317.69
  4767.2  297.67  4798.4  282.62  4891.0  282.59  4893.8  282.09  4897.0  282.59
  5161.5  282.84  5234.2  324.14  5433.8  323.78  5514.3  325.70  5547.4  326.68
  5582.7  331.71  5631.1  368.02  5646.2  370.27  5661.4  356.89  5709.8  381.89
  5774.6  402.39  5791.6  415.72  5812.8  414.81  5856.6  436.25  5874.5  432.46
#Mann=9,-1,0
  4441.4     0.1       0  4767.2    0.05       0  4891.0    0.04       0
  4897.0    0.05       0  5433.8    0.08       0  5514.3    0.05       0
  5547.4    0.08       0  5709.8    0.05       0  5774.6    0.08       0
Bank Sta=4891,4897
Exp/Cntr=0.3,0.1

Type RM Length L Ch R = 1,7641,621,621,621
BEGIN DESCRIPTION:
UNT0170 IN SAND CR 16.0
END DESCRIPTION:
XS GIS Cut Line= 2
      3584467.95     10493043.89      3583914.54     10494790.93
#Sta/Elev= 30
  4241.8  455.27  4386.3  453.30  4428.3  429.41  4522.7  425.16  4572.8  388.06
  4642.6  380.51  4674.9  349.59  4707.2  328.54  4753.4  320.97  4789.9  288.56
  4804.1  282.78  5037.6  282.63  5040.4  282.13  5043.6  282.63  5059.3  282.65
  5142.7  282.72  5161.9  289.09  5225.5  324.73  5470.9  331.26  5503.2  355.08
  5535.5  389.73  5540.7  386.09  5567.8  402.77  5613.6  413.37  5645.1  398.28
  5708.0  388.68  5804.3  389.18  5872.6  398.99  5911.2  407.43  6074.4  435.09
#Mann=8,-1,0
  4241.8    0.05       0  4789.9    0.16       0  5037.6    0.07       0
  5043.6    0.16       0  5059.3    0.05       0  5161.9    0.16       0
  5872.6    0.05       0  5911.2    0.16       0
Bank Sta=5037.6,5043.6
Exp/Cntr=0.3,0.1

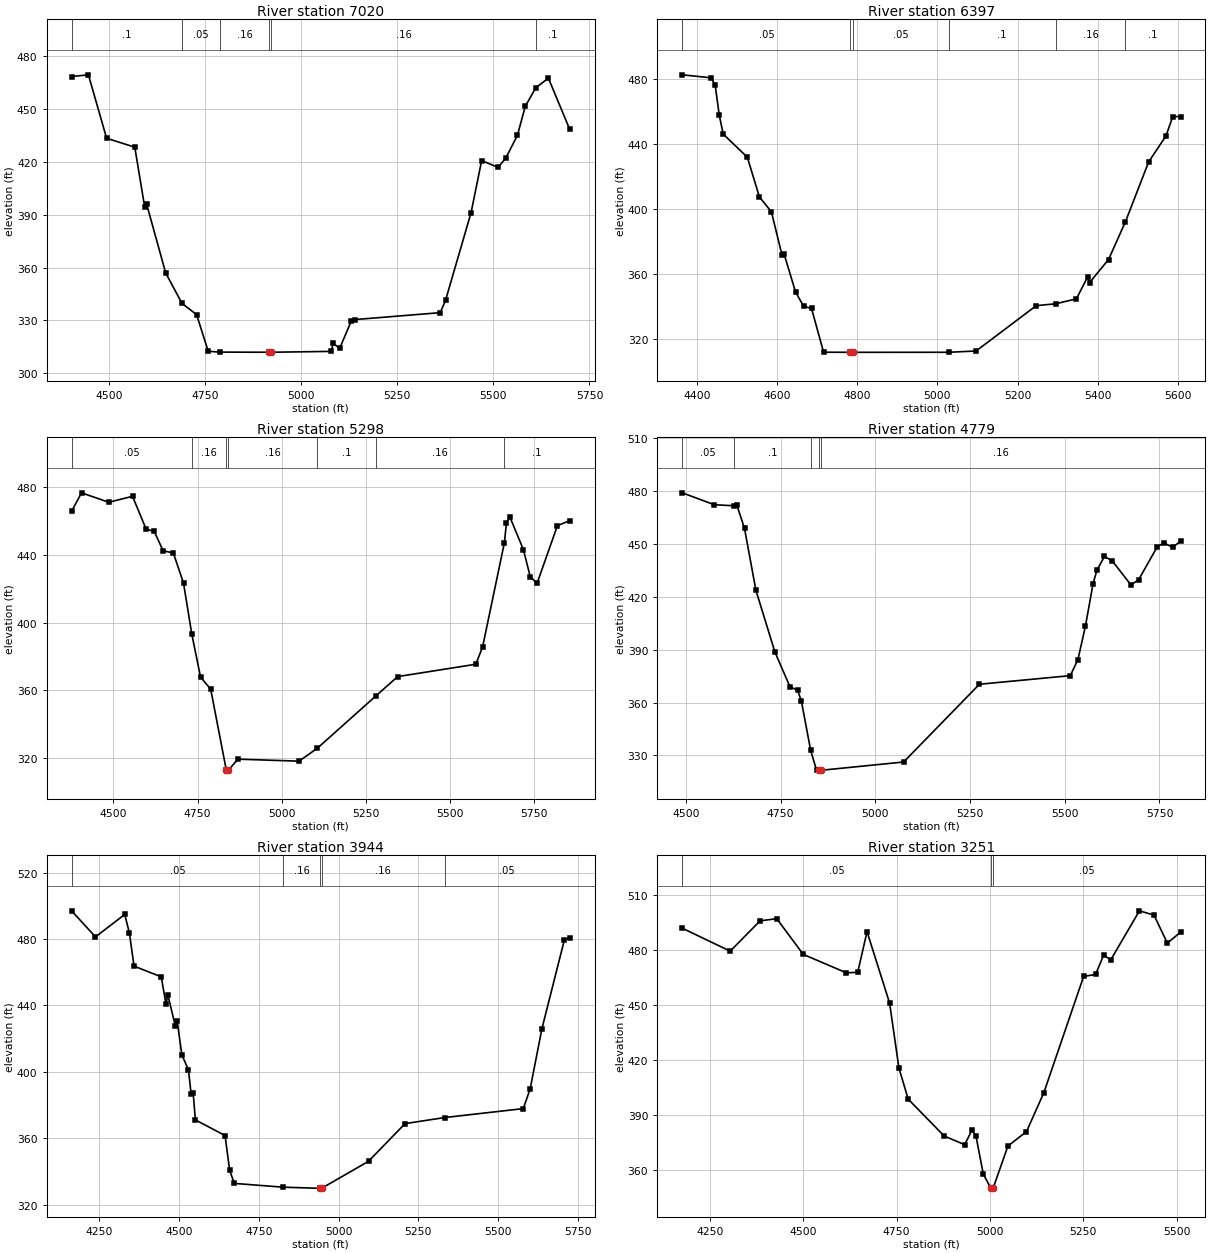
Type RM Length L Ch R = 1,7020,623,623,623
BEGIN DESCRIPTION:
UNT0170 IN SAND CR 15.0
END DESCRIPTION:
XS GIS Cut Line= 2
      3583557.56     10493218.11      3583690.34     10494506.89
#Sta/Elev= 30
  4403.1  468.43  4446.9  469.40  4494.2  433.40  4567.5  428.33  4593.2  394.38
  4598.3  396.02  4647.9  356.90  4690.4  339.65  4728.3  333.28  4758.5  312.47
  4789.5  312.02  4916.3  311.94  4919.1  311.44  4922.3  311.94  5078.4  312.43
  5083.5  316.96  5100.3  314.15  5130.5  329.61  5140.5  330.49  5361.7  334.41
  5375.6  341.35  5442.1  391.23  5469.6  420.75  5512.5  416.86  5532.6  422.29
  5562.7  435.08  5582.8  451.43  5610.4  462.09  5643.2  467.51  5698.7  438.40
#Mann=6,-1,0
  4403.1     0.1       0  4690.4    0.05       0  4789.5    0.16       0
  4916.3    0.07       0  4922.3    0.16       0  5610.4     0.1       0
Bank Sta=4916.3,4922.3
Exp/Cntr=0.3,0.1

Type RM Length L Ch R = 1,6397,1099,1099,1099
BEGIN DESCRIPTION:
UNT0170 IN SAND CR 14.0
END DESCRIPTION:
XS GIS Cut Line= 2
      3583030.22     10493209.64      3582965.11     10494451.03
#Sta/Elev= 30
  4363.5  482.67  4435.6  480.83  4445.6  476.16  4455.6  457.85  4465.6  446.19
  4525.7  431.98  4555.8  407.58  4585.8  398.38  4612.4  371.59  4617.4  372.48
  4645.9  349.17  4665.9  340.36  4685.9  338.92  4716.0  312.03  4783.1  311.96
  4785.8  311.46  4789.1  311.96  5028.0  311.98  5096.5  312.77  5246.7  340.68
  5294.9  341.80  5346.9  344.86  5374.7  358.33  5379.7  354.86  5427.0  369.03
  5469.2  392.27  5527.1  429.09  5570.3  445.08  5587.2  456.93  5606.6  457.00
#Mann=6,-1,0
  4363.5    0.05       0  4783.1    0.04       0  4789.1    0.05       0
  5028.0     0.1       0  5294.9    0.16       0  5469.2     0.1       0
Bank Sta=4783.1,4789.1
Exp/Cntr=0.3,0.1

Type RM Length L Ch R = 1,5298,519,519,519
BEGIN DESCRIPTION:
UNT0170 IN SAND CR 12.0
END DESCRIPTION:
XS GIS Cut Line= 2
      3581990.00     10493142.27      3581790.52     10494607.96
#Sta/Elev= 30
  4375.7  465.84  4405.3  476.75  4486.1  471.17  4556.7  474.69  4597.1  455.25
  4621.0  454.01  4647.6  442.44  4677.8  441.21  4708.1  423.35  4732.6  393.24
  4758.6  367.82  4788.8  360.63  4835.2  312.70  4837.9  312.20  4841.2  312.70
  4869.6  319.28  5051.2  318.09  5105.7  325.78  5280.0  356.80  5343.9  368.09
  5576.0  375.39  5596.2  385.69  5660.8  447.25  5666.9  458.93  5677.0  462.55
  5717.3  443.12  5737.5  427.24  5757.7  423.17  5818.3  457.35  5854.9  460.29
#Mann=7,-1,0
  4375.7    0.05       0  4732.6    0.16       0  4835.2    0.07       0
  4841.2    0.16       0  5105.7     0.1       0  5280.0    0.16       0
  5660.8     0.1       0
Bank Sta=4835.2,4841.2
Exp/Cntr=0.3,0.1

Type RM Length L Ch R = 1,4779,835,835,835
BEGIN DESCRIPTION:
UNT0170 IN SAND CR 10.0
END DESCRIPTION:
XS GIS Cut Line= 2
      3581393.93     10493257.41      3581376.57     10494572.50
#Sta/Elev= 30
  4490.4  479.06  4574.6  472.32  4626.5  471.71  4634.6  471.94  4654.6  458.82
  4684.6  423.78  4734.7  388.76  4774.7  368.90  4794.7  367.05  4804.7  360.82
  4829.2  332.89  4844.7  321.64  4851.7  321.58  4854.4  321.08  4857.7  321.58
  5074.7  326.26  5274.7  370.40  5514.7  375.28  5534.7  384.35  5554.7  403.47
  5574.7  427.46  5584.7  434.97  5604.7  442.92  5624.7  440.62  5674.7  426.79
  5694.7  429.63  5744.7  448.59  5762.4  450.57  5784.7  448.12  5805.6  451.55
#Mann=5,-1,0
  4490.4    0.05       0  4626.5     0.1       0  4829.2    0.16       0
  4851.7    0.07       0  4857.7    0.16       0
Bank Sta=4851.7,4857.7
Exp/Cntr=0.3,0.1

Type RM Length L Ch R = 1,3944,693,693,693
BEGIN DESCRIPTION:
UNT0170 IN SAND CR 9.0
END DESCRIPTION:
XS GIS Cut Line= 2
      3580078.82     10493200.98      3581016.32     10494450.98
#Sta/Elev= 30
  4162.5  496.97  4237.5  481.28  4329.2  494.78  4343.8  483.71  4358.4  463.65
  4443.8  457.22  4458.4  440.99  4464.6  446.21  4487.5  427.89  4493.8  430.50
  4508.4  410.22  4529.2  401.17  4537.5  386.41  4543.8  387.49  4550.8  371.06
  4643.8  361.65  4658.4  340.62  4672.9  332.81  4826.3  330.52  4940.8  329.86
  4943.5  329.36  4946.8  329.86  5093.8  346.12  5208.4  368.81  5332.3  372.46
  5579.2  377.85  5600.8  389.69  5637.5  425.82  5708.4  479.66  5725.0  480.71
#Mann=5,-1,0
  4162.5    0.05       0  4826.3    0.16       0  4940.8    0.07       0
  4946.8    0.16       0  5332.3    0.05       0
Bank Sta=4940.8,4946.8
Exp/Cntr=0.3,0.1

Type RM Length L Ch R = 1,3251,409,409,409
BEGIN DESCRIPTION:
UNT0170 IN SAND CR 7.0
END DESCRIPTION:
XS GIS Cut Line= 2
      3579675.18     10494212.27      3580925.18     10494681.02
#Sta/Elev= 30
  4175.7  491.82  4304.0  479.32  4384.1  495.85  4428.7  497.04  4499.8  477.54
  4615.5  467.49  4645.7  467.79  4670.7  489.96  4731.2  450.92  4756.1  415.56
  4781.0  398.55  4877.3  378.46  4932.3  373.71  4951.9  381.72  4962.7  378.35
  4982.2  357.67  5002.5  349.97  5005.2  349.47  5008.5  349.97  5048.2  372.98
  5097.9  380.84  5144.3  401.99  5251.1  465.53  5283.1  466.59  5304.5  477.10
  5323.9  474.61  5400.6  501.32  5439.6  499.00  5475.4  483.73  5510.7  489.63
#Mann=3,-1,0
  4175.7    0.05       0  5002.5    0.03       0  5008.5    0.05       0
Bank Sta=5002.5,5008.5
Exp/Cntr=0.3,0.1

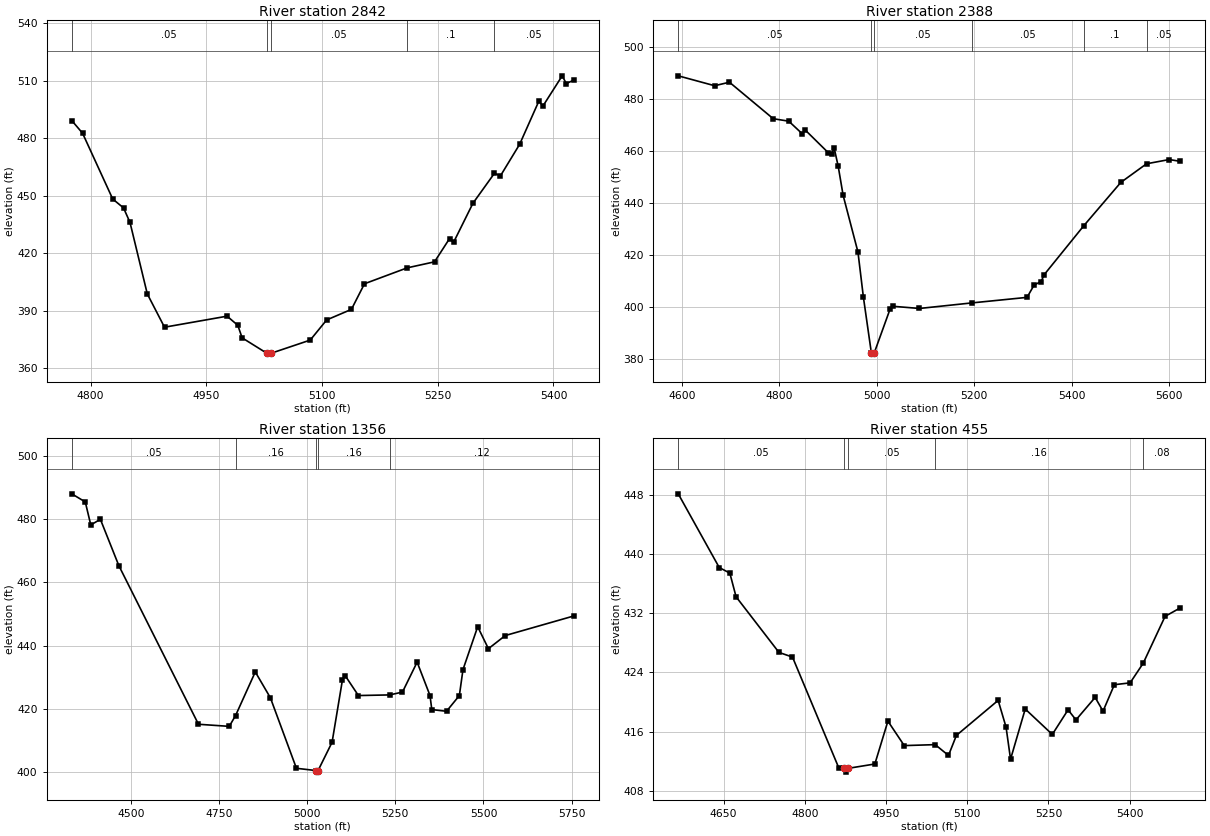
Type RM Length L Ch R = 1,2842,454,454,454
BEGIN DESCRIPTION:
UNT0170 IN SAND CR 6.0
END DESCRIPTION:
XS GIS Cut Line= 3
      3580192.08     10494991.65      3580392.11     10494891.64
      3580792.07     10494741.65
#Sta/Elev= 30
  4775.6  489.18  4789.6  482.57  4828.7  448.27  4842.7  443.65  4851.1  436.05
  4873.5  398.82  4895.8  381.47  4976.9  387.22  4990.8  382.48  4996.4  375.93
  5028.3  367.94  5031.0  367.44  5034.3  367.94  5084.7  374.76  5106.0  385.26
  5138.1  390.77  5155.0  404.11  5210.3  412.40  5245.8  415.54  5265.3  427.67
  5270.7  425.87  5295.6  446.07  5323.5  461.71  5331.2  460.32  5356.1  476.77
  5381.0  499.26  5386.4  496.79  5411.3  512.49  5416.6  508.46  5426.4  510.26
#Mann=5,-1,0
  4775.6    0.05       0  5028.3    0.03       0  5034.3    0.05       0
  5210.3     0.1       0  5323.5    0.05       0
Bank Sta=5028.3,5034.3
Exp/Cntr=0.3,0.1

Type RM Length L Ch R = 1,2388,1032,1032,1032
BEGIN DESCRIPTION:
UNT0170 IN SAND CR 5.0
END DESCRIPTION:
XS GIS Cut Line= 3
      3580048.48     10495410.18      3580656.08     10495306.02
      3580981.57     10495049.97
#Sta/Elev= 30
  4592.6  489.07  4667.3  485.26  4697.7  486.61  4787.6  472.56  4819.5  471.61
  4847.6  466.68  4852.7  468.31  4900.7  459.45  4907.6  459.11  4912.7  461.25
  4921.0  454.21  4931.1  443.04  4961.5  421.24  4972.7  403.82  4989.0  382.43
  4991.7  381.93  4995.0  382.43  5027.7  399.41  5032.7  400.36  5087.7  399.51
  5195.9  401.66  5308.6  403.78  5323.1  408.53  5337.5  409.89  5344.0  412.57
  5425.3  431.41  5501.1  448.04  5553.9  455.21  5600.5  456.84  5623.2  456.14
#Mann=6,-1,0
  4592.6    0.05       0  4989.0    0.07       0  4995.0    0.05       0
  5195.9    0.05       0  5425.3     0.1       0  5553.9    0.05       0
Bank Sta=4989,4995
Exp/Cntr=0.3,0.1

Type RM Length L Ch R = 1,1356,901,901,901
BEGIN DESCRIPTION:
UNT0170 IN SAND CR 3.0
END DESCRIPTION:
XS GIS Cut Line= 3
      3580044.07     10495957.05      3580716.85     10496360.71
      3581337.35     10496512.58
#Sta/Elev= 30
  4332.9  487.91  4371.2  485.35  4386.8  478.08  4414.0  479.87  4466.4  465.22
  4692.1  415.15  4779.4  414.49  4797.3  417.91  4853.2  431.68  4896.0  423.51
  4969.8  401.25  5025.2  400.54  5027.9  400.04  5031.2  400.54  5070.9  409.48
  5100.3  429.19  5107.8  430.54  5145.5  424.22  5234.1  424.42  5270.4  425.31
  5312.0  434.77  5348.5  424.23  5353.6  419.79  5395.3  419.25  5431.7  424.21
  5442.0  432.41  5483.7  445.95  5514.1  439.01  5561.8  443.16  5756.3  449.35
#Mann=5,-1,0
  4332.9    0.05       0  4797.3    0.16       0  5025.2    0.07       0
  5031.2    0.16       0  5234.1    0.12       0
Bank Sta=5025.2,5031.2
Exp/Cntr=0.3,0.1

Type RM Length L Ch R = 1,455,0,0,0
BEGIN DESCRIPTION:
UNT0170 IN SAND CR 1.0
END DESCRIPTION:
XS GIS Cut Line= 3
      3580142.10     10496591.61      3580292.11     10496991.64
      3580592.09     10497391.62
#Sta/Elev= 30
  4566.4  448.17  4642.1  438.20  4661.7  437.44  4673.2  434.24  4752.4  426.71
  4777.4  426.08  4862.8  411.10  4873.1  411.01  4875.9  410.51  4879.1  411.01
  4929.5  411.61  4953.6  417.41  4983.8  414.10  5040.9  414.23  5065.5  412.77
  5080.1  415.48  5157.2  420.22  5171.8  416.60  5180.1  412.26  5207.2  419.05
  5257.2  415.61  5286.3  418.94  5300.9  417.58  5336.3  420.62  5350.9  418.76
  5371.8  422.34  5400.9  422.59  5425.1  425.25  5465.5  431.59  5493.6  432.74
#Mann=5,-1,0
  4566.4    0.05       0  4873.1    0.03       0  4879.1    0.05       0
  5040.9    0.16       0  5425.1    0.08       0
Bank Sta=4873.1,4879.1
Exp/Cntr=0.3,0.1

Chan Stop Cuts=-1