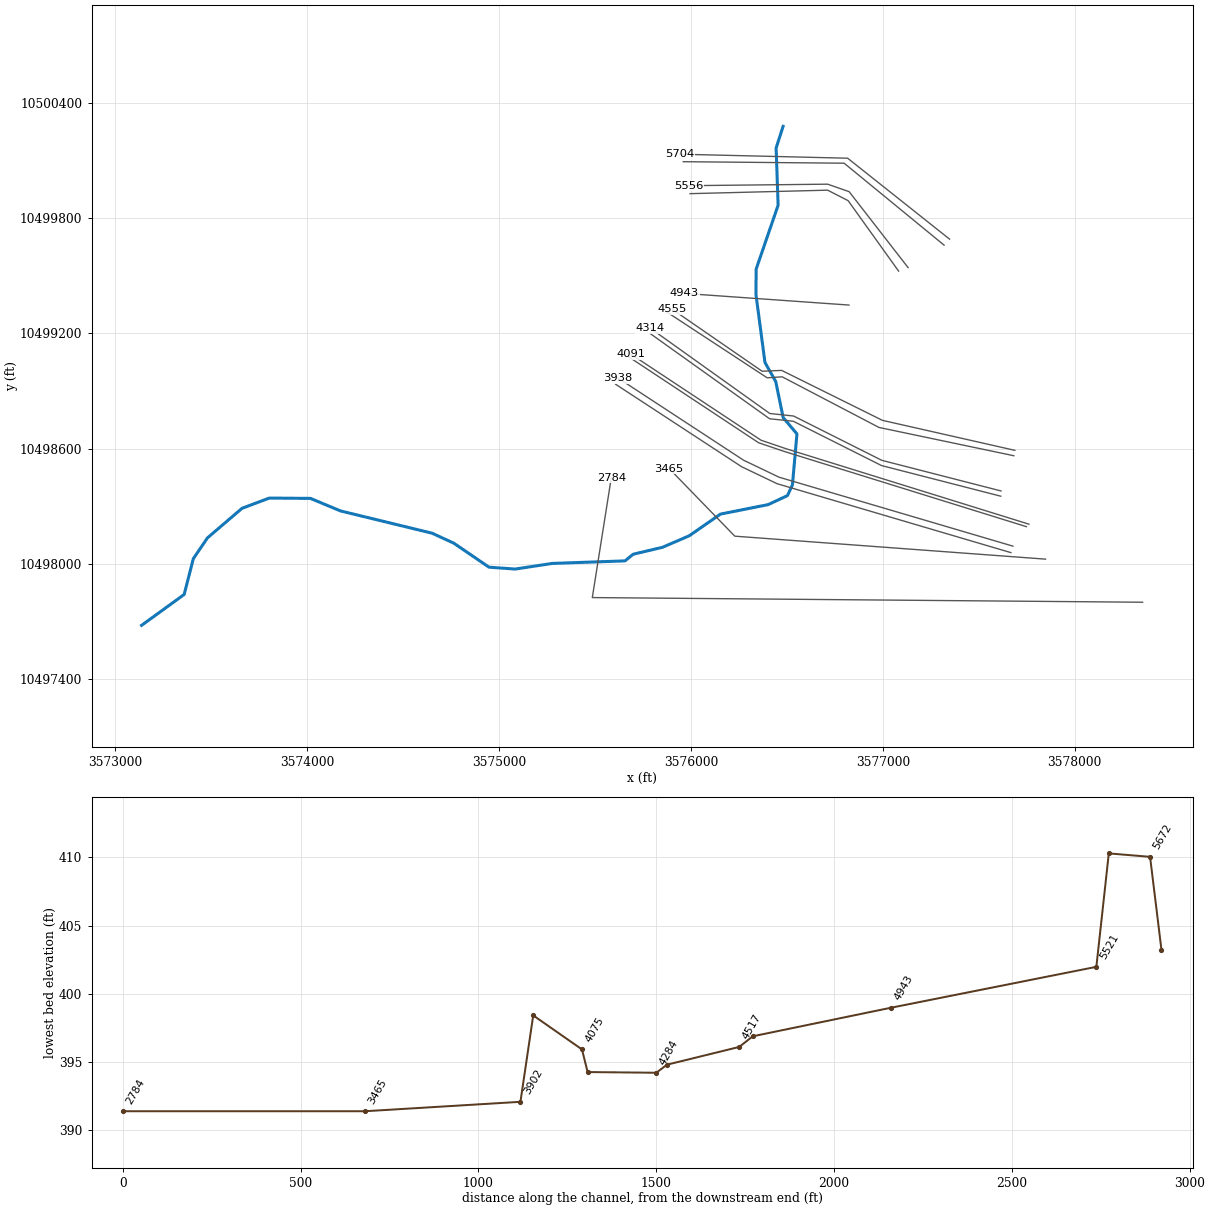
--- UNT0171 IN SAND CR.prj (project) ---

Proj Title=UNT0171 IN SAND CR Base Level Engineering
Current Plan=p01
Default Exp/Contr=0.3,0.1
English Units
Geom File=g01
Flow File=f01
Plan File=p01
BEGIN DESCRIPTION:
UNT0171 IN SAND CR
END DESCRIPTION:

--- UNT0171 IN SAND CR.p01 (plan) ---

Plan Title=Multiple Run
Short Identifier=Multiple
Geom File=g01
Flow File=f01
Subcritical Flow
K Sum by GR= 0
Std Step Tol= 0.01
Critical Tol= 0.01
Num of Std Step Trials= 20
Max Error Tol= 0.3
Flow Tol Ratio= 0.001
Split Flow NTrial= 30
Split Flow Tol= 0.02
Split Flow Ratio= 0.02
Log Output Level= 0
Friction Slope Method= 1
Unsteady Friction Slope Method= 2
Unsteady Bridges Friction Slope Method= 1
Parabolic Critical Depth
Global Vel Dist=  1 , 1 , 1
Global Log Level= 0
CheckData=True
Encroach Param= -1, 0, 0, 0
BEGIN DESCRIPTION:
Multiple Run
END DESCRIPTION:

--- UNT0171 IN SAND CR.f01 (steady flow) ---

Flow Title=Multiple
Number of Profiles=7
Profile Names=10-year,25-year,50-year,1pct_min,100-year,1pct_plu,500-year
River Rch & RM= UNT0171 IN SAND ,Reach-1,5704
    1410    1970    2438    2198    2973    4021    4412
Boundary for River Rch & Prof#=UNT0171 IN SAND ,Reach-1,1
Up Type=0
Dn Type=3
Dn Slope=0.005
Boundary for River Rch & Prof#=UNT0171 IN SAND ,Reach-1,2
Up Type=0
Dn Type=3
Dn Slope=0.005
Boundary for River Rch & Prof#=UNT0171 IN SAND ,Reach-1,3
Up Type=0
Dn Type=3
Dn Slope=0.005
Boundary for River Rch & Prof#=UNT0171 IN SAND ,Reach-1,4
Up Type=0
Dn Type=3
Dn Slope=0.005
Boundary for River Rch & Prof#=UNT0171 IN SAND ,Reach-1,5
Up Type=0
Dn Type=3
Dn Slope=0.005
Boundary for River Rch & Prof#=UNT0171 IN SAND ,Reach-1,6
Up Type=0
Dn Type=3
Dn Slope=0.005
Boundary for River Rch & Prof#=UNT0171 IN SAND ,Reach-1,7
Up Type=0
Dn Type=3
Dn Slope=0.005

--- UNT0171 IN SAND CR.g01 (geometry) ---

Geom Title=Existing Conditions

River Reach=UNT0171 IN SAND ,Reach-1
Reach XY= 30
      3576480.10     10500279.64      3576443.66     10500167.00
      3576454.08     10499868.39      3576339.49     10499535.05
      3576338.62     10499402.67      3576385.50     10499048.51
      3576441.49     10498949.55      3576480.55     10498760.75
      3576552.17     10498676.11      3576528.73     10498410.49
      3576502.69     10498354.50      3576402.43     10498307.62
      3576153.60     10498258.04      3575990.73     10498144.96
      3575850.82     10498084.75      3575698.63     10498048.83
      3575656.33     10498014.20      3575277.17     10498000.91
      3575083.35     10497971.51      3574946.98     10497981.33
      3574764.47     10498105.97      3574650.77     10498158.42
      3574173.32     10498274.57      3574016.52     10498339.96
      3573802.11     10498341.64      3573659.87     10498288.23
      3573479.74     10498134.15      3573405.96     10498025.64
      3573358.22     10497839.01      3573136.32     10497677.98

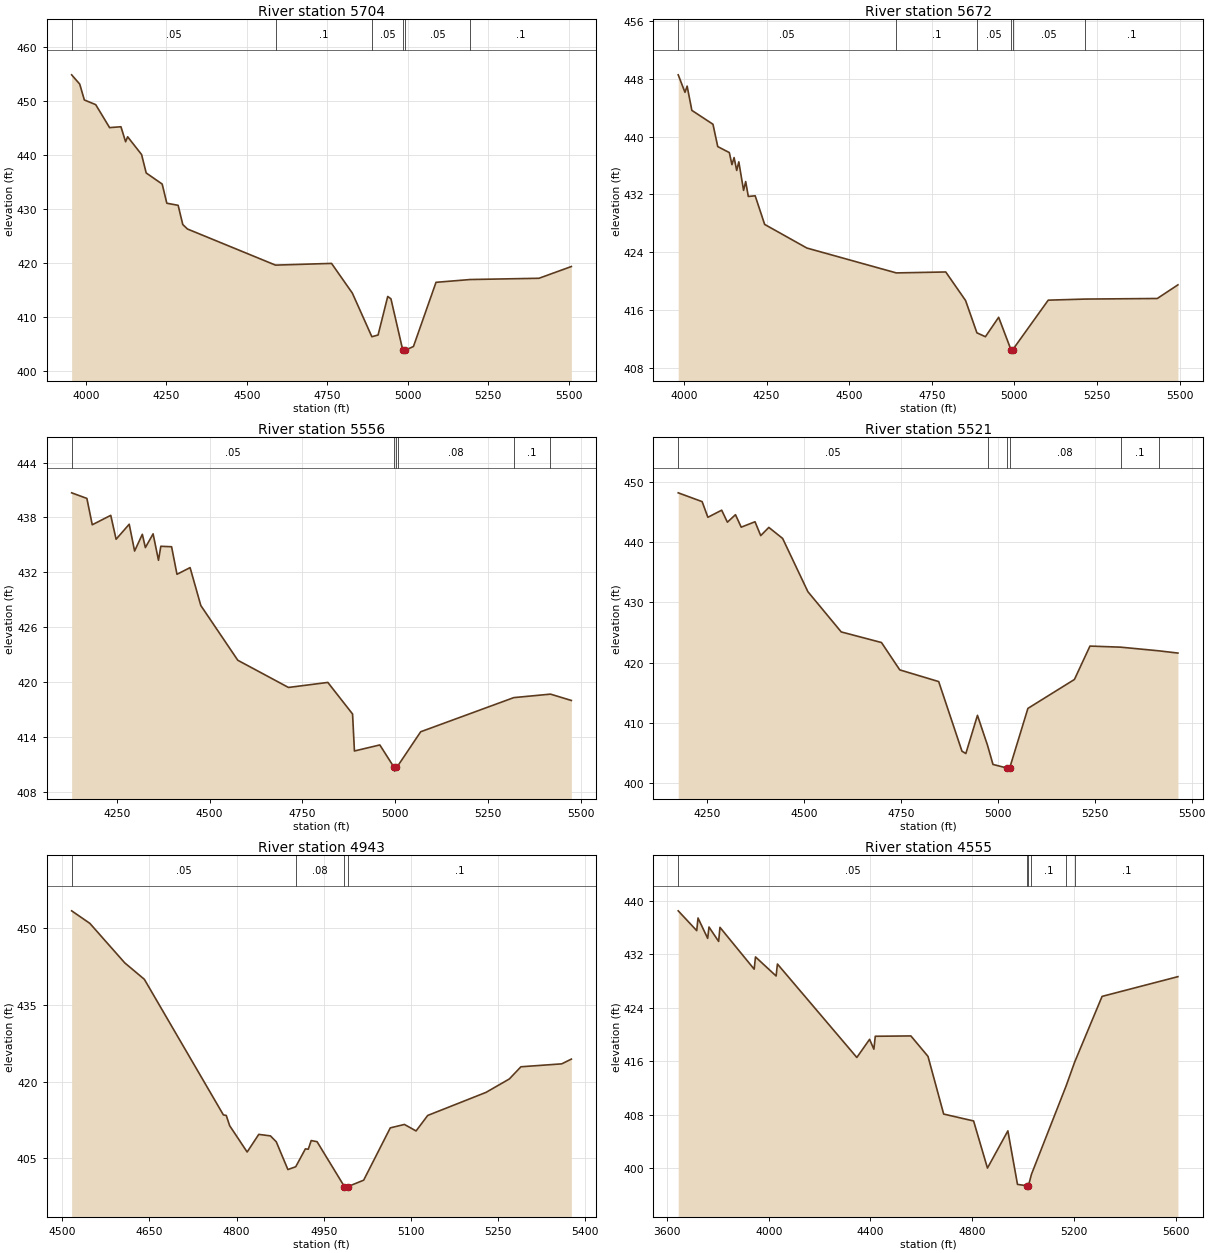
Type RM Length L Ch R = 1,5704,32,32,32
BEGIN DESCRIPTION:
UNT0171 IN SAND CR 6.4
END DESCRIPTION:
XS GIS Cut Line= 3
      3577347.62     10499691.69      3576816.40     10500113.55
      3575941.39     10500134.38
#Sta/Elev= 30
  3955.2  454.84  3980.3  453.12  3994.7  450.18  4030.0  449.31  4073.2  445.05
  4108.5  445.21  4122.9  442.43  4129.3  443.35  4172.6  440.06  4187.0  436.64
  4236.7  434.58  4251.1  431.03  4286.3  430.64  4300.7  427.08  4315.2  426.25
  4589.0  419.55  4763.2  419.87  4827.9  414.36  4888.6  406.27  4907.9  406.59
  4937.9  413.74  4947.9  413.30  4984.9  403.73  4987.7  403.23  4990.9  403.73
  5017.9  404.46  5088.0  416.36  5194.5  416.88  5408.1  417.11  5508.8  419.29
#Mann=6,-1,0
  3955.2    0.05       0  4589.0     0.1       0  4888.6    0.05       0
  4984.9    0.03       0  4990.9    0.05       0  5194.5     0.1       0
Bank Sta=4984.9,4990.9
Exp/Cntr=0.3,0.1

Type RM Length L Ch R = 1,5672,116,116,116
BEGIN DESCRIPTION:
UNT0171 IN SAND CR 6.3
END DESCRIPTION:
XS GIS Cut Line= 3
      3577319.02     10499660.41      3576798.17     10500087.50
      3575959.58     10500095.32
#Sta/Elev= 30
  3982.8  448.55  4003.3  446.13  4009.8  446.99  4024.1  443.63  4088.0  441.71
  4102.4  438.62  4137.5  437.79  4145.4  436.12  4151.9  437.10  4159.8  435.32
  4166.2  436.51  4180.6  432.56  4187.0  433.78  4194.9  431.72  4215.7  431.81
  4244.4  427.85  4372.2  424.58  4642.8  421.14  4792.4  421.27  4852.4  417.32
  4886.7  412.85  4912.4  412.31  4952.5  415.00  4989.5  410.54  4992.2  410.04
  4995.5  410.54  5102.5  417.37  5214.5  417.52  5432.5  417.60  5495.0  419.49
#Mann=6,-1,0
  3982.8    0.05       0  4642.8     0.1       0  4886.7    0.05       0
  4989.5    0.03       0  4995.5    0.05       0  5214.5     0.1       0
Bank Sta=4989.5,4995.5
Exp/Cntr=0.3,0.1

Type RM Length L Ch R = 1,5556,35,35,35
BEGIN DESCRIPTION:
UNT0171 IN SAND CR 6.1
END DESCRIPTION:
XS GIS Cut Line= 4
      3577131.47     10499543.27      3576824.21     10499939.07
      3576712.23     10499978.13      3575986.43     10499970.33
#Sta/Elev= 30
  4128.5  440.69  4169.5  440.08  4184.0  437.20  4233.8  438.23  4248.2  435.62
  4283.5  437.26  4298.0  434.33  4318.8  436.16  4327.0  434.71  4347.8  436.21
  4362.3  433.32  4368.6  434.85  4397.6  434.80  4412.1  431.79  4447.4  432.52
  4476.3  428.38  4575.9  422.40  4712.3  419.43  4818.3  419.98  4884.9  416.53
  4889.9  412.49  4958.3  413.15  4995.3  410.79  4998.1  410.29  5001.3  410.79
  5006.3  410.84  5068.3  414.59  5319.0  418.32  5417.8  418.70  5474.0  418.01
#Mann=6,-1,0
  4128.5    0.05       0  4995.3    0.03       0  5001.3    0.05       0
  5006.3    0.08       0  5319.0     0.1       0  5417.8    0.08       0
Bank Sta=4995.3,5001.3
Exp/Cntr=0.3,0.1

Type RM Length L Ch R = 1,5521,578,578,578
BEGIN DESCRIPTION:
UNT0171 IN SAND CR 6.2
END DESCRIPTION:
XS GIS Cut Line= 4
      3577082.02     10499525.01      3576819.00     10499892.19
      3576712.23     10499946.88      3575995.29     10499928.70
#Sta/Elev= 30
  4175.9  448.16  4237.6  446.70  4252.4  444.10  4288.0  445.28  4302.7  443.29
  4323.6  444.53  4338.4  442.46  4374.0  443.36  4388.7  441.06  4409.6  442.42
  4445.2  440.59  4510.3  431.76  4596.3  425.08  4700.1  423.32  4747.3  418.78
  4847.7  416.84  4907.7  405.29  4917.7  404.90  4947.7  411.24  4973.6  406.27
  4987.7  403.09  5024.7  402.48  5027.5  401.98  5030.7  402.48  5077.8  412.39
  5197.8  417.19  5237.8  422.73  5317.0  422.55  5415.8  421.94  5464.7  421.57
#Mann=6,-1,0
  4175.9    0.05       0  4973.6    0.08       0  5024.7    0.07       0
  5030.7    0.08       0  5317.0     0.1       0  5415.8    0.08       0
Bank Sta=5024.7,5030.7
Exp/Cntr=0.3,0.1

Type RM Length L Ch R = 1,4943,388,388,388
BEGIN DESCRIPTION:
UNT0171 IN SAND CR 4.1
END DESCRIPTION:
XS GIS Cut Line= 2
      3576823.32     10499347.92      3575965.57     10499408.57
#Sta/Elev= 30
  4516.2  453.41  4547.5  450.96  4607.6  443.23  4641.3  440.02  4777.3  413.50
  4782.3  413.38  4788.1  411.39  4818.2  406.24  4838.2  409.69  4858.3  409.39
  4868.3  408.24  4888.3  402.81  4901.8  403.36  4918.4  406.85  4923.4  406.79
  4928.4  408.48  4938.5  408.26  4985.6  399.48  4988.3  398.98  4991.6  399.48
  5018.7  400.73  5064.5  410.96  5088.8  411.63  5108.9  410.36  5128.9  413.39
  5229.2  417.90  5269.3  420.52  5289.3  422.91  5359.5  423.48  5376.1  424.41
#Mann=4,-1,0
  4516.2    0.05       0  4901.8    0.08       0  4985.6    0.07       0
  4991.6     0.1       0
Bank Sta=4985.6,4991.6
Exp/Cntr=0.3,0.1

Type RM Length L Ch R = 1,4555,38,38,38
BEGIN DESCRIPTION:
UNT0171 IN SAND CR 4.3
END DESCRIPTION:
XS GIS Cut Line= 5
      3577687.92     10498590.54      3576997.82     10498746.79
      3576472.65     10499007.21      3576370.65     10499002.87
      3575901.91     10499326.22
#Sta/Elev= 30
  3643.9  438.49  3716.7  435.53  3721.8  437.42  3759.8  434.37  3764.9  436.07
  3802.9  433.92  3808.1  436.02  3942.6  429.77  3947.8  431.60  4028.9  428.75
  4034.1  430.54  4346.4  416.57  4396.5  419.28  4413.4  417.81  4418.9  419.74
  4559.0  419.79  4626.3  416.73  4687.9  408.11  4805.6  407.08  4860.1  400.04
  4940.4  405.60  4978.2  397.60  5015.3  397.39  5018.0  396.89  5021.3  397.39
  5033.1  399.10  5169.4  412.31  5203.1  415.88  5310.9  425.70  5609.2  428.65
#Mann=6,-1,0
  3643.9    0.05       0  5015.3   0.035       0  5021.3    0.05       0
  5033.1     0.1       0  5169.4    0.05       0  5203.1     0.1       0
Bank Sta=5015.3,5021.3
Exp/Cntr=0.3,0.1

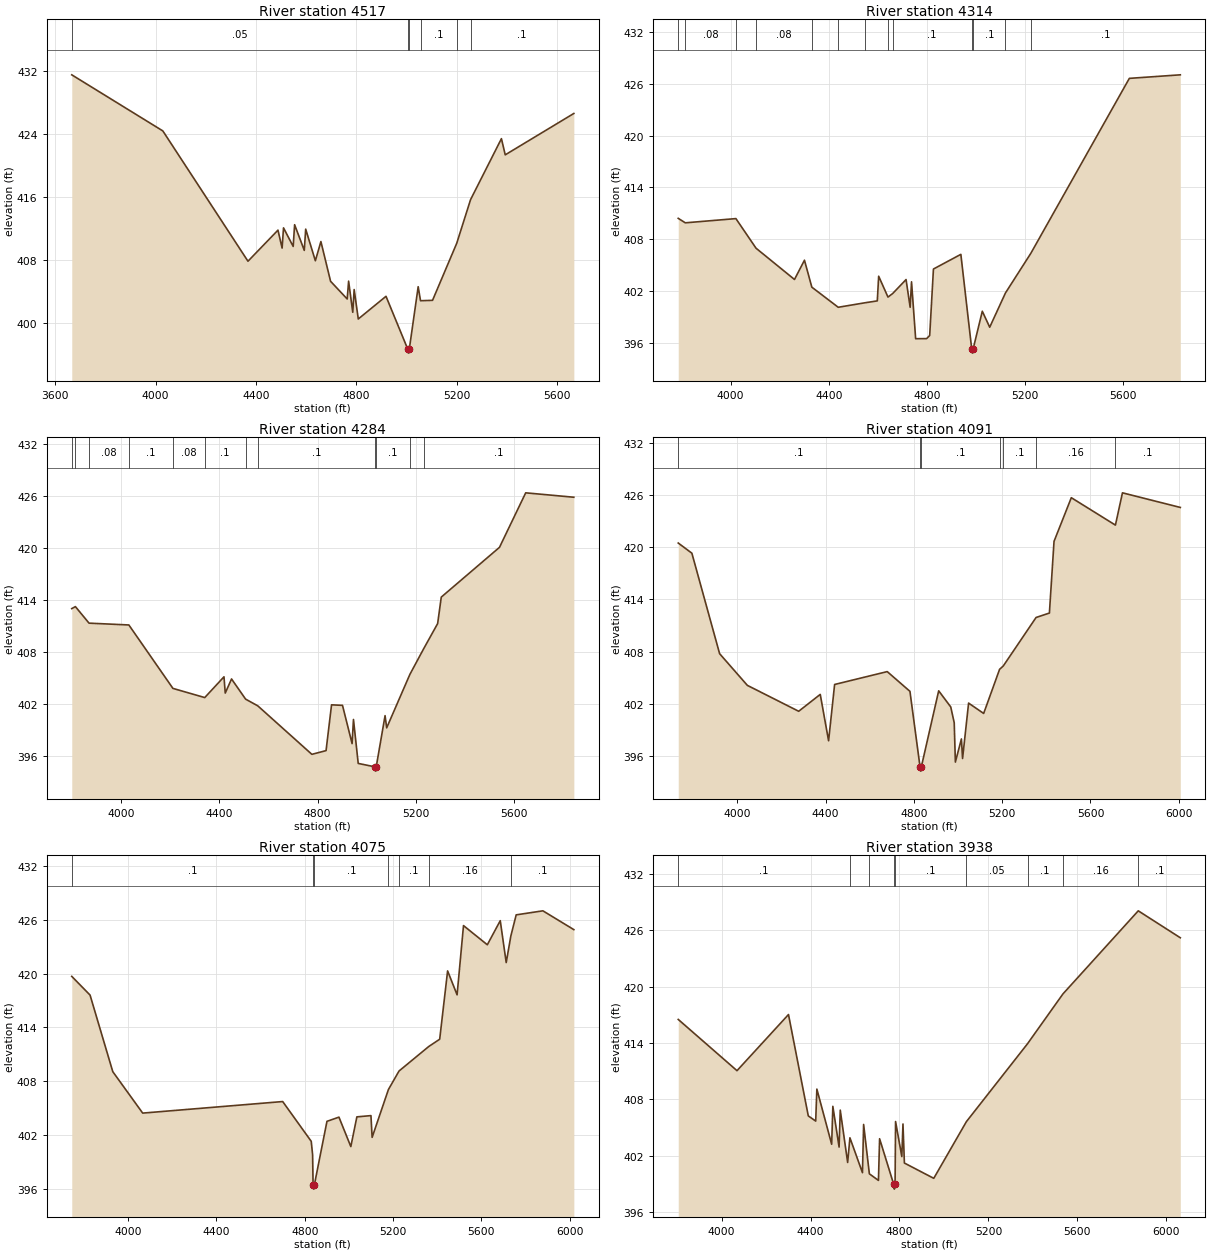
Type RM Length L Ch R = 1,4517,203,203,203
BEGIN DESCRIPTION:
UNT0171 IN SAND CR 4.2
END DESCRIPTION:
XS GIS Cut Line= 5
      3577682.71     10498562.33      3576979.59     10498709.90
      3576475.25     10498973.79      3576397.13     10498968.58
      3575867.65     10499315.78
#Sta/Elev= 30
  3666.5  431.48  4029.1  424.35  4368.1  407.79  4487.5  411.74  4504.0  409.46
  4509.6  412.03  4548.1  409.67  4553.8  412.43  4592.3  409.17  4597.9  411.87
  4636.4  407.85  4658.5  410.29  4697.0  405.24  4763.2  402.99  4768.8  405.26
  4785.3  401.30  4790.9  404.19  4807.3  400.45  4917.7  403.33  5004.4  396.61
  5007.2  396.11  5010.4  396.61  5045.8  404.55  5055.1  402.77  5103.0  402.82
  5199.3  410.07  5254.4  415.62  5377.3  423.37  5392.4  421.31  5665.6  426.57
#Mann=6,-1,0
  3666.5    0.05       0  5004.4   0.035       0  5010.4    0.05       0
  5055.1     0.1       0  5199.3    0.05       0  5254.4     0.1       0
Bank Sta=5004.4,5010.4
Exp/Cntr=0.3,0.1

Type RM Length L Ch R = 1,4314,30,30,30
BEGIN DESCRIPTION:
UNT0171 IN SAND CR 3.1
END DESCRIPTION:
XS GIS Cut Line= 5
      3577615.84     10498378.75      3576994.35     10498538.46
      3576534.54     10498769.45      3576410.84     10498782.47
      3575787.95     10499227.21
#Sta/Elev= 30
  3786.4  410.42  3815.2  409.90  4021.4  410.39  4103.5  406.96  4260.1  403.34
  4300.8  405.57  4330.8  402.45  4438.4  400.12  4547.3  400.64  4597.6  400.86
  4603.2  403.72  4641.1  401.30  4660.2  401.71  4714.8  403.33  4731.5  400.12
  4737.1  403.07  4753.9  396.48  4798.5  396.49  4811.1  396.85  4826.4  404.55
  4938.1  406.25  4982.3  395.31  4985.1  394.81  4988.3  395.31  5025.5  399.66
  5055.7  397.81  5119.9  401.78  5223.5  406.38  5624.7  426.63  5832.4  427.04
#Mann=13,-1,0
  3786.4    0.05       0  3815.2    0.08       0  4021.4     0.1       0
  4103.5    0.08       0  4330.8     0.1       0  4438.4    0.05       0
  4547.3     0.1       0  4641.1    0.05       0  4660.2     0.1       0
  4982.3    0.07       0  4988.3     0.1       0  5119.9    0.05       0
  5223.5     0.1       0
Bank Sta=4982.3,4988.3
Exp/Cntr=0.3,0.1

Type RM Length L Ch R = 1,4284,193,193,193
BEGIN DESCRIPTION:
UNT0171 IN SAND CR 3.3
END DESCRIPTION:
XS GIS Cut Line= 5
      3577614.62     10498351.38      3576993.05     10498511.12
      3576533.24     10498742.11      3576409.54     10498755.13
      3575786.47     10499199.99
#Sta/Elev= 30
  3798.2  413.00  3813.0  413.23  3868.6  411.32  4030.9  411.11  4210.5  403.78
  4340.2  402.72  4418.6  405.12  4423.7  403.24  4449.4  404.87  4506.7  402.54
  4556.5  401.76  4776.8  396.16  4834.6  396.59  4857.0  401.88  4901.6  401.82
  4940.7  397.40  4946.3  400.19  4965.7  395.11  5033.1  394.72  5035.9  394.22
  5039.1  394.72  5075.1  400.63  5081.7  399.22  5176.3  405.40  5232.4  408.36
  5289.4  411.27  5304.2  414.33  5541.4  420.08  5648.3  426.38  5844.5  425.87
#Mann=12,-1,0
  3798.2    0.05       0  3813.0     0.1       0  3868.6    0.08       0
  4030.9     0.1       0  4210.5    0.08       0  4340.2     0.1       0
  4506.7    0.05       0  4556.5     0.1       0  5033.1    0.07       0
  5039.1     0.1       0  5176.3    0.05       0  5232.4     0.1       0
Bank Sta=5033.1,5039.1
Exp/Cntr=0.3,0.1

Type RM Length L Ch R = 1,4091,16,16,16
BEGIN DESCRIPTION:
UNT0171 IN SAND CR 3.6
END DESCRIPTION:
XS GIS Cut Line= 4
      3577761.13     10498205.64      3576495.48     10498598.88
      3576365.27     10498643.15      3575688.19     10499091.06
#Sta/Elev= 30
  3732.4  420.49  3794.2  419.32  3919.9  407.77  4045.5  404.13  4278.1  401.15
  4375.8  403.09  4413.6  397.76  4440.9  404.23  4679.3  405.71  4782.2  403.44
  4827.9  394.77  4830.6  394.27  4833.9  394.77  4912.4  403.50  4967.0  401.65
  4982.8  399.83  4988.0  395.31  5015.3  397.97  5020.6  395.72  5047.9  402.09
  5116.2  400.90  5188.3  405.97  5205.1  406.36  5353.6  411.93  5414.0  412.44
  5435.0  420.68  5513.3  425.70  5713.1  422.55  5745.0  426.26  6007.1  424.58
#Mann=7,-1,0
  3732.4     0.1       0  4827.9    0.07       0  4833.9     0.1       0
  5188.3    0.05       0  5205.1     0.1       0  5353.6    0.16       0
  5713.1     0.1       0
Bank Sta=4827.9,4833.9
Exp/Cntr=0.3,0.1

Type RM Length L Ch R = 1,4075,137,137,137
BEGIN DESCRIPTION:
UNT0171 IN SAND CR 3.2
END DESCRIPTION:
XS GIS Cut Line= 4
      3577748.11     10498192.62      3576482.46     10498585.86
      3576352.25     10498630.13      3575675.16     10499078.05
#Sta/Elev= 30
  3744.7  419.69  3827.6  417.60  3930.5  409.05  4066.0  404.42  4700.3  405.71
  4829.6  401.27  4835.8  399.79  4838.0  396.43  4840.8  395.93  4844.0  396.43
  4900.9  403.50  4955.2  403.97  5009.0  400.68  5036.4  404.00  5100.2  404.14
  5105.5  401.71  5179.3  407.05  5227.4  409.12  5362.2  411.86  5411.6  412.67
  5447.5  420.30  5490.4  417.63  5519.5  425.36  5627.4  423.22  5686.0  425.91
  5713.0  421.23  5733.9  424.19  5758.2  426.56  5879.2  427.01  6019.4  424.91
#Mann=7,-1,0
  3744.7     0.1       0  4838.0    0.07       0  4844.0     0.1       0
  5179.3    0.05       0  5227.4     0.1       0  5362.2    0.16       0
  5733.9     0.1       0
Bank Sta=4838,4844
Exp/Cntr=0.3,0.1

Type RM Length L Ch R = 1,3938,36,36,36
BEGIN DESCRIPTION:
UNT0171 IN SAND CR 3.4
END DESCRIPTION:
XS GIS Cut Line= 4
      3577677.77     10498091.06      3576459.02     10498450.44
      3576274.12     10498538.98      3575619.42     10498967.66
#Sta/Elev= 30
  3804.9  416.50  4069.2  411.04  4300.8  417.02  4389.9  406.22  4423.2  405.67
  4428.4  409.08  4495.0  403.20  4500.3  407.24  4528.4  402.90  4533.6  406.84
  4566.9  401.26  4577.1  403.89  4633.5  400.17  4638.7  405.31  4664.6  400.05
  4705.4  399.35  4710.6  403.79  4774.2  398.92  4777.0  398.42  4780.2  398.92
  4782.4  405.62  4810.5  401.89  4815.7  405.36  4822.1  401.20  4954.2  399.57
  5101.0  405.61  5375.9  413.91  5535.0  419.21  5874.0  428.07  6063.1  425.20
#Mann=9,-1,0
  3804.9     0.1       0  4577.1    0.08       0  4664.6     0.1       0
  4774.2    0.07       0  4780.2     0.1       0  5101.0    0.05       0
  5375.9     0.1       0  5535.0    0.16       0  5874.0     0.1       0
Bank Sta=4774.2,4780.2
Exp/Cntr=0.3,0.1

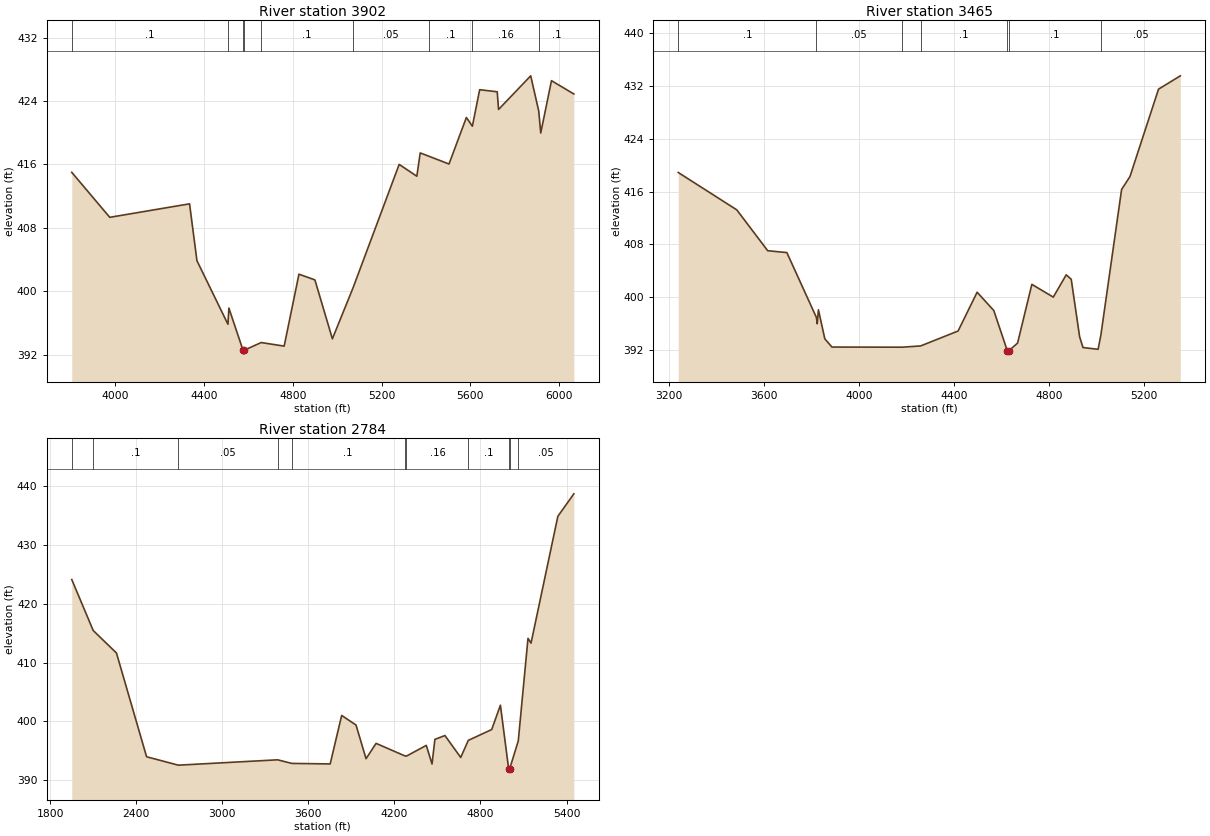
Type RM Length L Ch R = 1,3902,437,437,437
BEGIN DESCRIPTION:
UNT0171 IN SAND CR 3.5
END DESCRIPTION:
XS GIS Cut Line= 4
      3577667.38     10498057.20      3576448.60     10498416.58
      3576263.71     10498505.13      3575607.43     10498934.83
#Sta/Elev= 30
  3805.4  415.01  3976.4  409.34  4335.6  411.04  4368.9  403.87  4508.4  395.86
  4512.6  397.90  4576.2  392.59  4579.0  392.09  4582.2  392.59  4658.0  393.55
  4761.5  393.10  4828.1  402.17  4899.9  401.45  4978.6  394.02  5072.0  400.48
  5279.2  416.01  5358.8  414.52  5373.9  417.46  5412.2  417.05  5503.5  416.06
  5581.8  421.93  5608.7  420.83  5641.6  425.43  5720.6  425.17  5726.6  422.94
  5871.3  427.18  5907.5  422.74  5916.5  419.97  5964.8  426.57  6065.5  424.89
#Mann=9,-1,0
  3805.4     0.1       0  4508.4    0.08       0  4576.2    0.07       0
  4582.2    0.08       0  4658.0     0.1       0  5072.0    0.05       0
  5412.2     0.1       0  5608.7    0.16       0  5907.5     0.1       0
Bank Sta=4576.2,4582.2
Exp/Cntr=0.3,0.1

Type RM Length L Ch R = 1,3465,681,681,681
BEGIN DESCRIPTION:
UNT0171 IN SAND CR 3.0
END DESCRIPTION:
XS GIS Cut Line= 3
      3577848.06     10498023.21      3576228.30     10498143.00
      3575886.11     10498495.56
#Sta/Elev= 30
  3237.8  418.89  3484.4  413.24  3614.8  407.05  3695.5  406.77  3819.9  396.96
  3823.5  396.00  3828.5  398.11  3855.4  393.72  3885.5  392.47  4181.0  392.45
  4259.2  392.64  4417.0  394.90  4497.2  400.77  4567.4  398.00  4624.5  391.90
  4627.3  391.40  4630.5  391.90  4667.6  393.07  4727.8  401.96  4818.1  400.03
  4872.6  403.40  4893.7  402.73  4929.1  394.02  4943.3  392.40  5006.8  392.13
  5018.7  394.30  5105.9  416.32  5141.1  418.27  5261.5  431.50  5353.3  433.52
#Mann=7,-1,0
  3237.8     0.1       0  3819.9    0.05       0  4181.0    0.08       0
  4259.2     0.1       0  4624.5    0.07       0  4630.5     0.1       0
  5018.7    0.05       0
Bank Sta=4624.5,4630.5
Exp/Cntr=0.3,0.1

Type RM Length L Ch R = 1,2784,0,0,0
BEGIN DESCRIPTION:
UNT0171 IN SAND CR 4.0
END DESCRIPTION:
XS GIS Cut Line= 3
      3578353.69     10497798.54      3575485.59     10497822.85
      3575584.45     10498447.27
#Sta/Elev= 30
  1950.7  424.09  2100.2  415.44  2262.3  411.62  2472.3  394.01  2693.6  392.58
  3385.9  393.49  3484.8  392.88  3752.3  392.79  3832.4  401.02  3932.4  399.40
  4002.4  393.68  4072.4  396.28  4271.7  394.17  4284.2  394.12  4422.4  395.94
  4462.4  392.78  4482.4  396.96  4552.4  397.61  4662.4  393.89  4715.3  396.79
  4878.4  398.63  4939.2  402.76  4996.9  391.90  4999.7  391.40  5002.9  391.90
  5063.6  396.69  5131.5  414.11  5152.6  413.30  5339.6  434.82  5451.1  438.64
#Mann=11,-1,0
  1950.7    0.05       0  2100.2     0.1       0  2693.6    0.05       0
  3385.9    0.08       0  3484.8     0.1       0  4271.7    0.05       0
  4284.2    0.16       0  4715.3     0.1       0  4996.9    0.07       0
  5002.9     0.1       0  5063.6    0.05       0
Bank Sta=4996.9,5002.9
Exp/Cntr=0.3,0.1

Chan Stop Cuts=-1