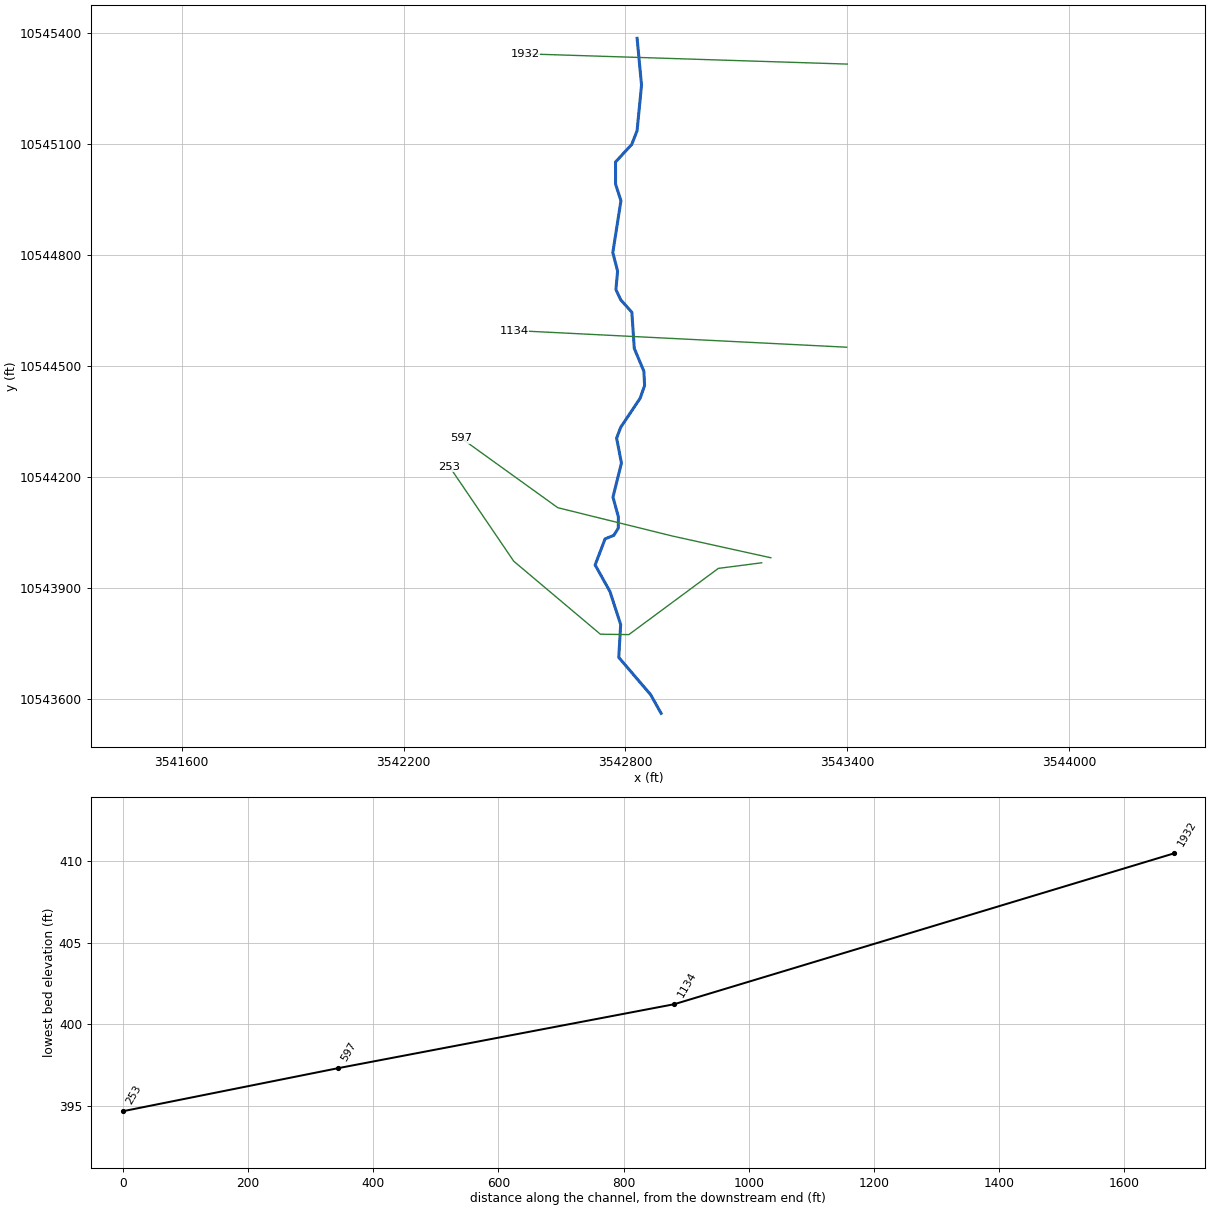
--- UNT01712 IN SAND CR.prj (project) ---

Proj Title=UNT01712 IN SAND CR Base Level Engineering
Current Plan=p01
Default Exp/Contr=0.3,0.1
English Units
Geom File=g01
Flow File=f01
Plan File=p01
BEGIN DESCRIPTION:
UNT01712 IN SAND CR
END DESCRIPTION:

--- UNT01712 IN SAND CR.p01 (plan) ---

Plan Title=Multiple Run
Short Identifier=Multiple
Geom File=g01
Flow File=f01
Subcritical Flow
K Sum by GR= 0
Std Step Tol= 0.01
Critical Tol= 0.01
Num of Std Step Trials= 20
Max Error Tol= 0.3
Flow Tol Ratio= 0.001
Split Flow NTrial= 30
Split Flow Tol= 0.02
Split Flow Ratio= 0.02
Log Output Level= 0
Friction Slope Method= 1
Unsteady Friction Slope Method= 2
Unsteady Bridges Friction Slope Method= 1
Parabolic Critical Depth
Global Vel Dist=  1 , 1 , 1
Global Log Level= 0
CheckData=True
Encroach Param= -1, 0, 0, 0
BEGIN DESCRIPTION:
Multiple Run
END DESCRIPTION:

--- UNT01712 IN SAND CR.f01 (steady flow) ---

Flow Title=Multiple
Number of Profiles=7
Profile Names=10-year,25-year,50-year,1pct_min,100-year,1pct_plu,500-year
River Rch & RM= UNT01712 IN SAND,Reach-1,1932
     261     329     379     322     435     588     567
Boundary for River Rch & Prof#=UNT01712 IN SAND,Reach-1,1
Up Type=0
Dn Type=3
Dn Slope=0.005
Boundary for River Rch & Prof#=UNT01712 IN SAND,Reach-1,2
Up Type=0
Dn Type=3
Dn Slope=0.005
Boundary for River Rch & Prof#=UNT01712 IN SAND,Reach-1,3
Up Type=0
Dn Type=3
Dn Slope=0.005
Boundary for River Rch & Prof#=UNT01712 IN SAND,Reach-1,4
Up Type=0
Dn Type=3
Dn Slope=0.005
Boundary for River Rch & Prof#=UNT01712 IN SAND,Reach-1,5
Up Type=0
Dn Type=3
Dn Slope=0.005
Boundary for River Rch & Prof#=UNT01712 IN SAND,Reach-1,6
Up Type=0
Dn Type=3
Dn Slope=0.005
Boundary for River Rch & Prof#=UNT01712 IN SAND,Reach-1,7
Up Type=0
Dn Type=3
Dn Slope=0.005

--- UNT01712 IN SAND CR.g01 (geometry) ---

Geom Title=Existing Conditions

River Reach=UNT01712 IN SAND,Reach-1
Reach XY= 30
      3542831.70     10545385.83      3542843.68     10545259.44
      3542831.64     10545136.00      3542817.14     10545098.94
      3542773.37     10545051.39      3542773.35     10544991.71
      3542787.98     10544946.60      3542766.02     10544806.61
      3542778.95     10544756.10      3542774.36     10544706.63
      3542787.14     10544678.98      3542817.50     10544645.06
      3542824.07     10544547.20      3542850.00     10544485.53
      3542851.98     10544446.94      3542839.95     10544412.63
      3542787.36     10544334.02      3542776.27     10544304.70
      3542789.37     10544237.14      3542766.41     10544145.08
      3542781.08     10544091.71      3542780.83     10544061.21
      3542768.45     10544041.51      3542745.18     10544032.34
      3542718.16     10543961.72      3542758.18     10543890.06
      3542787.24     10543800.60      3542782.11     10543711.64
      3542868.58     10543610.59      3542896.64     10543560.33

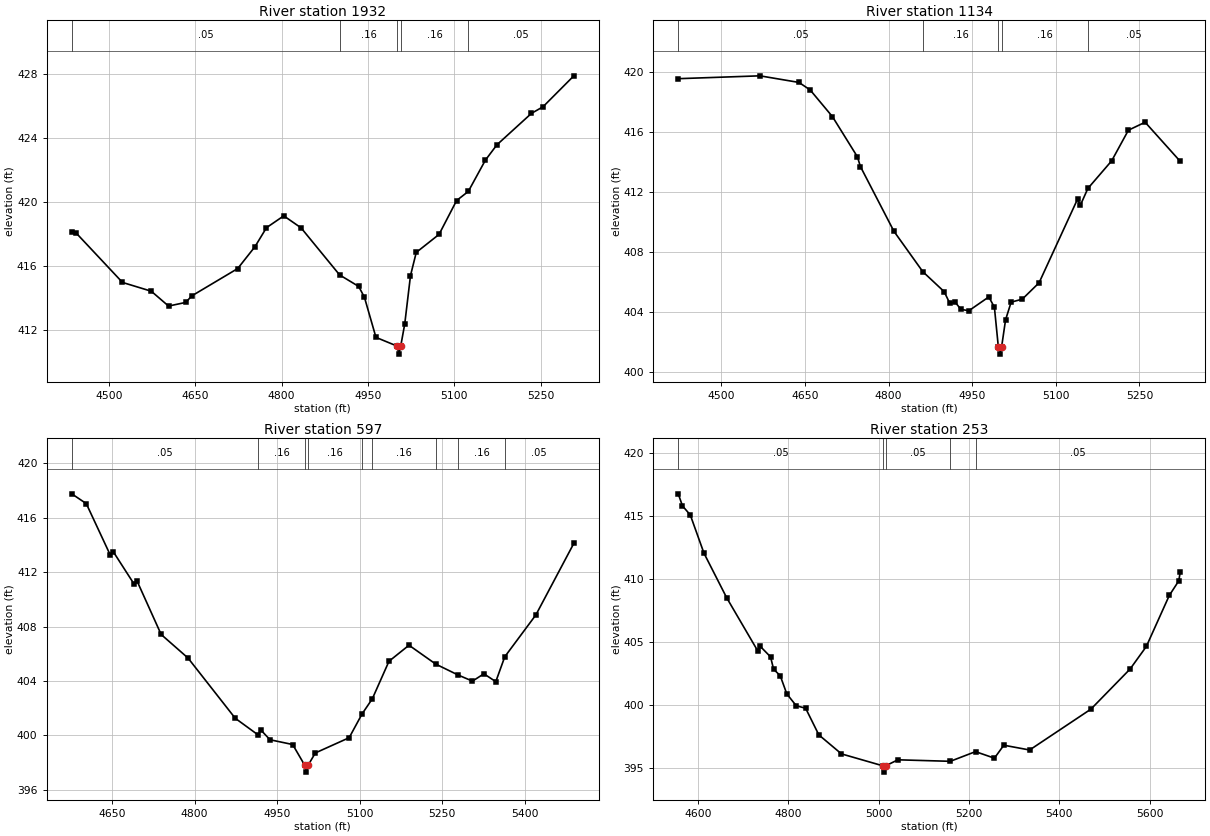
Type RM Length L Ch R = 1,1932,798,798,798
BEGIN DESCRIPTION:
UNT01712 IN SAND CR 4.0
END DESCRIPTION:
XS GIS Cut Line= 2
      3543400.14     10545316.18      3542528.58     10545343.95
#Sta/Elev= 30
  4435.6  418.08  4443.6  418.03  4523.7  414.95  4573.7  414.40  4603.7  413.47
  4633.7  413.70  4643.7  414.10  4723.8  415.82  4753.8  417.19  4773.8  418.38
  4803.8  419.12  4833.8  418.37  4900.8  415.42  4933.9  414.70  4943.9  414.02
  4963.9  411.51  5000.9  410.96  5003.7  410.46  5006.9  410.96  5013.9  412.35
  5023.9  415.38  5033.9  416.83  5073.5  417.96  5104.0  420.08  5124.3  420.65
  5154.0  422.61  5174.0  423.57  5234.0  425.54  5254.0  425.95  5307.6  427.89
#Mann=5,-1,0
  4435.6    0.05       0  4900.8    0.16       0  5000.9    0.07       0
  5006.9    0.16       0  5124.3    0.05       0
Bank Sta=5000.9,5006.9
Exp/Cntr=0.3,0.1

Type RM Length L Ch R = 1,1134,537,537,537
BEGIN DESCRIPTION:
UNT01712 IN SAND CR 3.0
END DESCRIPTION:
XS GIS Cut Line= 2
      3543398.38     10544550.55      3542499.11     10544595.69
#Sta/Elev= 30
  4422.8  419.56  4569.3  419.75  4639.3  419.31  4659.4  418.81  4699.4  417.03
  4744.1  414.36  4749.5  413.71  4809.6  409.40  4861.4  406.71  4899.7  405.38
  4909.7  404.61  4919.7  404.67  4929.7  404.20  4944.0  404.11  4979.8  405.03
  4989.8  404.34  4996.8  401.72  4999.5  401.22  5002.8  401.72  5009.8  403.50
  5019.8  404.68  5039.8  404.88  5069.9  405.97  5138.9  411.54  5143.9  411.13
  5157.4  412.25  5200.1  414.09  5230.1  416.13  5260.1  416.66  5323.2  414.05
#Mann=5,-1,0
  4422.8    0.05       0  4861.4    0.16       0  4996.8    0.07       0
  5002.8    0.16       0  5157.4    0.05       0
Bank Sta=4996.8,5002.8
Exp/Cntr=0.3,0.1

Type RM Length L Ch R = 1,597,344,344,344
BEGIN DESCRIPTION:
UNT01712 IN SAND CR 1.0
END DESCRIPTION:
XS GIS Cut Line= 4
      3543193.53     10543981.11      3542926.18     10544040.13
      3542617.19     10544116.56      3542356.89     10544303.91
#Sta/Elev= 30
  4576.6  417.76  4603.0  417.04  4646.6  413.26  4651.8  413.52  4690.3  411.10
  4695.4  411.34  4739.1  407.42  4787.9  405.69  4873.8  401.26  4915.2  400.04
  4920.3  400.40  4937.0  399.68  4978.2  399.33  5000.2  397.80  5003.0  397.30
  5006.2  397.80  5019.4  398.71  5080.9  399.83  5104.4  401.58  5123.0  402.69
  5153.3  405.45  5189.7  406.63  5238.4  405.24  5279.0  404.44  5305.1  403.99
  5325.9  404.53  5347.5  403.95  5363.8  405.78  5420.4  408.86  5489.4  414.12
#Mann=9,-1,0
  4576.6    0.05       0  4915.2    0.16       0  5000.2    0.07       0
  5006.2    0.16       0  5104.4    0.05       0  5123.0    0.16       0
  5238.4    0.05       0  5279.0    0.16       0  5363.8    0.05       0
Bank Sta=5000.2,5006.2
Exp/Cntr=0.3,0.1

Type RM Length L Ch R = 1,253,0,0,0
BEGIN DESCRIPTION:
UNT01712 IN SAND CR 1.01
END DESCRIPTION:
XS GIS Cut Line= 6
      3543168.60     10543967.58      3543051.36     10543952.38
      3542809.39     10543773.34      3542732.35     10543774.43
      3542497.98     10543971.91      3542324.09     10544227.88
#Sta/Elev= 30
  4555.8  416.79  4565.2  415.83  4582.5  415.11  4612.8  412.07  4663.2  408.52
  4731.6  404.32  4737.8  404.65  4760.2  403.83  4767.1  402.84  4781.7  402.33
  4796.3  400.88  4817.2  399.94  4838.0  399.74  4867.3  397.62  4917.4  396.11
  5009.3  395.16  5012.1  394.66  5015.3  395.16  5042.3  395.64  5158.5  395.52
  5214.3  396.29  5256.2  395.77  5277.0  396.80  5334.2  396.42  5470.0  399.67
  5556.8  402.86  5592.7  404.65  5643.6  408.71  5664.6  409.87  5668.0  410.61
#Mann=5,-1,0
  4555.8    0.05       0  5009.3    0.03       0  5015.3    0.05       0
  5158.5    0.16       0  5214.3    0.05       0
Bank Sta=5009.3,5015.3
Exp/Cntr=0.3,0.1

Chan Stop Cuts=-1