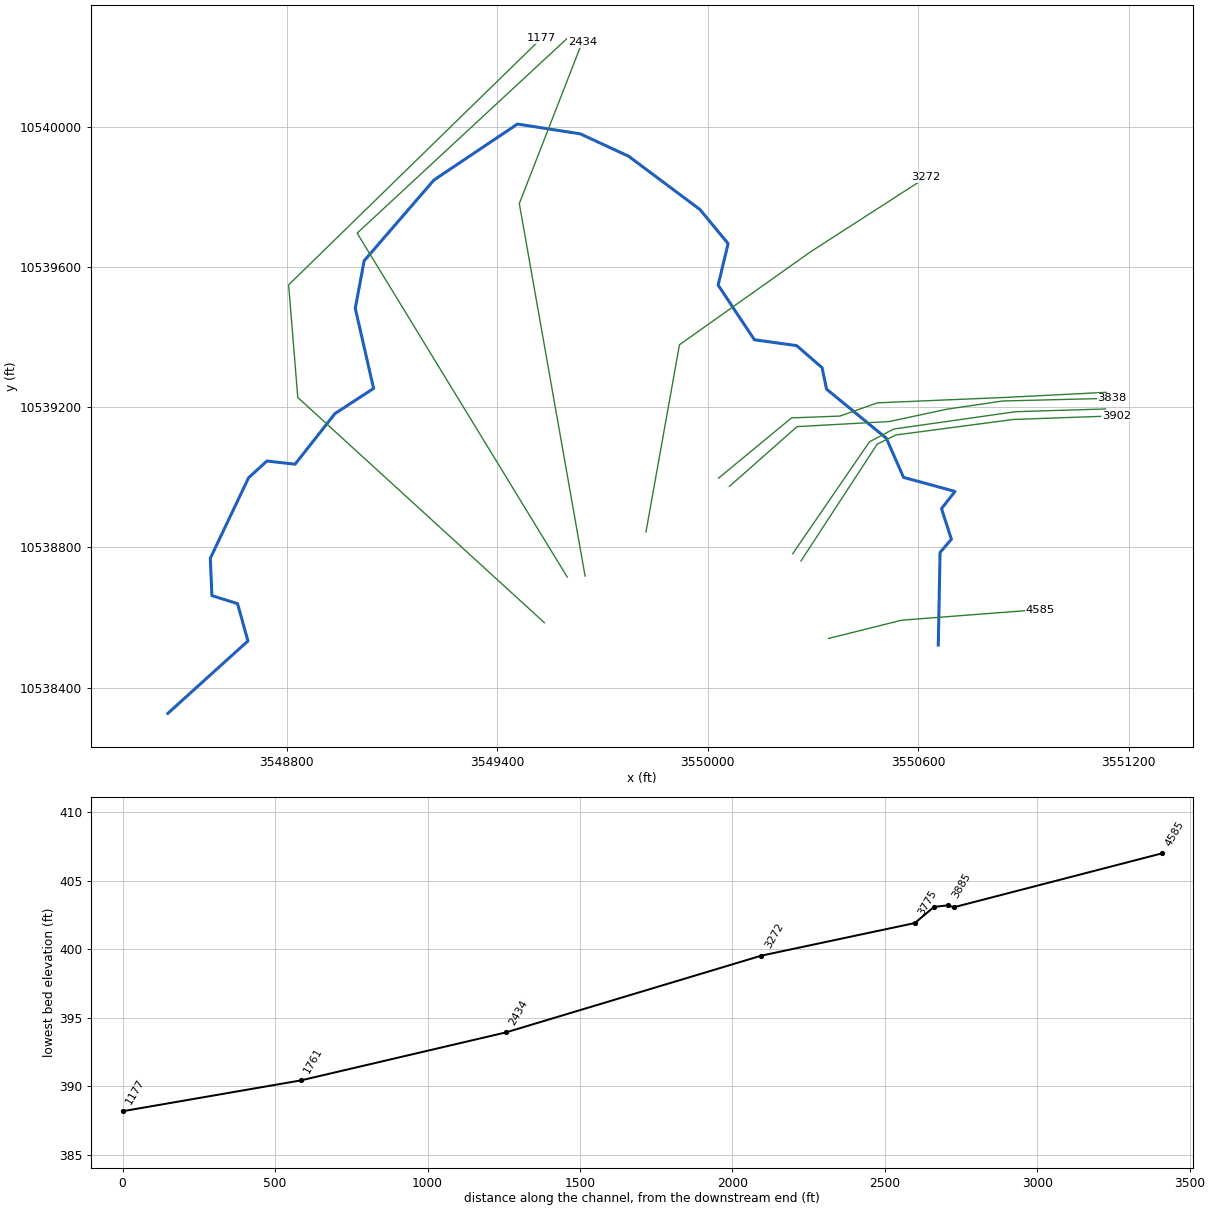
--- UNT01729 IN SAND CR.prj (project) ---

Proj Title=UNT01729 IN SAND CR Base Level Engineering
Current Plan=p01
Default Exp/Contr=0.3,0.1
English Units
Geom File=g01
Flow File=f01
Plan File=p01
BEGIN DESCRIPTION:
UNT01729 IN SAND CR
END DESCRIPTION:

--- UNT01729 IN SAND CR.p01 (plan) ---

Plan Title=Multiple Run
Short Identifier=Multiple
Geom File=g01
Flow File=f01
Subcritical Flow
K Sum by GR= 0
Std Step Tol= 0.01
Critical Tol= 0.01
Num of Std Step Trials= 20
Max Error Tol= 0.3
Flow Tol Ratio= 0.001
Split Flow NTrial= 30
Split Flow Tol= 0.02
Split Flow Ratio= 0.02
Log Output Level= 0
Friction Slope Method= 1
Unsteady Friction Slope Method= 2
Unsteady Bridges Friction Slope Method= 1
Parabolic Critical Depth
Global Vel Dist=  1 , 1 , 1
Global Log Level= 0
CheckData=True
Encroach Param= -1, 0, 0, 0
BEGIN DESCRIPTION:
Multiple Run
END DESCRIPTION:

--- UNT01729 IN SAND CR.f01 (steady flow) ---

Flow Title=Multiple
Number of Profiles=7
Profile Names=10-year,25-year,50-year,1pct_min,100-year,1pct_plu,500-year
River Rch & RM= UNT01729 IN SAND,Reach-1,4585
     527     694     826     719     972    1315    1341
Boundary for River Rch & Prof#=UNT01729 IN SAND,Reach-1,1
Up Type=0
Dn Type=3
Dn Slope=0.005
Boundary for River Rch & Prof#=UNT01729 IN SAND,Reach-1,2
Up Type=0
Dn Type=3
Dn Slope=0.005
Boundary for River Rch & Prof#=UNT01729 IN SAND,Reach-1,3
Up Type=0
Dn Type=3
Dn Slope=0.005
Boundary for River Rch & Prof#=UNT01729 IN SAND,Reach-1,4
Up Type=0
Dn Type=3
Dn Slope=0.005
Boundary for River Rch & Prof#=UNT01729 IN SAND,Reach-1,5
Up Type=0
Dn Type=3
Dn Slope=0.005
Boundary for River Rch & Prof#=UNT01729 IN SAND,Reach-1,6
Up Type=0
Dn Type=3
Dn Slope=0.005
Boundary for River Rch & Prof#=UNT01729 IN SAND,Reach-1,7
Up Type=0
Dn Type=3
Dn Slope=0.005

--- UNT01729 IN SAND CR.g01 (geometry) ---

Geom Title=Existing Conditions

River Reach=UNT01729 IN SAND,Reach-1
Reach XY= 30
      3550657.10     10538521.67      3550662.20     10538785.78
      3550694.49     10538823.28      3550666.37     10538910.78
      3550704.91     10538959.73      3550558.03     10538999.84
      3550509.07     10539111.30      3550338.55     10539251.57
      3550325.82     10539312.66      3550253.38     10539375.54
      3550132.87     10539392.38      3550029.44     10539548.23
      3550057.88     10539666.59      3549977.80     10539763.65
      3549774.53     10539915.69      3549636.41     10539979.65
      3549457.18     10540007.59      3549219.10     10539847.78
      3549020.26     10539617.65      3548994.96     10539481.95
      3549047.16     10539253.45      3548936.95     10539181.76
      3548823.37     10539037.42      3548742.89     10539046.47
      3548690.60     10538998.40      3548581.65     10538769.05
      3548586.23     10538662.64      3548659.35     10538639.60
      3548688.89     10538533.22      3548460.58     10538326.70

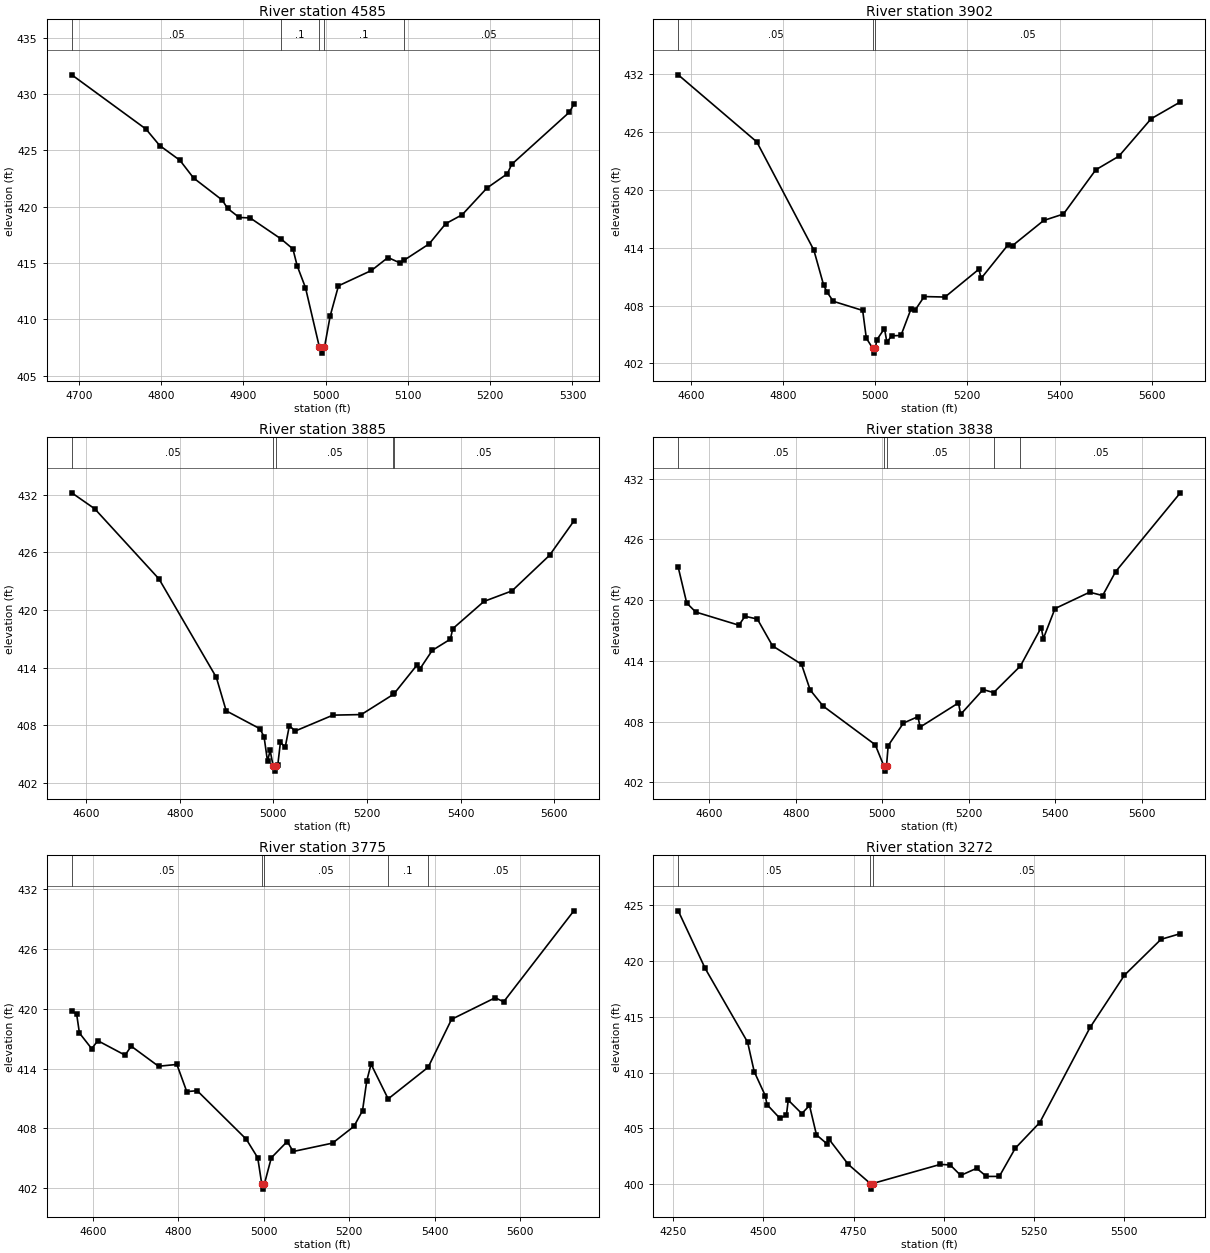
Type RM Length L Ch R = 1,4585,683,683,683
BEGIN DESCRIPTION:
UNT01729 IN SAND CR 4.0
END DESCRIPTION:
XS GIS Cut Line= 3
      3550344.56     10538540.42      3550552.91     10538592.51
      3550947.48     10538622.86
#Sta/Elev= 30
  4691.2  431.69  4781.4  426.88  4798.1  425.42  4822.7  424.11  4839.3  422.54
  4874.2  420.58  4880.6  419.85  4894.8  419.04  4908.1  419.00  4945.6  417.14
  4960.1  416.25  4965.3  414.75  4975.4  412.81  4992.4  407.51  4995.2  407.01
  4998.4  407.51  5005.5  410.33  5015.5  412.98  5055.6  414.34  5075.7  415.49
  5090.5  415.00  5095.1  415.24  5125.8  416.70  5145.9  418.49  5165.9  419.28
  5196.0  421.65  5220.9  422.92  5226.1  423.75  5296.3  428.38  5301.7  429.08
#Mann=5,-1,0
  4691.2    0.05       0  4945.6     0.1       0  4992.4    0.07       0
  4998.4     0.1       0  5095.1    0.05       0
Bank Sta=4992.4,4998.4
Exp/Cntr=0.3,0.1

Type RM Length L Ch R = 1,3902,17,17,17
BEGIN DESCRIPTION:
UNT01729 IN SAND CR 3.1
END DESCRIPTION:
XS GIS Cut Line= 5
      3550265.61     10538761.37      3550483.06     10539094.71
      3550536.44     10539120.75      3550871.08     10539165.02
      3551165.35     10539175.44
#Sta/Elev= 30
  4572.7  431.90  4743.2  424.95  4866.9  413.75  4888.0  410.15  4895.4  409.40
  4909.1  408.44  4972.9  407.49  4980.8  404.62  4994.7  403.57  4997.4  403.07
  5000.7  403.57  5003.2  404.42  5020.2  405.62  5025.4  404.21  5035.8  404.86
  5056.0  404.90  5078.1  407.69  5086.2  407.49  5106.4  408.93  5151.5  408.88
  5225.0  411.76  5230.0  410.82  5288.0  414.27  5298.1  414.21  5365.6  416.81
  5408.6  417.48  5478.7  422.06  5528.8  423.47  5598.8  427.35  5662.1  429.09
#Mann=3,-1,0
  4572.7    0.05       0  4994.7   0.035       0  5000.7    0.05       0
Bank Sta=4994.7,5000.7
Exp/Cntr=0.3,0.1

Type RM Length L Ch R = 1,3885,47,47,47
BEGIN DESCRIPTION:
UNT01729 IN SAND CR 3.0
END DESCRIPTION:
XS GIS Cut Line= 5
      3550242.16     10538782.18      3550460.92     10539101.22
      3550529.93     10539137.68      3550877.59     10539187.16
      3551134.12     10539194.97
#Sta/Elev= 30
  4569.3  432.20  4618.3  430.54  4755.7  423.23  4878.2  412.98  4899.2  409.50
  4971.1  407.64  4980.1  406.81  4987.5  404.25  4993.1  405.37  4999.7  403.72
  5002.5  403.22  5005.7  403.72  5009.5  403.88  5015.1  406.22  5025.3  405.70
  5034.2  407.96  5046.5  407.39  5127.3  409.05  5187.9  409.11  5256.3  411.21
  5258.5  411.32  5307.4  414.30  5312.4  413.81  5339.4  415.79  5378.2  416.96
  5383.3  418.05  5449.9  420.89  5509.9  421.99  5590.0  425.69  5642.0  429.26
#Mann=5,-1,0
  4569.3    0.05       0  4999.7   0.035       0  5005.7    0.05       0
  5256.3     0.1       0  5258.5    0.05       0
Bank Sta=4999.7,5005.7
Exp/Cntr=0.3,0.1

Type RM Length L Ch R = 1,3838,63,63,63
BEGIN DESCRIPTION:
UNT01729 IN SAND CR 3.3
END DESCRIPTION:
XS GIS Cut Line= 6
      3550061.78     10538974.18      3550254.49     10539144.59
      3550517.50     10539159.07      3550681.56     10539194.23
      3550840.42     10539217.67      3551151.60     10539225.48
#Sta/Elev= 30
  4528.4  423.24  4548.0  419.71  4568.9  418.82  4668.5  417.52  4682.7  418.40
  4711.2  418.13  4746.3  415.48  4813.3  413.66  4833.3  411.12  4863.4  409.52
  4983.6  405.71  5003.7  403.60  5006.5  403.10  5009.7  403.60  5013.6  405.62
  5048.9  407.85  5082.3  408.48  5087.4  407.45  5176.0  409.84  5181.1  408.71
  5233.0  411.16  5257.3  410.86  5319.2  413.49  5367.2  417.29  5372.2  416.20
  5399.1  419.16  5479.1  420.78  5509.2  420.45  5539.2  422.81  5688.7  430.60
#Mann=5,-1,0
  4528.4    0.05       0  5003.7   0.035       0  5009.7    0.05       0
  5257.3     0.1       0  5319.2    0.05       0
Bank Sta=5003.7,5009.7
Exp/Cntr=0.3,0.1

Type RM Length L Ch R = 1,3775,503,503,503
BEGIN DESCRIPTION:
UNT01729 IN SAND CR 3.2
END DESCRIPTION:
XS GIS Cut Line= 6
      3550030.49     10538997.59      3550238.86     10539169.49
      3550376.88     10539174.70      3550483.65     10539212.46
      3550853.44     10539228.08      3551135.96     10539242.40
#Sta/Elev= 30
  4551.0  419.76  4562.4  419.46  4568.9  417.56  4597.6  415.99  4611.9  416.79
  4675.7  415.34  4690.1  416.24  4753.9  414.23  4796.9  414.41  4820.0  411.69
  4844.4  411.78  4959.2  406.92  4986.0  405.06  4995.5  402.42  4998.2  401.92
  5001.5  402.42  5017.8  405.06  5055.0  406.69  5069.0  405.69  5161.0  406.53
  5211.1  408.21  5231.1  409.77  5241.1  412.78  5251.1  414.44  5291.1  410.96
  5384.7  414.13  5439.4  418.93  5541.4  421.09  5561.4  420.69  5725.5  429.80
#Mann=5,-1,0
  4551.0    0.05       0  4995.5   0.035       0  5001.5    0.05       0
  5291.1     0.1       0  5384.7    0.05       0
Bank Sta=4995.5,5001.5
Exp/Cntr=0.3,0.1

Type RM Length L Ch R = 1,3272,838,838,838
BEGIN DESCRIPTION:
UNT01729 IN SAND CR 2.0
END DESCRIPTION:
XS GIS Cut Line= 4
      3549823.75     10538844.25      3549919.23     10539378.10
      3550292.50     10539642.85      3550622.34     10539855.52
#Sta/Elev= 30
  4263.9  424.52  4338.6  419.35  4456.3  412.73  4474.6  410.09  4505.1  407.94
  4510.1  407.13  4545.7  405.90  4563.9  406.17  4569.0  407.53  4606.6  406.32
  4627.9  407.05  4647.3  404.41  4676.6  403.60  4681.7  404.03  4735.5  401.76
  4796.7  400.04  4799.4  399.54  4802.7  400.04  4990.7  401.76  5018.2  401.71
  5047.2  400.77  5091.6  401.41  5118.6  400.68  5154.3  400.68  5198.6  403.21
  5266.6  405.52  5406.2  414.06  5501.3  418.74  5602.7  421.96  5656.3  422.47
#Mann=3,-1,0
  4263.9    0.05       0  4796.7    0.03       0  4802.7    0.05       0
Bank Sta=4796.7,4802.7
Exp/Cntr=0.3,0.1

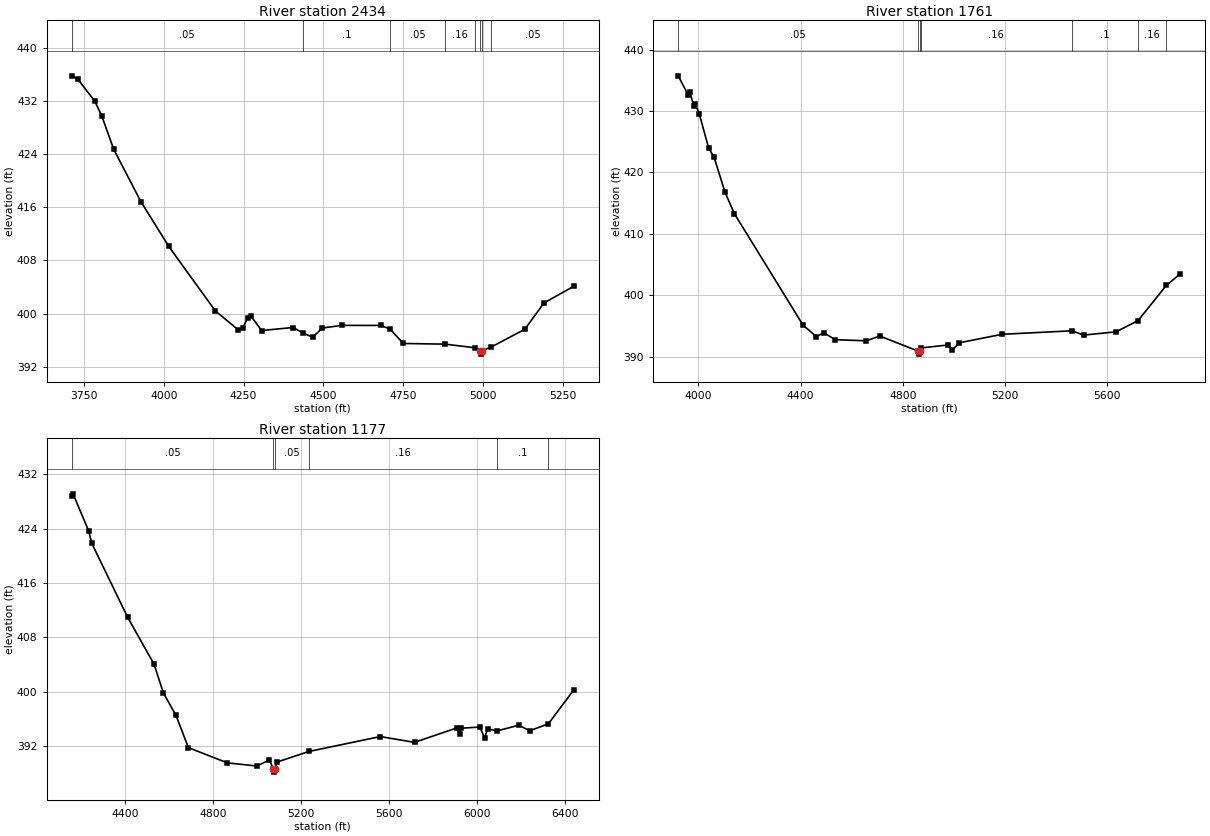
Type RM Length L Ch R = 1,2434,673,673,673
BEGIN DESCRIPTION:
UNT01729 IN SAND CR 1.0
END DESCRIPTION:
XS GIS Cut Line= 3
      3549650.14     10538718.37      3549462.64     10539780.87
      3549642.10     10540241.63
#Sta/Elev= 30
  3711.7  435.75  3729.7  435.30  3783.9  431.94  3806.4  429.64  3843.1  424.71
  3928.3  416.85  4015.7  410.11  4161.8  400.42  4232.9  397.60  4247.6  397.84
  4263.4  399.42  4273.5  399.62  4306.8  397.48  4405.5  397.93  4435.2  397.13
  4466.5  396.46  4496.9  397.85  4557.8  398.25  4679.7  398.24  4708.6  397.72
  4750.8  395.53  4881.6  395.43  4976.7  394.88  4989.9  394.43  4992.6  393.93
  4995.9  394.43  5026.1  394.99  5131.5  397.67  5191.3  401.61  5285.1  404.13
#Mann=8,-1,0
  3711.7    0.05       0  4435.2     0.1       0  4708.6    0.05       0
  4881.6    0.16       0  4976.7     0.1       0  4989.9    0.07       0
  4995.9     0.1       0  5026.1    0.05       0
Bank Sta=4989.9,4995.9
Exp/Cntr=0.3,0.1

Type RM Length L Ch R = 1,1761,584,584,584
BEGIN DESCRIPTION:
UNT01729 IN SAND CR 1.1
END DESCRIPTION:
XS GIS Cut Line= 3
      3549599.25     10538715.54      3549000.27     10539696.49
      3549598.20     10540251.09
#Sta/Elev= 30
  3920.8  435.74  3960.3  432.57  3966.1  433.13  3981.6  430.82  3987.4  431.13
  4002.9  429.58  4039.7  424.01  4061.0  422.48  4103.7  416.81  4140.4  413.30
  4409.4  395.13  4461.6  393.27  4490.4  393.91  4535.2  392.77  4657.2  392.59
  4709.4  393.37  4859.3  390.92  4862.0  390.42  4865.3  390.92  4869.3  391.42
  4978.4  391.92  4993.9  391.11  5021.1  392.27  5188.3  393.65  5461.5  394.22
  5506.9  393.52  5633.9  394.05  5720.3  395.88  5831.4  401.63  5885.7  403.50
#Mann=7,-1,0
  3920.8    0.05       0  4859.3    0.07       0  4865.3    0.05       0
  4869.3    0.16       0  5461.5     0.1       0  5720.3    0.16       0
  5831.4    0.05       0
Bank Sta=4859.3,4865.3
Exp/Cntr=0.3,0.1

Type RM Length L Ch R = 1,1177,0,0,0
BEGIN DESCRIPTION:
UNT01729 IN SAND CR 1.2
END DESCRIPTION:
XS GIS Cut Line= 4
      3549534.15     10538585.35      3548831.00     10539227.74
      3548804.96     10539548.92      3549525.47     10540252.06
#Sta/Elev= 30
  4159.2  428.78  4164.9  429.11  4235.9  423.67  4250.0  421.84  4412.9  410.96
  4533.1  404.04  4575.7  399.81  4632.4  396.54  4689.2  391.77  4866.2  389.53
  5000.6  389.07  5056.7  389.94  5075.3  388.67  5078.0  388.17  5081.3  388.67
  5092.5  389.66  5236.9  391.21  5561.0  393.40  5716.6  392.55  5907.5  394.66
  5921.6  393.78  5928.8  394.63  6013.7  394.80  6034.8  393.22  6049.0  394.53
  6092.0  394.24  6190.4  395.07  6240.0  394.26  6324.6  395.27  6440.6  400.28
#Mann=6,-1,0
  4159.2    0.05       0  5075.3    0.03       0  5081.3    0.05       0
  5236.9    0.16       0  6092.0     0.1       0  6324.6    0.16       0
Bank Sta=5075.3,5081.3
Exp/Cntr=0.3,0.1

Chan Stop Cuts=-1