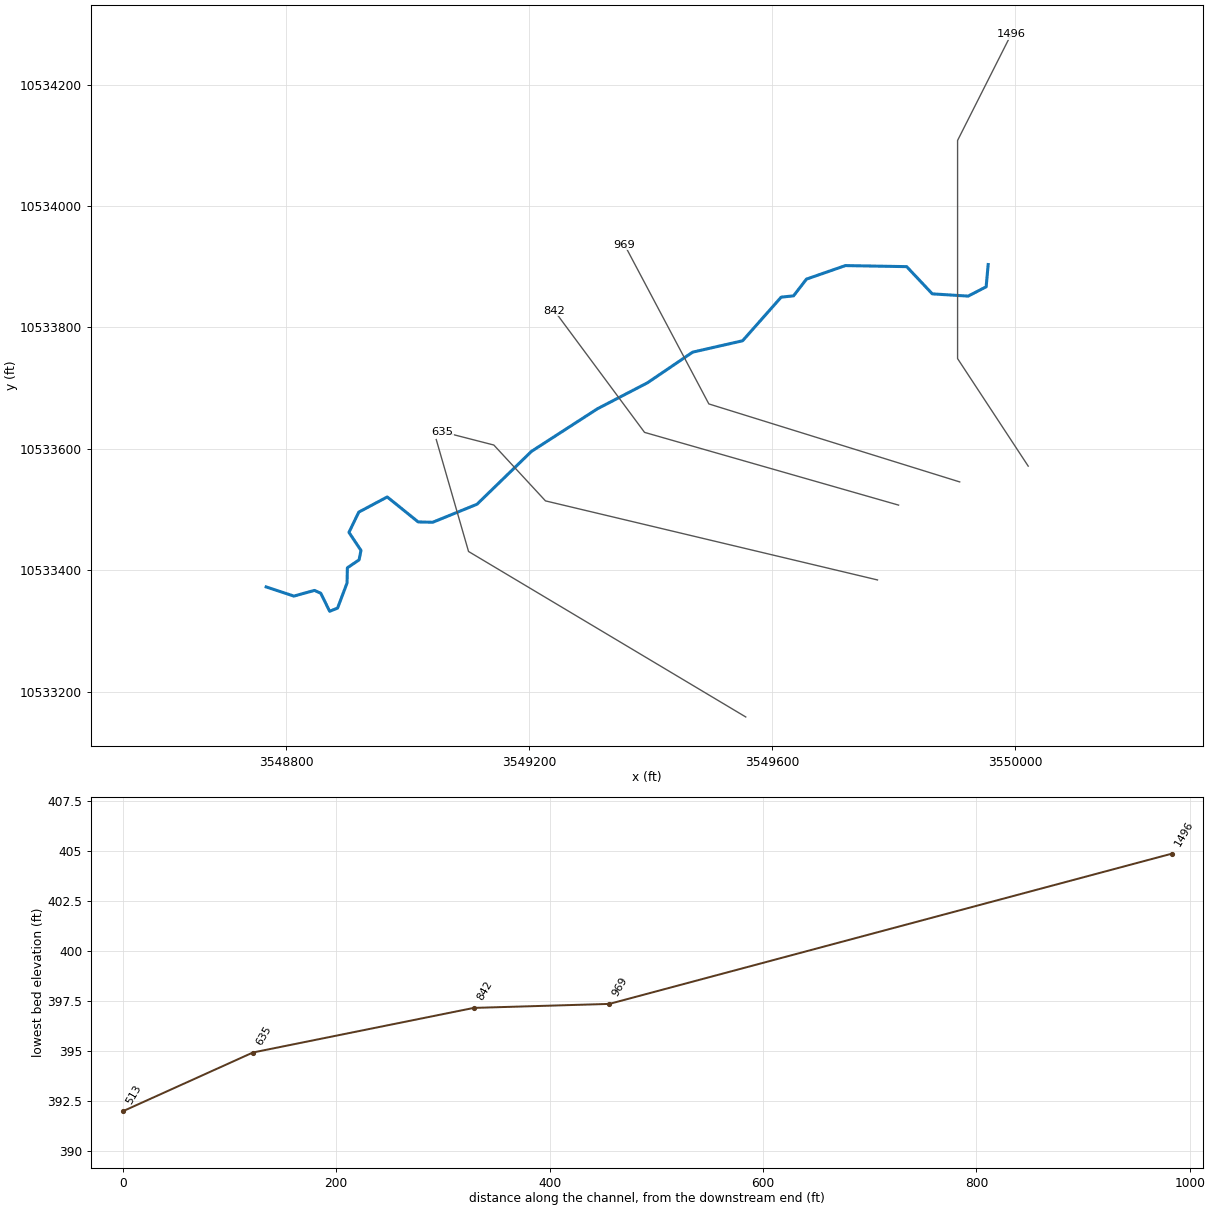
--- UNT01732 IN SAND CR.prj (project) ---

Proj Title=UNT01732 IN SAND CR Base Level Engineering
Current Plan=p01
Default Exp/Contr=0.3,0.1
English Units
Geom File=g01
Flow File=f01
Plan File=p01
BEGIN DESCRIPTION:
UNT01732 IN SAND CR
END DESCRIPTION:

--- UNT01732 IN SAND CR.p01 (plan) ---

Plan Title=Multiple Run
Short Identifier=Multiple
Geom File=g01
Flow File=f01
Subcritical Flow
K Sum by GR= 0
Std Step Tol= 0.01
Critical Tol= 0.01
Num of Std Step Trials= 20
Max Error Tol= 0.3
Flow Tol Ratio= 0.001
Split Flow NTrial= 30
Split Flow Tol= 0.02
Split Flow Ratio= 0.02
Log Output Level= 0
Friction Slope Method= 1
Unsteady Friction Slope Method= 2
Unsteady Bridges Friction Slope Method= 1
Parabolic Critical Depth
Global Vel Dist=  1 , 1 , 1
Global Log Level= 0
CheckData=True
Encroach Param= -1, 0, 0, 0
BEGIN DESCRIPTION:
Multiple Run
END DESCRIPTION:

--- UNT01732 IN SAND CR.f01 (steady flow) ---

Flow Title=Multiple
Number of Profiles=7
Profile Names=10-year,25-year,50-year,1pct_min,100-year,1pct_plu,500-year
River Rch & RM= UNT01732 IN SAND,Reach-1,1496
     469     616     732     638     863    1167    1192
Boundary for River Rch & Prof#=UNT01732 IN SAND,Reach-1,1
Up Type=0
Dn Type=3
Dn Slope=0.005
Boundary for River Rch & Prof#=UNT01732 IN SAND,Reach-1,2
Up Type=0
Dn Type=3
Dn Slope=0.005
Boundary for River Rch & Prof#=UNT01732 IN SAND,Reach-1,3
Up Type=0
Dn Type=3
Dn Slope=0.005
Boundary for River Rch & Prof#=UNT01732 IN SAND,Reach-1,4
Up Type=0
Dn Type=3
Dn Slope=0.005
Boundary for River Rch & Prof#=UNT01732 IN SAND,Reach-1,5
Up Type=0
Dn Type=3
Dn Slope=0.005
Boundary for River Rch & Prof#=UNT01732 IN SAND,Reach-1,6
Up Type=0
Dn Type=3
Dn Slope=0.005
Boundary for River Rch & Prof#=UNT01732 IN SAND,Reach-1,7
Up Type=0
Dn Type=3
Dn Slope=0.005

--- UNT01732 IN SAND CR.g01 (geometry) ---

Geom Title=Existing Conditions

River Reach=UNT01732 IN SAND,Reach-1
Reach XY= 30
      3549955.89     10533903.67      3549952.57     10533866.99
      3549922.93     10533851.68      3549863.86     10533855.36
      3549821.64     10533900.21      3549720.74     10533901.95
      3549656.62     10533879.67      3549635.27     10533852.07
      3549614.95     10533849.98      3549551.41     10533778.11
      3549469.12     10533759.36      3549394.64     10533708.84
      3549312.35     10533666.13      3549203.50     10533595.82
      3549113.91     10533508.84      3549041.00     10533479.15
      3549017.04     10533479.67      3548966.00     10533520.82
      3548919.12     10533495.82      3548902.97     10533462.48
      3548922.77     10533432.80      3548919.64     10533417.17
      3548900.37     10533404.15      3548899.85     10533379.15
      3548884.22     10533337.74      3548871.14     10533332.54
      3548856.56     10533362.22      3548846.14     10533366.91
      3548812.28     10533357.54      3548766.57     10533372.65

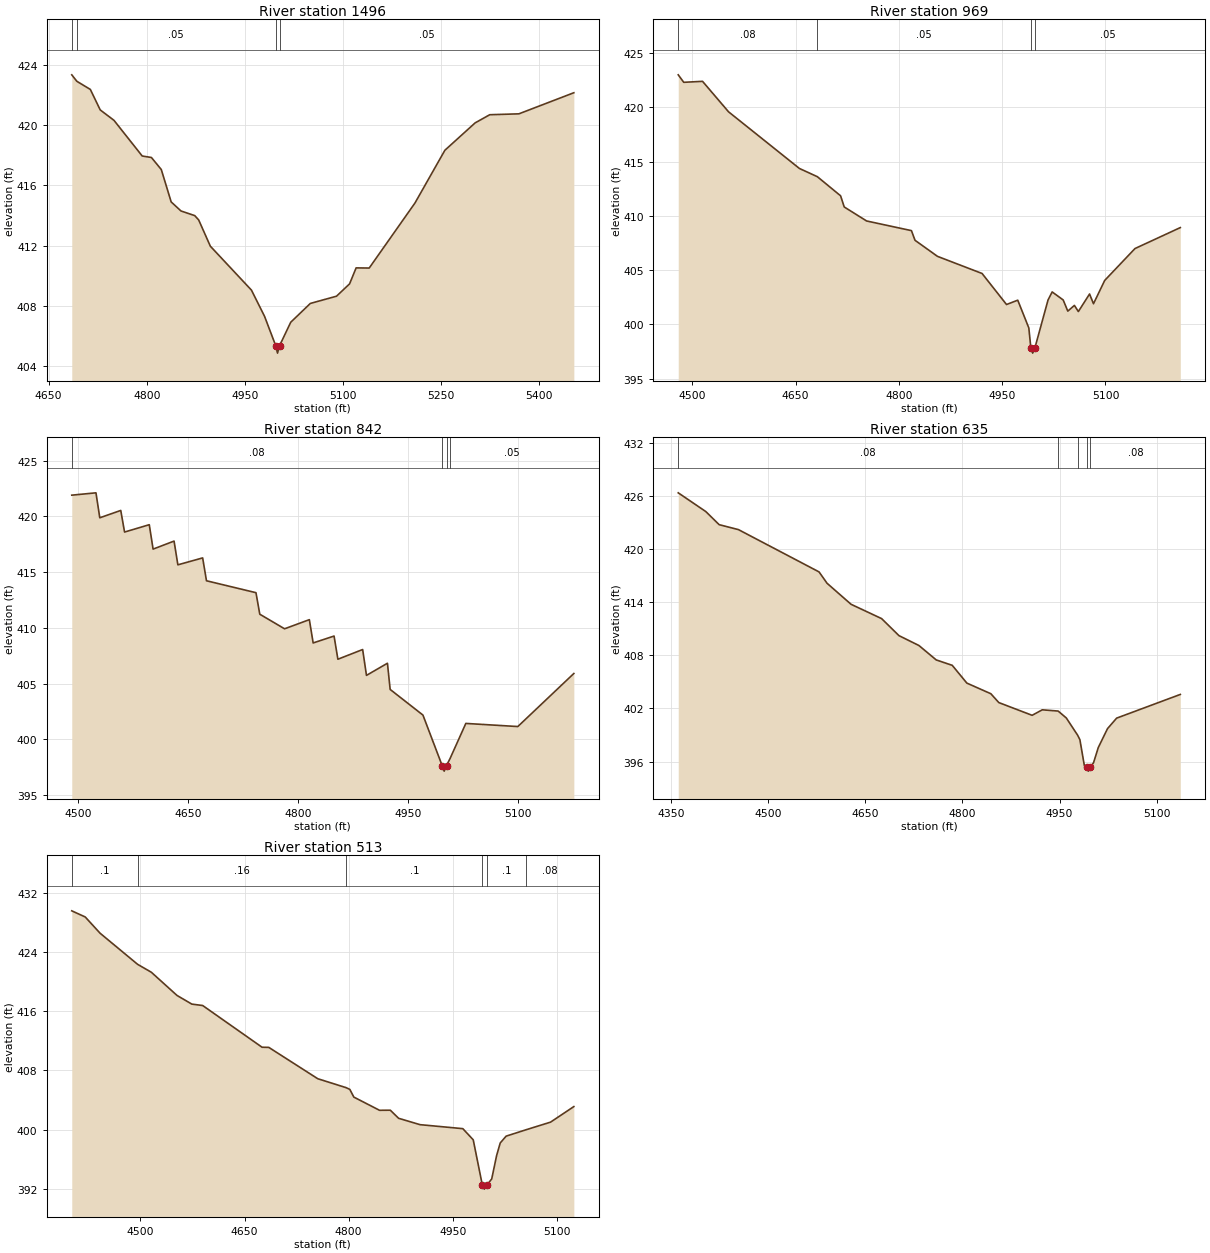
Type RM Length L Ch R = 1,1496,527,527,527
BEGIN DESCRIPTION:
UNT01732 IN SAND CR 3.0
END DESCRIPTION:
XS GIS Cut Line= 4
      3550021.84     10533571.62      3549905.51     10533748.72
      3549905.51     10534108.10      3549994.05     10534283.44
#Sta/Elev= 30
  4685.4  423.34  4693.2  422.91  4713.8  422.37  4728.9  421.01  4749.9  420.32
  4793.1  417.95  4807.2  417.85  4822.3  417.05  4837.4  414.90  4852.4  414.30
  4873.5  413.99  4879.5  413.70  4897.3  411.96  4960.2  409.04  4980.2  407.30
  4997.2  405.36  5000.0  404.86  5003.2  405.36  5020.2  406.91  5050.2  408.16
  5090.2  408.64  5110.2  409.46  5120.2  410.52  5140.2  410.51  5210.2  414.83
  5255.9  418.33  5302.2  420.15  5324.5  420.69  5369.1  420.75  5453.1  422.15
#Mann=4,-1,0
  4685.4    0.08       0  4693.2    0.05       0  4997.2    0.03       0
  5003.2    0.05       0
Bank Sta=4997.2,5003.2
Exp/Cntr=0.3,0.1

Type RM Length L Ch R = 1,969,127,127,127
BEGIN DESCRIPTION:
UNT01732 IN SAND CR 2.0
END DESCRIPTION:
XS GIS Cut Line= 3
      3549908.99     10533545.60      3549495.79     10533674.07
      3549356.98     10533936.06
#Sta/Elev= 30
  4479.5  423.00  4487.5  422.31  4514.8  422.40  4552.6  419.59  4655.5  414.37
  4681.6  413.61  4715.3  411.85  4720.6  410.82  4753.1  409.53  4818.2  408.64
  4823.4  407.75  4856.0  406.27  4920.8  404.69  4956.3  401.83  4972.6  402.23
  4988.7  399.67  4991.6  397.85  4994.3  397.35  4997.6  397.85  5016.6  402.25
  5022.6  402.99  5038.6  402.25  5045.3  401.22  5054.9  401.75  5060.6  401.18
  5076.9  402.80  5082.6  401.90  5098.9  404.05  5142.9  406.99  5208.7  408.92
#Mann=4,-1,0
  4479.5    0.08       0  4681.6    0.05       0  4991.6    0.03       0
  4997.6    0.05       0
Bank Sta=4991.6,4997.6
Exp/Cntr=0.3,0.1

Type RM Length L Ch R = 1,842,207,207,207
BEGIN DESCRIPTION:
UNT01732 IN SAND CR 2.1
END DESCRIPTION:
XS GIS Cut Line= 3
      3549808.29     10533507.40      3549389.88     10533627.20
      3549241.30     10533827.61
#Sta/Elev= 30
  4491.9  421.91  4524.9  422.12  4530.1  419.88  4558.7  420.54  4563.9  418.60
  4597.6  419.26  4602.8  417.07  4631.4  417.79  4636.6  415.66  4670.4  416.28
  4675.6  414.23  4743.1  413.16  4748.3  411.23  4782.1  409.92  4815.9  410.74
  4821.1  408.65  4849.6  409.27  4854.8  407.19  4888.6  408.06  4893.8  405.74
  4922.4  406.83  4926.1  404.48  4970.8  402.18  4997.0  397.65  4999.8  397.15
  5003.0  397.65  5007.8  398.28  5029.3  401.43  5100.2  401.15  5176.6  405.91
#Mann=4,-1,0
  4491.9    0.08       0  4997.0    0.07       0  5003.0    0.08       0
  5007.8    0.05       0
Bank Sta=4997,5003
Exp/Cntr=0.3,0.1

Type RM Length L Ch R = 1,635,122,122,122
BEGIN DESCRIPTION:
UNT01732 IN SAND CR 1.1
END DESCRIPTION:
XS GIS Cut Line= 4
      3549773.58     10533384.14      3549226.69     10533514.35
      3549141.62     10533606.36      3549056.77     10533628.18
#Sta/Elev= 30
  4361.3  426.38  4403.9  424.26  4424.5  422.78  4454.3  422.22  4578.7  417.44
  4591.0  416.16  4628.1  413.78  4675.3  412.16  4702.0  410.24  4732.9  409.12
  4759.6  407.49  4784.3  406.88  4806.9  404.87  4843.9  403.67  4856.2  402.67
  4907.6  401.23  4923.3  401.85  4947.8  401.71  4960.4  400.93  4977.9  398.98
  4981.4  398.47  4988.2  395.57  4991.7  395.42  4994.4  394.92  4997.7  395.42
  5002.4  395.86  5009.8  397.59  5024.0  399.72  5038.1  400.91  5136.4  403.59
#Mann=5,-1,0
  4361.3    0.08       0  4947.8    0.16       0  4977.9    0.08       0
  4991.7    0.07       0  4997.7    0.08       0
Bank Sta=4991.7,4997.7
Exp/Cntr=0.3,0.1

Type RM Length L Ch R = 1,513,0,0,0
BEGIN DESCRIPTION:
UNT01732 IN SAND CR 1.0
END DESCRIPTION:
XS GIS Cut Line= 3
      3549556.59     10533158.42      3549099.95     10533431.01
      3549046.76     10533615.38
#Sta/Elev= 30
  4401.0  429.54  4420.4  428.71  4441.8  426.52  4495.9  422.32  4515.7  421.25
  4552.7  418.12  4574.1  416.95  4589.7  416.76  4675.3  411.13  4685.0  411.11
  4755.6  406.88  4796.6  405.67  4801.8  405.44  4807.6  404.40  4844.6  402.62
  4860.2  402.63  4872.1  401.54  4903.0  400.68  4964.7  400.14  4979.7  398.63
  4992.9  392.48  4995.7  391.98  4998.9  392.48  5006.3  393.35  5013.4  396.52
  5018.6  398.21  5027.1  399.13  5056.1  400.00  5091.1  401.02  5124.7  403.12
#Mann=6,-1,0
  4401.0     0.1       0  4495.9    0.16       0  4796.6     0.1       0
  4992.9    0.07       0  4998.9     0.1       0  5056.1    0.08       0
Bank Sta=4992.9,4998.9
Exp/Cntr=0.3,0.1

Chan Stop Cuts=-1