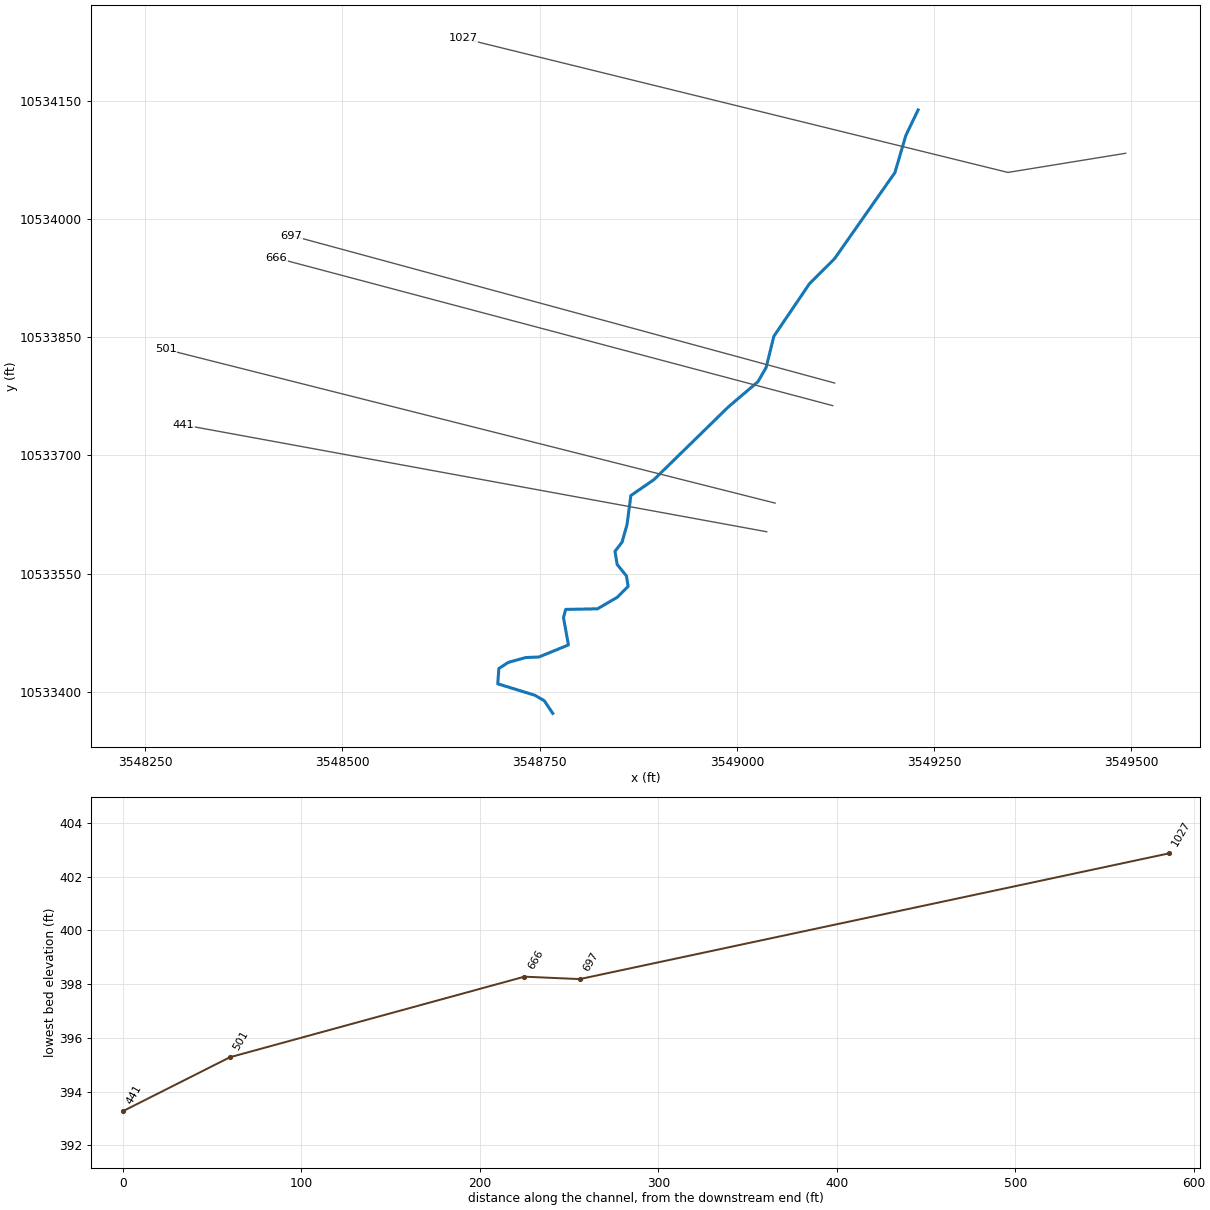
--- UNT01733 IN SAND CR.prj (project) ---

Proj Title=UNT01733 IN SAND CR Base Level Engineering
Current Plan=p01
Default Exp/Contr=0.3,0.1
English Units
Geom File=g01
Flow File=f01
Plan File=p01
Y Axis Title=Elevation
X Axis Title(PF)=Main Channel Distance
X Axis Title(XS)=Station
BEGIN DESCRIPTION:
UNT01733 IN SAND CR
END DESCRIPTION:
DSS Export Rating Curves= 0
DSS Export Rating Curve Sorted= 0
DSS Export Volume Flow Curves= 0
DXF OffsetX= 0
DXF OffsetY= 0
DXF ScaleX= 1
DXF ScaleY= 10

--- UNT01733 IN SAND CR.p01 (plan) ---

Plan Title=Multiple Run
Short Identifier=Multiple
Geom File=g01
Flow File=f01
Subcritical Flow
K Sum by GR= 0
Std Step Tol= 0.01
Critical Tol= 0.01
Num of Std Step Trials= 20
Max Error Tol= 0.3
Flow Tol Ratio= 0.001
Split Flow NTrial= 30
Split Flow Tol= 0.02
Split Flow Ratio= 0.02
Log Output Level= 0
Friction Slope Method= 1
Unsteady Friction Slope Method= 2
Unsteady Bridges Friction Slope Method= 1
Parabolic Critical Depth
Global Vel Dist=  1 , 1 , 1
Global Log Level= 0
CheckData=True
Encroach Param= -1, 0, 0, 0
BEGIN DESCRIPTION:
Multiple Run
END DESCRIPTION:

--- UNT01733 IN SAND CR.f01 (steady flow) ---

Flow Title=Multiple
Number of Profiles=7
Profile Names=10-year,25-year,50-year,1pct_min,100-year,1pct_plu,500-year
River Rch & RM= UNT01733 IN SAND,Reach-1,1027
     313     399     464     396     536     725     710
Boundary for River Rch & Prof#=UNT01733 IN SAND,Reach-1,1
Up Type=0
Dn Type=3
Dn Slope=0.005
Boundary for River Rch & Prof#=UNT01733 IN SAND,Reach-1,2
Up Type=0
Dn Type=3
Dn Slope=0.005
Boundary for River Rch & Prof#=UNT01733 IN SAND,Reach-1,3
Up Type=0
Dn Type=3
Dn Slope=0.005
Boundary for River Rch & Prof#=UNT01733 IN SAND,Reach-1,4
Up Type=0
Dn Type=3
Dn Slope=0.005
Boundary for River Rch & Prof#=UNT01733 IN SAND,Reach-1,5
Up Type=0
Dn Type=3
Dn Slope=0.005
Boundary for River Rch & Prof#=UNT01733 IN SAND,Reach-1,6
Up Type=0
Dn Type=3
Dn Slope=0.005
Boundary for River Rch & Prof#=UNT01733 IN SAND,Reach-1,7
Up Type=0
Dn Type=3
Dn Slope=0.005

--- UNT01733 IN SAND CR.g01 (geometry) ---

Geom Title=Existing Conditions
Program Version=4.10

River Reach=UNT01733 IN SAND,Reach-1
Reach XY= 30
      3549229.78     10534138.37      3549214.23       10534106.
      3549200.34     10534058.78      3549123.95     10533949.75
        3549092.     10533917.81      3549046.86     10533851.14
      3549037.14     10533811.56      3549026.73      10533793.5
      3548989.23     10533761.56      3548894.78     10533669.19
      3548865.61     10533649.06      3548860.75     10533612.25
       3548854.5     10533590.03      3548845.48     10533578.22
      3548848.25     10533561.56      3548860.06     10533546.97
      3548862.14     10533533.78      3548848.25     10533519.89
      3548823.25     10533505.31      3548782.98     10533504.61
       3548780.2     10533494.19      3548786.45     10533459.47
      3548748.95     10533444.19      3548732.28      10533443.5
      3548710.06     10533437.25      3548698.25     10533429.61
      3548696.86     10533410.17      3548744.09     10533395.58
      3548755.89     10533388.64      3548766.57     10533372.65

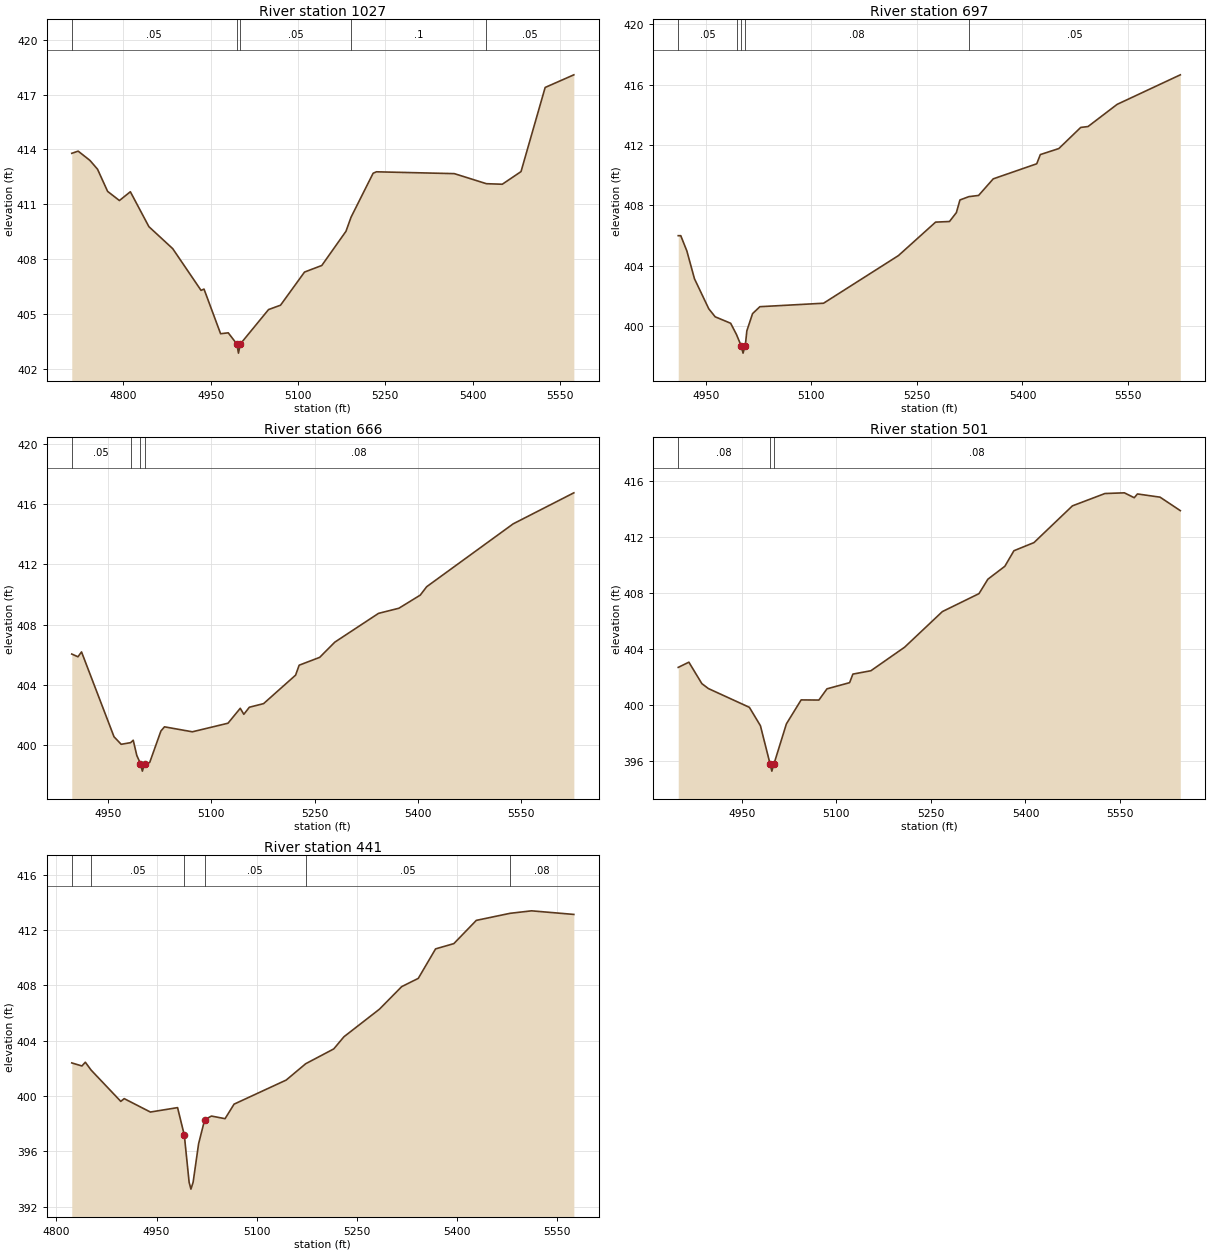
Type RM Length L Ch R = 1 ,1027    ,330,330,330
BEGIN DESCRIPTION:
UNT01733 IN SAND CR 1.2
END DESCRIPTION:
XS GIS Cut Line= 3
      3549492.95     10534083.41      3549343.66     10534059.11
      3548652.66     10534229.26
#Sta/Elev= 30
  4711.2  413.79  4722.2  413.91  4742.5   413.4  4755.5  412.92  4772.8  411.71
  4793.1  411.21  4811.9  411.69  4843.8  409.78  4884.7  408.58  4933.4   406.3
  4938.5  406.37    4967  403.93  4980.1  403.98  4994.9  403.37  4997.7  402.87
  5000.9  403.37  5049.4  405.25    5070  405.49  5111.2   407.3  5140.9  407.66
  5182.5  409.53  5191.2   410.3  5229.1   412.7  5234.8  412.78  5368.7  412.68
  5423.8  412.13  5451.1   412.1  5483.3  412.79  5524.8  417.39  5574.1  418.08
#Mann= 5 ,-1 , 0
  4711.2     .05       0  4994.9     .03       0  5000.9     .05       0
  5191.2      .1       0  5423.8     .05       0
Bank Sta=4994.9,5000.9
XS Rating Curve= 0 ,0
Exp/Cntr=0.3,0.1

Type RM Length L Ch R = 1 ,697     ,31,31,31
BEGIN DESCRIPTION:
UNT01733 IN SAND CR 2.0
END DESCRIPTION:
XS GIS Cut Line= 2
      3549124.02     10533791.83      3548435.58     10533978.88
#Sta/Elev= 30
  4910.9  405.98  4914.5  405.98  4923.2  404.96    4934  403.12  4954.3  401.13
  4963.4   400.6  4985.4  400.17  4993.7  399.42  5000.2  398.69    5003  398.19
  5006.2  398.69  5008.4  399.67  5016.5  400.81  5026.9  401.27  5117.4   401.5
  5223.8  404.66  5276.6  406.88  5296.3  406.92  5306.1  407.51  5311.2  408.35
  5323.9  408.57  5337.7  408.65  5358.5  409.75  5420.3  410.75  5425.4  411.36
  5451.7  411.76  5482.8  413.16  5493.2  413.22  5534.5  414.69  5624.3  416.65
#Mann= 5 ,-1 , 0
  4910.9     .05       0  4993.7     .08       0  5000.2     .07       0
  5006.2     .08       0  5323.9     .05       0
Bank Sta=5000.2,5006.2
XS Rating Curve= 0 ,0
Exp/Cntr=0.3,0.1

Type RM Length L Ch R = 1 ,666     ,165,165,165
BEGIN DESCRIPTION:
UNT01733 IN SAND CR 3.0
END DESCRIPTION:
XS GIS Cut Line= 2
      3549121.47     10533763.17      3548416.42     10533950.49
#Sta/Elev= 30
  4897.2  406.05  4906.2  405.87  4911.4  406.19  4958.6  400.56    4969  400.06
  4982.7  400.17  4986.5  400.33  4991.7  399.32    4997  398.78  4999.8  398.28
    5003  398.78  5010.4  398.85  5026.7  400.94  5031.9  401.22  5072.4  400.89
  5124.2  401.46    5142  402.45  5147.2  402.05  5155.2  402.52  5175.9  402.76
  5222.4  404.65  5227.6  405.31  5257.4  405.83  5279.4  406.84  5342.9  408.75
  5372.5  409.09  5403.5  409.96  5412.9  410.52  5538.5  414.69  5626.7  416.75
#Mann= 4 ,-1 , 0
  4897.2     .05       0  4982.7     .08       0    4997     .07       0
    5003     .08       0
Bank Sta=4997,5003
XS Rating Curve= 0 ,0
Exp/Cntr=0.3,0.1

Type RM Length L Ch R = 1 ,501     ,60,60,60
BEGIN DESCRIPTION:
UNT01733 IN SAND CR 4.0
END DESCRIPTION:
XS GIS Cut Line= 2
      3549048.49     10533639.49      3548276.14     10533834.53
#Sta/Elev= 30
  4849.1  402.68    4866  403.05  4886.6  401.52  4896.9  401.17    4962  399.83
  4979.5  398.52  4994.9  395.78  4997.6  395.28  5000.9  395.78  5020.7  398.65
  5044.1  400.36  5072.3  400.35  5085.1  401.15    5121  401.59  5126.2   402.2
  5154.8  402.44  5208.3  404.12  5268.2  406.66  5326.3  407.94  5340.4  408.97
  5367.3  409.89  5381.7     411  5413.5  411.58  5474.5   414.2  5526.1  415.08
    5557  415.13  5572.6  414.78  5577.7  415.05  5613.6  414.82  5645.7  413.86
#Mann= 3 ,-1 , 0
  4849.1     .08       0  4994.9     .07       0  5000.9     .08       0
Bank Sta=4994.9,5000.9
XS Rating Curve= 0 ,0
Exp/Cntr=0.3,0.1

Type RM Length L Ch R = 1 ,441     ,0,0,0
BEGIN DESCRIPTION:
UNT01733 IN SAND CR 5.0
END DESCRIPTION:
XS GIS Cut Line= 2
      3549037.86     10533603.14      3548298.49     10533738.72
#Sta/Elev= 30
    4823  402.39  4838.2  402.17  4843.3  402.44    4852  401.87  4896.4  399.61
  4901.5  399.81  4940.7  398.84  4981.4  399.16  4991.5  397.17  4998.7  393.77
  5001.4  393.27  5004.7  393.77  5012.9  396.55    5022  398.29  5032.2  398.55
  5052.5  398.36    5066  399.41    5144  401.15  5173.2  402.33  5215.2   403.4
  5230.5  404.28  5283.6  406.27  5316.9   407.9  5341.8   408.5  5367.7  410.63
    5395  411.01  5428.7  412.69  5479.2   413.2  5511.4  413.38  5574.7  413.12
#Mann= 6 ,-1 , 0
    4823     .08       0    4852     .05       0  4991.5    .035       0
    5022     .05       0  5173.2     .05       0  5479.2     .08       0
Bank Sta=4991.5,5022
XS Rating Curve= 0 ,0
Exp/Cntr=0.3,0.1

Chan Stop Cuts=-1
Use User Specified Reach Order=0
Composite Channel Slope=5