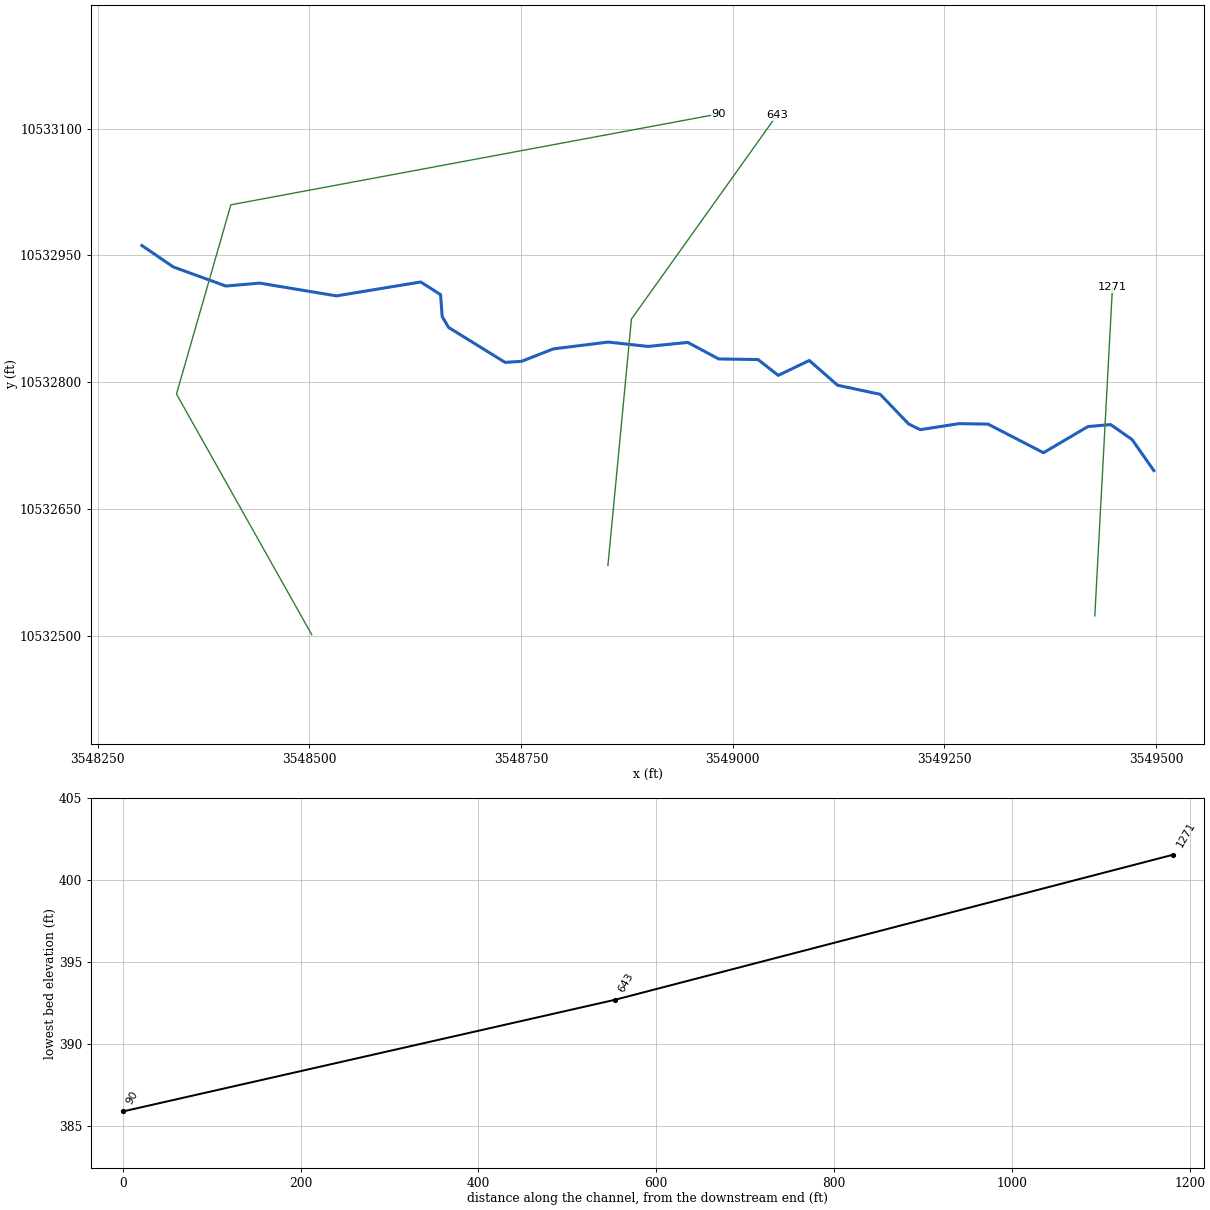
--- UNT01734 IN SAND CR.prj (project) ---

Proj Title=UNT01734 IN SAND CR Base Level Engineering
Current Plan=p01
Default Exp/Contr=0.3,0.1
English Units
Geom File=g01
Flow File=f01
Plan File=p01
BEGIN DESCRIPTION:
UNT01734 IN SAND CR
END DESCRIPTION:

--- UNT01734 IN SAND CR.p01 (plan) ---

Plan Title=Multiple Run
Short Identifier=Multiple
Geom File=g01
Flow File=f01
Subcritical Flow
K Sum by GR= 0
Std Step Tol= 0.01
Critical Tol= 0.01
Num of Std Step Trials= 20
Max Error Tol= 0.3
Flow Tol Ratio= 0.001
Split Flow NTrial= 30
Split Flow Tol= 0.02
Split Flow Ratio= 0.02
Log Output Level= 0
Friction Slope Method= 1
Unsteady Friction Slope Method= 2
Unsteady Bridges Friction Slope Method= 1
Parabolic Critical Depth
Global Vel Dist=  1 , 1 , 1
Global Log Level= 0
CheckData=True
Encroach Param= -1, 0, 0, 0
BEGIN DESCRIPTION:
Multiple Run
END DESCRIPTION:

--- UNT01734 IN SAND CR.f01 (steady flow) ---

Flow Title=Multiple
Number of Profiles=7
Profile Names=10-year,25-year,50-year,1pct_min,100-year,1pct_plu,500-year
River Rch & RM= UNT01734 IN SAND,Reach-1,1271
     310     398     465     400     541     732     727
Boundary for River Rch & Prof#=UNT01734 IN SAND,Reach-1,1
Up Type=0
Dn Type=3
Dn Slope=0.005
Boundary for River Rch & Prof#=UNT01734 IN SAND,Reach-1,2
Up Type=0
Dn Type=3
Dn Slope=0.005
Boundary for River Rch & Prof#=UNT01734 IN SAND,Reach-1,3
Up Type=0
Dn Type=3
Dn Slope=0.005
Boundary for River Rch & Prof#=UNT01734 IN SAND,Reach-1,4
Up Type=0
Dn Type=3
Dn Slope=0.005
Boundary for River Rch & Prof#=UNT01734 IN SAND,Reach-1,5
Up Type=0
Dn Type=3
Dn Slope=0.005
Boundary for River Rch & Prof#=UNT01734 IN SAND,Reach-1,6
Up Type=0
Dn Type=3
Dn Slope=0.005
Boundary for River Rch & Prof#=UNT01734 IN SAND,Reach-1,7
Up Type=0
Dn Type=3
Dn Slope=0.005

--- UNT01734 IN SAND CR.g01 (geometry) ---

Geom Title=Existing Conditions

River Reach=UNT01734 IN SAND,Reach-1
Reach XY= 30
      3549497.42     10532695.24      3549471.69     10532732.05
      3549446.36     10532749.72      3549419.52     10532747.33
      3549367.09     10532716.40      3549301.50     10532750.26
      3549267.39     10532750.82      3549221.45     10532743.68
      3549207.81     10532750.42      3549174.27     10532785.50
      3549123.86     10532796.28      3549090.42     10532825.56
      3549053.79     10532807.94      3549029.85     10532826.70
      3548983.41     10532827.38      3548946.96     10532846.97
      3548899.92     10532842.19      3548852.82     10532847.37
      3548787.98     10532839.26      3548750.59     10532824.58
      3548731.11     10532823.32      3548664.41     10532864.66
      3548656.85     10532877.48      3548654.91     10532903.54
      3548631.47     10532918.47      3548531.97     10532902.05
      3548441.33     10532917.14      3548401.25     10532913.70
      3548339.26     10532936.26      3548302.11     10532961.64

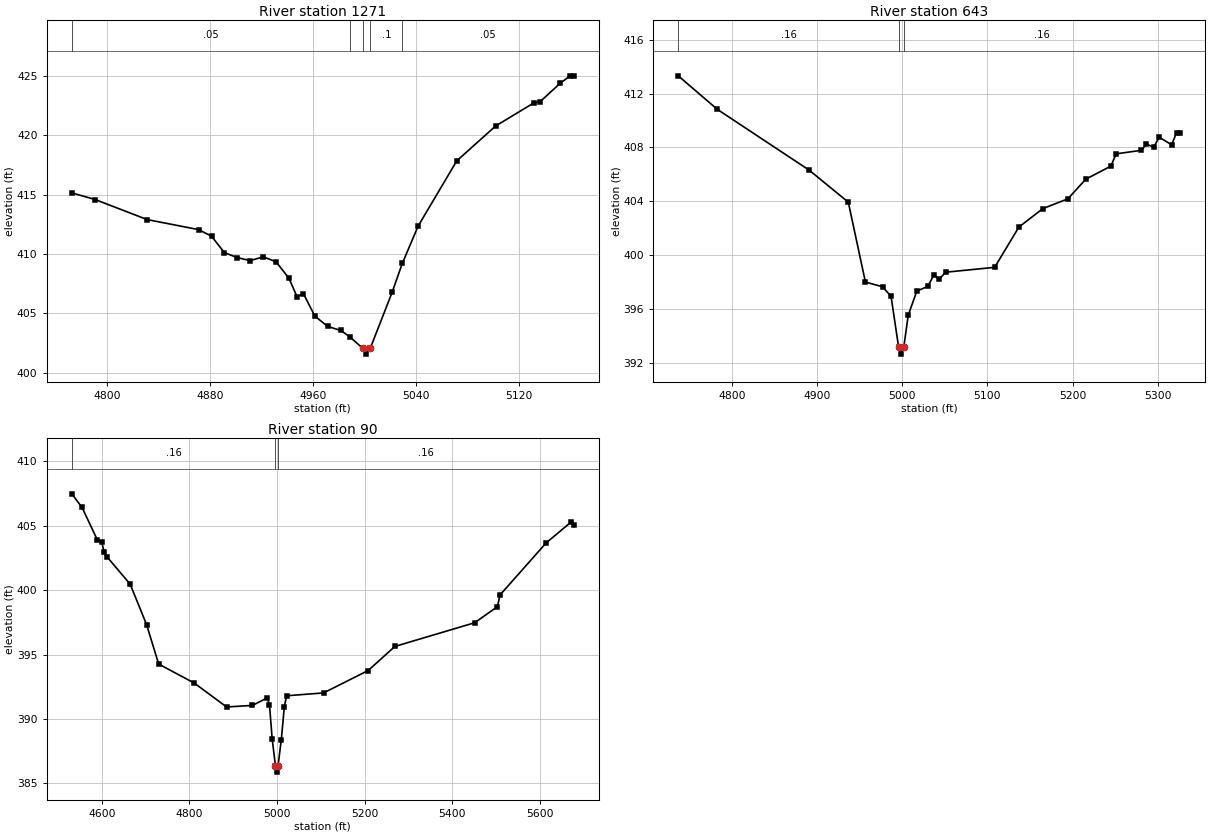
Type RM Length L Ch R = 1,1271,628,628,628
BEGIN DESCRIPTION:
UNT01734 IN SAND CR 2.0
END DESCRIPTION:
XS GIS Cut Line= 2
      3549427.70     10532523.36      3549448.54     10532912.30
#Sta/Elev= 30
  4772.9  415.15  4791.2  414.58  4831.3  412.90  4871.3  412.05  4881.3  411.50
  4891.3  410.11  4901.4  409.69  4911.4  409.44  4921.4  409.76  4931.4  409.34
  4941.4  407.95  4947.6  406.41  4952.6  406.66  4961.5  404.76  4971.5  403.89
  4981.5  403.56  4988.6  403.02  4998.5  402.06  5001.3  401.56  5004.5  402.06
  5021.5  406.79  5029.3  409.20  5041.6  412.35  5071.6  417.85  5101.7  420.78
  5131.2  422.72  5136.2  422.83  5151.7  424.37  5159.5  425.01  5162.4  425.01
#Mann=5,-1,0
  4772.9    0.05       0  4988.6     0.1       0  4998.5    0.07       0
  5004.5     0.1       0  5029.3    0.05       0
Bank Sta=4998.5,5004.5
Exp/Cntr=0.3,0.1

Type RM Length L Ch R = 1,643,553,553,553
BEGIN DESCRIPTION:
UNT01734 IN SAND CR 1.0
END DESCRIPTION:
XS GIS Cut Line= 3
      3548852.59     10532582.94      3548880.37     10532874.63
      3549052.25     10533115.96
#Sta/Elev= 30
  4737.1  413.31  4782.9  410.83  4890.8  406.32  4936.7  403.95  4956.8  398.03
  4976.9  397.68  4986.9  396.97  4995.8  393.19  4998.6  392.69  5001.8  393.19
  5007.0  395.56  5017.1  397.36  5030.1  397.71  5037.2  398.57  5043.3  398.24
  5051.0  398.76  5108.5  399.12  5136.9  402.10  5165.0  403.47  5194.5  404.20
  5215.4  405.65  5244.9  406.62  5251.1  407.53  5280.6  407.79  5286.7  408.24
  5295.3  408.03  5301.5  408.77  5316.2  408.20  5322.0  409.09  5326.4  409.09
#Mann=3,-1,0
  4737.1    0.16       0  4995.8    0.07       0  5001.8    0.16       0
Bank Sta=4995.8,5001.8
Exp/Cntr=0.3,0.1

Type RM Length L Ch R = 1,90,0,0,0
BEGIN DESCRIPTION:
UNT01734 IN SAND CR 1.1
END DESCRIPTION:
XS GIS Cut Line= 4
      3548502.72     10532501.10      3548342.97     10532785.86
      3548407.21     10533009.82      3548983.56     10533117.45
#Sta/Elev= 30
  4531.6  407.48  4555.1  406.42  4589.6  403.93  4599.8  403.77  4605.6  402.94
  4612.5  402.57  4664.9  400.46  4702.5  397.31  4729.9  394.26  4811.0  392.79
  4884.9  390.93  4943.9  391.05  4977.6  391.63  4982.8  391.10  4989.0  388.43
  4996.4  386.37  4999.1  385.87  5002.4  386.37  5009.8  388.40  5016.6  390.91
  5021.8  391.80  5106.2  392.02  5208.0  393.76  5269.0  395.63  5451.1  397.47
  5503.0  398.72  5508.8  399.62  5614.2  403.67  5671.9  405.31  5677.4  405.03
#Mann=3,-1,0
  4531.6    0.16       0  4996.4    0.07       0  5002.4    0.16       0
Bank Sta=4996.4,5002.4
Exp/Cntr=0.3,0.1

Chan Stop Cuts=-1