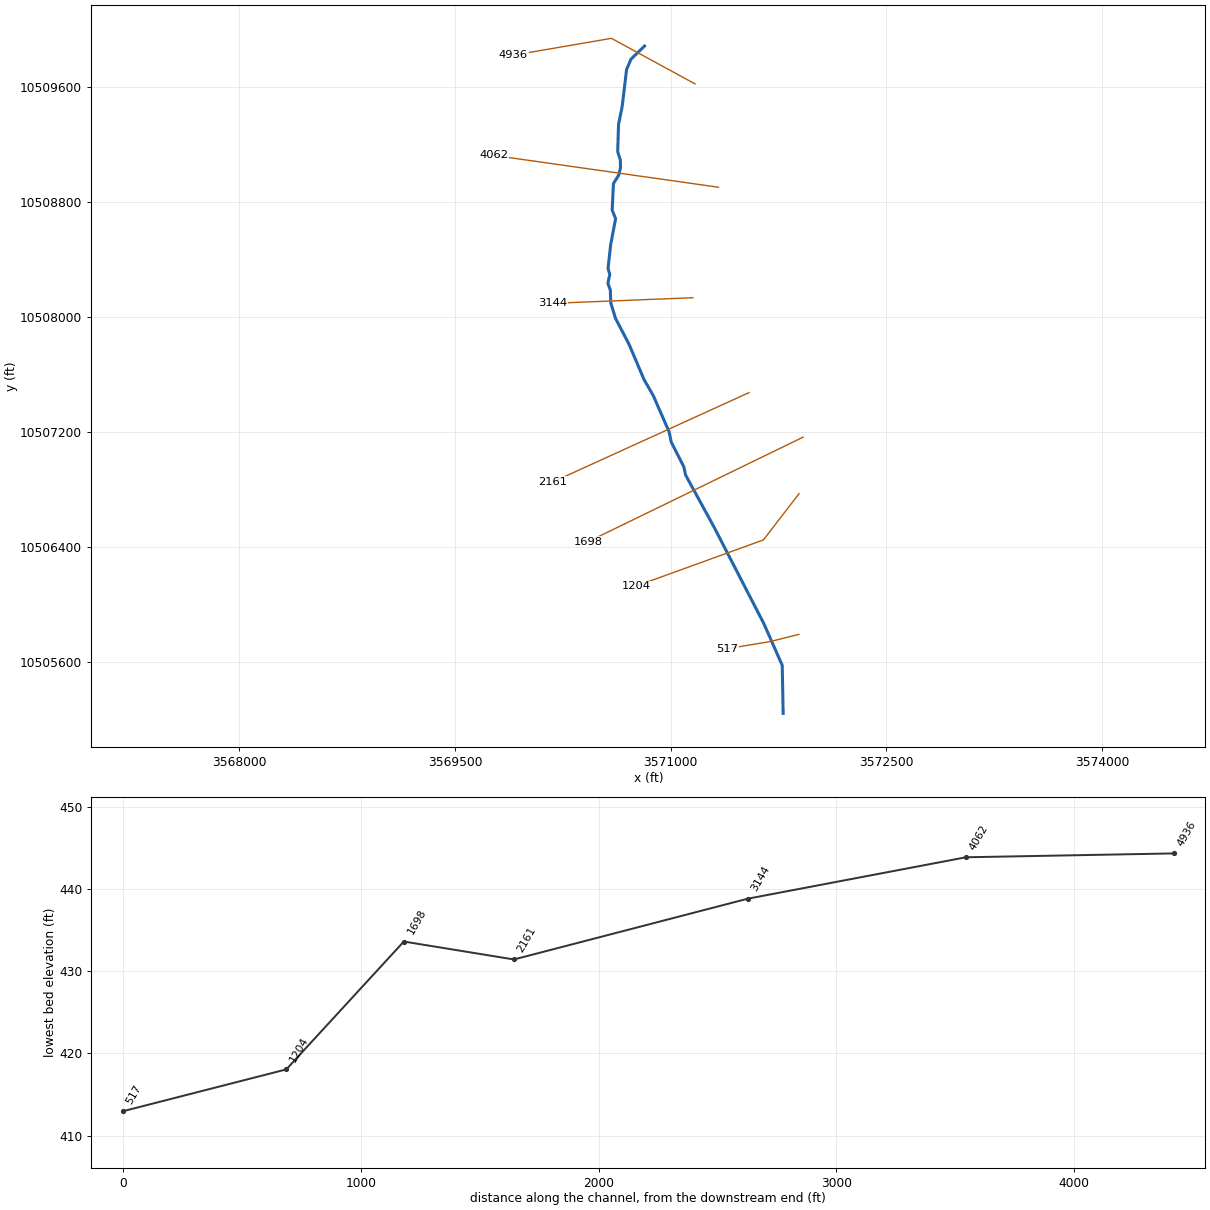
--- UNT0174 IN SAND CR.prj (project) ---

Proj Title=UNT0174 IN SAND CR Base Level Engineering
Current Plan=p01
Default Exp/Contr=0.3,0.1
English Units
Geom File=g01
Flow File=f01
Plan File=p01
BEGIN DESCRIPTION:
UNT0174 IN SAND CR
END DESCRIPTION:

--- UNT0174 IN SAND CR.p01 (plan) ---

Plan Title=Multiple Run
Short Identifier=Multiple
Geom File=g01
Flow File=f01
Subcritical Flow
K Sum by GR= 0
Std Step Tol= 0.01
Critical Tol= 0.01
Num of Std Step Trials= 20
Max Error Tol= 0.3
Flow Tol Ratio= 0.001
Split Flow NTrial= 30
Split Flow Tol= 0.02
Split Flow Ratio= 0.02
Log Output Level= 0
Friction Slope Method= 1
Unsteady Friction Slope Method= 2
Unsteady Bridges Friction Slope Method= 1
Parabolic Critical Depth
Global Vel Dist=  1 , 1 , 1
Global Log Level= 0
CheckData=True
Encroach Param= -1, 0, 0, 0
BEGIN DESCRIPTION:
Multiple Run
END DESCRIPTION:

--- UNT0174 IN SAND CR.f01 (steady flow) ---

Flow Title=Multiple
Number of Profiles=7
Profile Names=10-year,25-year,50-year,1pct_min,100-year,1pct_plu,500-year
River Rch & RM= UNT0174 IN SAND ,Reach-1,4936
    1199    1677    2079    1881    2544    3440    3798
River Rch & RM= UNT0174 IN SAND ,Reach-1,4062
    1450    2045    2548    2315    3131    4235    4717
Boundary for River Rch & Prof#=UNT0174 IN SAND ,Reach-1,1
Up Type=0
Dn Type=3
Dn Slope=0.005
Boundary for River Rch & Prof#=UNT0174 IN SAND ,Reach-1,2
Up Type=0
Dn Type=3
Dn Slope=0.005
Boundary for River Rch & Prof#=UNT0174 IN SAND ,Reach-1,3
Up Type=0
Dn Type=3
Dn Slope=0.005
Boundary for River Rch & Prof#=UNT0174 IN SAND ,Reach-1,4
Up Type=0
Dn Type=3
Dn Slope=0.005
Boundary for River Rch & Prof#=UNT0174 IN SAND ,Reach-1,5
Up Type=0
Dn Type=3
Dn Slope=0.005
Boundary for River Rch & Prof#=UNT0174 IN SAND ,Reach-1,6
Up Type=0
Dn Type=3
Dn Slope=0.005
Boundary for River Rch & Prof#=UNT0174 IN SAND ,Reach-1,7
Up Type=0
Dn Type=3
Dn Slope=0.005

--- UNT0174 IN SAND CR.g01 (geometry) ---

Geom Title=Existing Conditions

River Reach=UNT0174 IN SAND ,Reach-1
Reach XY= 30
      3570818.72     10509882.44      3570724.96     10509791.89
      3570694.06     10509719.32      3570663.16     10509460.64
      3570638.20     10509338.72      3570632.17     10509146.71
      3570650.69     10509090.94      3570651.81     10509036.92
      3570638.26     10508983.25      3570602.69     10508926.40
      3570593.80     10508741.89      3570617.74     10508682.28
      3570583.40     10508501.58      3570565.09     10508336.11
      3570577.41     10508295.03      3570564.07     10508232.21
      3570581.00     10508186.94      3570584.02     10508097.21
      3570616.89     10507989.25      3570710.15     10507810.83
      3570815.67     10507563.12      3570880.18     10507450.85
      3570989.54     10507200.27      3571005.17     10507127.35
      3571091.97     10506957.21      3571104.19     10506900.01
      3571304.87     10506532.73      3571648.62     10505866.07
      3571776.22     10505577.00      3571782.73     10505242.37

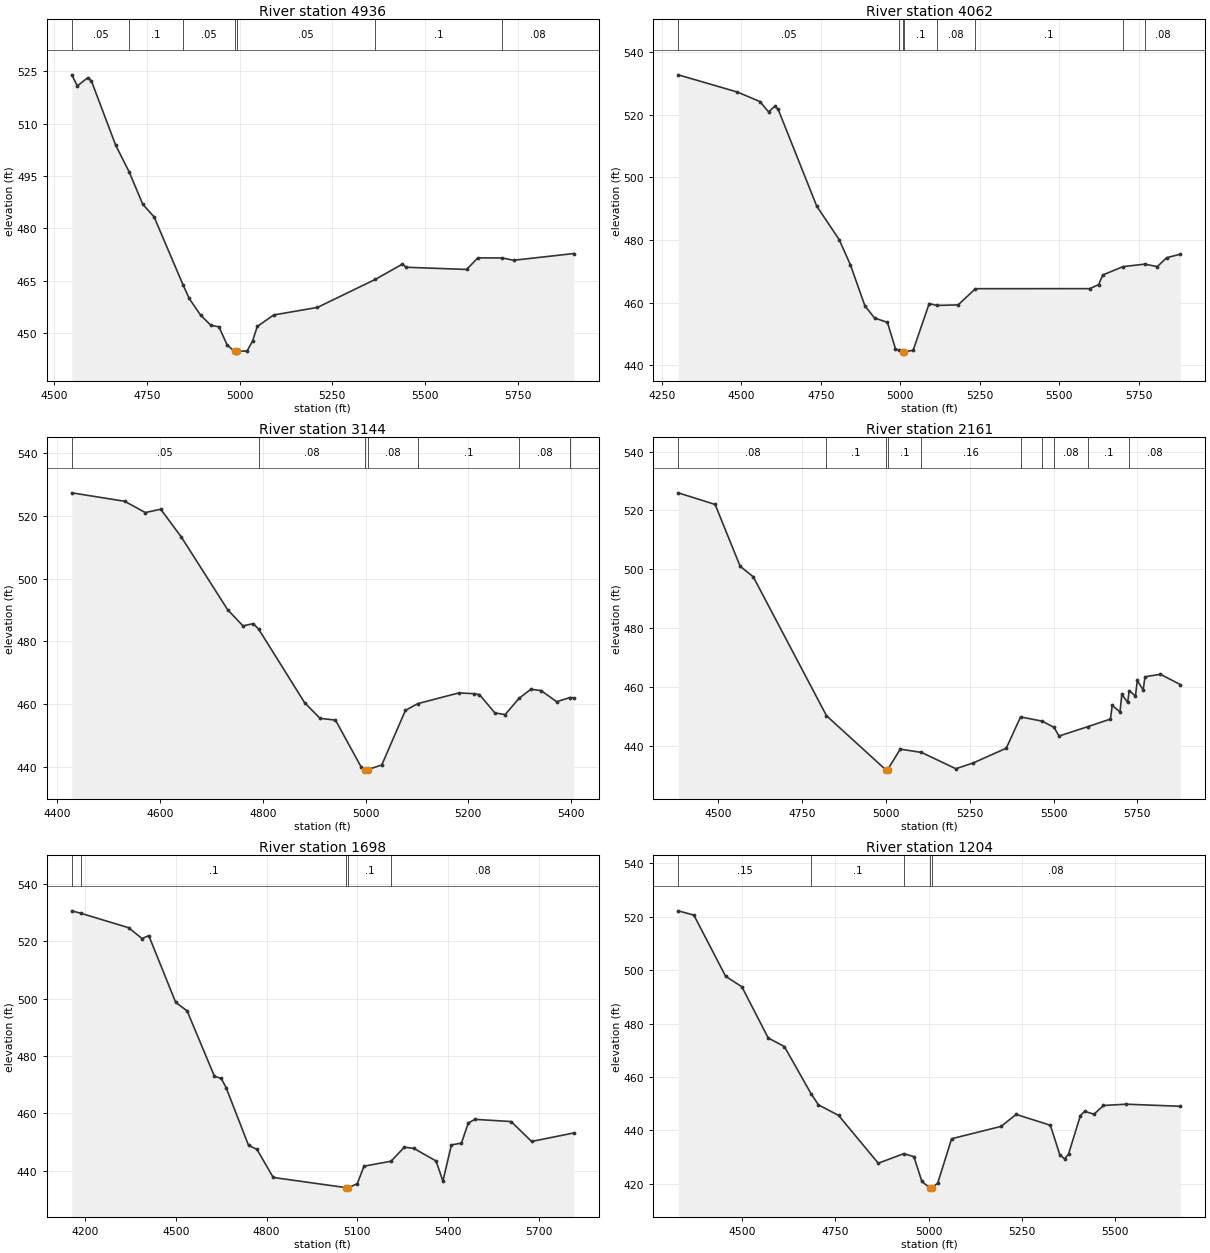
Type RM Length L Ch R = 1,4936,874,874,874
BEGIN DESCRIPTION:
UNT0174 IN SAND CR 10.0
END DESCRIPTION:
XS GIS Cut Line= 3
      3571170.15     10509619.41      3570588.58     10509936.24
      3569907.15     10509819.05
#Sta/Elev= 30
  4547.6  523.96  4562.6  520.78  4590.9  523.16  4600.6  522.20  4666.1  503.79
  4702.2  496.22  4739.0  486.92  4769.6  483.30  4847.5  463.89  4864.2  459.97
  4894.9  455.20  4922.5  452.29  4944.3  451.85  4966.7  446.64  4986.5  444.82
  4989.2  444.32  4992.5  444.82  5020.3  444.95  5035.0  447.78  5047.8  451.95
  5092.0  455.24  5209.9  457.40  5366.0  465.42  5439.0  469.79  5449.8  468.89
  5612.2  468.27  5642.6  471.59  5708.5  471.55  5738.7  470.89  5901.3  472.82
#Mann=7,-1,0
  4547.6    0.05       0  4702.2     0.1       0  4847.5    0.05       0
  4986.5    0.03       0  4992.5    0.05       0  5366.0     0.1       0
  5708.5    0.08       0
Bank Sta=4986.5,4992.5
Exp/Cntr=0.3,0.1

Type RM Length L Ch R = 1,4062,918,918,918
BEGIN DESCRIPTION:
UNT0174 IN SAND CR 9.0
END DESCRIPTION:
XS GIS Cut Line= 2
      3571333.08     10508900.86      3569770.58     10509122.22
#Sta/Elev= 30
  4302.2  532.79  4488.0  527.29  4559.0  524.25  4586.0  520.96  4606.2  522.80
  4616.3  521.75  4737.5  490.83  4808.2  480.10  4843.0  472.17  4889.0  458.94
  4919.3  455.08  4959.7  453.67  4985.0  445.25  4997.1  444.69  5007.2  444.35
  5009.9  443.85  5013.2  444.35  5040.5  444.72  5091.0  459.70  5114.2  459.10
  5181.9  459.27  5236.5  464.44  5596.0  464.46  5623.9  465.77  5636.4  468.82
  5700.1  471.49  5768.6  472.29  5808.1  471.50  5836.9  474.33  5880.3  475.47
#Mann=8,-1,0
  4302.2    0.05       0  4997.1     0.1       0  5007.2    0.07       0
  5013.2     0.1       0  5114.2    0.08       0  5236.5     0.1       0
  5700.1    0.05       0  5768.6    0.08       0
Bank Sta=5007.2,5013.2
Exp/Cntr=0.3,0.1

Type RM Length L Ch R = 1,3144,983,983,983
BEGIN DESCRIPTION:
UNT0174 IN SAND CR 7.0
END DESCRIPTION:
XS GIS Cut Line= 2
      3571155.14     10508132.64      3570178.52     10508093.57
#Sta/Elev= 30
  4428.0  527.22  4531.1  524.53  4571.1  520.96  4601.2  522.01  4641.2  513.20
  4731.3  490.12  4761.3  484.95  4781.3  485.67  4792.0  483.88  4881.4  460.53
  4911.4  455.58  4941.4  455.02  4991.5  440.08  4998.5  439.31  5001.2  438.81
  5004.5  439.31  5031.5  440.77  5077.5  458.09  5101.3  460.24  5181.6  463.66
  5211.7  463.40  5221.7  463.11  5251.7  457.30  5271.7  456.78  5298.8  461.95
  5321.7  464.82  5341.8  464.40  5371.8  460.87  5397.6  462.17  5405.4  462.11
#Mann=7,-1,0
  4428.0    0.05       0  4792.0    0.08       0  4998.5    0.07       0
  5004.5    0.08       0  5101.3     0.1       0  5298.8    0.08       0
  5397.6    0.16       0
Bank Sta=4998.5,5004.5
Exp/Cntr=0.3,0.1

Type RM Length L Ch R = 1,2161,463,463,463
BEGIN DESCRIPTION:
UNT0174 IN SAND CR 5.0
END DESCRIPTION:
XS GIS Cut Line= 2
      3571545.73     10507472.92      3570182.90     10506852.27
#Sta/Elev= 30
  4380.6  526.00  4490.6  522.05  4565.3  501.04  4604.3  497.48  4822.8  450.25
  4999.2  431.92  5001.9  431.42  5005.2  431.92  5042.8  438.90  5106.0  437.78
  5208.7  432.24  5261.2  434.24  5359.0  439.21  5401.6  449.84  5466.4  448.40
  5501.5  446.27  5516.4  443.35  5602.1  446.53  5669.6  449.11  5675.1  453.77
  5698.2  451.53  5703.7  457.53  5721.2  454.75  5725.5  458.77  5744.3  456.93
  5749.8  462.26  5767.3  458.99  5772.8  463.49  5818.9  464.33  5878.1  460.85
#Mann=10,-1,0
  4380.6    0.08       0  4822.8     0.1       0  4999.2    0.07       0
  5005.2     0.1       0  5106.0    0.16       0  5401.6    0.08       0
  5466.4     0.1       0  5501.5    0.08       0  5602.1     0.1       0
  5725.5    0.08       0
Bank Sta=4999.2,5005.2
Exp/Cntr=0.3,0.1

Type RM Length L Ch R = 1,1698,494,494,494
BEGIN DESCRIPTION:
UNT0174 IN SAND CR 3.0
END DESCRIPTION:
XS GIS Cut Line= 2
      3571921.11     10507162.91      3570428.03     10506437.20
#Sta/Elev= 30
  4156.1  530.65  4186.9  529.77  4344.0  524.77  4388.5  520.98  4410.7  522.01
  4499.7  498.73  4537.5  495.76  4627.7  472.99  4650.3  472.19  4666.4  469.01
  4740.5  448.88  4768.6  447.45  4822.1  437.67  5064.4  434.10  5067.2  433.60
  5070.4  434.10  5100.1  435.49  5122.3  441.61  5211.8  443.33  5255.7  448.22
  5287.4  447.80  5360.7  443.41  5383.2  436.41  5411.4  449.02  5444.7  449.65
  5467.0  456.65  5489.2  457.93  5608.8  457.17  5676.5  450.23  5816.2  453.19
#Mann=5,-1,0
  4156.1    0.15       0  4186.9     0.1       0  5064.4    0.07       0
  5070.4     0.1       0  5211.8    0.08       0
Bank Sta=5064.4,5070.4
Exp/Cntr=0.3,0.1

Type RM Length L Ch R = 1,1204,687,687,687
BEGIN DESCRIPTION:
UNT0174 IN SAND CR 3.01
END DESCRIPTION:
XS GIS Cut Line= 3
      3571892.92     10506769.76      3571645.54     10506448.61
      3570760.17     10506127.44
#Sta/Elev= 30
  4328.2  522.23  4370.2  520.62  4455.4  497.72  4498.9  493.81  4569.6  474.64
  4613.1  471.41  4684.5  453.80  4704.5  449.59  4758.5  445.65  4864.9  427.75
  4933.4  431.33  4960.6  430.21  4981.9  420.92  5002.9  418.55  5005.6  418.05
  5008.9  418.55  5024.4  420.30  5061.8  436.92  5194.6  441.54  5234.9  446.01
  5326.7  441.97  5352.0  430.94  5364.9  429.37  5375.5  431.20  5407.4  445.60
  5418.6  447.16  5443.9  446.10  5469.2  449.36  5530.4  449.85  5675.4  449.06
#Mann=5,-1,0
  4328.2    0.15       0  4684.5     0.1       0  4933.4    0.08       0
  5002.9    0.07       0  5008.9    0.08       0
Bank Sta=5002.9,5008.9
Exp/Cntr=0.3,0.1

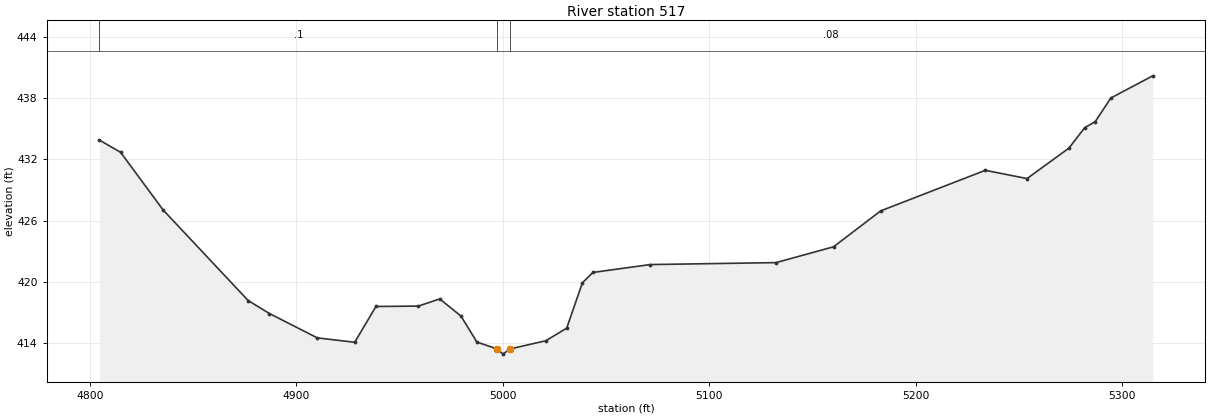
Type RM Length L Ch R = 1,517,0,0,0
BEGIN DESCRIPTION:
UNT0174 IN SAND CR 1.0
END DESCRIPTION:
XS GIS Cut Line= 3
      3571892.07     10505791.63      3571692.11     10505741.64
      3571392.06     10505691.63
#Sta/Elev= 30
  4804.5  433.90  4814.8  432.70  4835.4  427.06  4876.6  418.20  4886.9  416.93
  4910.1  414.55  4928.2  414.12  4938.5  417.62  4959.1  417.66  4969.4  418.36
  4979.7  416.68  4987.4  414.14  4997.3  413.46  5000.1  412.96  5003.3  413.46
  5020.8  414.27  5030.9  415.50  5038.5  419.93  5043.6  420.95  5071.4  421.72
  5132.3  421.91  5160.2  423.46  5183.0  426.97  5233.7  430.94  5253.9  430.13
  5274.2  433.11  5281.8  435.10  5286.9  435.69  5294.5  438.01  5314.8  440.18
#Mann=3,-1,0
  4804.5     0.1       0  4997.3    0.07       0  5003.3    0.08       0
Bank Sta=4997.3,5003.3
Exp/Cntr=0.3,0.1

Chan Stop Cuts=-1