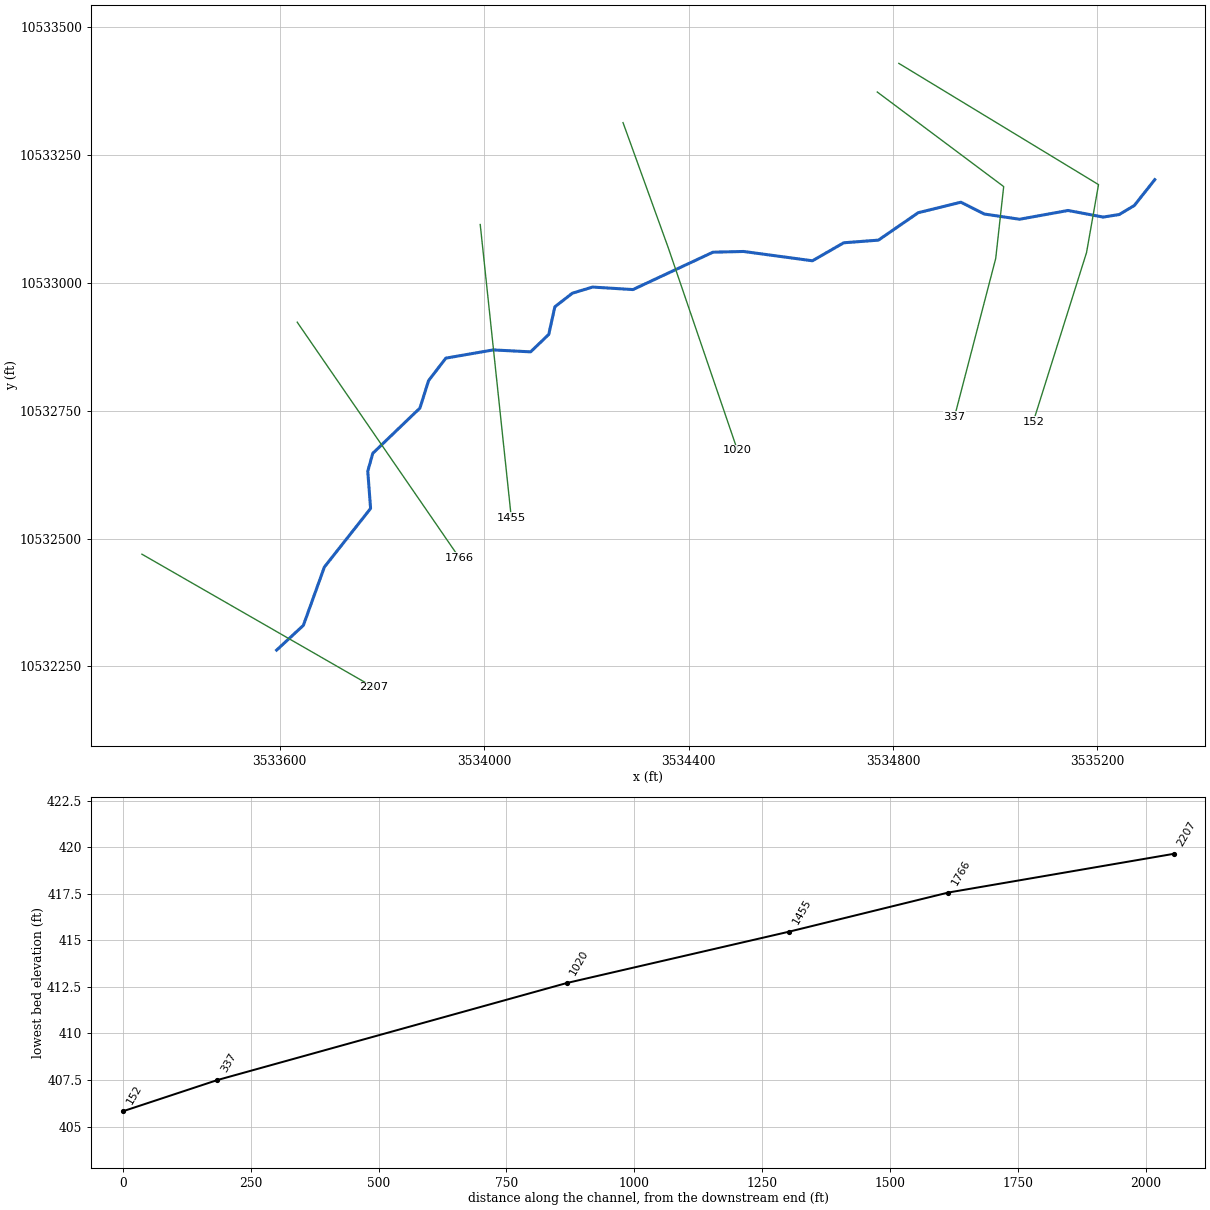
--- UNT01749 IN SAND CR.prj (project) ---

Proj Title=UNT01749 IN SAND CR Base Level Engineering
Current Plan=p01
Default Exp/Contr=0.3,0.1
English Units
Geom File=g01
Flow File=f01
Plan File=p01
BEGIN DESCRIPTION:
UNT01749 IN SAND CR
END DESCRIPTION:

--- UNT01749 IN SAND CR.p01 (plan) ---

Plan Title=Multiple Run
Short Identifier=Multiple
Geom File=g01
Flow File=f01
Subcritical Flow
K Sum by GR= 0
Std Step Tol= 0.01
Critical Tol= 0.01
Num of Std Step Trials= 20
Max Error Tol= 0.3
Flow Tol Ratio= 0.001
Split Flow NTrial= 30
Split Flow Tol= 0.02
Split Flow Ratio= 0.02
Log Output Level= 0
Friction Slope Method= 1
Unsteady Friction Slope Method= 2
Unsteady Bridges Friction Slope Method= 1
Parabolic Critical Depth
Global Vel Dist=  1 , 1 , 1
Global Log Level= 0
CheckData=True
Encroach Param= -1, 0, 0, 0
BEGIN DESCRIPTION:
Multiple Run
END DESCRIPTION:

--- UNT01749 IN SAND CR.f01 (steady flow) ---

Flow Title=Multiple
Number of Profiles=7
Profile Names=10-year,25-year,50-year,1pct_min,100-year,1pct_plu,500-year
River Rch & RM= UNT01749 IN SAND,Reach-1,2207
     314     401     468     400     541     731     718
Boundary for River Rch & Prof#=UNT01749 IN SAND,Reach-1,1
Up Type=0
Dn Type=3
Dn Slope=0.005
Boundary for River Rch & Prof#=UNT01749 IN SAND,Reach-1,2
Up Type=0
Dn Type=3
Dn Slope=0.005
Boundary for River Rch & Prof#=UNT01749 IN SAND,Reach-1,3
Up Type=0
Dn Type=3
Dn Slope=0.005
Boundary for River Rch & Prof#=UNT01749 IN SAND,Reach-1,4
Up Type=0
Dn Type=3
Dn Slope=0.005
Boundary for River Rch & Prof#=UNT01749 IN SAND,Reach-1,5
Up Type=0
Dn Type=3
Dn Slope=0.005
Boundary for River Rch & Prof#=UNT01749 IN SAND,Reach-1,6
Up Type=0
Dn Type=3
Dn Slope=0.005
Boundary for River Rch & Prof#=UNT01749 IN SAND,Reach-1,7
Up Type=0
Dn Type=3
Dn Slope=0.005

--- UNT01749 IN SAND CR.g01 (geometry) ---

Geom Title=Existing Conditions

River Reach=UNT01749 IN SAND,Reach-1
Reach XY= 30
      3533593.93     10532281.87      3533646.26     10532330.22
      3533687.33     10532444.19      3533777.75     10532558.77
      3533772.26     10532631.68      3533782.07     10532666.56
      3533874.30     10532755.06      3533891.21     10532808.70
      3533925.02     10532852.69      3534017.60     10532868.75
      3534090.87     10532864.99      3534126.36     10532899.02
      3534138.32     10532953.06      3534172.66     10532979.67
      3534212.14     10532991.65      3534291.08     10532986.74
      3534447.66     10533059.83      3534507.56     10533061.23
      3534642.33     10533043.02      3534703.48     10533078.21
      3534771.39     10533083.40      3534849.27     10533137.02
      3534932.84     10533157.54      3534978.54     10533134.44
      3535047.57     10533124.24      3535142.43     10533141.37
      3535211.22     10533128.48      3535242.44     10533133.45
      3535272.00     10533151.01      3535312.11     10533201.64

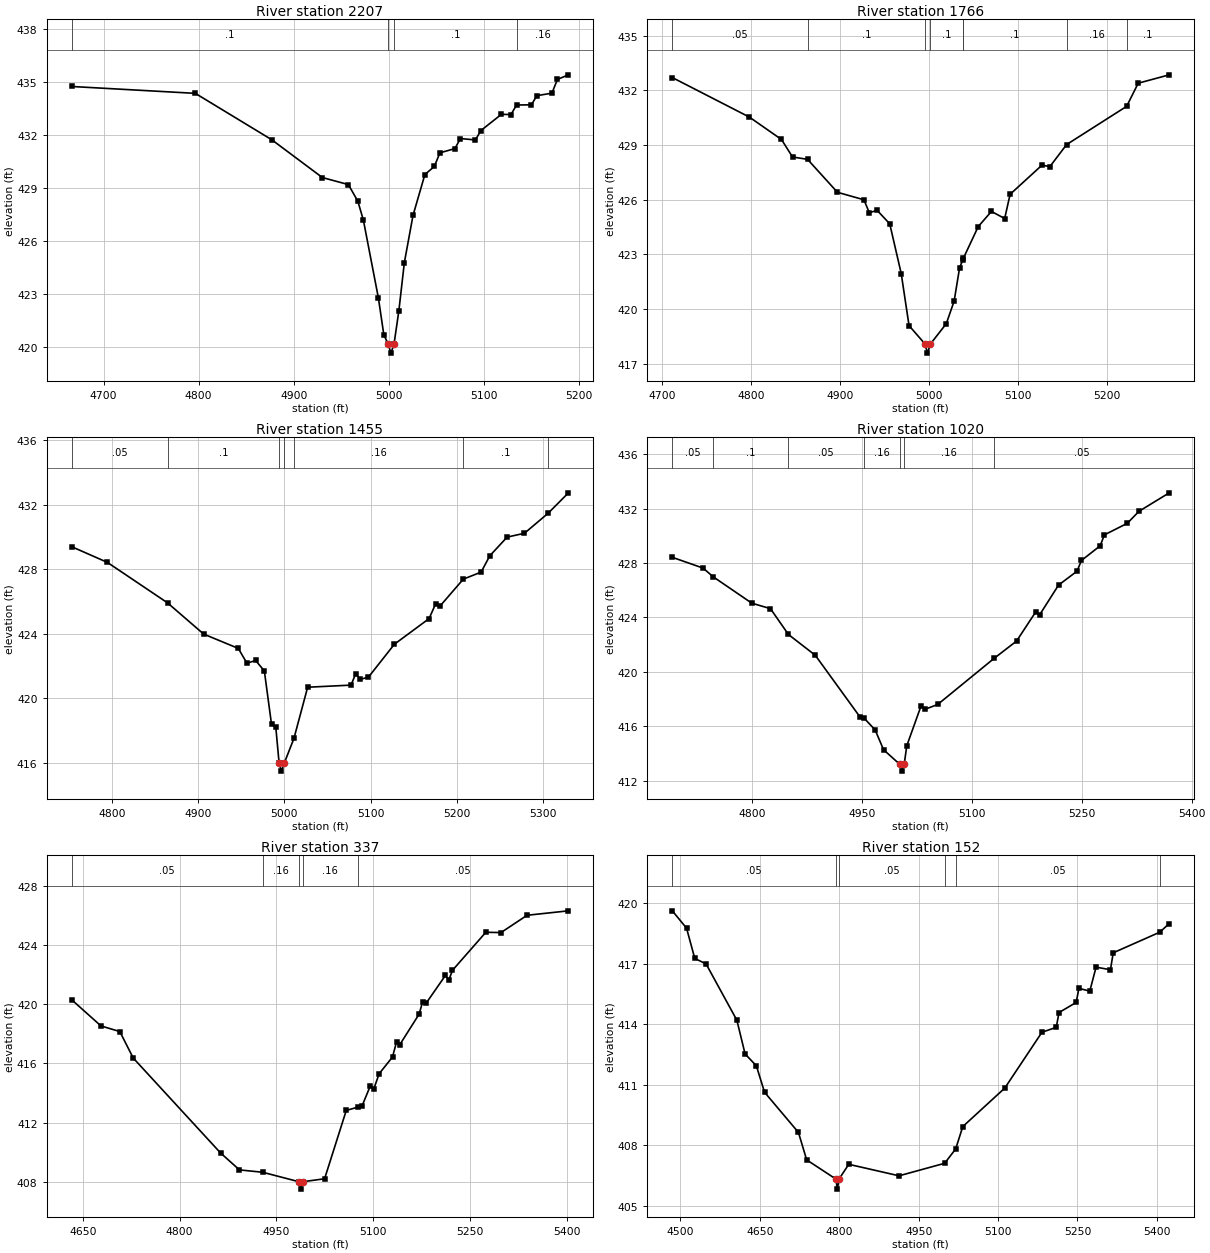
Type RM Length L Ch R = 1,2207,441,441,441
BEGIN DESCRIPTION:
UNT01749 IN SAND CR 4.1
END DESCRIPTION:
XS GIS Cut Line= 2
      3533330.38     10532469.39      3533783.94     10532208.98
#Sta/Elev= 30
  4666.2  434.76  4796.5  434.37  4877.0  431.74  4930.2  429.60  4957.6  429.20
  4967.6  428.25  4973.4  427.18  4989.2  422.77  4994.9  420.69  4999.6  420.15
  5002.3  419.65  5005.6  420.15  5010.7  422.04  5016.5  424.78  5025.6  427.45
  5038.1  429.77  5048.1  430.23  5053.9  431.00  5069.7  431.24  5075.5  431.81
  5091.3  431.73  5097.0  432.26  5118.6  433.18  5128.7  433.17  5134.6  433.71
  5150.2  433.72  5156.0  434.24  5171.8  434.38  5177.6  435.16  5189.2  435.42
#Mann=4,-1,0
  4666.2     0.1       0  4999.6    0.07       0  5005.6     0.1       0
  5134.6    0.16       0
Bank Sta=4999.6,5005.6
Exp/Cntr=0.3,0.1

Type RM Length L Ch R = 1,1766,311,311,311
BEGIN DESCRIPTION:
UNT01749 IN SAND CR 4.0
END DESCRIPTION:
XS GIS Cut Line= 2
      3533634.22     10532922.95      3533951.05     10532462.89
#Sta/Elev= 30
  4711.1  432.70  4797.7  430.53  4833.8  429.30  4846.2  428.34  4863.1  428.21
  4896.7  426.40  4926.5  425.99  4932.5  425.28  4941.3  425.41  4955.5  424.67
  4968.4  421.94  4977.2  419.08  4995.2  418.07  4997.9  417.57  5001.2  418.07
  5019.1  419.19  5027.9  420.43  5034.0  422.25  5037.5  422.68  5038.3  422.78
  5055.0  424.52  5069.8  425.35  5084.7  424.96  5090.8  426.29  5126.6  427.89
  5135.5  427.81  5154.3  429.02  5221.8  431.12  5234.8  432.39  5269.7  432.85
#Mann=8,-1,0
  4711.1    0.05       0  4863.1     0.1       0  4995.2    0.07       0
  5001.2     0.1       0  5037.5    0.16       0  5038.3     0.1       0
  5154.3    0.16       0  5221.8     0.1       0
Bank Sta=4995.2,5001.2
Exp/Cntr=0.3,0.1

Type RM Length L Ch R = 1,1455,435,435,435
BEGIN DESCRIPTION:
UNT01749 IN SAND CR 4.2
END DESCRIPTION:
XS GIS Cut Line= 2
      3533992.30     10533113.96      3534053.07     10532540.97
#Sta/Elev= 30
  4753.3  429.41  4794.9  428.43  4864.6  425.92  4906.5  423.98  4946.7  423.09
  4956.7  422.17  4966.8  422.34  4976.9  421.69  4985.2  418.38  4990.2  418.18
  4994.0  415.97  4996.7  415.47  5000.0  415.97  5011.2  417.50  5027.1  420.68
  5077.4  420.81  5082.9  421.53  5087.9  421.17  5097.5  421.30  5127.7  423.35
  5167.9  424.94  5175.6  425.87  5180.6  425.72  5207.6  427.39  5228.3  427.83
  5238.3  428.84  5258.4  430.00  5278.5  430.24  5305.9  431.48  5329.5  432.75
#Mann=7,-1,0
  4753.3    0.05       0  4864.6     0.1       0  4994.0    0.07       0
  5000.0     0.1       0  5011.2    0.16       0  5207.6     0.1       0
  5305.9    0.16       0
Bank Sta=4994,5000
Exp/Cntr=0.3,0.1

Type RM Length L Ch R = 1,1020,683,683,683
BEGIN DESCRIPTION:
UNT01749 IN SAND CR 2.0
END DESCRIPTION:
XS GIS Cut Line= 3
      3534271.71     10533313.11      3534360.25     10533068.32
      3534495.68     10532672.45
#Sta/Elev= 30
  4690.7  428.42  4732.7  427.63  4746.5  426.99  4799.3  425.05  4824.7  424.65
  4849.3  422.75  4886.0  421.22  4946.6  416.72  4952.2  416.63  4967.8  415.73
  4979.2  414.28  5001.4  413.21  5004.1  412.71  5007.4  413.21  5010.9  414.57
  5030.4  417.50  5035.7  417.25  5053.2  417.61  5130.3  421.00  5160.9  422.27
  5186.9  424.40  5192.2  424.18  5218.2  426.38  5243.4  427.40  5249.5  428.19
  5275.1  429.27  5280.8  430.07  5312.1  430.92  5328.0  431.80  5369.4  433.16
#Mann=7,-1,0
  4690.7    0.05       0  4746.5     0.1       0  4849.3    0.05       0
  4952.2    0.16       0  5001.4    0.07       0  5007.4    0.16       0
  5130.3    0.05       0
Bank Sta=5001.4,5007.4
Exp/Cntr=0.3,0.1

Type RM Length L Ch R = 1,337,185,185,185
BEGIN DESCRIPTION:
UNT01749 IN SAND CR 1.0
END DESCRIPTION:
XS GIS Cut Line= 4
      3534769.14     10533372.99      3535016.50     10533188.11
      3535000.88     10533047.49      3534920.16     10532737.64
#Sta/Elev= 30
  4632.5  420.31  4678.2  418.53  4707.4  418.15  4728.2  416.36  4863.7  409.94
  4892.9  408.80  4928.9  408.64  4985.1  408.00  4987.8  407.50  4991.1  408.00
  5024.9  408.20  5058.5  412.82  5076.4  413.04  5082.8  413.10  5095.9  414.49
  5101.1  414.26  5109.5  415.30  5130.2  416.43  5136.4  417.44  5141.6  417.27
  5171.5  419.33  5176.9  420.16  5182.1  420.05  5212.2  421.94  5217.4  421.62
  5223.2  422.29  5274.9  424.86  5298.4  424.84  5338.9  426.01  5403.0  426.31
#Mann=5,-1,0
  4632.5    0.05       0  4928.9    0.16       0  4985.1    0.07       0
  4991.1    0.16       0  5076.4    0.05       0
Bank Sta=4985.1,4991.1
Exp/Cntr=0.3,0.1

Type RM Length L Ch R = 1,152,0,0,0
BEGIN DESCRIPTION:
UNT01749 IN SAND CR 1.1
END DESCRIPTION:
XS GIS Cut Line= 4
      3534811.39     10533428.96      3535202.05     10533191.96
      3535178.61     10533059.15      3535074.45     10532728.46
#Sta/Elev= 30
  4484.8  419.61  4511.7  418.75  4527.2  417.25  4548.5  416.98  4606.7  414.19
  4622.2  412.52  4643.5  411.93  4659.0  410.62  4723.0  408.63  4738.5  407.27
  4793.7  406.32  4796.4  405.82  4799.7  406.32  4818.0  407.05  4913.0  406.48
  4999.1  407.10  5019.9  407.81  5033.4  408.92  5112.8  410.83  5182.8  413.59
  5209.9  413.84  5215.1  414.57  5247.5  415.07  5252.7  415.77  5273.2  415.63
  5285.1  416.82  5312.2  416.69  5317.5  417.53  5405.3  418.55  5423.3  418.98
#Mann=6,-1,0
  4484.8    0.05       0  4793.7    0.07       0  4799.7    0.05       0
  4999.1    0.16       0  5019.9    0.05       0  5405.3     0.1       0
Bank Sta=4793.7,4799.7
Exp/Cntr=0.3,0.1

Chan Stop Cuts=-1