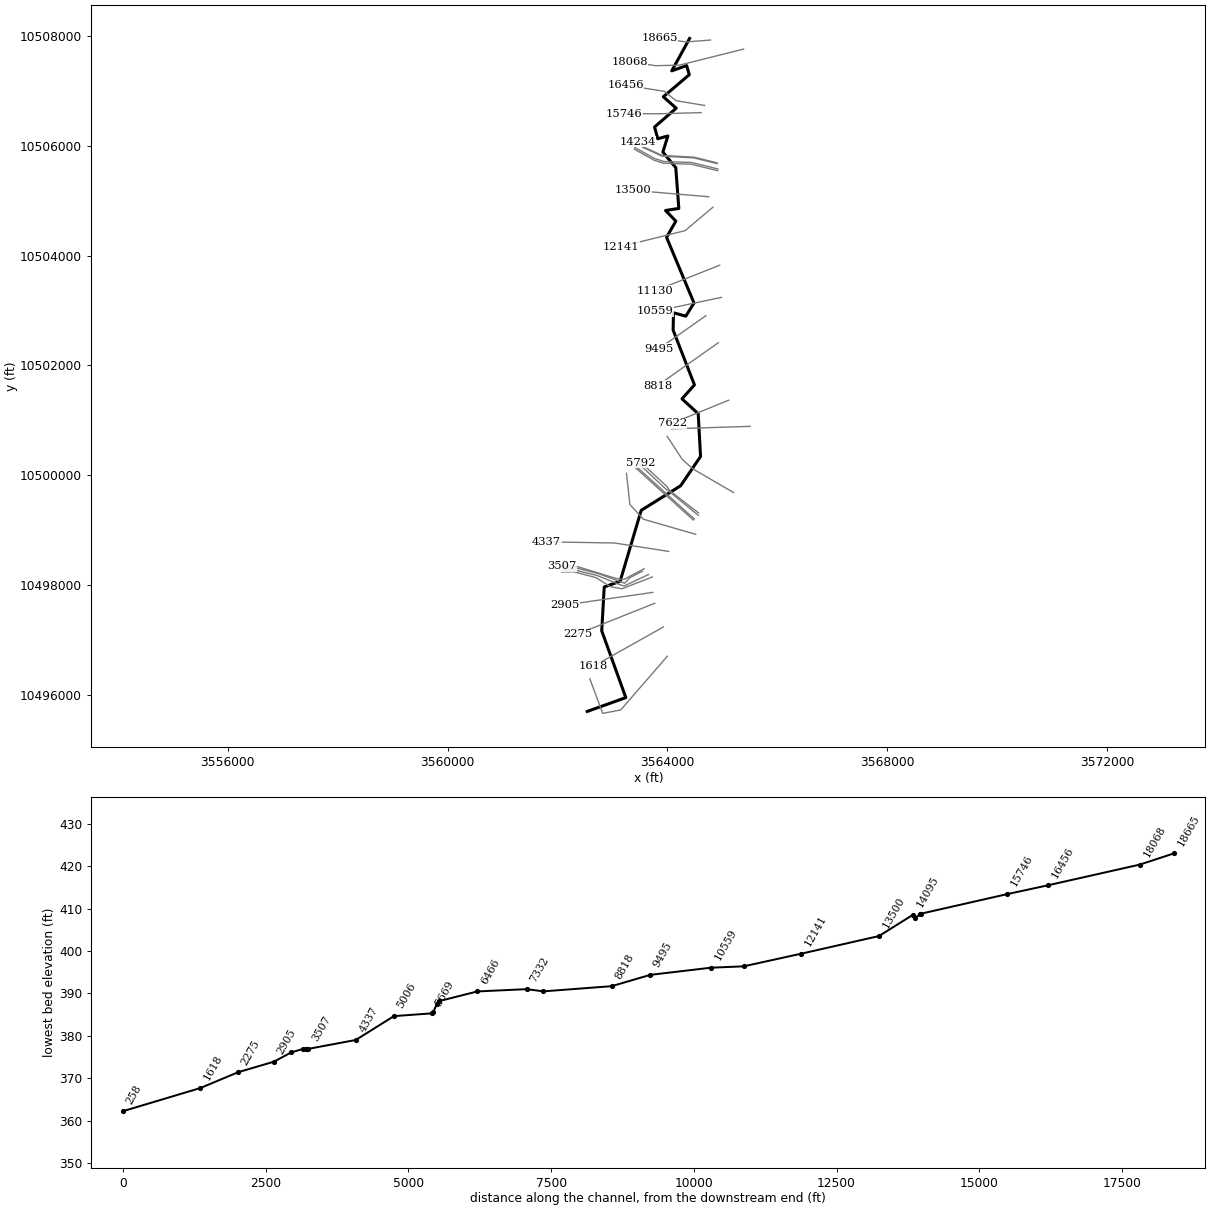
--- UNT0175 IN SAND CR.prj (project) ---

Proj Title=UNT0175 IN SAND CR Base Level Engineering
Current Plan=p01
Default Exp/Contr=0.3,0.1
English Units
Geom File=g01
Flow File=f01
Plan File=p01
BEGIN DESCRIPTION:
UNT0175 IN SAND CR
END DESCRIPTION:

--- UNT0175 IN SAND CR.p01 (plan) ---

Plan Title=Multiple Run
Short Identifier=Multiple
Geom File=g01
Flow File=f01
Subcritical Flow
K Sum by GR= 0
Std Step Tol= 0.01
Critical Tol= 0.01
Num of Std Step Trials= 20
Max Error Tol= 0.3
Flow Tol Ratio= 0.001
Split Flow NTrial= 30
Split Flow Tol= 0.02
Split Flow Ratio= 0.02
Log Output Level= 0
Friction Slope Method= 1
Unsteady Friction Slope Method= 2
Unsteady Bridges Friction Slope Method= 1
Parabolic Critical Depth
Global Vel Dist=  1 , 1 , 1
Global Log Level= 0
CheckData=True
Encroach Param= -1, 0, 0, 0
BEGIN DESCRIPTION:
Multiple Run
END DESCRIPTION:

--- UNT0175 IN SAND CR.f01 (steady flow) ---

Flow Title=Multiple
Number of Profiles=7
Profile Names=10-year,25-year,50-year,1pct_min,100-year,1pct_plu,500-year
River Rch & RM= UNT0175 IN SAND ,Reach-1,18665
    1524    2133    2644    2386    3227    4365    4798
River Rch & RM= UNT0175 IN SAND ,Reach-1,4337
    1902    2690    3358    3049    4124    5577    6209
Boundary for River Rch & Prof#=UNT0175 IN SAND ,Reach-1,1
Up Type=0
Dn Type=3
Dn Slope=0.005
Boundary for River Rch & Prof#=UNT0175 IN SAND ,Reach-1,2
Up Type=0
Dn Type=3
Dn Slope=0.005
Boundary for River Rch & Prof#=UNT0175 IN SAND ,Reach-1,3
Up Type=0
Dn Type=3
Dn Slope=0.005
Boundary for River Rch & Prof#=UNT0175 IN SAND ,Reach-1,4
Up Type=0
Dn Type=3
Dn Slope=0.005
Boundary for River Rch & Prof#=UNT0175 IN SAND ,Reach-1,5
Up Type=0
Dn Type=3
Dn Slope=0.005
Boundary for River Rch & Prof#=UNT0175 IN SAND ,Reach-1,6
Up Type=0
Dn Type=3
Dn Slope=0.005
Boundary for River Rch & Prof#=UNT0175 IN SAND ,Reach-1,7
Up Type=0
Dn Type=3
Dn Slope=0.005

--- UNT0175 IN SAND CR.g01 (geometry) ---

Geom Title=Existing Conditions

River Reach=UNT0175 IN SAND ,Reach-1
Reach XY= 30
      3564402.11     10507951.64      3564078.06     10507362.52
      3564348.37     10507458.35      3564396.77     10507292.16
      3563924.63     10506890.33      3564158.75     10506682.00
      3563765.00     10506339.81      3563823.59     10506125.49
      3564007.18     10506177.57      3563916.53     10505883.04
      3564151.04     10505601.18      3564206.51     10504857.83
      3563965.27     10504820.51      3564152.25     10504626.44
      3563983.30     10504331.52      3564482.41     10503136.60
      3564334.41     10502896.95      3564109.74     10502957.85
      3564103.01     10502641.91      3564490.91     10501645.41
      3564264.09     10501391.40      3564559.47     10501120.52
      3564601.45     10500342.05      3564239.86     10499809.04
      3563521.86     10499360.92      3563138.79     10498070.26
      3562849.20     10497966.10      3562804.26     10497167.60
      3563242.41     10495952.09      3562540.85     10495700.55

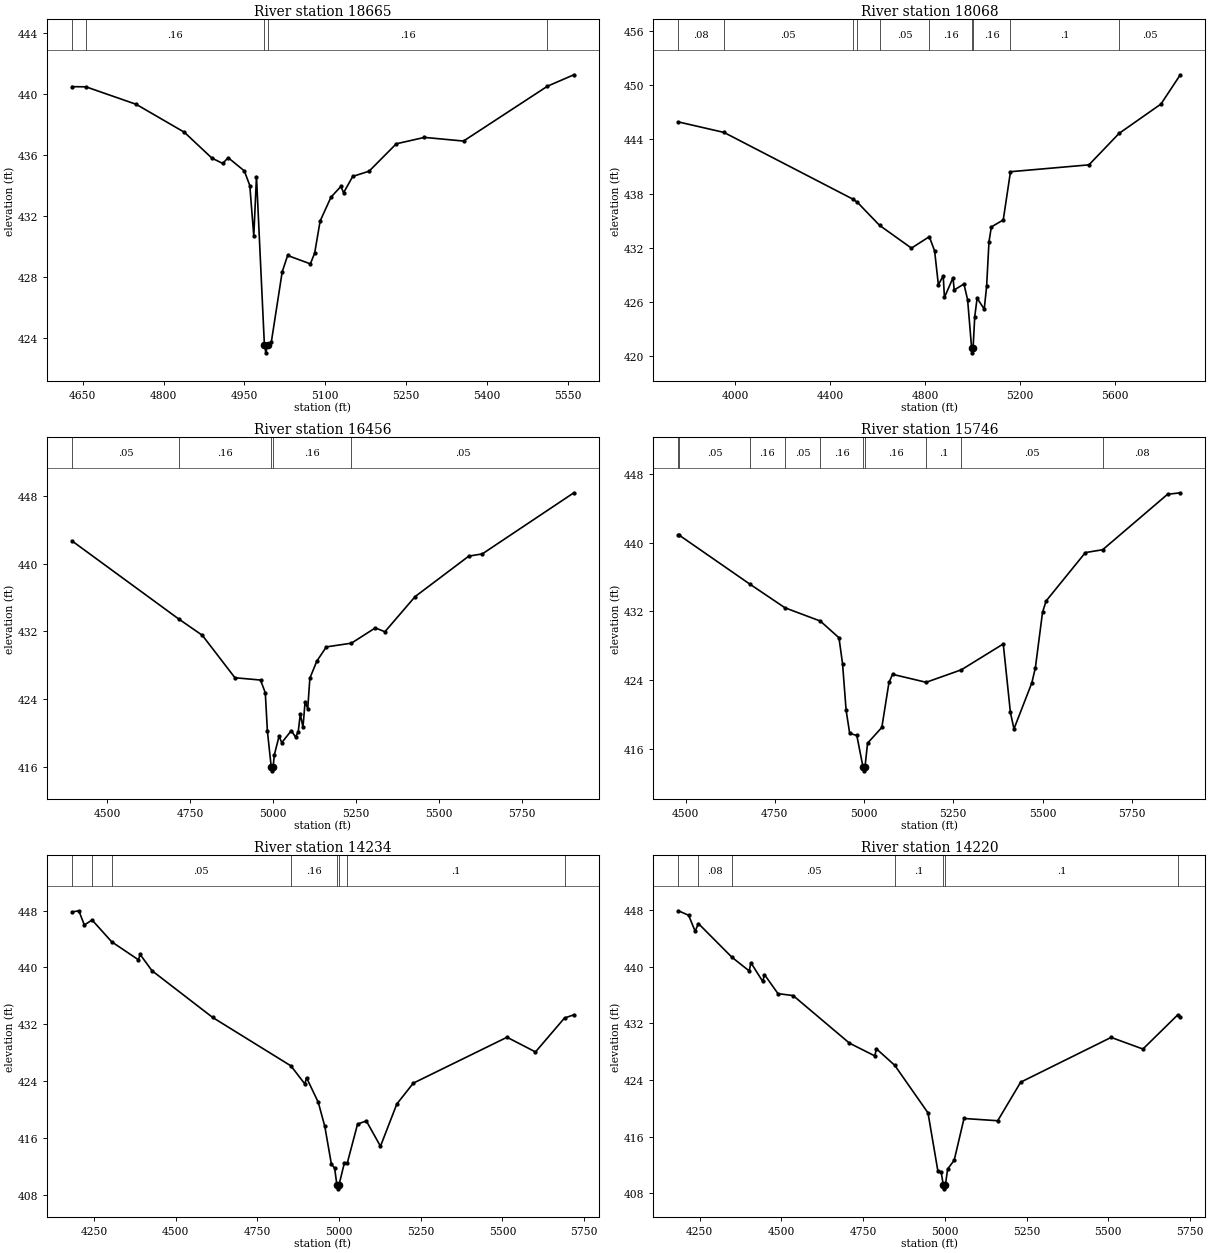
Type RM Length L Ch R = 1,18665,597,597,597
BEGIN DESCRIPTION:
UNT0175 IN SAND CR 31.0
END DESCRIPTION:
XS GIS Cut Line= 3
      3564781.04     10507923.31      3564340.06     10507888.59
      3563855.55     10507954.34
#Sta/Elev= 30
  4630.1  440.49  4656.0  440.48  4749.4  439.33  4838.6  437.50  4889.8  435.80
  4909.9  435.45  4919.9  435.83  4950.0  434.96  4960.1  434.00  4967.5  430.68
  4972.5  434.59  4987.2  423.52  4989.9  423.02  4993.2  423.52  5000.2  423.76
  5020.2  428.33  5030.3  429.41  5072.5  428.86  5080.5  429.57  5090.6  431.67
  5110.8  433.24  5129.1  433.94  5134.2  433.53  5151.1  434.60  5181.4  434.94
  5231.9  436.74  5284.2  437.16  5356.7  436.92  5512.4  440.52  5561.4  441.27
#Mann=5,-1,0
  4630.1    0.15       0  4656.0    0.16       0  4987.2    0.07       0
  4993.2    0.16       0  5512.4    0.05       0
Bank Sta=4987.2,4993.2
Exp/Cntr=0.3,0.1

Type RM Length L Ch R = 1,18068,1612,1612,1612
BEGIN DESCRIPTION:
UNT0175 IN SAND CR 30.0
END DESCRIPTION:
XS GIS Cut Line= 4
      3565384.31     10507758.34      3564217.59     10507466.66
      3563787.04     10507456.25      3563311.38     10507525.69
#Sta/Elev= 30
  3761.6  445.94  3953.4  444.78  4496.0  437.40  4515.5  437.04  4608.9  434.49
  4743.1  431.97  4818.5  433.24  4840.8  431.65  4856.5  427.91  4876.9  428.91
  4882.1  426.51  4918.1  428.69  4923.3  427.34  4964.2  428.00  4979.7  426.25
  4996.7  420.88  4999.5  420.38  5002.7  420.88  5009.7  424.38  5019.7  426.43
  5049.7  425.22  5059.7  427.73  5069.7  432.67  5079.7  434.32  5129.8  435.09
  5160.2  440.43  5490.8  441.19  5617.6  444.67  5794.0  447.92  5875.6  451.16
#Mann=10,-1,0
  3761.6    0.08       0  3953.4    0.05       0  4496.0    0.08       0
  4515.5    0.16       0  4608.9    0.05       0  4818.5    0.16       0
  4996.7    0.07       0  5002.7    0.16       0  5160.2     0.1       0
  5617.6    0.05       0
Bank Sta=4996.7,5002.7
Exp/Cntr=0.3,0.1

Type RM Length L Ch R = 1,16456,710,710,710
BEGIN DESCRIPTION:
UNT0175 IN SAND CR 28.0
END DESCRIPTION:
XS GIS Cut Line= 4
      3564676.83     10506732.34      3564156.03     10506819.14
      3563944.22     10506989.28      3563239.39     10507100.39
#Sta/Elev= 30
  4394.4  442.69  4716.7  433.44  4787.5  431.52  4885.8  426.50  4962.9  426.23
  4977.3  424.73  4983.7  420.17  4995.1  415.99  4997.8  415.49  5001.1  415.99
  5004.5  417.36  5018.9  419.60  5026.9  418.82  5055.7  420.24  5068.5  419.49
  5076.5  420.08  5082.9  422.22  5090.9  420.63  5097.3  423.66  5105.3  422.85
  5111.7  426.45  5132.6  428.46  5161.3  430.15  5237.0  430.59  5309.1  432.40
  5337.9  431.94  5429.0  436.10  5591.0  440.89  5631.6  441.15  5907.6  448.38
#Mann=5,-1,0
  4394.4    0.05       0  4716.7    0.16       0  4995.1    0.07       0
  5001.1    0.16       0  5237.0    0.05       0
Bank Sta=4995.1,5001.1
Exp/Cntr=0.3,0.1

Type RM Length L Ch R = 1,15746,1512,1512,1512
BEGIN DESCRIPTION:
UNT0175 IN SAND CR 27.0
END DESCRIPTION:
XS GIS Cut Line= 3
      3564611.63     10506602.13      3563830.34     10506580.43
      3563206.24     10506584.76
#Sta/Elev= 30
  4480.1  440.89  4482.3  440.89  4679.9  435.19  4778.7  432.42  4877.5  430.88
  4929.8  428.93  4939.8  425.90  4949.8  420.47  4959.8  417.79  4979.8  417.54
  4996.8  413.92  4999.6  413.42  5002.8  413.92  5009.8  416.64  5049.8  418.48
  5069.8  423.72  5079.9  424.67  5173.9  423.74  5272.7  425.20  5389.9  428.21
  5409.9  420.23  5419.9  418.31  5469.9  423.67  5479.9  425.45  5499.9  431.90
  5509.9  433.22  5619.9  438.86  5668.3  439.19  5849.9  445.65  5885.8  445.83
#Mann=10,-1,0
  4480.1    0.16       0  4482.3    0.05       0  4679.9    0.16       0
  4778.7    0.05       0  4877.5    0.16       0  4996.8    0.07       0
  5002.8    0.16       0  5173.9     0.1       0  5272.7    0.05       0
  5668.3    0.08       0
Bank Sta=4996.8,5002.8
Exp/Cntr=0.3,0.1

Type RM Length L Ch R = 1,14234,14,14,14
BEGIN DESCRIPTION:
UNT0175 IN SAND CR 26.1
END DESCRIPTION:
XS GIS Cut Line= 5
      3564902.60     10505687.19      3564482.42     10505791.37
      3563902.56     10505822.62      3563562.28     10505978.87
      3563451.16     10506076.10
#Sta/Elev= 30
  4182.8  447.81  4203.9  447.98  4220.7  445.98  4244.5  446.68  4304.4  443.61
  4386.3  441.07  4391.4  441.83  4427.6  439.54  4613.3  432.95  4853.0  426.12
  4895.5  423.57  4900.5  424.46  4936.5  420.99  4956.5  417.59  4976.5  412.31
  4986.6  411.70  4993.6  409.30  4996.3  408.80  4999.6  409.30  5016.6  412.50
  5025.1  412.41  5056.7  417.92  5083.5  418.37  5126.8  414.80  5176.8  420.75
  5227.2  423.69  5514.0  430.16  5601.1  428.09  5689.9  432.87  5718.5  433.32
#Mann=8,-1,0
  4182.8    0.05       0  4244.5    0.08       0  4304.4    0.05       0
  4853.0    0.16       0  4993.6    0.07       0  4999.6    0.16       0
  5025.1     0.1       0  5689.9    0.05       0
Bank Sta=4993.6,4999.6
Exp/Cntr=0.3,0.1

Type RM Length L Ch R = 1,14220,93,93,93
BEGIN DESCRIPTION:
UNT0175 IN SAND CR 26.0
END DESCRIPTION:
XS GIS Cut Line= 5
      3564902.55     10505673.31      3564482.42     10505777.48
      3563902.56     10505808.73      3563562.28     10505964.98
      3563451.19     10506062.18
#Sta/Elev= 30
  4185.0  447.89  4216.4  447.25  4236.1  445.00  4246.1  446.09  4349.0  441.32
  4401.6  439.40  4406.8  440.56  4443.0  437.91  4448.2  438.89  4489.6  436.20
  4536.1  435.92  4708.3  429.21  4785.8  427.41  4790.8  428.41  4846.9  426.08
  4948.6  419.37  4978.8  411.18  4988.7  411.04  4995.7  409.15  4998.5  408.65
  5001.7  409.15  5008.7  411.44  5028.8  412.69  5058.8  418.58  5161.9  418.26
  5232.1  423.70  5508.9  430.02  5606.2  428.38  5712.2  433.18  5720.6  432.97
#Mann=7,-1,0
  4185.0    0.05       0  4246.1    0.08       0  4349.0    0.05       0
  4846.9     0.1       0  4995.7    0.07       0  5001.7     0.1       0
  5712.2    0.05       0
Bank Sta=4995.7,5001.7
Exp/Cntr=0.3,0.1

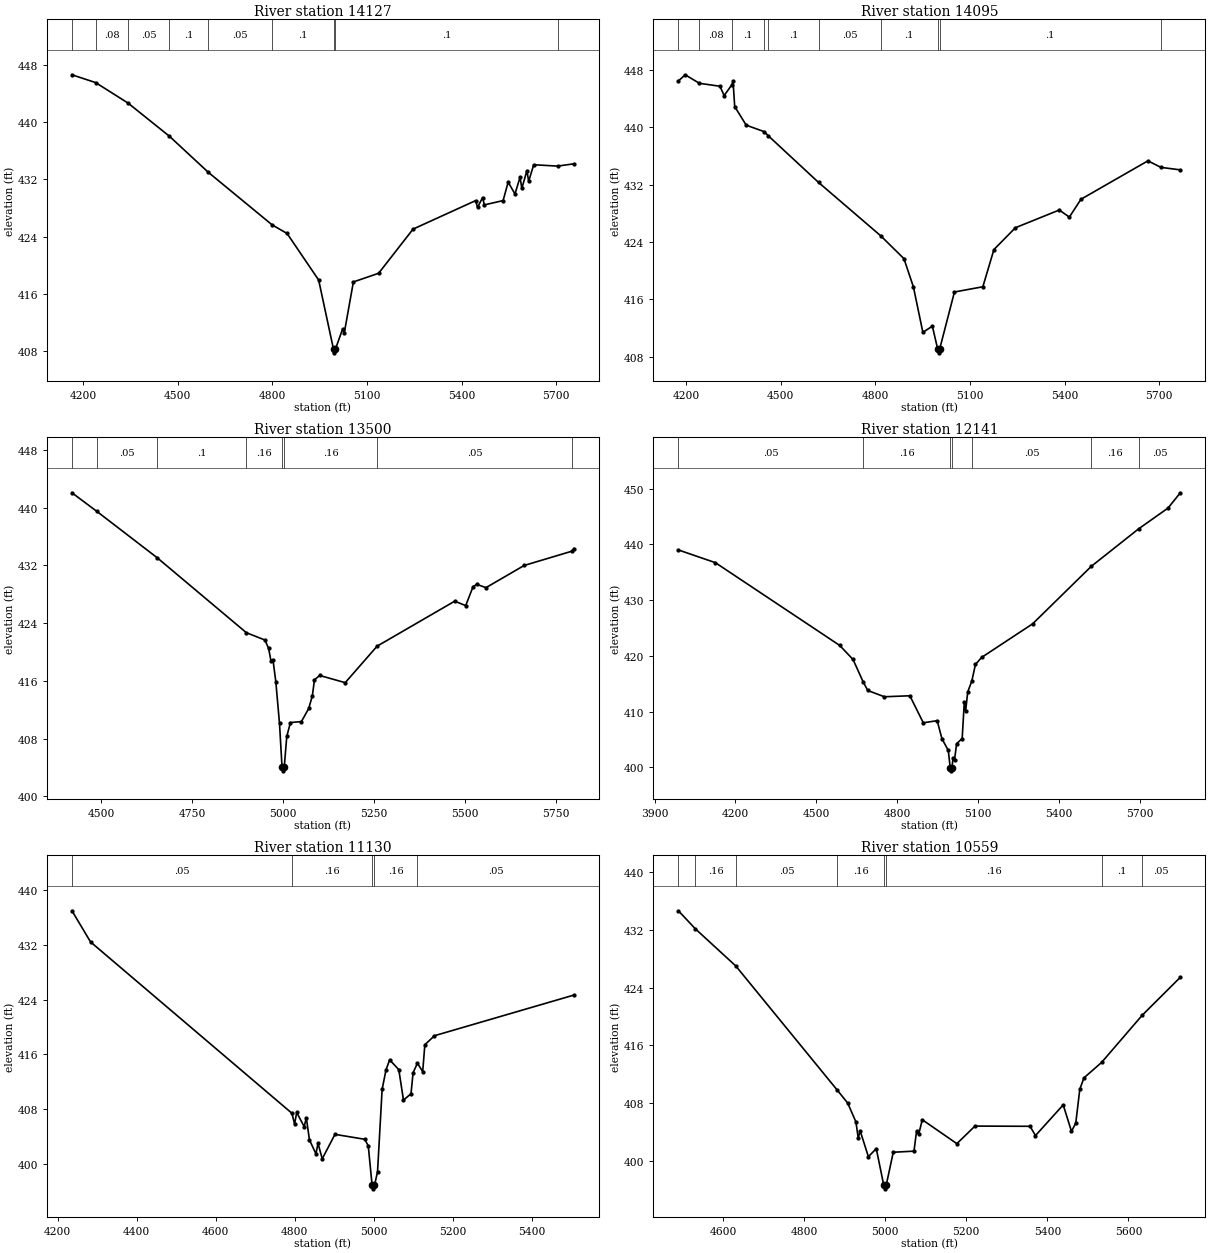
Type RM Length L Ch R = 1,14127,32,32,32
BEGIN DESCRIPTION:
UNT0175 IN SAND CR 25.0
END DESCRIPTION:
XS GIS Cut Line= 5
      3564919.88     10505576.10      3564437.28     10505694.14
      3563933.81     10505711.51      3563763.67     10505767.06
      3563404.17     10505967.55
#Sta/Elev= 30
  4164.9  446.57  4240.0  445.48  4342.8  442.62  4473.8  438.00  4597.3  432.96
  4799.6  425.63  4847.0  424.43  4947.1  417.93  4994.1  408.28  4996.9  407.78
  5000.1  408.28  5023.2  411.13  5028.2  410.54  5057.1  417.67  5137.2  418.88
  5246.3  425.04  5444.9  429.02  5450.7  428.07  5466.7  429.44  5472.4  428.42
  5531.8  429.02  5547.8  431.59  5569.5  429.94  5585.5  432.28  5591.2  430.72
  5607.2  433.19  5612.9  431.72  5628.9  434.02  5704.7  433.83  5756.1  434.15
#Mann=9,-1,0
  4164.9     0.1       0  4240.0    0.08       0  4342.8    0.05       0
  4473.8     0.1       0  4597.3    0.05       0  4799.6     0.1       0
  4994.1    0.07       0  5000.1     0.1       0  5704.7    0.05       0
Bank Sta=4994.1,5000.1
Exp/Cntr=0.3,0.1

Type RM Length L Ch R = 1,14095,595,595,595
BEGIN DESCRIPTION:
UNT0175 IN SAND CR 25.1
END DESCRIPTION:
XS GIS Cut Line= 5
      3564912.95     10505544.84      3564430.34     10505662.89
      3563926.86     10505680.26      3563756.72     10505735.81
      3563396.90     10505936.49
#Sta/Elev= 30
  4175.6  446.48  4197.1  447.34  4242.2  446.15  4307.3  445.74  4320.6  444.44
  4345.0  445.94  4348.9  446.41  4354.1  442.90  4390.6  440.31  4447.8  439.40
  4460.3  438.84  4620.2  432.31  4817.4  424.86  4890.8  421.68  4920.8  417.74
  4950.8  411.40  4980.9  412.26  4997.9  409.04  5000.6  408.54  5003.9  409.04
  5050.9  417.03  5141.0  417.76  5176.1  422.95  5244.3  426.00  5383.4  428.47
  5415.3  427.48  5452.1  429.97  5664.4  435.33  5705.9  434.42  5767.2  434.07
#Mann=10,-1,0
  4175.6     0.1       0  4242.2    0.08       0  4345.0     0.1       0
  4447.8    0.05       0  4460.3     0.1       0  4620.2    0.05       0
  4817.4     0.1       0  4997.9    0.07       0  5003.9     0.1       0
  5705.9    0.05       0
Bank Sta=4997.9,5003.9
Exp/Cntr=0.3,0.1

Type RM Length L Ch R = 1,13500,1359,1359,1359
BEGIN DESCRIPTION:
UNT0175 IN SAND CR 23.0
END DESCRIPTION:
XS GIS Cut Line= 2
      3564750.52     10505070.01      3563375.89     10505187.09
#Sta/Elev= 30
  4419.3  442.04  4487.8  439.46  4653.4  433.05  4898.8  422.66  4949.6  421.65
  4959.7  420.51  4966.7  418.68  4971.8  418.94  4979.7  415.86  4989.8  410.09
  4996.8  404.03  4999.6  403.53  5002.8  404.03  5009.8  408.30  5019.9  410.22
  5050.0  410.35  5070.1  412.17  5080.1  413.92  5085.9  416.13  5100.2  416.74
  5170.4  415.74  5258.2  420.80  5471.5  427.03  5501.6  426.41  5521.7  429.02
  5531.7  429.36  5557.4  428.90  5662.2  431.97  5794.8  433.97  5798.9  434.32
#Mann=8,-1,0
  4419.3     0.1       0  4487.8    0.05       0  4653.4     0.1       0
  4898.8    0.16       0  4996.8    0.07       0  5002.8    0.16       0
  5258.2    0.05       0  5794.8    0.16       0
Bank Sta=4996.8,5002.8
Exp/Cntr=0.3,0.1

Type RM Length L Ch R = 1,12141,1011,1011,1011
BEGIN DESCRIPTION:
UNT0175 IN SAND CR 22.0
END DESCRIPTION:
XS GIS Cut Line= 3
      3564826.98     10504879.87      3564320.02     10504452.78
      3563156.98     10504164.62
#Sta/Elev= 30
  3988.5  439.01  4125.6  436.73  4586.6  421.88  4636.0  419.36  4673.2  415.38
  4690.5  413.80  4752.3  412.67  4846.7  412.85  4896.5  408.00  4948.0  408.38
  4965.7  405.14  4989.2  403.05  4996.5  399.88  4999.3  399.38  5002.5  399.88
  5007.1  401.67  5012.3  401.33  5020.1  404.26  5040.7  405.16  5048.5  411.66
  5053.7  410.20  5061.3  413.54  5076.6  415.52  5089.9  418.47  5112.8  419.73
  5302.0  425.76  5519.4  436.07  5694.7  442.79  5803.9  446.52  5849.6  449.27
#Mann=7,-1,0
  3988.5    0.05       0  4673.2    0.16       0  4996.5    0.07       0
  5002.5    0.16       0  5076.6    0.05       0  5519.4    0.16       0
  5694.7    0.05       0
Bank Sta=4996.5,5002.5
Exp/Cntr=0.3,0.1

Type RM Length L Ch R = 1,11130,571,571,571
BEGIN DESCRIPTION:
UNT0175 IN SAND CR 20.0
END DESCRIPTION:
XS GIS Cut Line= 2
      3564950.10     10503824.34      3563770.86     10503356.11
#Sta/Elev= 30
  4236.5  436.96  4283.6  432.41  4792.5  407.42  4799.3  405.85  4804.7  407.54
  4823.6  405.46  4829.0  406.76  4836.9  403.53  4853.3  401.50  4858.6  403.03
  4869.2  400.77  4901.4  404.34  4976.7  403.62  4985.6  402.66  4995.3  396.89
  4998.0  396.39  5001.3  396.89  5009.0  398.87  5020.6  410.90  5030.5  413.76
  5039.6  415.21  5062.8  413.78  5074.6  409.33  5093.6  410.27  5098.9  413.33
  5109.8  414.72  5123.2  413.50  5128.6  417.41  5152.9  418.73  5505.3  424.66
#Mann=5,-1,0
  4236.5    0.05       0  4792.5    0.16       0  4995.3    0.07       0
  5001.3    0.16       0  5109.8    0.05       0
Bank Sta=4995.3,5001.3
Exp/Cntr=0.3,0.1

Type RM Length L Ch R = 1,10559,1064,1064,1064
BEGIN DESCRIPTION:
UNT0175 IN SAND CR 18.0
END DESCRIPTION:
XS GIS Cut Line= 2
      3564980.48     10503238.41      3563769.56     10502982.34
#Sta/Elev= 30
  4490.1  434.66  4531.4  432.18  4631.6  427.00  4882.1  409.75  4907.5  407.98
  4927.9  405.35  4933.4  403.15  4938.5  404.08  4958.6  400.53  4978.0  401.65
  4996.5  396.57  4999.2  396.07  5002.5  396.57  5019.9  401.15  5071.0  401.30
  5077.4  404.10  5082.5  403.62  5091.5  405.66  5176.8  402.34  5221.4  404.78
  5357.2  404.75  5370.6  403.46  5439.0  407.72  5459.4  404.05  5470.0  405.20
  5479.9  409.88  5490.1  411.47  5533.6  413.61  5633.8  420.16  5727.8  425.43
#Mann=8,-1,0
  4490.1     0.1       0  4531.4    0.16       0  4631.6    0.05       0
  4882.1    0.16       0  4996.5    0.07       0  5002.5    0.16       0
  5533.6     0.1       0  5633.8    0.05       0
Bank Sta=4996.5,5002.5
Exp/Cntr=0.3,0.1

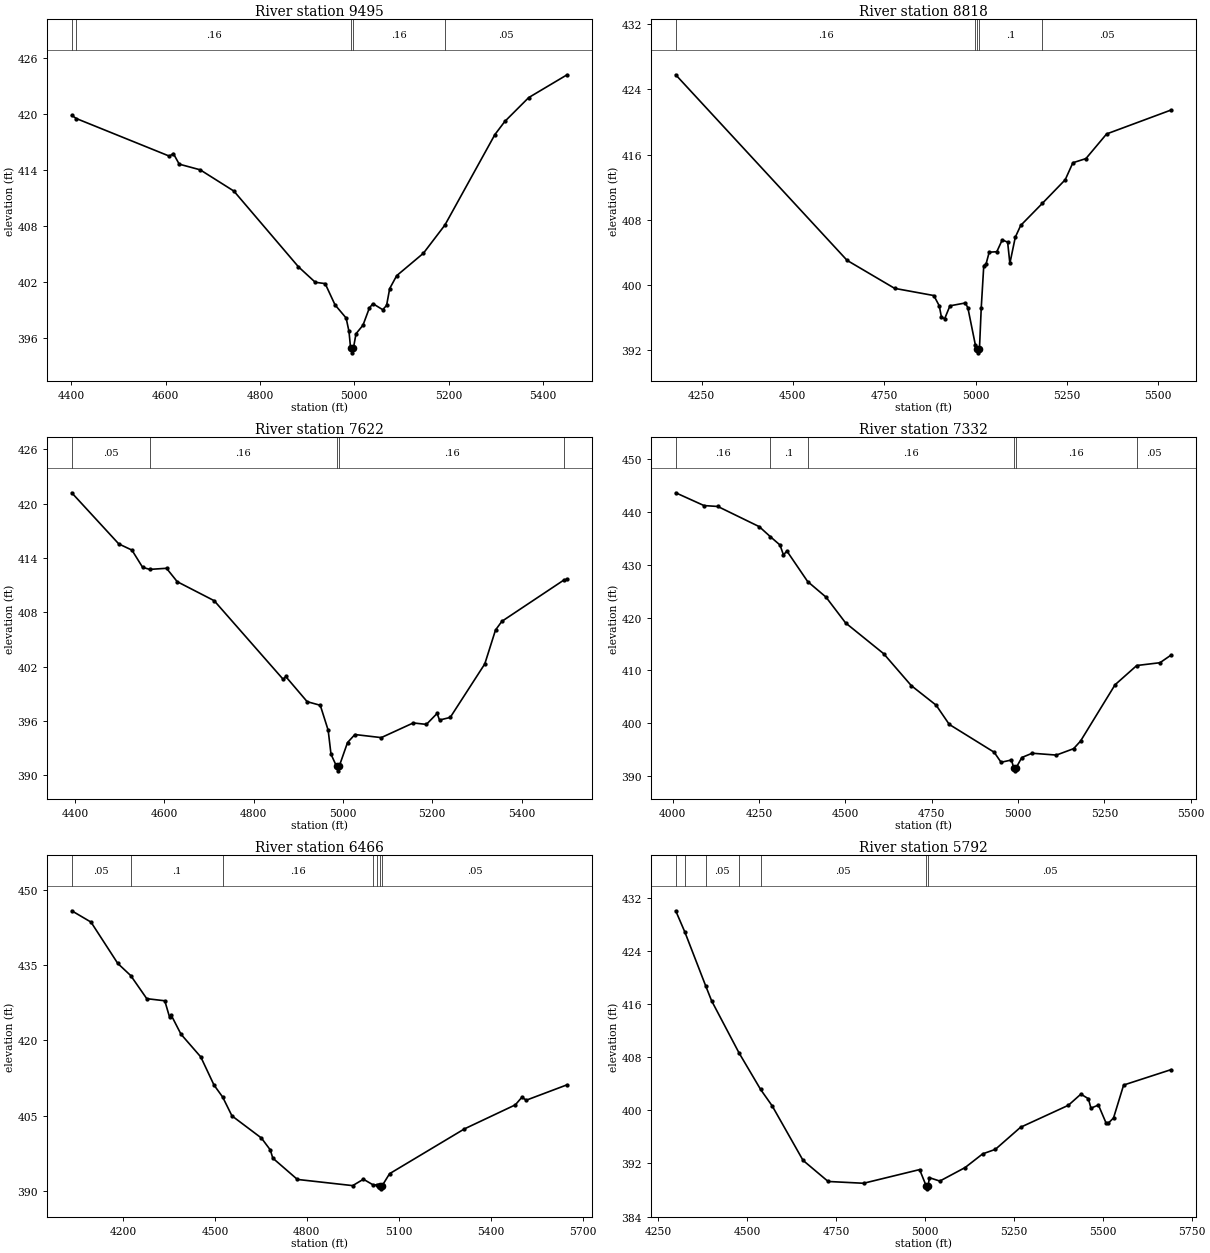
Type RM Length L Ch R = 1,9495,677,677,677
BEGIN DESCRIPTION:
UNT0175 IN SAND CR 16.0
END DESCRIPTION:
XS GIS Cut Line= 2
      3564698.36     10502904.19      3563838.99     10502300.89
#Sta/Elev= 30
  4401.0  419.87  4410.9  419.52  4607.9  415.49  4616.4  415.77  4628.8  414.63
  4673.3  414.02  4744.7  411.74  4881.6  403.61  4917.3  401.95  4938.2  401.81
  4959.1  399.53  4982.6  398.12  4988.7  396.68  4992.1  394.88  4994.9  394.38
  4998.1  394.88  5003.6  396.43  5018.4  397.35  5031.8  399.18  5039.3  399.66
  5060.2  399.01  5068.4  399.47  5075.0  401.28  5089.8  402.66  5146.5  405.07
  5192.0  408.09  5298.1  417.81  5319.0  419.21  5369.6  421.77  5451.0  424.22
#Mann=5,-1,0
  4401.0    0.05       0  4410.9    0.16       0  4992.1    0.07       0
  4998.1    0.16       0  5192.0    0.05       0
Bank Sta=4992.1,4998.1
Exp/Cntr=0.3,0.1

Type RM Length L Ch R = 1,8818,1196,1196,1196
BEGIN DESCRIPTION:
UNT0175 IN SAND CR 15.0
END DESCRIPTION:
XS GIS Cut Line= 2
      3564925.35     10502412.94      3563817.75     10501631.72
#Sta/Elev= 30
  4179.4  425.78  4648.4  403.04  4778.5  399.61  4885.7  398.73  4900.5  397.48
  4906.6  396.08  4915.3  395.88  4929.8  397.47  4971.9  397.82  4978.8  397.24
  4999.5  392.65  5004.6  392.21  5007.3  391.71  5010.6  392.21  5015.5  397.25
  5022.4  402.41  5028.5  402.57  5037.2  404.04  5058.1  404.10  5072.9  405.55
  5087.7  405.27  5093.8  402.67  5108.6  405.87  5123.4  407.32  5183.0  410.04
  5245.3  412.92  5266.2  415.00  5301.9  415.51  5358.5  418.53  5534.8  421.46
#Mann=5,-1,0
  4179.4    0.16       0  4999.5     0.1       0  5004.6    0.07       0
  5010.6     0.1       0  5183.0    0.05       0
Bank Sta=5004.6,5010.6
Exp/Cntr=0.3,0.1

Type RM Length L Ch R = 1,7622,290,290,290
BEGIN DESCRIPTION:
UNT0175 IN SAND CR 13.0
END DESCRIPTION:
XS GIS Cut Line= 2
      3565113.75     10501366.96      3564086.92     10500946.70
#Sta/Elev= 30
  4392.4  421.20  4497.8  415.55  4527.2  414.87  4551.2  412.96  4567.2  412.74
  4604.7  412.86  4628.7  411.38  4711.5  409.28  4866.3  400.58  4871.7  400.91
  4919.7  398.13  4949.1  397.73  4966.8  394.97  4973.1  392.33  4985.5  390.99
  4988.2  390.49  4991.5  390.99  5010.1  393.61  5026.6  394.50  5085.7  394.16
  5157.4  395.78  5186.8  395.62  5210.8  396.83  5216.2  396.10  5240.2  396.39
  5317.6  402.30  5341.6  406.04  5355.8  407.00  5495.3  411.58  5501.9  411.65
#Mann=5,-1,0
  4392.4    0.05       0  4567.2    0.16       0  4985.5    0.07       0
  4991.5    0.16       0  5495.3    0.05       0
Bank Sta=4985.5,4991.5
Exp/Cntr=0.3,0.1

Type RM Length L Ch R = 1,7332,866,866,866
BEGIN DESCRIPTION:
UNT0175 IN SAND CR 11.0
END DESCRIPTION:
XS GIS Cut Line= 2
      3565504.06     10500890.28      3564070.07     10500845.14
#Sta/Elev= 30
  4008.2  443.60  4090.2  441.18  4130.2  441.01  4250.3  437.19  4282.1  435.31
  4310.3  433.72  4320.3  431.85  4330.3  432.58  4390.4  426.81  4443.5  423.87
  4500.4  418.98  4610.5  413.17  4690.5  407.13  4762.5  403.43  4800.6  399.79
  4930.6  394.53  4950.6  392.63  4980.6  393.06  4987.6  391.51  4990.4  391.01
  4993.6  391.51  5010.7  393.53  5040.7  394.34  5110.7  393.99  5160.7  395.20
  5180.7  396.63  5280.8  407.29  5343.6  410.93  5410.9  411.46  5442.9  412.90
#Mann=6,-1,0
  4008.2    0.16       0  4282.1     0.1       0  4390.4    0.16       0
  4987.6    0.07       0  4993.6    0.16       0  5343.6    0.05       0
Bank Sta=4987.6,4993.6
Exp/Cntr=0.3,0.1

Type RM Length L Ch R = 1,6466,674,674,674
BEGIN DESCRIPTION:
UNT0175 IN SAND CR 10.0
END DESCRIPTION:
XS GIS Cut Line= 4
      3565202.01     10499685.39      3564462.38     10500115.97
      3564271.41     10500286.11      3563994.66     10500708.16
#Sta/Elev= 30
  4032.8  445.77  4095.6  443.52  4183.1  435.29  4225.3  432.88  4277.6  428.29
  4336.4  427.87  4352.1  424.59  4357.9  424.95  4389.3  421.22  4453.9  416.70
  4496.9  411.12  4525.3  408.72  4555.6  404.98  4651.6  400.58  4680.7  398.21
  4688.8  396.58  4769.1  392.34  4949.5  391.11  4984.6  392.38  5017.4  391.21
  5030.0  391.28  5038.5  390.97  5041.2  390.47  5044.5  390.97  5069.9  393.48
  5314.4  402.40  5480.2  407.17  5501.3  408.66  5516.4  408.11  5649.1  411.16
#Mann=7,-1,0
  4032.8    0.05       0  4225.3     0.1       0  4525.3    0.16       0
  5017.4     0.1       0  5030.0    0.05       0  5038.5    0.07       0
  5044.5    0.05       0
Bank Sta=5038.5,5044.5
Exp/Cntr=0.3,0.1

Type RM Length L Ch R = 1,5792,32,32,32
BEGIN DESCRIPTION:
UNT0175 IN SAND CR 8.3
END DESCRIPTION:
XS GIS Cut Line= 4
      3564565.44     10499313.55      3564042.42     10499719.39
      3563988.16     10499797.51      3563521.58     10500229.38
#Sta/Elev= 30
  4299.1  430.07  4324.8  426.87  4383.0  418.81  4400.1  416.50  4477.1  408.66
  4537.8  403.15  4570.3  400.68  4657.2  392.46  4727.8  389.28  4827.4  389.01
  4985.0  391.07  5003.0  388.67  5005.7  388.17  5009.0  388.67  5012.6  389.85
  5041.8  389.34  5113.0  391.38  5162.3  393.44  5198.0  394.12  5268.9  397.45
  5403.3  400.76  5438.5  402.44  5459.6  401.75  5466.8  400.32  5487.8  400.80
  5509.3  398.09  5516.1  398.09  5530.3  398.85  5558.7  403.81  5692.0  406.13
#Mann=7,-1,0
  4299.1    0.05       0  4324.8    0.16       0  4383.0    0.05       0
  4477.1    0.16       0  4537.8    0.05       0  5003.0    0.03       0
  5009.0    0.05       0
Bank Sta=5003,5009
Exp/Cntr=0.3,0.1

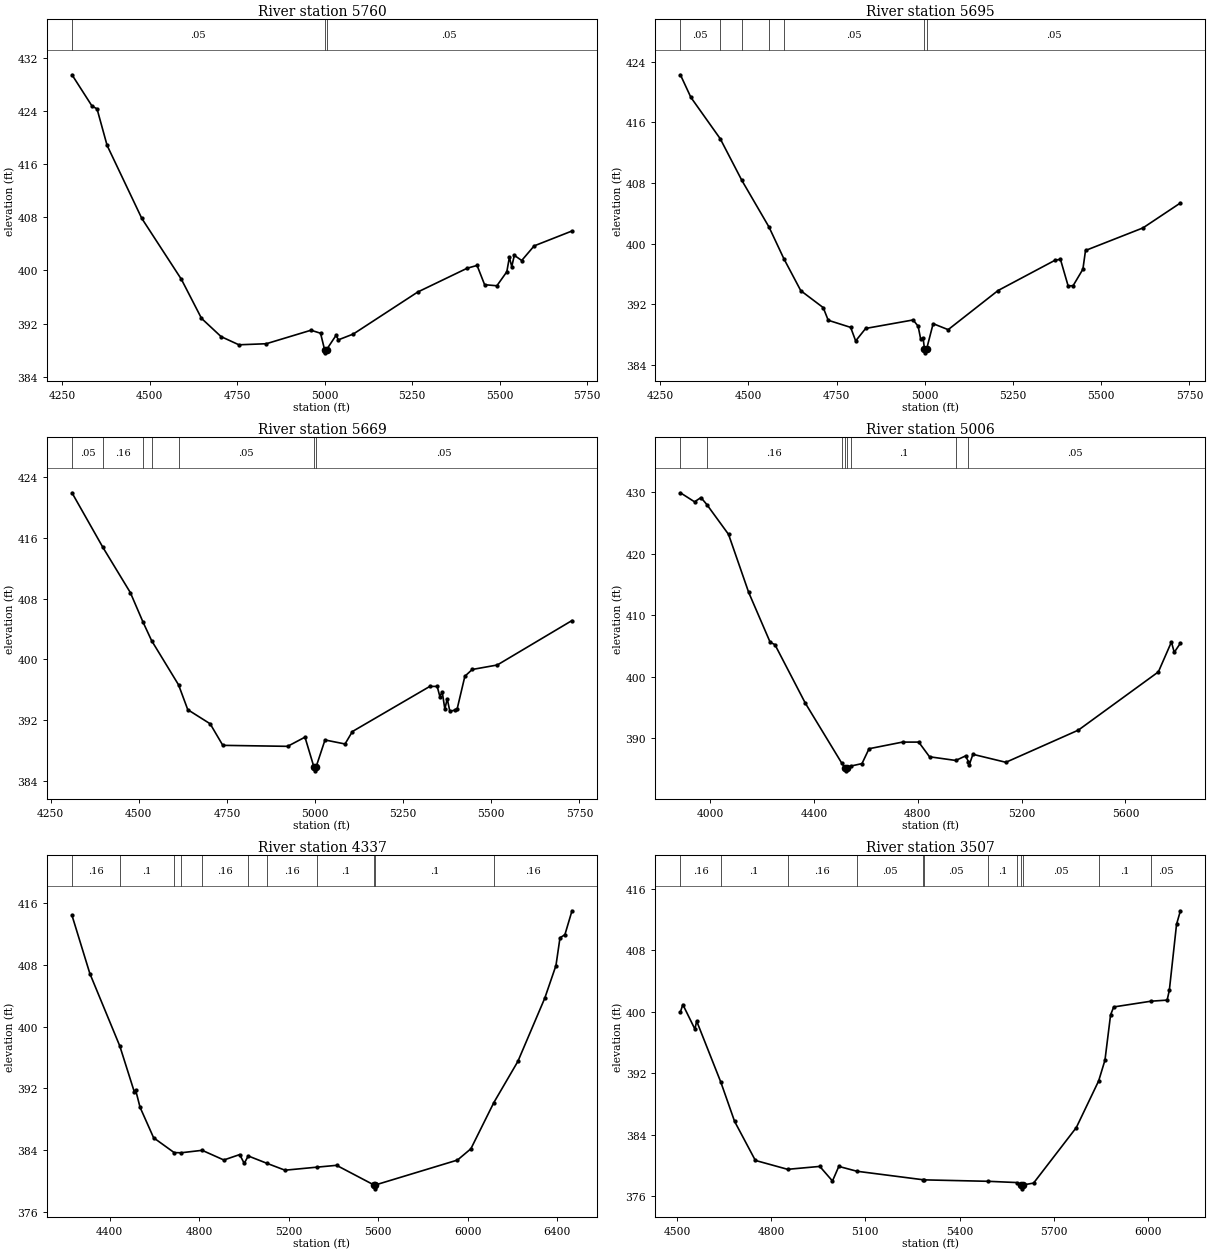
Type RM Length L Ch R = 1,5760,65,65,65
BEGIN DESCRIPTION:
UNT0175 IN SAND CR 8.0
END DESCRIPTION:
XS GIS Cut Line= 4
      3564560.82     10499269.90      3564017.29     10499717.37
      3563973.02     10499746.01      3563483.43     10500206.09
#Sta/Elev= 30
  4278.2  429.44  4335.4  424.74  4349.8  424.31  4378.5  418.82  4477.5  407.85
  4590.8  398.67  4648.2  392.80  4704.2  390.05  4755.1  388.82  4833.3  388.98
  4961.0  391.01  4988.4  390.56  4999.8  388.11  5002.5  387.61  5005.8  388.11
  5032.5  390.23  5039.5  389.57  5082.0  390.44  5266.1  396.76  5407.3  400.34
  5435.6  400.76  5457.1  397.86  5492.2  397.70  5520.6  399.81  5527.9  401.98
  5534.7  400.57  5542.0  402.28  5563.1  401.50  5598.7  403.70  5706.8  405.94
#Mann=3,-1,0
  4278.2    0.05       0  4999.8    0.03       0  5005.8    0.05       0
Bank Sta=4999.8,5005.8
Exp/Cntr=0.3,0.1

Type RM Length L Ch R = 1,5695,26,26,26
BEGIN DESCRIPTION:
UNT0175 IN SAND CR 8.1
END DESCRIPTION:
XS GIS Cut Line= 2
      3564487.33     10499205.03      3563436.56     10500156.14
#Sta/Elev= 30
  4307.2  422.29  4336.9  419.31  4420.1  413.85  4481.4  408.35  4558.4  402.19
  4600.3  398.03  4648.5  393.79  4712.0  391.56  4726.2  389.89  4789.8  388.95
  4804.0  387.16  4832.3  388.81  4966.8  389.93  4981.0  389.11  4988.5  387.36
  4995.2  387.52  4999.1  386.09  5001.9  385.59  5005.1  386.09  5023.6  389.44
  5066.2  388.65  5207.5  393.81  5370.3  397.84  5384.5  397.92  5406.2  394.43
  5420.3  394.45  5448.1  396.63  5455.5  399.10  5618.4  402.08  5724.5  405.37
#Mann=7,-1,0
  4307.2    0.05       0  4420.1    0.16       0  4481.4    0.05       0
  4558.4    0.16       0  4600.3    0.05       0  4999.1    0.03       0
  5005.1    0.05       0
Bank Sta=4999.1,5005.1
Exp/Cntr=0.3,0.1

Type RM Length L Ch R = 1,5669,663,663,663
BEGIN DESCRIPTION:
UNT0175 IN SAND CR 8.2
END DESCRIPTION:
XS GIS Cut Line= 2
      3564469.94     10499185.53      3563418.28     10500137.44
#Sta/Elev= 30
  4310.3  421.95  4397.8  414.77  4475.9  408.79  4511.4  404.95  4536.1  402.47
  4612.7  396.63  4638.8  393.36  4702.3  391.50  4738.2  388.66  4922.0  388.53
  4971.3  389.74  4996.7  385.80  4999.5  385.30  5002.7  385.80  5028.1  389.37
  5084.9  388.84  5105.8  390.48  5325.5  396.43  5346.4  396.43  5353.9  395.09
  5360.6  395.71  5368.1  393.44  5374.8  394.80  5382.3  393.14  5396.5  393.31
  5403.2  393.50  5424.9  397.77  5445.8  398.66  5516.8  399.25  5728.8  405.11
#Mann=7,-1,0
  4310.3    0.05       0  4397.8    0.16       0  4511.4    0.05       0
  4536.1    0.16       0  4612.7    0.05       0  4996.7    0.03       0
  5002.7    0.05       0
Bank Sta=4996.7,5002.7
Exp/Cntr=0.3,0.1

Type RM Length L Ch R = 1,5006,669,669,669
BEGIN DESCRIPTION:
UNT0175 IN SAND CR 6.0
END DESCRIPTION:
XS GIS Cut Line= 4
      3564514.43     10498925.01      3563563.08     10499199.30
      3563316.55     10499466.66      3563254.06     10500036.07
#Sta/Elev= 30
  3885.1  429.92  3939.6  428.45  3964.4  429.14  3987.0  428.00  4070.6  423.15
  4148.3  413.69  4231.0  405.58  4249.3  405.20  4366.3  395.68  4507.3  385.87
  4519.4  385.15  4522.1  384.65  4525.4  385.15  4542.1  385.43  4584.8  385.83
  4611.9  388.25  4740.9  389.33  4803.4  389.33  4845.0  386.94  4946.1  386.34
  4983.8  387.08  4995.1  386.13  4998.0  385.62  5012.2  387.34  5139.2  386.04
  5418.5  391.28  5726.8  400.76  5777.1  405.63  5787.9  403.94  5811.7  405.43
#Mann=8,-1,0
  3885.1     0.1       0  3987.0    0.16       0  4507.3    0.05       0
  4519.4    0.03       0  4525.4    0.05       0  4542.1     0.1       0
  4946.1    0.16       0  4995.1    0.05       0
Bank Sta=4519.4,4525.4
Exp/Cntr=0.3,0.1

Type RM Length L Ch R = 1,4337,830,830,830
BEGIN DESCRIPTION:
UNT0175 IN SAND CR 5.0
END DESCRIPTION:
XS GIS Cut Line= 3
      3564022.64     10498613.88      3563036.52     10498766.66
      3561800.38     10498787.49
#Sta/Elev= 30
  4231.3  414.38  4311.2  406.85  4445.0  397.48  4510.4  391.50  4515.4  391.83
  4535.4  389.57  4596.1  385.62  4687.7  383.71  4717.9  383.68  4813.0  384.00
  4909.8  382.75  4980.7  383.45  5000.9  382.31  5018.9  383.27  5101.4  382.33
  5183.1  381.43  5324.9  381.82  5413.6  382.06  5580.6  379.52  5583.4  379.02
  5586.6  379.52  5953.7  382.74  6013.7  384.20  6116.4  390.18  6223.7  395.50
  6343.8  403.67  6393.8  407.89  6411.9  411.48  6433.8  411.88  6465.5  414.97
#Mann=11,-1,0
  4231.3    0.16       0  4445.0     0.1       0  4687.7    0.05       0
  4717.9     0.1       0  4813.0    0.16       0  5018.9     0.1       0
  5101.4    0.16       0  5324.9     0.1       0  5580.6    0.07       0
  5586.6     0.1       0  6116.4    0.16       0
Bank Sta=5580.6,5586.6
Exp/Cntr=0.3,0.1

Type RM Length L Ch R = 1,3507,47,47,47
BEGIN DESCRIPTION:
UNT0175 IN SAND CR 4.4
END DESCRIPTION:
XS GIS Cut Line= 5
      3563576.75     10498298.81      3563201.77     10498100.90
      3563069.82     10498120.00      3562312.88     10498352.64
      3562069.79     10498345.70
#Sta/Elev= 30
  4511.1  399.96  4518.9  400.92  4557.3  397.72  4562.9  398.77  4640.1  390.79
  4683.7  385.71  4749.8  380.63  4852.6  379.47  4955.0  379.85  4995.4  377.95
  5015.6  379.85  5073.2  379.22  5282.6  378.12  5285.4  378.10  5492.0  377.91
  5581.5  377.75  5595.0  377.43  5597.7  376.93  5601.0  377.43  5635.9  377.68
  5772.0  384.91  5843.1  390.98  5863.2  393.68  5881.1  399.58  5891.1  400.61
  6010.2  401.36  6061.2  401.50  6068.2  402.77  6091.2  411.37  6103.5  413.13
#Mann=12,-1,0
  4511.1    0.16       0  4640.1     0.1       0  4852.6    0.16       0
  5073.2    0.05       0  5282.6     0.1       0  5285.4    0.05       0
  5492.0     0.1       0  5581.5    0.05       0  5595.0    0.07       0
  5601.0    0.05       0  5843.1     0.1       0  6010.2    0.05       0
Bank Sta=5595,5601
Exp/Cntr=0.3,0.1

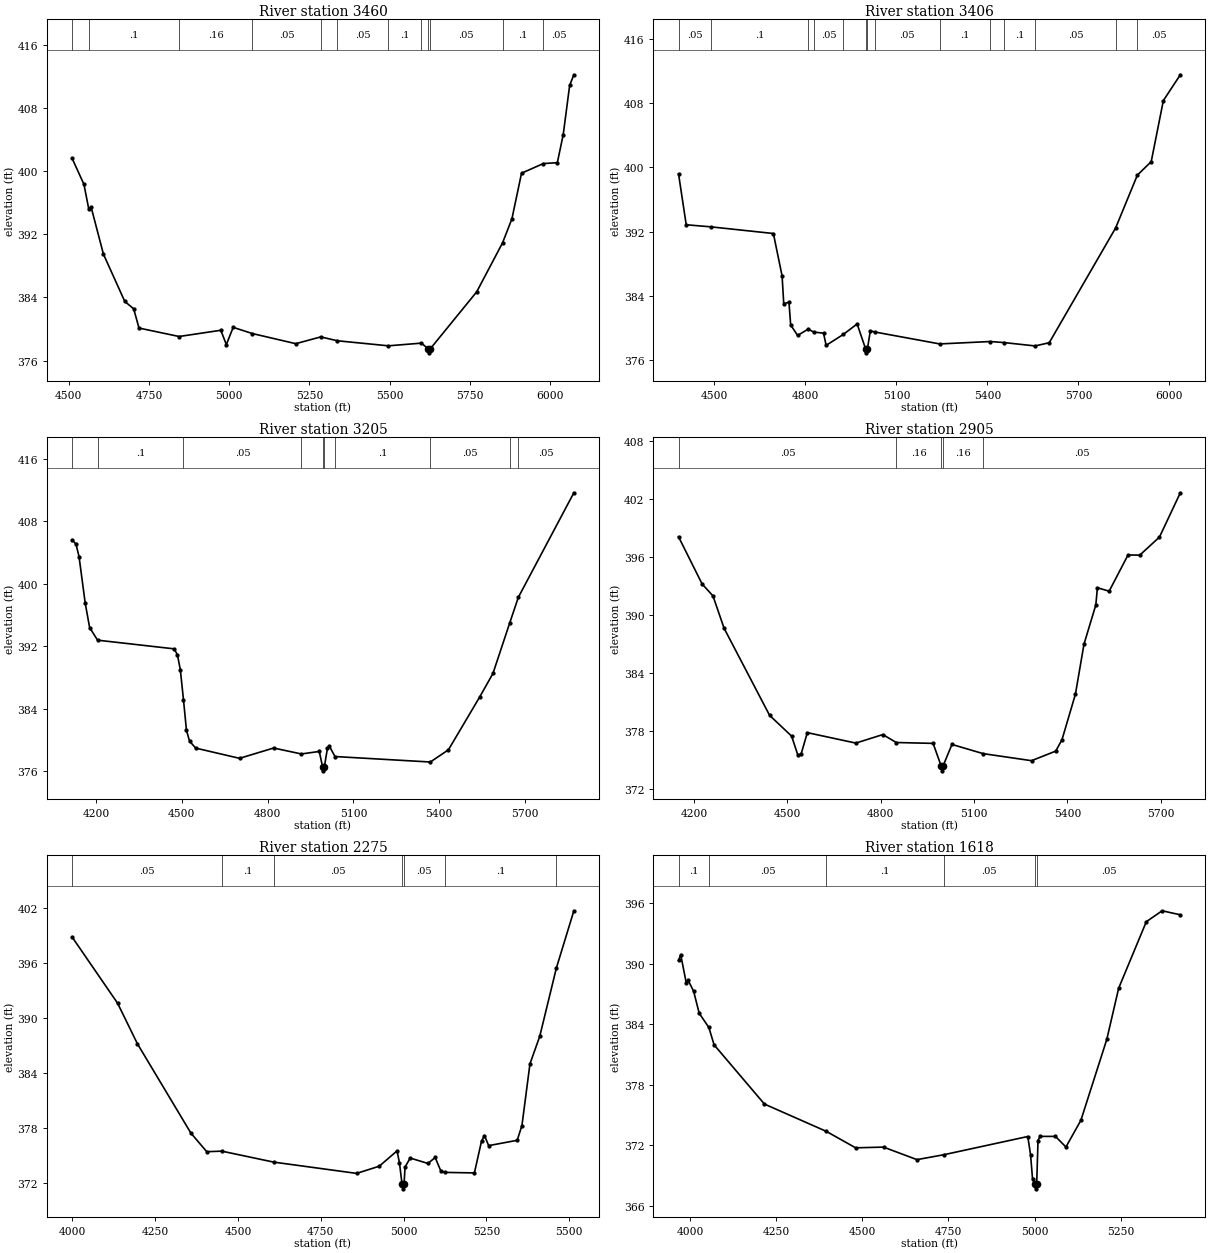
Type RM Length L Ch R = 1,3460,54,54,54
BEGIN DESCRIPTION:
UNT0175 IN SAND CR 4.1
END DESCRIPTION:
XS GIS Cut Line= 6
      3563541.73     10498252.77      3563315.17     10498135.58
      3563221.42     10498034.02      3562744.85     10498208.50
      3562307.35     10498320.48      3562099.04     10498315.27
#Sta/Elev= 30
  4510.5  401.63  4547.5  398.33  4562.5  395.21  4569.7  395.47  4608.3  389.48
  4674.8  383.49  4702.5  382.56  4719.1  380.12  4844.1  379.05  4974.1  379.84
  4991.3  378.02  5012.6  380.21  5071.9  379.43  5207.7  378.14  5285.6  379.00
  5337.3  378.51  5496.3  377.87  5599.4  378.21  5620.7  377.48  5623.5  376.98
  5626.7  377.48  5771.6  384.71  5852.1  390.91  5881.3  393.95  5911.3  399.74
  5979.3  400.96  6022.9  401.07  6041.3  404.64  6061.3  410.87  6074.4  412.21
#Mann=12,-1,0
  4510.5    0.16       0  4562.5     0.1       0  4844.1    0.16       0
  5071.9    0.05       0  5285.6     0.1       0  5337.3    0.05       0
  5496.3     0.1       0  5599.4    0.05       0  5620.7    0.07       0
  5626.7    0.05       0  5852.1     0.1       0  5979.3    0.05       0
Bank Sta=5620.7,5626.7
Exp/Cntr=0.3,0.1

Type RM Length L Ch R = 1,3406,201,201,201
BEGIN DESCRIPTION:
UNT0175 IN SAND CR 4.2
END DESCRIPTION:
XS GIS Cut Line= 6
      3563655.01     10498192.44      3563212.30     10497984.11
      3563145.03     10498003.64      3562720.11     10498175.51
      3562309.52     10498275.34      3562096.12     10498272.75
#Sta/Elev= 30
  4381.5  399.20  4406.8  392.85  4488.1  392.59  4694.2  391.76  4722.9  386.48
  4728.4  383.01  4745.6  383.20  4751.2  380.37  4774.0  379.06  4809.3  379.85
  4826.8  379.48  4859.6  379.34  4868.1  377.82  4925.0  379.19  4970.3  380.49
  4998.2  377.39  5000.9  376.89  5004.2  377.39  5013.9  379.63  5028.4  379.49
  5242.6  378.00  5409.5  378.30  5454.5  378.17  5557.2  377.75  5603.7  378.15
  5822.7  392.46  5894.3  399.04  5939.9  400.71  5979.9  408.32  6035.9  411.54
#Mann=14,-1,0
  4381.5    0.05       0  4488.1     0.1       0  4809.3    0.16       0
  4826.8    0.05       0  4925.0    0.16       0  4998.2    0.07       0
  5004.2    0.16       0  5028.4    0.05       0  5242.6     0.1       0
  5409.5    0.05       0  5454.5     0.1       0  5557.2    0.05       0
  5822.7     0.1       0  5894.3    0.05       0
Bank Sta=4998.2,5004.2
Exp/Cntr=0.3,0.1

Type RM Length L Ch R = 1,3205,300,300,300
BEGIN DESCRIPTION:
UNT0175 IN SAND CR 4.3
END DESCRIPTION:
XS GIS Cut Line= 6
      3563724.84     10498148.72      3563172.72     10497933.43
      3562960.91     10497971.62      3562703.97     10498134.82
      3562297.72     10498242.46      3562076.32     10498239.00
#Sta/Elev= 30
  4116.0  405.65  4129.7  405.09  4140.4  403.49  4161.9  397.55  4177.4  394.41
  4205.2  392.80  4473.1  391.69  4484.4  390.93  4494.6  389.04  4505.6  385.20
  4516.1  381.27  4526.8  379.89  4548.3  378.99  4701.8  377.68  4821.0  379.00
  4917.9  378.24  4980.6  378.56  4992.3  376.58  4995.0  376.08  4998.3  376.58
  5009.2  378.95  5016.1  379.23  5035.6  377.91  5369.1  377.21  5432.4  378.77
  5541.7  385.53  5588.1  388.54  5647.2  395.05  5677.0  398.29  5871.1  411.66
#Mann=10,-1,0
  4116.0    0.05       0  4205.2     0.1       0  4505.6    0.05       0
  4917.9    0.16       0  4992.3    0.07       0  4998.3    0.16       0
  5035.6     0.1       0  5369.1    0.05       0  5647.2     0.1       0
  5677.0    0.05       0
Bank Sta=4992.3,4998.3
Exp/Cntr=0.3,0.1

Type RM Length L Ch R = 1,2905,630,630,630
BEGIN DESCRIPTION:
UNT0175 IN SAND CR 4.0
END DESCRIPTION:
XS GIS Cut Line= 2
      3563731.72     10497867.45      3562135.77     10497638.47
#Sta/Elev= 30
  4150.5  398.12  4226.2  393.24  4261.2  392.00  4296.8  388.66  4443.1  379.65
  4513.8  377.50  4534.0  375.53  4544.1  375.62  4564.3  377.86  4720.2  376.78
  4806.8  377.66  4850.2  376.84  4968.4  376.75  4994.4  374.41  4997.2  373.91
  5000.4  374.41  5029.0  376.64  5129.2  375.69  5284.7  374.96  5362.4  375.95
  5382.6  377.13  5425.8  381.85  5453.3  387.02  5491.3  391.07  5496.4  392.85
  5534.1  392.49  5594.8  396.24  5632.5  396.22  5695.8  398.09  5762.8  402.67
#Mann=5,-1,0
  4150.5    0.05       0  4850.2    0.16       0  4994.4    0.07       0
  5000.4    0.16       0  5129.2    0.05       0
Bank Sta=4994.4,5000.4
Exp/Cntr=0.3,0.1

Type RM Length L Ch R = 1,2275,657,657,657
BEGIN DESCRIPTION:
UNT0175 IN SAND CR 3.0
END DESCRIPTION:
XS GIS Cut Line= 2
      3563769.61     10497670.24      3562363.34     10497107.73
#Sta/Elev= 30
  3999.5  398.81  4136.8  391.61  4196.9  387.18  4358.4  377.46  4406.1  375.45
  4451.6  375.51  4607.7  374.32  4858.4  373.09  4926.6  373.87  4980.4  375.54
  4987.7  374.24  4995.5  371.91  4998.2  371.41  5001.5  371.91  5004.6  373.78
  5020.0  374.76  5073.8  374.17  5095.4  374.82  5112.3  373.38  5124.2  373.20
  5213.9  373.14  5235.4  376.60  5244.3  377.21  5256.9  376.11  5343.1  376.69
  5357.4  378.30  5381.6  385.01  5411.2  388.01  5461.3  395.43  5514.1  401.66
#Mann=7,-1,0
  3999.5    0.05       0  4451.6     0.1       0  4607.7    0.05       0
  4995.5    0.03       0  5001.5    0.05       0  5124.2     0.1       0
  5461.3    0.05       0
Bank Sta=4995.5,5001.5
Exp/Cntr=0.3,0.1

Type RM Length L Ch R = 1,1618,1360,1360,1360
BEGIN DESCRIPTION:
UNT0175 IN SAND CR 2.0
END DESCRIPTION:
XS GIS Cut Line= 2
      3563925.81     10497237.93      3562656.07     10496525.00
#Sta/Elev= 30
  3966.9  390.30  3973.2  390.88  3989.2  388.09  3994.9  388.33  4010.8  387.25
  4026.8  385.08  4054.9  383.67  4070.1  381.95  4216.2  376.09  4395.6  373.39
  4480.8  371.76  4561.8  371.83  4658.8  370.59  4736.0  371.07  4980.4  372.88
  4988.5  371.07  4994.2  368.69  5000.3  368.20  5003.1  367.70  5006.3  368.20
  5010.1  372.48  5015.9  372.89  5060.7  372.89  5091.1  371.84  5134.5  374.48
  5209.7  382.49  5244.2  387.56  5324.4  394.14  5370.3  395.22  5423.1  394.82
#Mann=6,-1,0
  3966.9     0.1       0  4054.9    0.05       0  4395.6     0.1       0
  4736.0    0.05       0  5000.3    0.03       0  5006.3    0.05       0
Bank Sta=5000.3,5006.3
Exp/Cntr=0.3,0.1

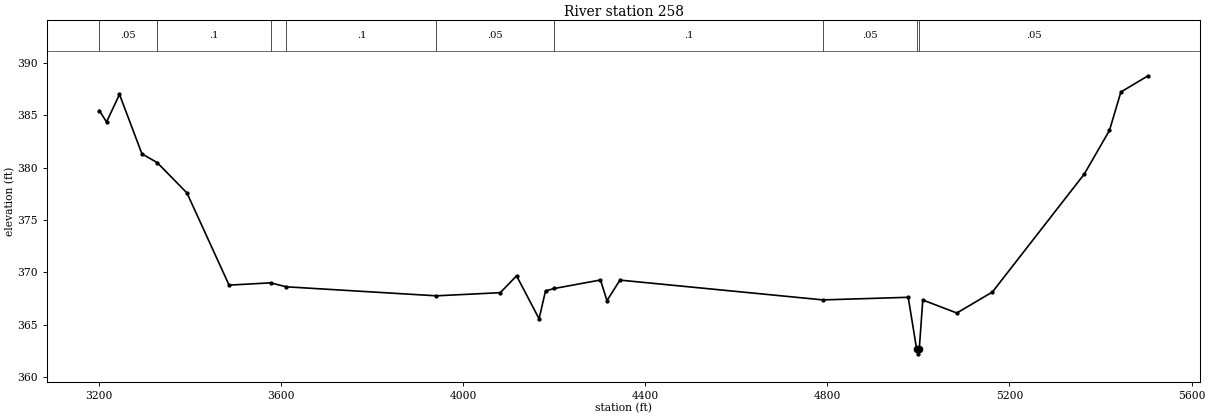
Type RM Length L Ch R = 1,258,0,0,0
BEGIN DESCRIPTION:
UNT0175 IN SAND CR 1.0
END DESCRIPTION:
XS GIS Cut Line= 4
      3563998.78     10496706.71      3563149.80     10495727.53
      3562821.68     10495665.03      3562587.30     10496295.25
#Sta/Elev= 30
  3201.9  385.44  3217.5  384.36  3246.0  386.99  3295.3  381.31  3328.8  380.48
  3394.1  377.58  3486.6  368.78  3577.7  369.00  3612.4  368.62  3941.7  367.76
  4082.1  368.06  4117.8  369.67  4167.2  365.57  4181.4  368.23  4200.7  368.46
  4302.0  369.27  4316.3  367.30  4344.8  369.26  4790.7  367.37  4977.7  367.62
  4996.0  362.72  4998.8  362.22  5002.0  362.72  5009.7  367.36  5084.4  366.12
  5162.5  368.12  5364.3  379.39  5419.6  383.56  5444.6  387.22  5504.3  388.77
#Mann=9,-1,0
  3201.9    0.05       0  3328.8     0.1       0  3577.7    0.05       0
  3612.4     0.1       0  3941.7    0.05       0  4200.7     0.1       0
  4790.7    0.05       0  4996.0    0.03       0  5002.0    0.05       0
Bank Sta=4996,5002
Exp/Cntr=0.3,0.1

Chan Stop Cuts=-1