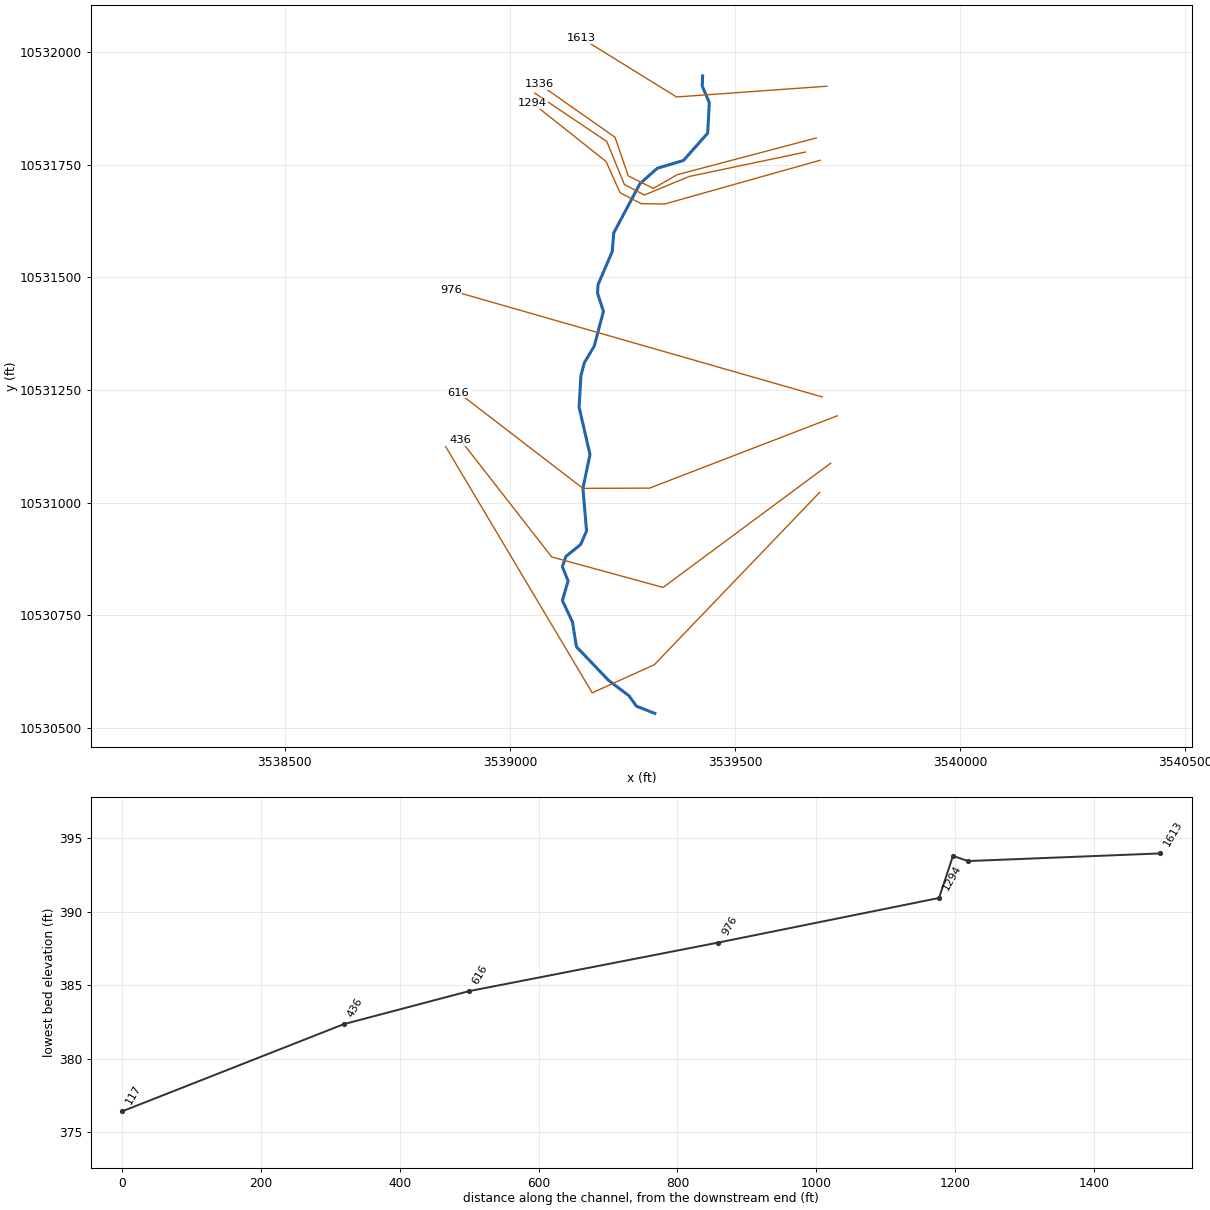
--- UNT01751 IN SAND CR.prj (project) ---

Proj Title=UNT01751 IN SAND CR Base Level Engineering
Current Plan=p01
Default Exp/Contr=0.3,0.1
English Units
Geom File=g01
Flow File=f01
Plan File=p01
BEGIN DESCRIPTION:
UNT01751 IN SAND CR
END DESCRIPTION:

--- UNT01751 IN SAND CR.p01 (plan) ---

Plan Title=Multiple Run
Short Identifier=Multiple
Geom File=g01
Flow File=f01
Subcritical Flow
K Sum by GR= 0
Std Step Tol= 0.01
Critical Tol= 0.01
Num of Std Step Trials= 20
Max Error Tol= 0.3
Flow Tol Ratio= 0.001
Split Flow NTrial= 30
Split Flow Tol= 0.02
Split Flow Ratio= 0.02
Log Output Level= 0
Friction Slope Method= 1
Unsteady Friction Slope Method= 2
Unsteady Bridges Friction Slope Method= 1
Parabolic Critical Depth
Global Vel Dist=  1 , 1 , 1
Global Log Level= 0
CheckData=True
Encroach Param= -1, 0, 0, 0
BEGIN DESCRIPTION:
Multiple Run
END DESCRIPTION:

--- UNT01751 IN SAND CR.f01 (steady flow) ---

Flow Title=Multiple
Number of Profiles=7
Profile Names=10-year,25-year,50-year,1pct_min,100-year,1pct_plu,500-year
River Rch & RM= UNT01751 IN SAND,Reach-1,1613
     231     289     333     282     381     515     494
Boundary for River Rch & Prof#=UNT01751 IN SAND,Reach-1,1
Up Type=0
Dn Type=3
Dn Slope=0.005
Boundary for River Rch & Prof#=UNT01751 IN SAND,Reach-1,2
Up Type=0
Dn Type=3
Dn Slope=0.005
Boundary for River Rch & Prof#=UNT01751 IN SAND,Reach-1,3
Up Type=0
Dn Type=3
Dn Slope=0.005
Boundary for River Rch & Prof#=UNT01751 IN SAND,Reach-1,4
Up Type=0
Dn Type=3
Dn Slope=0.005
Boundary for River Rch & Prof#=UNT01751 IN SAND,Reach-1,5
Up Type=0
Dn Type=3
Dn Slope=0.005
Boundary for River Rch & Prof#=UNT01751 IN SAND,Reach-1,6
Up Type=0
Dn Type=3
Dn Slope=0.005
Boundary for River Rch & Prof#=UNT01751 IN SAND,Reach-1,7
Up Type=0
Dn Type=3
Dn Slope=0.005

--- UNT01751 IN SAND CR.g01 (geometry) ---

Geom Title=Existing Conditions

River Reach=UNT01751 IN SAND,Reach-1
Reach XY= 30
      3539428.28     10531947.67      3539427.43     10531925.21
      3539443.06     10531888.32      3539439.59     10531820.61
      3539385.77     10531759.84      3539327.61     10531742.48
      3539288.98     10531708.19      3539230.90     10531599.06
      3539227.42     10531557.39      3539196.17     10531484.47
      3539194.79     10531465.03      3539207.98     10531424.75
      3539187.62     10531347.69      3539165.38     10531310.24
      3539157.96     10531281.68      3539153.85     10531212.00
      3539178.07     10531106.65      3539162.41     10531031.46
      3539170.45     10530936.67      3539157.19     10530906.60
      3539124.63     10530880.33      3539116.63     10530857.42
      3539129.48     10530826.01      3539116.69     10530782.37
      3539139.05     10530735.11      3539147.96     10530679.61
      3539218.97     10530605.36      3539264.88     10530570.51
      3539281.19     10530547.63      3539322.11     10530531.64

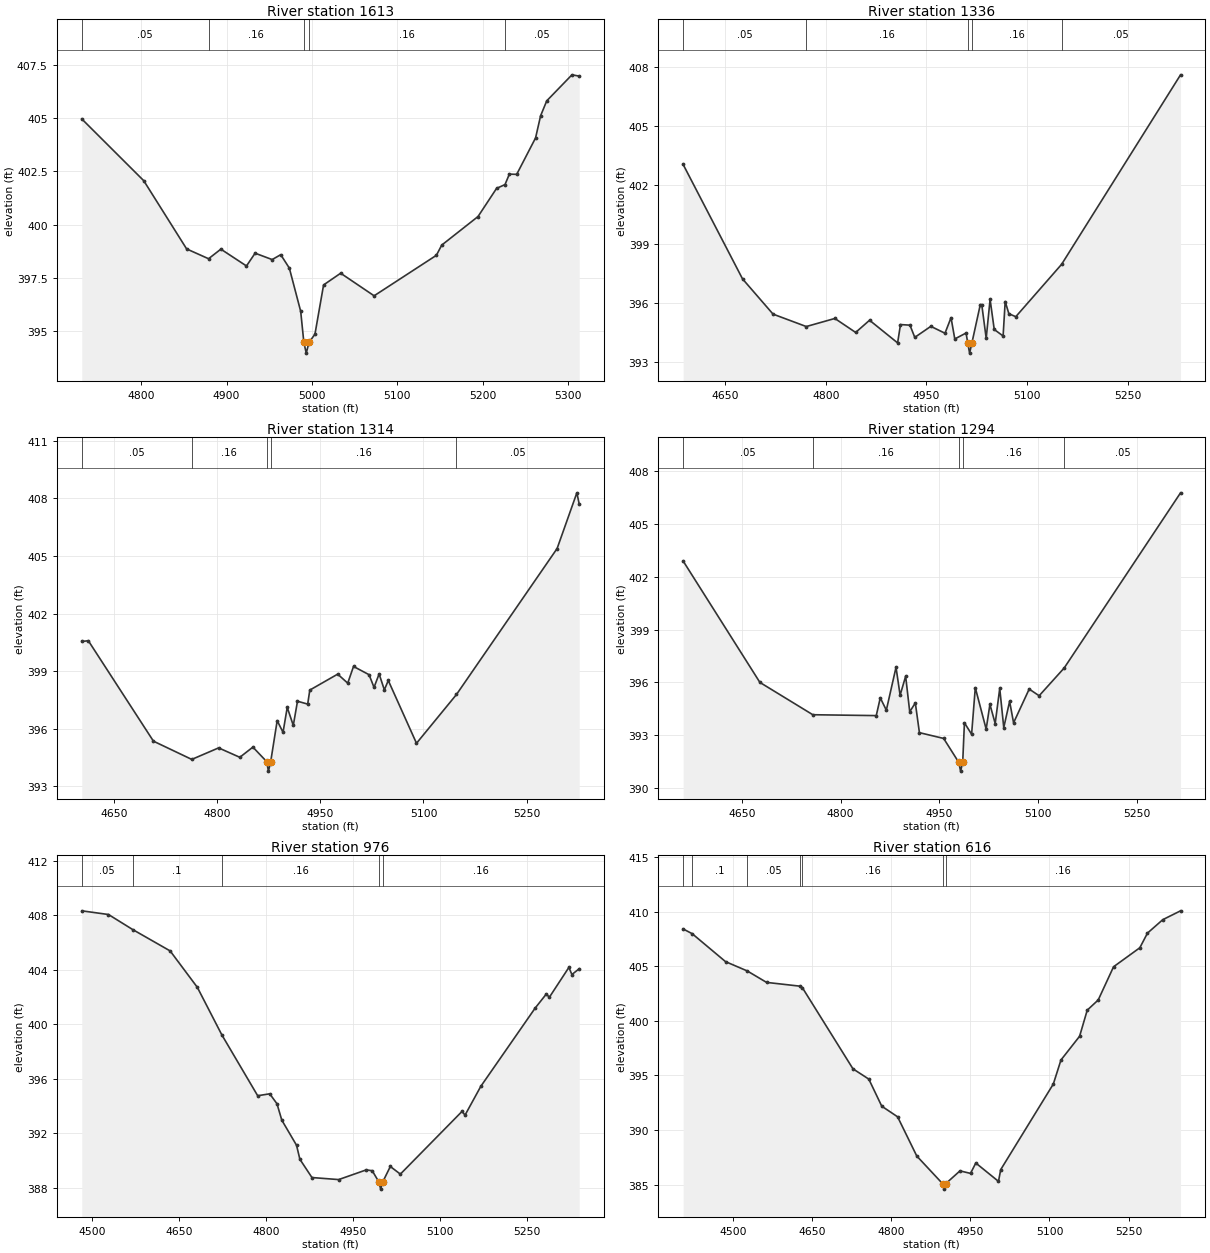
Type RM Length L Ch R = 1,1613,277,277,277
BEGIN DESCRIPTION:
UNT01751 IN SAND CR 2.1
END DESCRIPTION:
XS GIS Cut Line= 3
      3539704.56     10531924.79      3539370.31     10531900.91
      3539159.82     10532031.11
#Sta/Elev= 30
  4730.5  404.96  4803.1  402.06  4853.3  398.86  4879.0  398.40  4893.4  398.85
  4923.4  398.06  4933.5  398.66  4953.5  398.36  4963.5  398.59  4973.6  397.96
  4986.9  395.93  4990.6  394.47  4993.4  393.97  4996.6  394.47  5003.6  394.86
  5013.7  397.17  5033.7  397.72  5072.9  396.66  5145.8  398.56  5152.1  399.04
  5194.6  400.38  5216.3  401.70  5226.2  401.88  5231.3  402.37  5239.9  402.36
  5262.0  404.07  5267.9  405.11  5275.1  405.81  5304.6  407.03  5313.1  406.97
#Mann=5,-1,0
  4730.5    0.05       0  4879.0    0.16       0  4990.6    0.07       0
  4996.6    0.16       0  5226.2    0.05       0
Bank Sta=4990.6,4996.6
Exp/Cntr=0.3,0.1

Type RM Length L Ch R = 1,1336,22,22,22
BEGIN DESCRIPTION:
UNT01751 IN SAND CR 3.1
END DESCRIPTION:
XS GIS Cut Line= 6
      3539680.67     10531809.77      3539371.61     10531728.17
      3539318.66     10531697.79      3539263.11     10531725.56
      3539233.59     10531811.50      3539066.15     10531928.88
#Sta/Elev= 30
  4587.5  403.03  4676.0  397.22  4721.5  395.43  4771.0  394.80  4813.6  395.21
  4844.6  394.50  4865.3  395.12  4907.1  393.97  4911.4  394.90  4925.5  394.87
  4932.7  394.25  4956.6  394.81  4977.7  394.46  4986.7  395.25  4992.3  394.17
  5009.1  394.47  5011.7  393.95  5014.4  393.45  5017.7  393.95  5030.3  395.91
  5032.5  395.91  5039.1  394.20  5044.9  396.18  5051.1  394.65  5064.3  394.32
  5067.4  396.07  5072.9  395.45  5083.2  395.30  5151.5  397.96  5328.7  407.58
#Mann=5,-1,0
  4587.5    0.05       0  4771.0    0.16       0  5011.7    0.07       0
  5017.7    0.16       0  5151.5    0.05       0
Bank Sta=5011.7,5017.7
Exp/Cntr=0.3,0.1

Type RM Length L Ch R = 1,1314,20,20,20
BEGIN DESCRIPTION:
UNT01751 IN SAND CR 3.0
END DESCRIPTION:
XS GIS Cut Line= 6
      3539656.80     10531778.52      3539398.52     10531724.26
      3539298.70     10531683.03      3539254.43     10531706.47
      3539215.36     10531801.95      3539055.50     10531909.39
#Sta/Elev= 30
  4603.6  400.55  4613.1  400.59  4707.7  395.36  4763.4  394.41  4802.4  395.01
  4833.2  394.52  4852.2  395.05  4872.1  394.30  4874.8  393.80  4878.1  394.30
  4887.5  396.43  4896.0  395.82  4902.1  397.12  4910.9  396.18  4917.0  397.44
  4931.8  397.29  4934.9  398.02  4975.4  398.85  4990.0  398.38  4998.4  399.25
  5021.0  398.82  5028.2  398.16  5035.6  398.86  5043.2  398.03  5048.9  398.52
  5089.9  395.25  5148.0  397.79  5294.2  405.39  5322.9  408.29  5326.3  407.71
#Mann=5,-1,0
  4603.6    0.05       0  4763.4    0.16       0  4872.1    0.07       0
  4878.1    0.16       0  5148.0    0.05       0
Bank Sta=4872.1,4878.1
Exp/Cntr=0.3,0.1

Type RM Length L Ch R = 1,1294,318,318,318
BEGIN DESCRIPTION:
UNT01751 IN SAND CR 3.2
END DESCRIPTION:
XS GIS Cut Line= 6
      3539689.31     10531760.28      3539343.84     10531663.06
      3539291.75     10531663.93      3539244.88     10531688.24
      3539213.63     10531757.68      3539050.36     10531887.26
#Sta/Elev= 30
  4561.0  402.90  4677.5  395.99  4757.8  394.15  4854.1  394.10  4860.2  395.11
  4869.4  394.41  4884.1  396.85  4890.3  395.26  4898.7  396.34  4904.9  394.32
  4913.4  394.82  4919.6  393.13  4956.4  392.80  4979.3  391.44  4982.1  390.94
  4985.3  391.44  4987.9  393.69  4998.8  393.04  5004.4  395.69  5020.9  393.33
  5026.6  394.74  5034.6  393.65  5041.5  395.65  5047.6  393.42  5056.5  394.91
  5062.5  393.69  5086.2  395.61  5101.3  395.23  5139.3  396.81  5315.9  406.78
#Mann=5,-1,0
  4561.0    0.05       0  4757.8    0.16       0  4979.3    0.07       0
  4985.3    0.16       0  5139.3    0.05       0
Bank Sta=4979.3,4985.3
Exp/Cntr=0.3,0.1

Type RM Length L Ch R = 1,976,360,360,360
BEGIN DESCRIPTION:
UNT01751 IN SAND CR 2.0
END DESCRIPTION:
XS GIS Cut Line= 2
      3539693.71     10531234.67      3538868.97     10531471.24
#Sta/Elev= 30
  4482.5  408.32  4528.5  408.05  4570.2  406.95  4634.9  405.38  4681.8  402.71
  4724.1  399.22  4785.9  394.76  4806.7  394.90  4819.2  394.17  4827.5  392.97
  4852.9  391.13  4858.7  390.10  4879.5  388.76  4925.6  388.61  4973.1  389.32
  4983.5  389.26  4995.3  388.41  4998.0  387.91  5001.3  388.41  5014.7  389.57
  5032.0  389.01  5138.4  393.61  5143.6  393.34  5170.8  395.45  5264.4  401.18
  5283.8  402.22  5289.0  401.98  5322.7  404.17  5327.9  403.65  5340.5  404.07
#Mann=5,-1,0
  4482.5    0.05       0  4570.2     0.1       0  4724.1    0.16       0
  4995.3    0.07       0  5001.3    0.16       0
Bank Sta=4995.3,5001.3
Exp/Cntr=0.3,0.1

Type RM Length L Ch R = 1,616,180,180,180
BEGIN DESCRIPTION:
UNT01751 IN SAND CR 1.0
END DESCRIPTION:
XS GIS Cut Line= 4
      3539727.13     10531192.59      3539310.44     10531031.99
      3539162.41     10531031.46      3538886.12     10531243.87
#Sta/Elev= 30
  4405.4  408.41  4422.5  407.98  4485.8  405.42  4526.9  404.57  4563.6  403.52
  4627.8  403.17  4631.3  403.05  4727.4  395.61  4757.4  394.67  4782.0  392.19
  4812.0  391.22  4848.4  387.63  4897.3  385.10  4900.1  384.60  4903.3  385.10
  4930.3  386.27  4950.3  386.04  4960.3  386.99  5003.3  385.31  5007.6  386.39
  5107.3  394.22  5121.8  396.42  5157.1  398.59  5171.6  400.98  5192.4  401.91
  5221.5  404.95  5271.3  406.69  5285.8  408.03  5314.8  409.26  5348.5  410.07
#Mann=7,-1,0
  4405.4    0.05       0  4422.5     0.1       0  4526.9    0.05       0
  4627.8     0.1       0  4631.3    0.16       0  4897.3    0.07       0
  4903.3    0.16       0
Bank Sta=4897.3,4903.3
Exp/Cntr=0.3,0.1

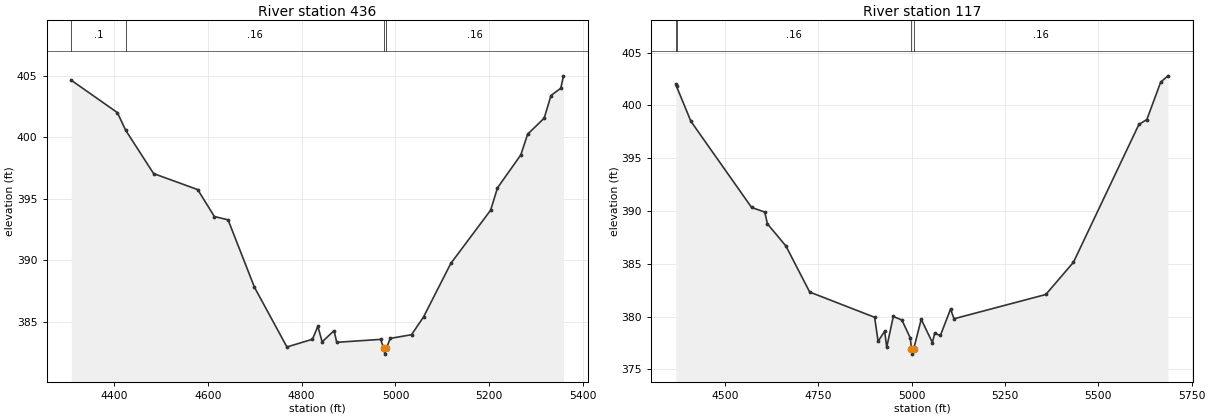
Type RM Length L Ch R = 1,436,319,319,319
BEGIN DESCRIPTION:
UNT01751 IN SAND CR 1.01
END DESCRIPTION:
XS GIS Cut Line= 4
      3539712.88     10531087.44      3539340.47     10530811.39
      3539093.08     10530879.10      3538891.07     10531138.08
#Sta/Elev= 30
  4309.4  404.63  4407.6  402.00  4425.2  400.57  4484.8  397.04  4578.7  395.74
  4614.2  393.55  4643.4  393.28  4699.7  387.79  4768.8  382.94  4823.1  383.57
  4834.7  384.62  4843.8  383.36  4869.2  384.27  4874.9  383.32  4968.3  383.56
  4974.8  382.86  4977.6  382.36  4980.8  382.86  4989.0  383.64  5034.2  383.94
  5059.9  385.39  5117.8  389.73  5202.8  394.07  5217.3  395.88  5267.0  398.56
  5281.5  400.24  5316.8  401.55  5331.3  403.39  5352.1  403.98  5357.9  404.99
#Mann=4,-1,0
  4309.4     0.1       0  4425.2    0.16       0  4974.8    0.07       0
  4980.8    0.16       0
Bank Sta=4974.8,4980.8
Exp/Cntr=0.3,0.1

Type RM Length L Ch R = 1,117,0,0,0
BEGIN DESCRIPTION:
UNT01751 IN SAND CR 1.1
END DESCRIPTION:
XS GIS Cut Line= 4
      3539688.23     10531022.58      3539321.05     10530639.77
      3539183.03     10530577.27      3538857.50     10531124.16
#Sta/Elev= 30
  4368.2  402.04  4370.3  401.80  4408.7  398.50  4571.2  390.34  4606.5  389.90
  4613.7  388.78  4663.1  386.69  4726.9  382.32  4900.8  379.93  4910.1  377.65
  4927.7  378.61  4933.2  377.09  4950.8  380.01  4973.9  379.67  4996.3  377.97
  4999.5  376.94  5002.2  376.44  5005.5  376.94  5025.6  379.74  5055.6  377.53
  5061.4  378.41  5077.0  378.21  5104.2  380.71  5113.4  379.79  5359.3  382.09
  5433.3  385.14  5608.6  398.20  5630.0  398.67  5667.0  402.21  5686.6  402.81
#Mann=4,-1,0
  4368.2     0.1       0  4370.3    0.16       0  4999.5    0.07       0
  5005.5    0.16       0
Bank Sta=4999.5,5005.5
Exp/Cntr=0.3,0.1

Chan Stop Cuts=-1