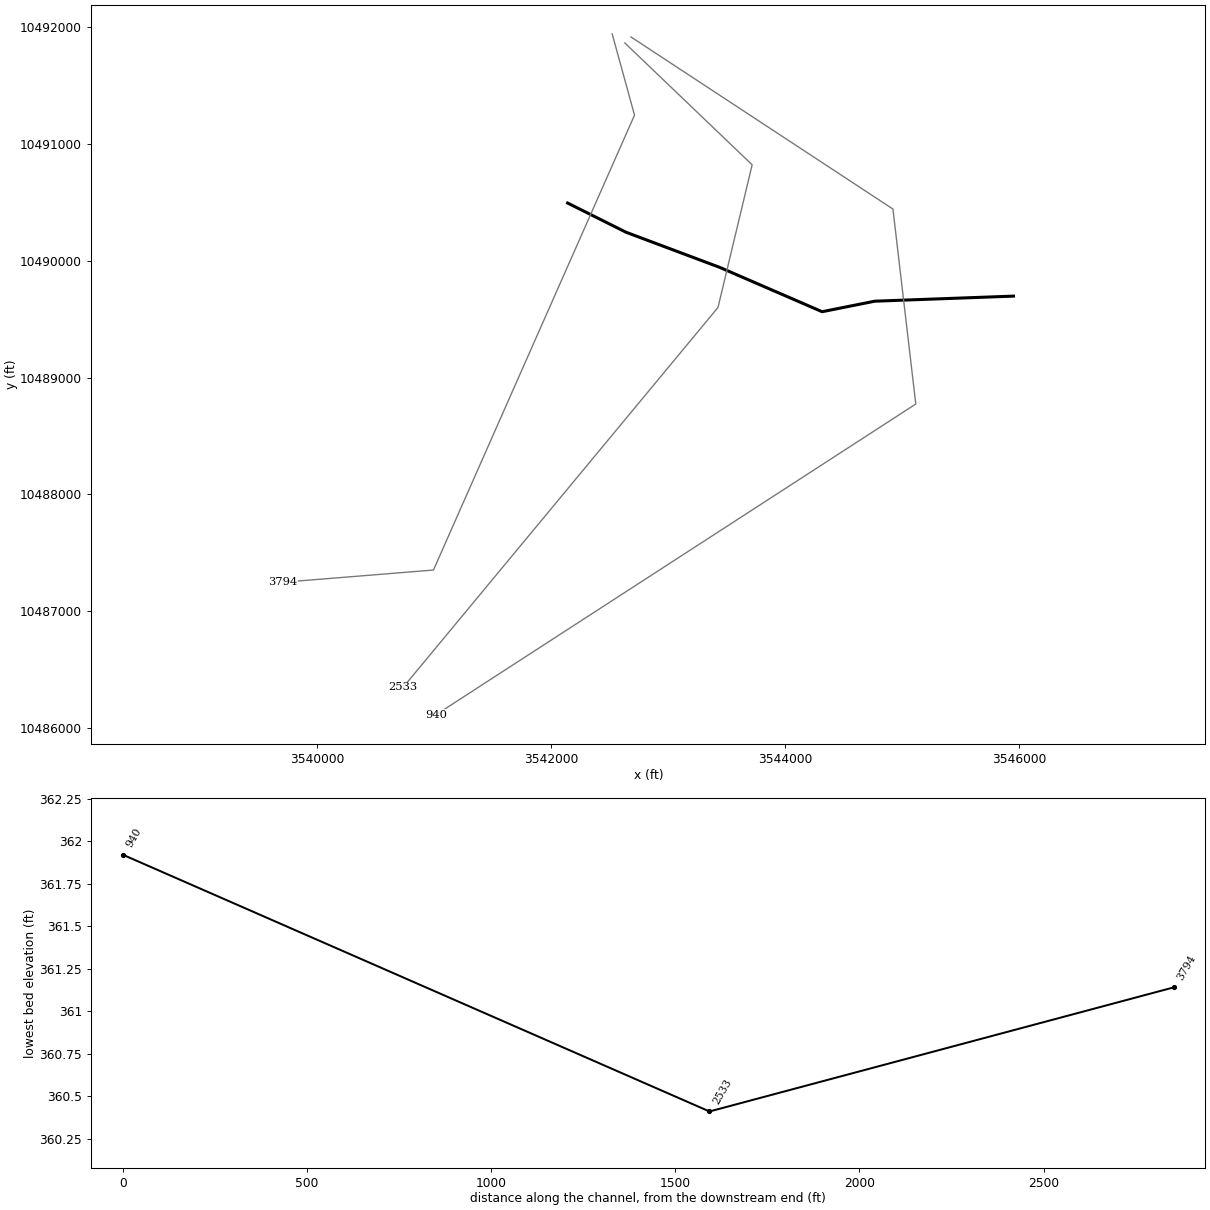
--- UNT0177 IN SAND CR.prj (project) ---

Proj Title=UNT0177 IN SAND CR Base Level Engineering
Current Plan=p01
Default Exp/Contr=0.3,0.1
English Units
Geom File=g01
Flow File=f01
Plan File=p01
BEGIN DESCRIPTION:
UNT0177 IN SAND CR
END DESCRIPTION:

--- UNT0177 IN SAND CR.p01 (plan) ---

Plan Title=Multiple Run
Short Identifier=Multiple
Geom File=g01
Flow File=f01
Subcritical Flow
K Sum by GR= 0
Std Step Tol= 0.01
Critical Tol= 0.01
Num of Std Step Trials= 20
Max Error Tol= 0.3
Flow Tol Ratio= 0.001
Split Flow NTrial= 30
Split Flow Tol= 0.02
Split Flow Ratio= 0.02
Log Output Level= 0
Friction Slope Method= 1
Unsteady Friction Slope Method= 2
Unsteady Bridges Friction Slope Method= 1
Parabolic Critical Depth
Global Vel Dist=  1 , 1 , 1
Global Log Level= 0
CheckData=True
Encroach Param= -1, 0, 0, 0
BEGIN DESCRIPTION:
Multiple Run
END DESCRIPTION:

--- UNT0177 IN SAND CR.f01 (steady flow) ---

Flow Title=Multiple
Number of Profiles=7
Profile Names=10-year,25-year,50-year,1pct_min,100-year,1pct_plu,500-year
River Rch & RM= UNT0177 IN SAND ,Reach-1,3794
    3967    5687    7157    6530    8832   11944   13427
Boundary for River Rch & Prof#=UNT0177 IN SAND ,Reach-1,1
Up Type=0
Dn Type=3
Dn Slope=0.005
Boundary for River Rch & Prof#=UNT0177 IN SAND ,Reach-1,2
Up Type=0
Dn Type=3
Dn Slope=0.005
Boundary for River Rch & Prof#=UNT0177 IN SAND ,Reach-1,3
Up Type=0
Dn Type=3
Dn Slope=0.005
Boundary for River Rch & Prof#=UNT0177 IN SAND ,Reach-1,4
Up Type=0
Dn Type=3
Dn Slope=0.005
Boundary for River Rch & Prof#=UNT0177 IN SAND ,Reach-1,5
Up Type=0
Dn Type=3
Dn Slope=0.005
Boundary for River Rch & Prof#=UNT0177 IN SAND ,Reach-1,6
Up Type=0
Dn Type=3
Dn Slope=0.005
Boundary for River Rch & Prof#=UNT0177 IN SAND ,Reach-1,7
Up Type=0
Dn Type=3
Dn Slope=0.005

--- UNT0177 IN SAND CR.g01 (geometry) ---

Geom Title=Existing Conditions

River Reach=UNT0177 IN SAND ,Reach-1
Reach XY= 6
      3542142.11     10490491.64      3542642.11     10490241.64
      3543442.11     10489941.64      3544317.97     10489562.46
      3544767.60     10489652.38      3545954.16     10489695.86

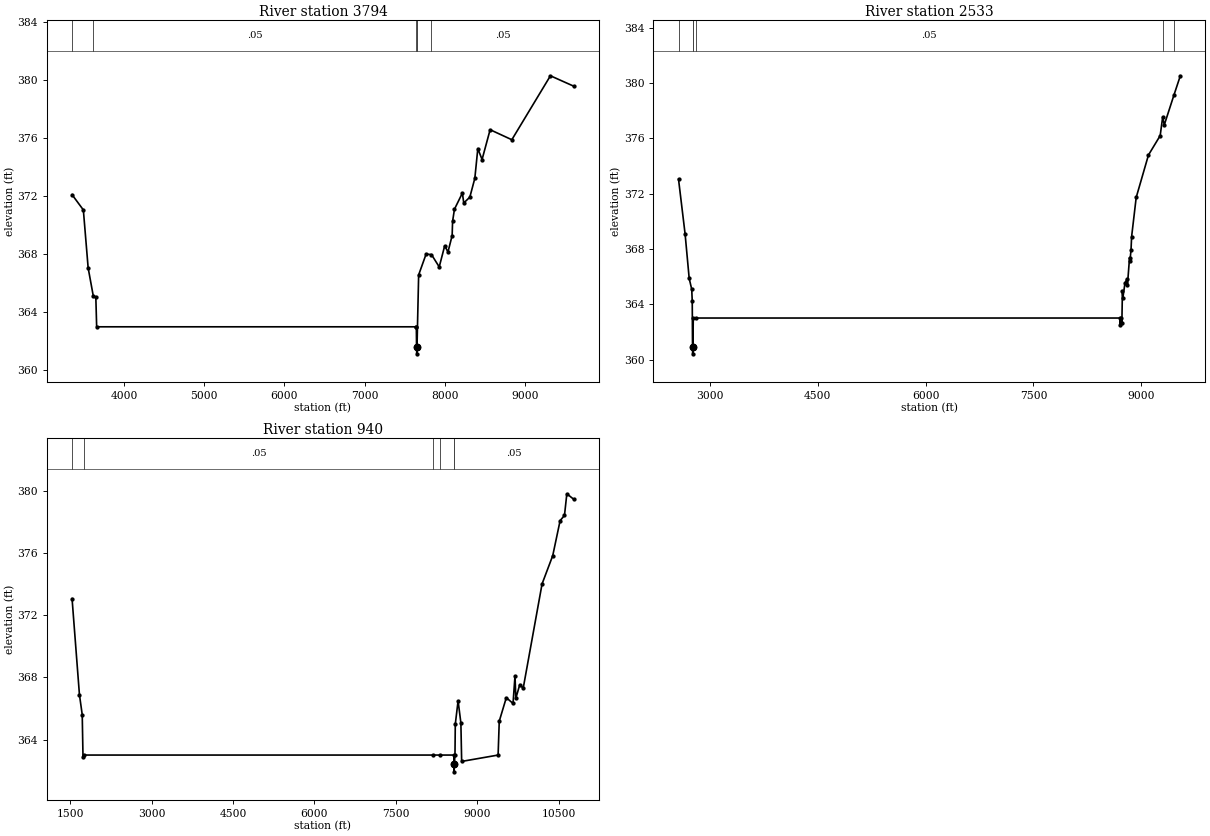
Type RM Length L Ch R = 1,3794,1261,1261,1261
BEGIN DESCRIPTION:
UNT0177 IN SAND CK 1.0
END DESCRIPTION:
XS GIS Cut Line= 4
      3542523.13     10491937.44      3542714.10     10491243.01
      3540995.35     10487354.12      3539710.64     10487249.96
#Sta/Elev= 30
  3350.9  372.09  3491.7  371.04  3551.6  367.05  3616.6  365.09  3647.3  365.05
  3657.7  363.00  7642.9  363.00  7646.4  363.00  7648.9  361.64  7651.7  361.14
  7654.9  361.64  7675.2  366.57  7768.0  368.00  7835.2  367.97  7932.0  367.12
  8000.0  368.57  8041.1  368.15  8093.2  369.28  8098.7  370.26  8122.0  371.09
  8220.7  372.20  8238.1  371.52  8313.9  371.92  8376.3  373.22  8413.4  375.26
  8466.6  374.51  8566.9  376.56  8837.8  375.87  9319.4  380.27  9611.8  379.55
#Mann=6,-1,0
  3350.9    0.16       0  3616.6    0.05       0  7642.9     0.1       0
  7648.9   0.033       0  7654.9     0.1       0  7835.2    0.05       0
Bank Sta=7648.9,7654.9
Exp/Cntr=0.3,0.1

Type RM Length L Ch R = 1,2533,1593,1593,1593
BEGIN DESCRIPTION:
UNT0177 IN SAND CK 2.0
END DESCRIPTION:
XS GIS Cut Line= 4
      3542631.13     10491860.10      3543719.66     10490818.44
      3543427.77     10489598.90      3540736.93     10486352.53
#Sta/Elev= 30
  2564.5  373.03  2656.0  369.07  2712.7  365.86  2747.9  365.08  2755.1  364.23
  2759.0  360.91  2761.8  360.41  2765.0  360.91  2769.3  363.00  2804.6  363.00
  8700.2  363.00  8708.0  362.46  8714.5  363.00  8728.8  362.64  8736.7  364.98
  8743.1  364.47  8771.8  365.52  8800.5  365.84  8807.0  365.41  8835.6  367.37
  8842.1  367.16  8856.4  367.95  8864.3  368.88  8928.1  371.72  9098.7  374.79
  9261.5  376.19  9296.0  377.52  9318.8  376.97  9451.4  379.10  9541.7  380.52
#Mann=6,-1,0
  2564.5    0.16       0  2759.0   0.033       0  2765.0    0.16       0
  2804.6    0.05       0  9296.0    0.08       0  9451.4    0.05       0
Bank Sta=2759,2765
Exp/Cntr=0.3,0.1

Type RM Length L Ch R = 1,940,0,0,0
BEGIN DESCRIPTION:
UNT0177 IN SAND CK 3.0
END DESCRIPTION:
XS GIS Cut Line= 4
      3542683.74     10491911.40      3544923.30     10490440.06
      3545118.62     10488773.39      3541017.12     10486117.18
#Sta/Elev= 30
  1536.4  373.06  1672.3  366.88  1723.5  365.60  1737.9  362.86  1762.6  363.00
  8192.0  363.00  8308.6  363.00  8569.3  363.00  8572.3  362.42  8575.0  361.92
  8578.3  362.42  8590.4  363.00  8596.4  364.99  8647.8  366.49  8699.2  365.07
  8713.6  362.59  9385.1  363.00  9406.2  365.18  9536.1  366.69  9660.1  366.32
  9696.3  368.10  9711.5  366.65  9784.0  367.53  9847.4  367.30 10194.9  374.01
 10391.4  375.83 10527.2  378.08 10607.9  378.42 10651.2  379.81 10780.6  379.45
#Mann=6,-1,0
  1536.4    0.16       0  1762.6    0.05       0  8192.0     0.1       0
  8308.6    0.05       0  8572.3   0.033       0  8578.3    0.05       0
Bank Sta=8572.3,8578.3
Exp/Cntr=0.3,0.1

Chan Stop Cuts=-1