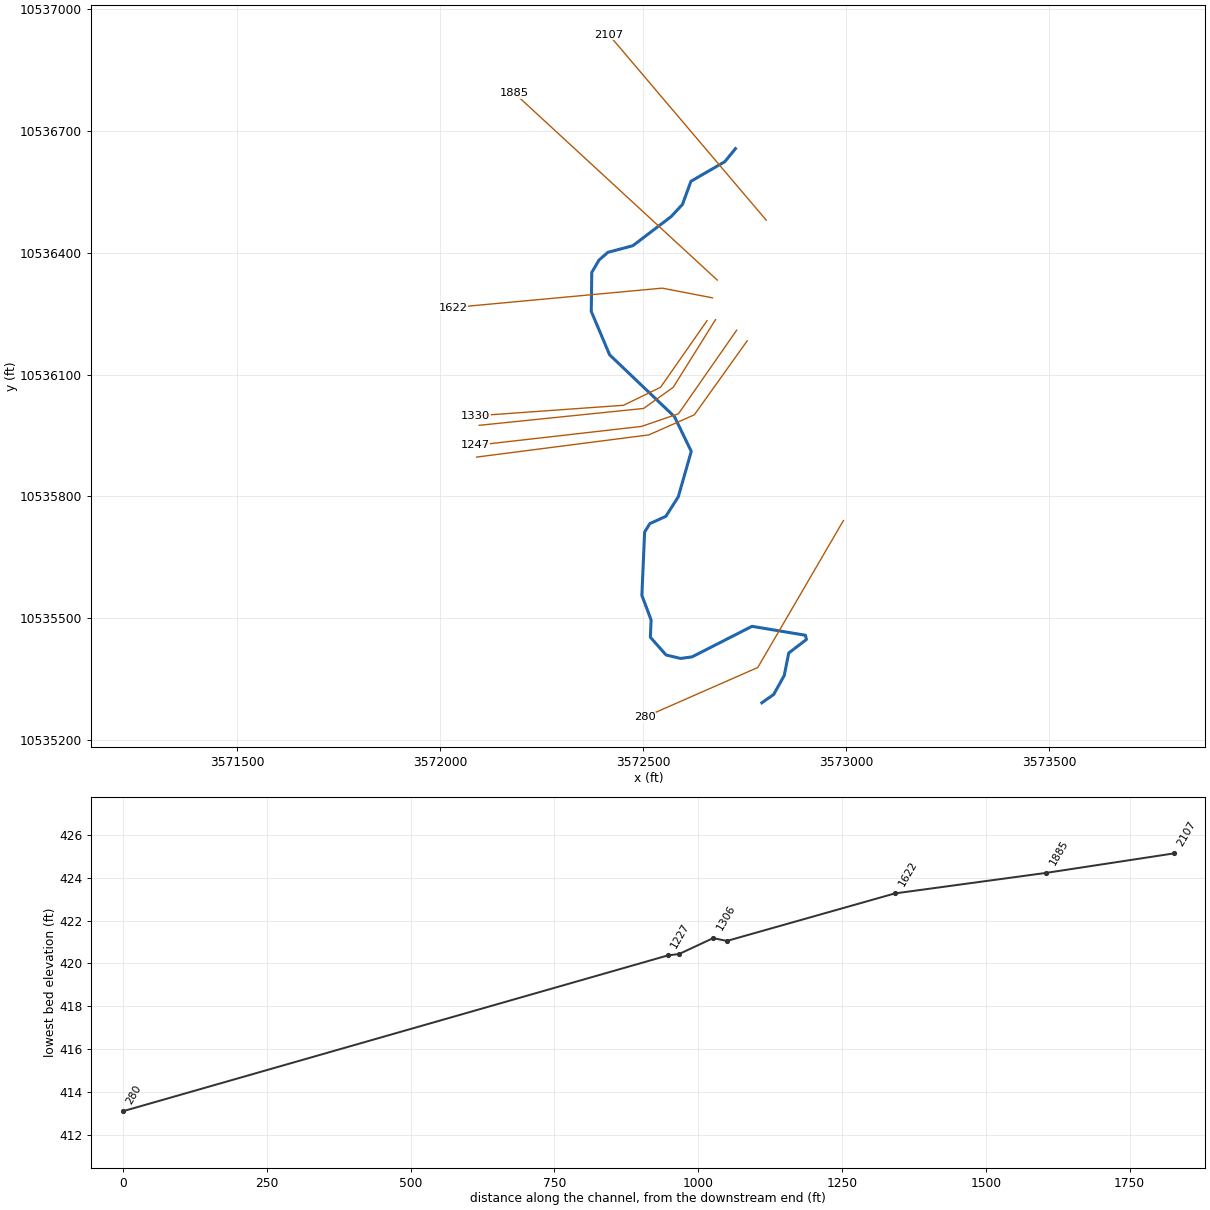
--- UNT01811 IN SAND CR.prj (project) ---

Proj Title=UNT01811 IN SAND CR Base Level Engineering
Current Plan=p01
Default Exp/Contr=0.3,0.1
English Units
Geom File=g01
Flow File=f01
Plan File=p01
BEGIN DESCRIPTION:
UNT01811 IN SAND CR
END DESCRIPTION:

--- UNT01811 IN SAND CR.p01 (plan) ---

Plan Title=Multiple Run
Short Identifier=Multiple
Geom File=g01
Flow File=f01
Subcritical Flow
K Sum by GR= 0
Std Step Tol= 0.01
Critical Tol= 0.01
Num of Std Step Trials= 20
Max Error Tol= 0.3
Flow Tol Ratio= 0.001
Split Flow NTrial= 30
Split Flow Tol= 0.02
Split Flow Ratio= 0.02
Log Output Level= 0
Friction Slope Method= 1
Unsteady Friction Slope Method= 2
Unsteady Bridges Friction Slope Method= 1
Parabolic Critical Depth
Global Vel Dist=  1 , 1 , 1
Global Log Level= 0
CheckData=True
Encroach Param= -1, 0, 0, 0
BEGIN DESCRIPTION:
Multiple Run
END DESCRIPTION:

--- UNT01811 IN SAND CR.f01 (steady flow) ---

Flow Title=Multiple
Number of Profiles=7
Profile Names=10-year,25-year,50-year,1pct_min,100-year,1pct_plu,500-year
River Rch & RM= UNT01811 IN SAND,Reach-1,2107
     346     442     517     442     598     809     797
Boundary for River Rch & Prof#=UNT01811 IN SAND,Reach-1,1
Up Type=0
Dn Type=3
Dn Slope=0.005
Boundary for River Rch & Prof#=UNT01811 IN SAND,Reach-1,2
Up Type=0
Dn Type=3
Dn Slope=0.005
Boundary for River Rch & Prof#=UNT01811 IN SAND,Reach-1,3
Up Type=0
Dn Type=3
Dn Slope=0.005
Boundary for River Rch & Prof#=UNT01811 IN SAND,Reach-1,4
Up Type=0
Dn Type=3
Dn Slope=0.005
Boundary for River Rch & Prof#=UNT01811 IN SAND,Reach-1,5
Up Type=0
Dn Type=3
Dn Slope=0.005
Boundary for River Rch & Prof#=UNT01811 IN SAND,Reach-1,6
Up Type=0
Dn Type=3
Dn Slope=0.005
Boundary for River Rch & Prof#=UNT01811 IN SAND,Reach-1,7
Up Type=0
Dn Type=3
Dn Slope=0.005

--- UNT01811 IN SAND CR.g01 (geometry) ---

Geom Title=Existing Conditions

River Reach=UNT01811 IN SAND,Reach-1
Reach XY= 30
      3572727.11     10536656.64      3572700.79     10536624.48
      3572617.47     10536576.26      3572596.58     10536519.25
      3572568.63     10536489.25      3572474.31     10536417.55
      3572412.89     10536401.29      3572390.94     10536382.17
      3572373.19     10536351.74      3572371.96     10536255.71
      3572417.18     10536148.81      3572576.87     10535996.48
      3572618.29     10535911.02      3572586.35     10535799.19
      3572555.66     10535750.95      3572516.34     10535733.15
      3572503.34     10535712.13      3572496.63     10535556.40
      3572519.37     10535495.69      3572517.46     10535453.22
      3572556.14     10535409.43      3572591.88     10535400.95
      3572620.40     10535404.92      3572767.87     10535480.09
      3572899.48     10535458.03      3572901.96     10535447.62
      3572858.30     10535414.26      3572847.28     10535358.92
      3572821.36     10535312.37      3572792.11     10535291.64

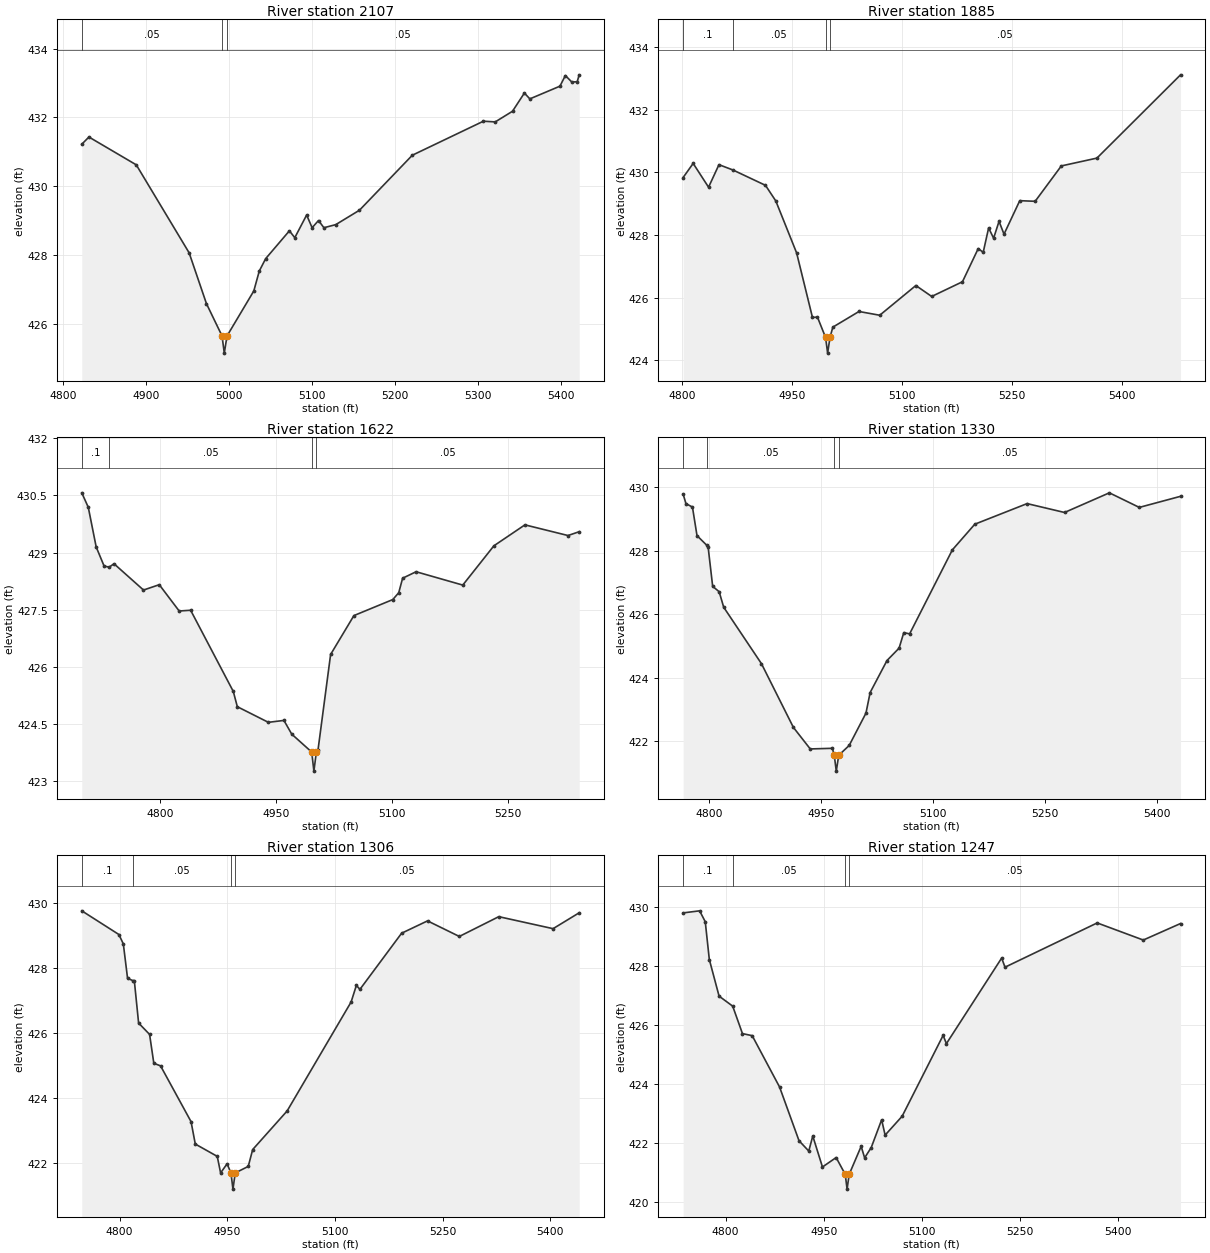
Type RM Length L Ch R = 1,2107,222,222,222
BEGIN DESCRIPTION:
UNT01811 IN SAND CR 2.1
END DESCRIPTION:
XS GIS Cut Line= 2
      3572802.94     10536480.45      3572414.94     10536937.72
#Sta/Elev= 30
  4822.2  431.22  4830.8  431.43  4887.9  430.62  4951.6  428.06  4972.5  426.58
  4991.3  425.64  4994.0  425.14  4997.3  425.64  5029.6  426.95  5036.2  427.53
  5043.9  427.89  5072.5  428.70  5079.0  428.50  5093.3  429.16  5099.9  428.79
  5107.6  429.00  5114.1  428.79  5128.4  428.88  5157.0  429.30  5220.7  430.90
  5306.4  431.89  5320.7  431.87  5341.5  432.18  5355.8  432.71  5362.4  432.54
  5398.7  432.91  5405.2  433.22  5413.0  433.03  5419.5  433.04  5421.9  433.24
#Mann=3,-1,0
  4822.2    0.05       0  4991.3    0.03       0  4997.3    0.05       0
Bank Sta=4991.3,4997.3
Exp/Cntr=0.3,0.1

Type RM Length L Ch R = 1,1885,263,263,263
BEGIN DESCRIPTION:
UNT01811 IN SAND CR 2.0
END DESCRIPTION:
XS GIS Cut Line= 2
      3572682.33     10536332.89      3572183.21     10536792.94
#Sta/Elev= 30
  4801.3  429.84  4815.0  430.29  4836.0  429.53  4850.2  430.25  4869.3  430.08
  4913.7  429.59  4927.8  429.09  4956.2  427.43  4977.8  425.37  4984.6  425.38
  4995.7  424.73  4998.5  424.23  5001.7  424.73  5005.6  425.06  5041.3  425.56
  5069.6  425.44  5118.9  426.39  5140.5  426.04  5182.5  426.51  5204.0  427.57
  5210.8  427.45  5218.2  428.23  5225.0  427.90  5232.4  428.44  5239.2  428.03
  5260.7  429.10  5281.7  429.08  5317.4  430.21  5366.0  430.46  5480.1  433.12
#Mann=4,-1,0
  4801.3     0.1       0  4869.3    0.05       0  4995.7    0.03       0
  5001.7    0.05       0
Bank Sta=4995.7,5001.7
Exp/Cntr=0.3,0.1

Type RM Length L Ch R = 1,1622,292,292,292
BEGIN DESCRIPTION:
UNT01811 IN SAND CR 2.2
END DESCRIPTION:
XS GIS Cut Line= 3
      3572670.36     10536289.21      3572546.66     10536313.08
      3572032.35     10536265.34
#Sta/Elev= 30
  4699.1  430.57  4707.5  430.19  4717.7  429.15  4727.9  428.65  4734.5  428.62
  4740.7  428.71  4778.8  428.02  4799.2  428.16  4824.9  427.47  4839.7  427.49
  4894.8  425.36  4900.0  424.96  4940.1  424.55  4960.2  424.60  4970.3  424.24
  4996.1  423.77  4998.9  423.27  5002.1  423.77  5004.2  423.82  5020.5  426.33
  5050.6  427.35  5100.8  427.77  5108.5  427.95  5113.5  428.33  5130.9  428.50
  5191.2  428.15  5231.4  429.18  5271.5  429.73  5327.1  429.45  5341.6  429.55
#Mann=4,-1,0
  4699.1     0.1       0  4734.5    0.05       0  4996.1    0.03       0
  5002.1    0.05       0
Bank Sta=4996.1,5002.1
Exp/Cntr=0.3,0.1

Type RM Length L Ch R = 1,1330,24,24,24
BEGIN DESCRIPTION:
UNT01811 IN SAND CR 1.3
END DESCRIPTION:
XS GIS Cut Line= 4
      3572657.13     10536232.85      3572542.56     10536068.80
      3572451.41     10536024.53      3572086.96     10535998.50
#Sta/Elev= 30
  4764.8  429.79  4768.6  429.49  4777.3  429.38  4783.4  428.48  4796.3  428.18
  4798.3  428.12  4804.4  426.88  4813.1  426.71  4819.2  426.22  4869.8  424.44
  4912.6  422.43  4935.2  421.75  4964.9  421.77  4967.4  421.55  4970.1  421.05
  4973.4  421.55  4987.4  421.86  5009.9  422.88  5015.5  423.53  5038.1  424.54
  5054.3  424.93  5060.6  425.42  5068.4  425.38  5125.7  428.03  5155.8  428.84
  5225.9  429.49  5276.1  429.21  5336.2  429.83  5376.3  429.37  5431.6  429.72
#Mann=4,-1,0
  4764.8     0.1       0  4796.3    0.05       0  4967.4    0.03       0
  4973.4    0.05       0
Bank Sta=4967.4,4973.4
Exp/Cntr=0.3,0.1

Type RM Length L Ch R = 1,1306,59,59,59
BEGIN DESCRIPTION:
UNT01811 IN SAND CR 1.1
END DESCRIPTION:
XS GIS Cut Line= 4
      3572677.99     10536235.49      3572573.81     10536068.80
      3572500.89     10536016.72      3572095.89     10535975.18
#Sta/Elev= 30
  4747.2  429.76  4798.9  429.03  4805.1  428.74  4811.0  427.68  4818.2  427.61
  4820.5  427.59  4826.4  426.30  4841.7  425.95  4847.6  425.06  4857.0  424.98
  4899.5  423.26  4905.4  422.57  4936.0  422.19  4940.7  421.68  4949.7  421.96
  4955.1  421.68  4957.9  421.18  4961.1  421.68  4979.2  421.88  4985.4  422.40
  5033.4  423.59  5122.6  426.95  5129.9  427.46  5134.9  427.34  5193.0  429.07
  5229.1  429.45  5273.4  428.97  5328.4  429.58  5404.1  429.21  5440.5  429.70
#Mann=4,-1,0
  4747.2     0.1       0  4818.2    0.05       0  4955.1    0.03       0
  4961.1    0.05       0
Bank Sta=4955.1,4961.1
Exp/Cntr=0.3,0.1

Type RM Length L Ch R = 1,1247,20,20,20
BEGIN DESCRIPTION:
UNT01811 IN SAND CR 1.0
END DESCRIPTION:
XS GIS Cut Line= 4
      3572730.03     10536209.39      3572586.83     10536003.69
      3572495.68     10535972.44      3572085.62     10535925.73
#Sta/Elev= 30
  4735.2  429.80  4760.4  429.87  4769.0  429.50  4775.2  428.22  4790.1  426.98
  4810.9  426.64  4825.8  425.71  4840.7  425.64  4882.5  423.90  4912.2  422.08
  4927.1  421.73  4933.2  422.24  4948.0  421.19  4968.9  421.51  4982.8  420.94
  4985.6  420.44  4988.8  420.94  5007.1  421.89  5012.4  421.50  5022.5  421.85
  5038.4  422.79  5043.7  422.27  5069.7  422.91  5132.3  425.65  5137.3  425.37
  5221.7  428.27  5226.8  427.96  5367.6  429.46  5438.0  428.88  5494.9  429.44
#Mann=4,-1,0
  4735.2     0.1       0  4810.9    0.05       0  4982.8    0.03       0
  4988.8    0.05       0
Bank Sta=4982.8,4988.8
Exp/Cntr=0.3,0.1

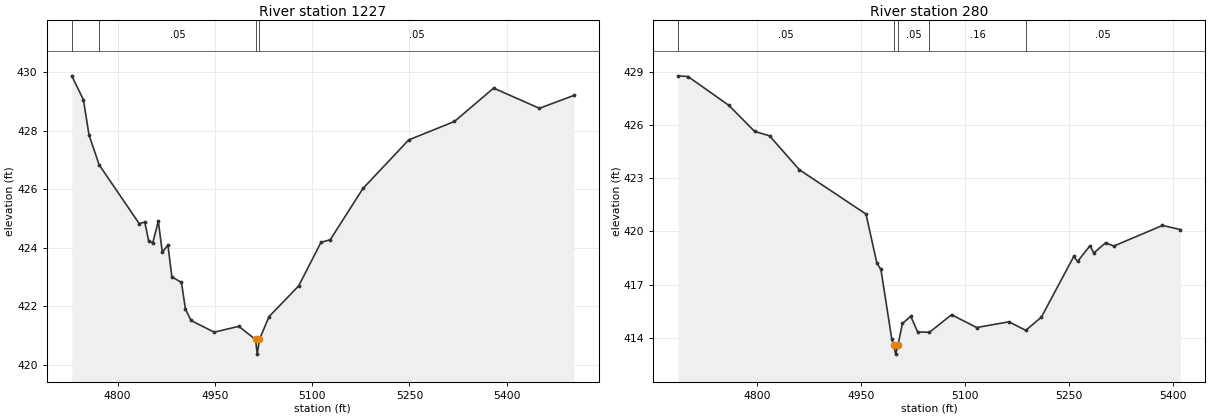
Type RM Length L Ch R = 1,1227,947,947,947
BEGIN DESCRIPTION:
UNT01811 IN SAND CR 1.2
END DESCRIPTION:
XS GIS Cut Line= 4
      3572756.10     10536183.38      3572625.89     10536001.09
      3572513.91     10535951.61      3572089.46     10535896.93
#Sta/Elev= 30
  4729.2  429.88  4747.2  429.06  4755.8  427.86  4771.4  426.84  4833.2  424.83
  4841.8  424.88  4848.0  424.22  4854.2  424.18  4862.7  424.91  4868.9  423.85
  4877.5  424.10  4883.6  423.01  4898.4  422.82  4904.5  421.91  4913.1  421.52
  4948.8  421.12  4986.8  421.32  5012.6  420.87  5015.3  420.37  5018.6  420.87
  5033.4  421.65  5079.1  422.70  5113.6  424.19  5127.9  424.28  5178.3  426.03
  5248.9  427.69  5319.4  428.32  5379.9  429.46  5450.5  428.77  5503.6  429.21
#Mann=4,-1,0
  4729.2     0.1       0  4771.4    0.05       0  5012.6   0.035       0
  5018.6    0.05       0
Bank Sta=5012.6,5018.6
Exp/Cntr=0.3,0.1

Type RM Length L Ch R = 1,280,0,0,0
BEGIN DESCRIPTION:
UNT01811 IN SAND CR 1.4
END DESCRIPTION:
XS GIS Cut Line= 3
      3572993.08     10535740.68      3572782.14     10535378.69
      3572503.50     10535256.30
#Sta/Elev= 30
  4686.7  428.77  4700.8  428.73  4759.5  427.11  4796.7  425.64  4818.2  425.39
  4861.2  423.48  4957.2  420.98  4972.9  418.21  4978.7  417.86  4994.4  413.92
  4997.2  413.59  4999.9  413.09  5003.2  413.59  5009.7  414.82  5021.7  415.22
  5031.6  414.34  5048.6  414.32  5080.4  415.31  5116.6  414.59  5163.1  414.91
  5187.3  414.43  5209.8  415.17  5256.6  418.60  5262.0  418.31  5279.9  419.20
  5285.4  418.79  5302.3  419.36  5314.2  419.18  5384.3  420.34  5410.0  420.11
#Mann=5,-1,0
  4686.7    0.05       0  4997.2    0.03       0  5003.2    0.05       0
  5048.6    0.16       0  5187.3    0.05       0
Bank Sta=4997.2,5003.2
Exp/Cntr=0.3,0.1

Chan Stop Cuts=-1