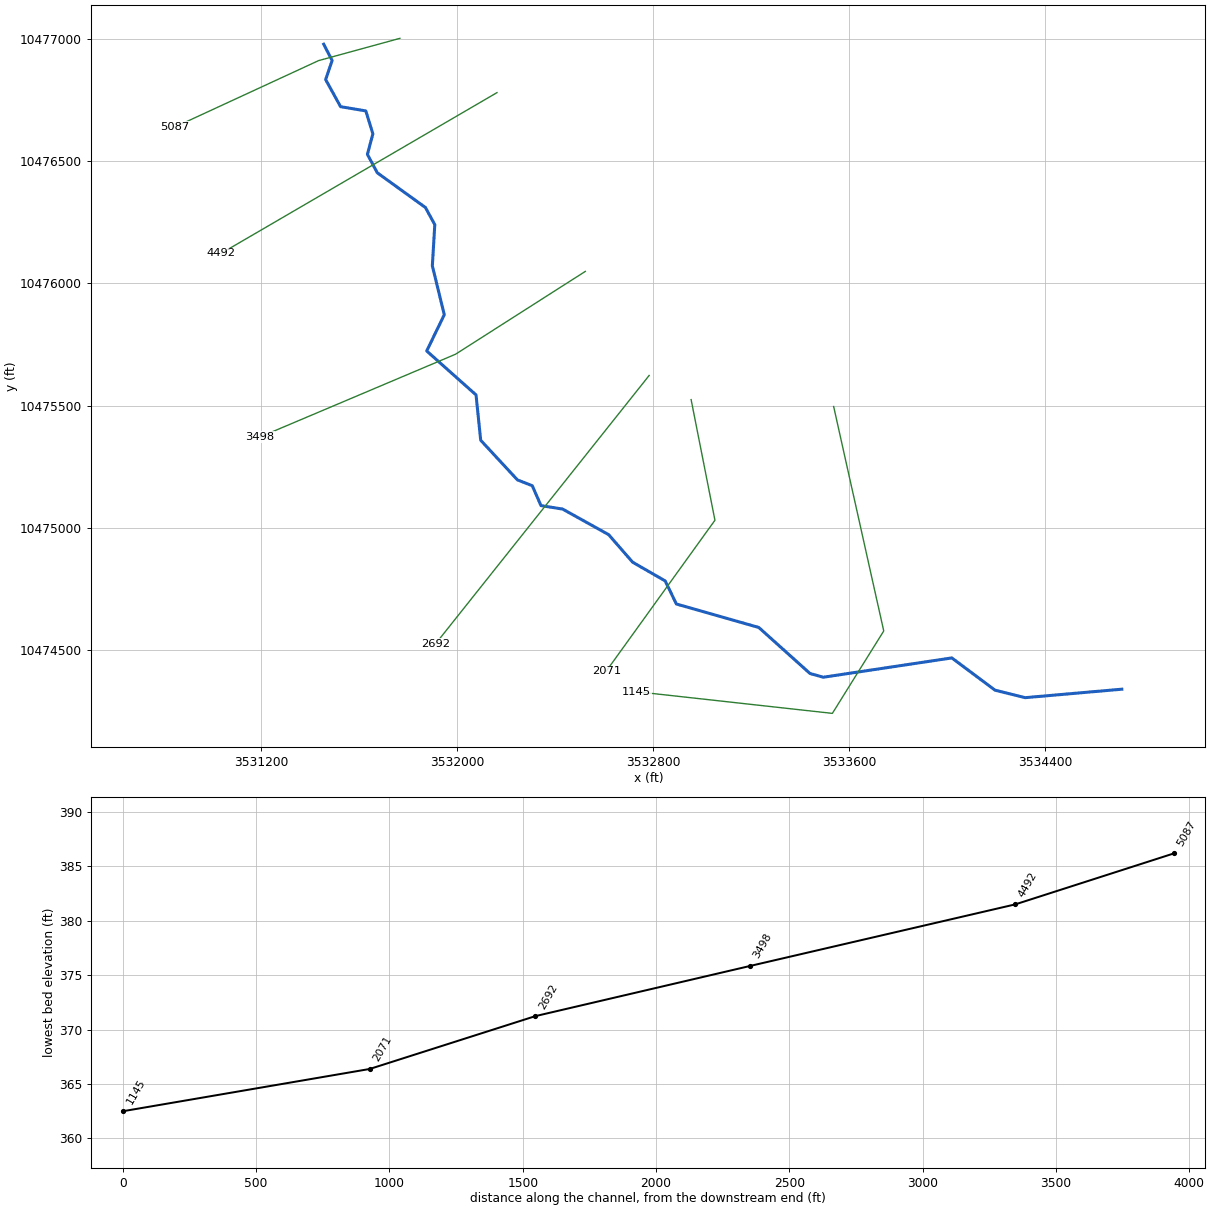
--- UNT0185 IN SAND CR.prj (project) ---

Proj Title=UNT0185 IN SAND CR Base Level Engineering
Current Plan=p01
Default Exp/Contr=0.3,0.1
English Units
Geom File=g01
Flow File=f01
Plan File=p01
BEGIN DESCRIPTION:
UNT0185 IN SAND CR
END DESCRIPTION:

--- UNT0185 IN SAND CR.p01 (plan) ---

Plan Title=Multiple Run
Short Identifier=Multiple
Geom File=g01
Flow File=f01
Subcritical Flow
K Sum by GR= 0
Std Step Tol= 0.01
Critical Tol= 0.01
Num of Std Step Trials= 20
Max Error Tol= 0.3
Flow Tol Ratio= 0.001
Split Flow NTrial= 30
Split Flow Tol= 0.02
Split Flow Ratio= 0.02
Log Output Level= 0
Friction Slope Method= 1
Unsteady Friction Slope Method= 2
Unsteady Bridges Friction Slope Method= 1
Parabolic Critical Depth
Global Vel Dist=  1 , 1 , 1
Global Log Level= 0
CheckData=True
Encroach Param= -1, 0, 0, 0
BEGIN DESCRIPTION:
Multiple Run
END DESCRIPTION:

--- UNT0185 IN SAND CR.f01 (steady flow) ---

Flow Title=Multiple
Number of Profiles=7
Profile Names=10-year,25-year,50-year,1pct_min,100-year,1pct_plu,500-year
River Rch & RM= UNT0185 IN SAND ,Reach-1,5087
    1086    1490    1822    1624    2197    2971    3184
Boundary for River Rch & Prof#=UNT0185 IN SAND ,Reach-1,1
Up Type=0
Dn Type=3
Dn Slope=0.005
Boundary for River Rch & Prof#=UNT0185 IN SAND ,Reach-1,2
Up Type=0
Dn Type=3
Dn Slope=0.005
Boundary for River Rch & Prof#=UNT0185 IN SAND ,Reach-1,3
Up Type=0
Dn Type=3
Dn Slope=0.005
Boundary for River Rch & Prof#=UNT0185 IN SAND ,Reach-1,4
Up Type=0
Dn Type=3
Dn Slope=0.005
Boundary for River Rch & Prof#=UNT0185 IN SAND ,Reach-1,5
Up Type=0
Dn Type=3
Dn Slope=0.005
Boundary for River Rch & Prof#=UNT0185 IN SAND ,Reach-1,6
Up Type=0
Dn Type=3
Dn Slope=0.005
Boundary for River Rch & Prof#=UNT0185 IN SAND ,Reach-1,7
Up Type=0
Dn Type=3
Dn Slope=0.005

--- UNT0185 IN SAND CR.g01 (geometry) ---

Geom Title=Existing Conditions

River Reach=UNT0185 IN SAND ,Reach-1
Reach XY= 30
      3531455.79     10476977.96      3531490.30     10476911.21
      3531463.74     10476833.36      3531524.71     10476722.60
      3531627.62     10476705.25      3531656.51     10476611.58
      3531634.14     10476527.65      3531674.47     10476452.43
      3531870.93     10476310.44      3531909.12     10476240.36
      3531899.11     10476072.01      3531947.89     10475872.17
      3531876.07     10475724.10      3532077.39     10475544.48
      3532096.40     10475359.19      3532246.26     10475197.16
      3532306.76     10475173.43      3532342.36     10475092.02
      3532430.53     10475077.93      3532618.25     10474973.48
      3532716.42     10474860.68      3532849.06     10474784.29
      3532894.89     10474689.84      3533231.00     10474594.01
      3533440.03     10474405.81      3533494.20     10474390.54
      3534018.58     10474469.49      3534194.89     10474337.71
      3534317.80     10474306.99      3534712.11     10474341.64

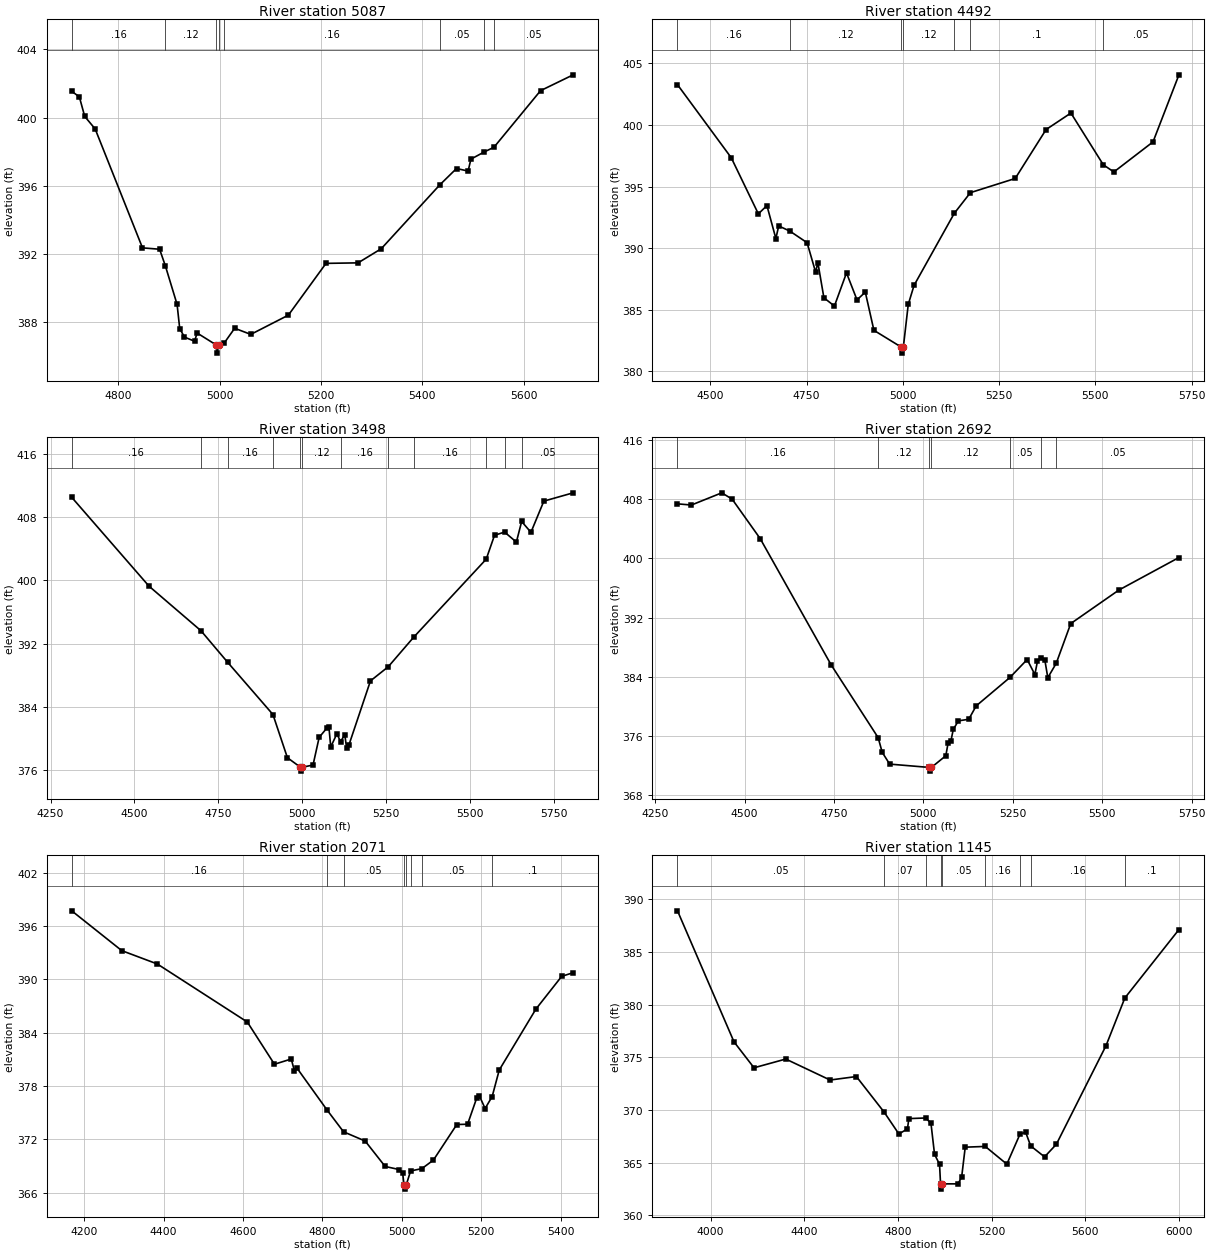
Type RM Length L Ch R = 1,5087,595,595,595
BEGIN DESCRIPTION:
UNT0185 IN SAND CR 8.0
END DESCRIPTION:
XS GIS Cut Line= 3
      3531766.78     10477001.94      3531434.77     10476910.80
      3530848.81     10476639.53
#Sta/Elev= 30
  4707.8  401.54  4722.8  401.22  4733.4  400.07  4754.1  399.33  4847.5  392.35
  4881.3  392.27  4892.7  391.29  4915.8  389.03  4921.0  387.61  4930.4  387.11
  4950.2  386.87  4955.4  387.35  4992.0  386.67  4994.8  386.17  4998.0  386.67
  5009.0  386.77  5029.5  387.63  5061.3  387.27  5135.5  388.40  5209.8  391.44
  5273.1  391.47  5318.9  392.30  5434.5  396.05  5467.5  397.01  5490.4  396.86
  5495.9  397.56  5522.1  397.98  5541.5  398.26  5633.4  401.58  5697.8  402.51
#Mann=8,-1,0
  4707.8    0.16       0  4892.7    0.12       0  4992.0    0.07       0
  4998.0    0.12       0  5009.0    0.16       0  5434.5    0.05       0
  5522.1     0.1       0  5541.5    0.05       0
Bank Sta=4992,4998
Exp/Cntr=0.3,0.1

Type RM Length L Ch R = 1,4492,994,994,994
BEGIN DESCRIPTION:
UNT0185 IN SAND CR 7.0
END DESCRIPTION:
XS GIS Cut Line= 2
      3532162.77     10476779.96      3531037.88     10476123.36
#Sta/Elev= 30
  4414.5  403.27  4554.2  397.34  4624.5  392.79  4646.8  393.46  4670.0  390.79
  4677.4  391.81  4706.4  391.39  4751.1  390.45  4773.3  388.06  4779.1  388.84
  4794.8  385.98  4822.1  385.31  4853.5  388.00  4880.8  385.81  4902.3  386.44
  4924.7  383.34  4995.2  381.99  4997.9  381.49  5001.2  381.99  5013.9  385.44
  5029.0  386.99  5133.4  392.83  5175.3  394.51  5291.7  395.66  5371.9  399.63
  5436.4  400.97  5520.6  396.77  5548.0  396.19  5649.7  398.63  5717.0  404.07
#Mann=7,-1,0
  4414.5    0.16       0  4706.4    0.12       0  4995.2    0.07       0
  5001.2    0.12       0  5133.4    0.16       0  5175.3     0.1       0
  5520.6    0.05       0
Bank Sta=4995.2,5001.2
Exp/Cntr=0.3,0.1

Type RM Length L Ch R = 1,3498,806,806,806
BEGIN DESCRIPTION:
UNT0185 IN SAND CR 5.0
END DESCRIPTION:
XS GIS Cut Line= 3
      3532523.32     10476049.34      3531993.84     10475710.82
      3531196.20     10475372.69
#Sta/Elev= 30
  4313.0  410.52  4543.3  399.27  4698.3  393.62  4777.9  389.62  4912.8  383.01
  4955.9  377.54  4994.6  376.34  4997.4  375.84  5000.6  376.34  5032.3  376.61
  5050.6  380.12  5073.7  381.30  5079.7  381.42  5085.1  378.90  5103.4  380.57
  5114.3  379.58  5127.0  380.45  5132.5  378.74  5138.8  379.09  5203.5  387.27
  5256.5  389.06  5332.1  392.79  5548.6  402.69  5573.3  405.71  5603.3  406.12
  5638.5  404.85  5654.2  407.46  5681.9  406.09  5720.4  410.04  5807.8  411.09
#Mann=12,-1,0
  4313.0    0.16       0  4698.3    0.05       0  4777.9    0.16       0
  4912.8    0.12       0  4994.6    0.07       0  5000.6    0.12       0
  5114.3    0.16       0  5256.5    0.05       0  5332.1    0.16       0
  5548.6    0.05       0  5603.3     0.1       0  5654.2    0.05       0
Bank Sta=4994.6,5000.6
Exp/Cntr=0.3,0.1

Type RM Length L Ch R = 1,2692,621,621,621
BEGIN DESCRIPTION:
UNT0185 IN SAND CR 3.0
END DESCRIPTION:
XS GIS Cut Line= 2
      3532783.77     10475624.02      3531911.66     10474526.28
#Sta/Elev= 30
  4312.5  407.37  4351.4  407.21  4436.3  408.86  4465.2  408.01  4543.7  402.67
  4742.3  385.58  4873.5  375.76  4884.9  373.77  4905.7  372.18  5016.4  371.73
  5019.2  371.23  5022.4  371.73  5062.7  373.31  5069.1  375.04  5077.1  375.33
  5083.5  376.86  5097.9  378.03  5126.8  378.24  5147.6  380.05  5242.1  383.90
  5290.2  386.32  5311.7  384.29  5319.0  386.10  5327.6  386.57  5339.8  386.19
  5347.9  383.86  5371.5  385.82  5412.0  391.18  5546.5  395.71  5714.5  400.11
#Mann=7,-1,0
  4312.5    0.16       0  4873.5    0.12       0  5016.4    0.07       0
  5022.4    0.12       0  5242.1    0.05       0  5327.6    0.16       0
  5371.5    0.05       0
Bank Sta=5016.4,5022.4
Exp/Cntr=0.3,0.1

Type RM Length L Ch R = 1,2071,926,926,926
BEGIN DESCRIPTION:
UNT0185 IN SAND CR 1.0
END DESCRIPTION:
XS GIS Cut Line= 3
      3532954.91     10475525.30      3533052.14     10475032.23
      3532608.59     10474415.42
#Sta/Elev= 30
  4168.9  397.69  4294.9  393.21  4384.3  391.71  4610.9  385.18  4679.2  380.43
  4721.5  381.02  4729.5  379.68  4735.7  380.01  4811.5  375.29  4853.1  372.83
  4907.6  371.79  4957.9  368.93  4993.5  368.58  5002.1  368.15  5005.2  366.88
  5008.0  366.38  5011.2  366.88  5021.9  368.42  5050.4  368.69  5079.4  369.65
  5138.3  373.65  5165.4  373.68  5188.6  376.66  5194.8  376.90  5209.5  375.45
  5227.3  376.80  5245.1  379.78  5337.3  386.63  5402.3  390.32  5431.2  390.73
#Mann=8,-1,0
  4168.9    0.16       0  4811.5    0.12       0  4853.1    0.05       0
  5005.2    0.04       0  5011.2    0.05       0  5021.9    0.16       0
  5050.4    0.05       0  5227.3     0.1       0
Bank Sta=5005.2,5011.2
Exp/Cntr=0.3,0.1

Type RM Length L Ch R = 1,1145,0,0,0
BEGIN DESCRIPTION:
UNT0185 IN SAND CR 1.1
END DESCRIPTION:
XS GIS Cut Line= 4
      3533536.42     10475497.19      3533740.86     10474579.68
      3533531.23     10474242.83      3532731.79     10474331.37
#Sta/Elev= 30
  3859.0  388.90  4100.3  376.47  4185.7  374.01  4321.3  374.84  4510.6  372.85
  4622.8  373.18  4741.5  369.80  4804.4  367.73  4841.0  368.22  4846.8  369.19
  4919.0  369.25  4941.3  368.74  4956.6  365.80  4977.9  364.86  4982.2  363.00
  4984.9  362.50  4988.2  363.00  5056.9  363.00  5072.3  363.64  5087.6  366.48
  5173.1  366.55  5265.3  364.87  5321.7  367.73  5345.8  367.89  5367.0  366.60
  5426.3  365.56  5476.6  366.75  5688.8  376.11  5769.1  380.63  6000.1  387.12
#Mann=9,-1,0
  3859.0    0.05       0  4741.5    0.07       0  4919.0    0.05       0
  4982.2    0.03       0  4988.2    0.05       0  5173.1    0.16       0
  5321.7    0.05       0  5367.0    0.16       0  5769.1     0.1       0
Bank Sta=4982.2,4988.2
Exp/Cntr=0.3,0.1

Chan Stop Cuts=-1