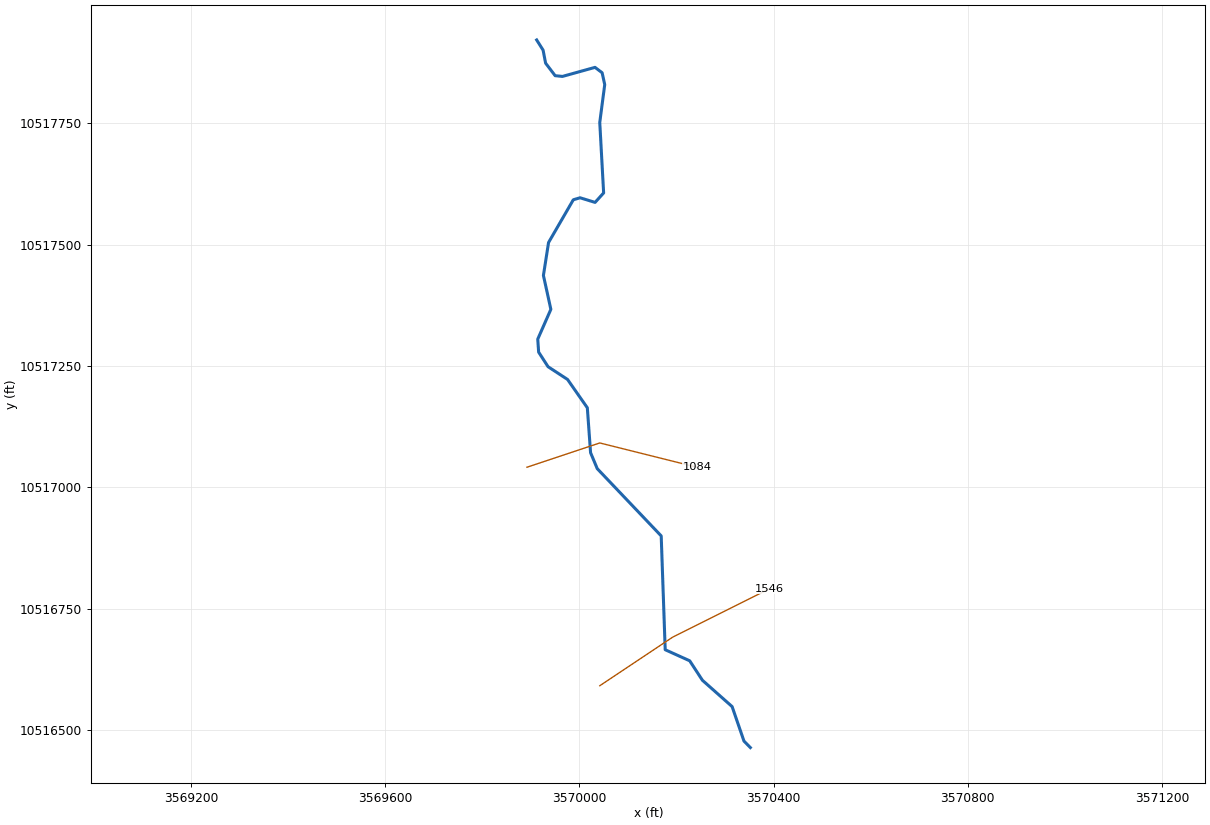
--- UNT01852 IN SAND CR.prj (project) ---

Proj Title=UNT01852 IN SAND CR Base Level Engineering
Current Plan=p01
Default Exp/Contr=0.3,0.1
English Units
Geom File=g01
Flow File=f01
Plan File=p01
BEGIN DESCRIPTION:
UNT01852 IN SAND CR
END DESCRIPTION:

--- UNT01852 IN SAND CR.p01 (plan) ---

Plan Title=Multiple Run
Short Identifier=Multiple
Geom File=g01
Flow File=f01
Subcritical Flow
K Sum by GR= 0
Std Step Tol= 0.01
Critical Tol= 0.01
Num of Std Step Trials= 20
Max Error Tol= 0.3
Flow Tol Ratio= 0.001
Split Flow NTrial= 30
Split Flow Tol= 0.02
Split Flow Ratio= 0.02
Log Output Level= 0
Friction Slope Method= 1
Unsteady Friction Slope Method= 2
Unsteady Bridges Friction Slope Method= 1
Parabolic Critical Depth
Global Vel Dist=  1 , 1 , 1
Global Log Level= 0
CheckData=True
Encroach Param= -1, 0, 0, 0
BEGIN DESCRIPTION:
Multiple Run
END DESCRIPTION:

--- UNT01852 IN SAND CR.f01 (steady flow) ---

Flow Title=Multiple
Number of Profiles=7
Profile Names=10-year,25-year,50-year,1pct_min,100-year,1pct_plu,500-year
River Rch & RM= UNT01852 IN SAND,Reach-1,1546
     509     678     814     716     968    1310    1364
Boundary for River Rch & Prof#=UNT01852 IN SAND,Reach-1,1
Up Type=0
Dn Type=3
Dn Slope=0.005
Boundary for River Rch & Prof#=UNT01852 IN SAND,Reach-1,2
Up Type=0
Dn Type=3
Dn Slope=0.005
Boundary for River Rch & Prof#=UNT01852 IN SAND,Reach-1,3
Up Type=0
Dn Type=3
Dn Slope=0.005
Boundary for River Rch & Prof#=UNT01852 IN SAND,Reach-1,4
Up Type=0
Dn Type=3
Dn Slope=0.005
Boundary for River Rch & Prof#=UNT01852 IN SAND,Reach-1,5
Up Type=0
Dn Type=3
Dn Slope=0.005
Boundary for River Rch & Prof#=UNT01852 IN SAND,Reach-1,6
Up Type=0
Dn Type=3
Dn Slope=0.005
Boundary for River Rch & Prof#=UNT01852 IN SAND,Reach-1,7
Up Type=0
Dn Type=3
Dn Slope=0.005

--- UNT01852 IN SAND CR.g01 (geometry) ---

Geom Title=Existing Conditions

River Reach=UNT01852 IN SAND,Reach-1
Reach XY= 30
      3570352.18     10516464.25      3570339.04     10516477.63
      3570314.61     10516548.67      3570253.43     10516602.91
      3570227.25     10516642.99      3570176.82     10516665.76
      3570168.57     10516900.18      3570036.89     10517038.68
      3570023.10     10517071.58      3570016.43     10517164.07
      3569975.69     10517222.42      3569935.52     10517248.69
      3569916.15     10517278.69      3569914.31     10517305.51
      3569941.31     10517366.84      3569925.99     10517436.65
      3569936.57     10517504.47      3569987.55     10517592.50
      3570001.46     10517596.62      3570032.40     10517587.09
      3570050.01     10517606.59      3570042.03     10517751.71
      3570052.26     10517829.68      3570046.89     10517854.15
      3570032.26     10517865.21      3569965.17     10517846.54
      3569950.12     10517848.07      3569930.50     10517873.87
      3569925.32     10517900.67      3569912.11     10517921.64

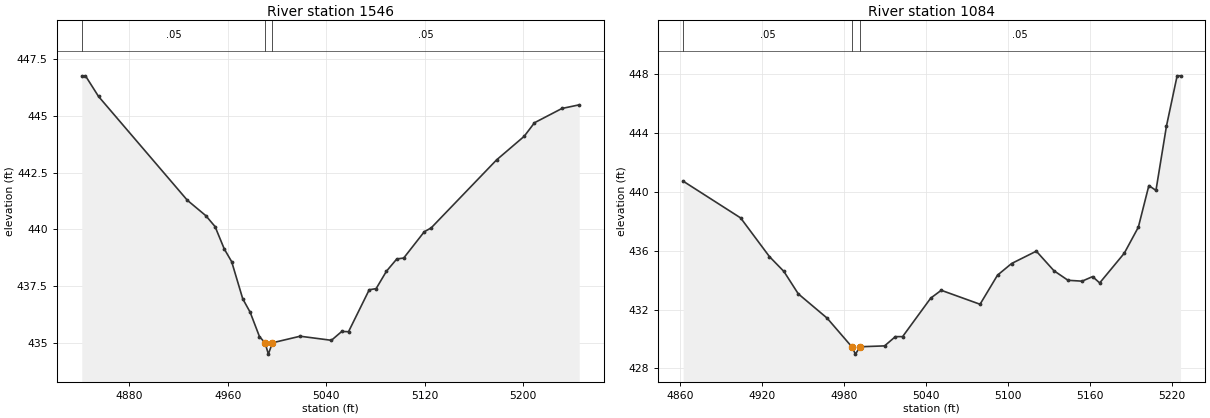
Type RM Length L Ch R = 1,1546,462,462,462
BEGIN DESCRIPTION:
UNT01852 IN SAND CR 3.0
END DESCRIPTION:
XS GIS Cut Line= 3
      3570042.08     10516591.62      3570192.11     10516691.64
      3570392.09     10516791.63
#Sta/Elev= 30
  4841.5  446.77  4844.5  446.77  4855.1  445.86  4927.2  441.28  4942.2  440.60
  4949.7  440.12  4957.2  439.13  4963.2  438.57  4972.2  436.93  4978.2  436.34
  4985.8  435.26  4990.3  434.99  4993.0  434.49  4996.3  434.99  5018.8  435.28
  5044.2  435.10  5052.6  435.49  5058.1  435.48  5074.9  437.33  5080.5  437.38
  5088.9  438.15  5097.3  438.69  5102.9  438.73  5119.6  439.89  5125.2  440.06
  5178.3  443.06  5200.7  444.10  5209.1  444.70  5231.4  445.33  5245.4  445.49
#Mann=3,-1,0
  4841.5    0.05       0  4990.3    0.03       0  4996.3    0.05       0
Bank Sta=4990.3,4996.3
Exp/Cntr=0.3,0.1

Type RM Length L Ch R = 1,1084,0,0,0
BEGIN DESCRIPTION:
UNT01852 IN SAND CR 2.0
END DESCRIPTION:
XS GIS Cut Line= 3
      3569892.13     10517041.65      3570042.11     10517091.64
      3570242.07     10517041.65
#Sta/Elev= 30
  4862.2  440.73  4904.3  438.23  4925.4  435.60  4936.0  434.59  4946.5  433.07
  4967.6  431.42  4985.7  429.47  4988.4  428.97  4991.7  429.47  5009.7  429.53
  5017.6  430.16  5022.9  430.16  5043.5  432.78  5051.2  433.31  5079.6  432.36
  5092.4  434.34  5102.7  435.13  5120.8  435.97  5133.7  434.64  5144.0  433.99
  5154.3  433.93  5162.0  434.24  5167.2  433.81  5185.2  435.83  5195.5  437.60
  5203.2  440.43  5208.4  440.10  5216.1  444.48  5223.9  447.89  5226.4  447.89
#Mann=3,-1,0
  4862.2    0.05       0  4985.7    0.03       0  4991.7    0.05       0
Bank Sta=4985.7,4991.7
Exp/Cntr=0.3,0.1

Chan Stop Cuts=-1