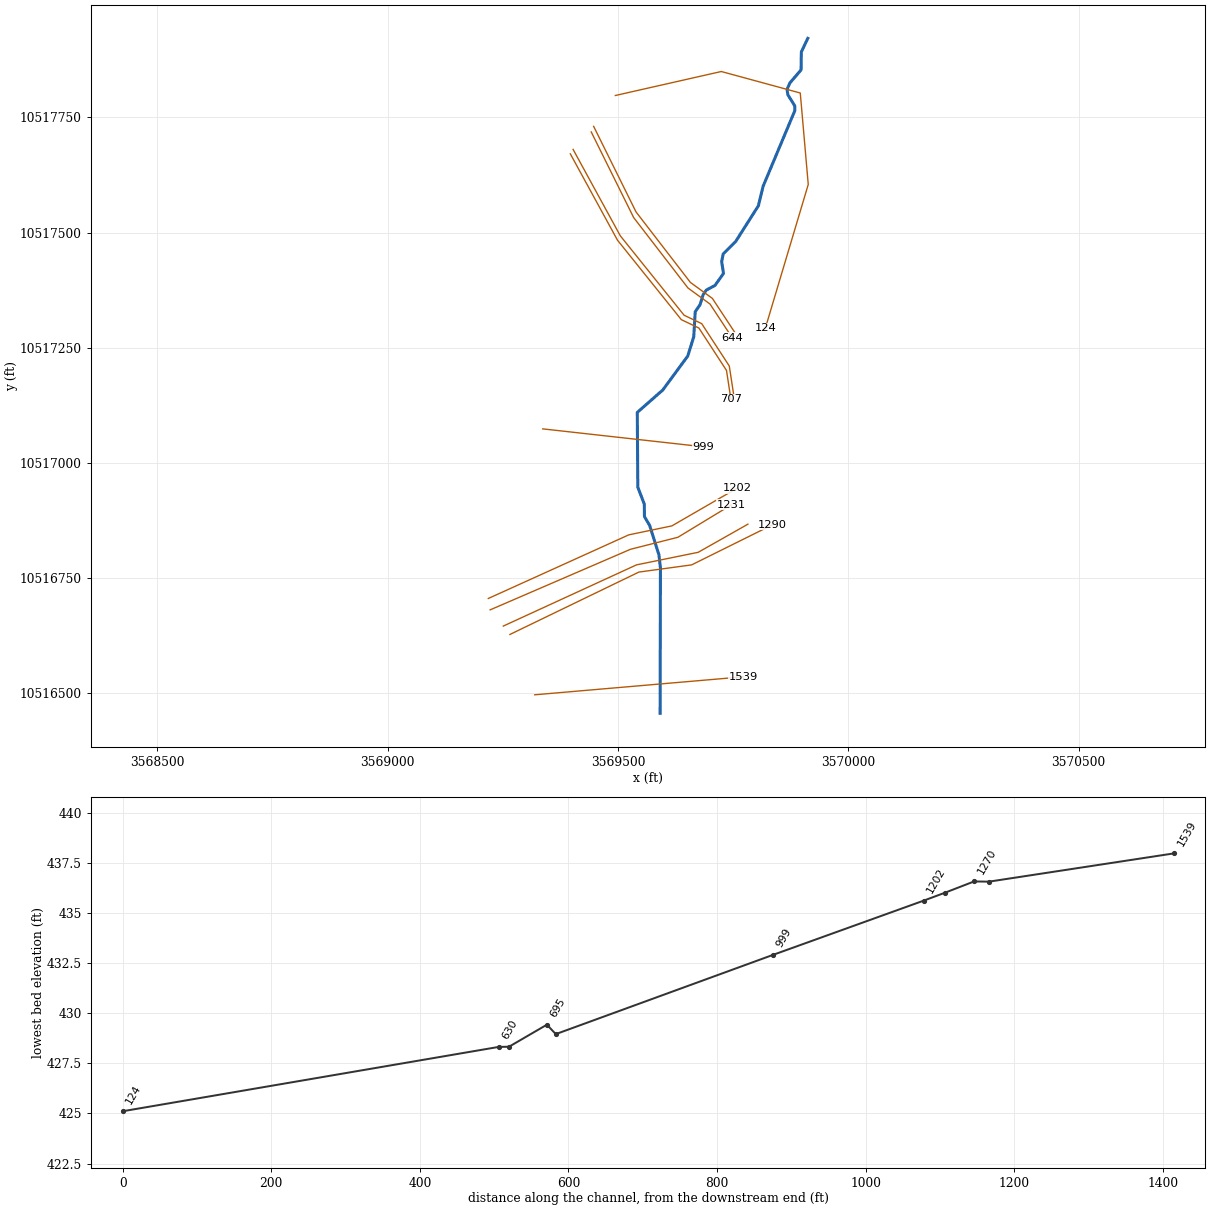
--- UNT01854 IN SAND CR.prj (project) ---

Proj Title=UNT01854 IN SAND CR Base Level Engineering
Current Plan=p01
Default Exp/Contr=0.3,0.1
English Units
Geom File=g01
Flow File=f01
Plan File=p01
BEGIN DESCRIPTION:
UNT01854 IN SAND CR
END DESCRIPTION:

--- UNT01854 IN SAND CR.p01 (plan) ---

Plan Title=Multiple Run
Short Identifier=Multiple
Geom File=g01
Flow File=f01
Subcritical Flow
K Sum by GR= 0
Std Step Tol= 0.01
Critical Tol= 0.01
Num of Std Step Trials= 20
Max Error Tol= 0.3
Flow Tol Ratio= 0.001
Split Flow NTrial= 30
Split Flow Tol= 0.02
Split Flow Ratio= 0.02
Log Output Level= 0
Friction Slope Method= 1
Unsteady Friction Slope Method= 2
Unsteady Bridges Friction Slope Method= 1
Parabolic Critical Depth
Global Vel Dist=  1 , 1 , 1
Global Log Level= 0
CheckData=True
Encroach Param= -1, 0, 0, 0
BEGIN DESCRIPTION:
Multiple Run
END DESCRIPTION:

--- UNT01854 IN SAND CR.f01 (steady flow) ---

Flow Title=Multiple
Number of Profiles=7
Profile Names=10-year,25-year,50-year,1pct_min,100-year,1pct_plu,500-year
River Rch & RM= UNT01854 IN SAND,Reach-1,1539
     375     487     574     496     671     908     913
Boundary for River Rch & Prof#=UNT01854 IN SAND,Reach-1,1
Up Type=0
Dn Type=3
Dn Slope=0.005
Boundary for River Rch & Prof#=UNT01854 IN SAND,Reach-1,2
Up Type=0
Dn Type=3
Dn Slope=0.005
Boundary for River Rch & Prof#=UNT01854 IN SAND,Reach-1,3
Up Type=0
Dn Type=3
Dn Slope=0.005
Boundary for River Rch & Prof#=UNT01854 IN SAND,Reach-1,4
Up Type=0
Dn Type=3
Dn Slope=0.005
Boundary for River Rch & Prof#=UNT01854 IN SAND,Reach-1,5
Up Type=0
Dn Type=3
Dn Slope=0.005
Boundary for River Rch & Prof#=UNT01854 IN SAND,Reach-1,6
Up Type=0
Dn Type=3
Dn Slope=0.005
Boundary for River Rch & Prof#=UNT01854 IN SAND,Reach-1,7
Up Type=0
Dn Type=3
Dn Slope=0.005

--- UNT01854 IN SAND CR.g01 (geometry) ---

Geom Title=Existing Conditions

River Reach=UNT01854 IN SAND,Reach-1
Reach XY= 30
      3569591.54     10516456.14      3569592.23     10516771.72
      3569588.94     10516800.40      3569568.86     10516864.02
      3569557.51     10516883.49      3569557.20     10516910.43
      3569543.06     10516947.21      3569541.98     10517109.58
      3569597.32     10517158.19      3569651.57     10517231.97
      3569664.60     10517274.07      3569667.68     10517327.96
      3569678.18     10517343.44      3569684.97     10517365.08
      3569691.86     10517375.11      3569710.63     10517385.18
      3569729.13     10517411.22      3569725.16     10517437.02
      3569728.48     10517453.65      3569755.58     10517480.57
      3569804.88     10517558.18      3569815.07     10517600.35
      3569883.86     10517764.38      3569883.86     10517774.91
      3569868.87     10517799.14      3569867.02     10517810.68
      3569873.18     10517824.75      3569897.53     10517853.14
      3569898.13     10517892.17      3569912.11     10517921.64

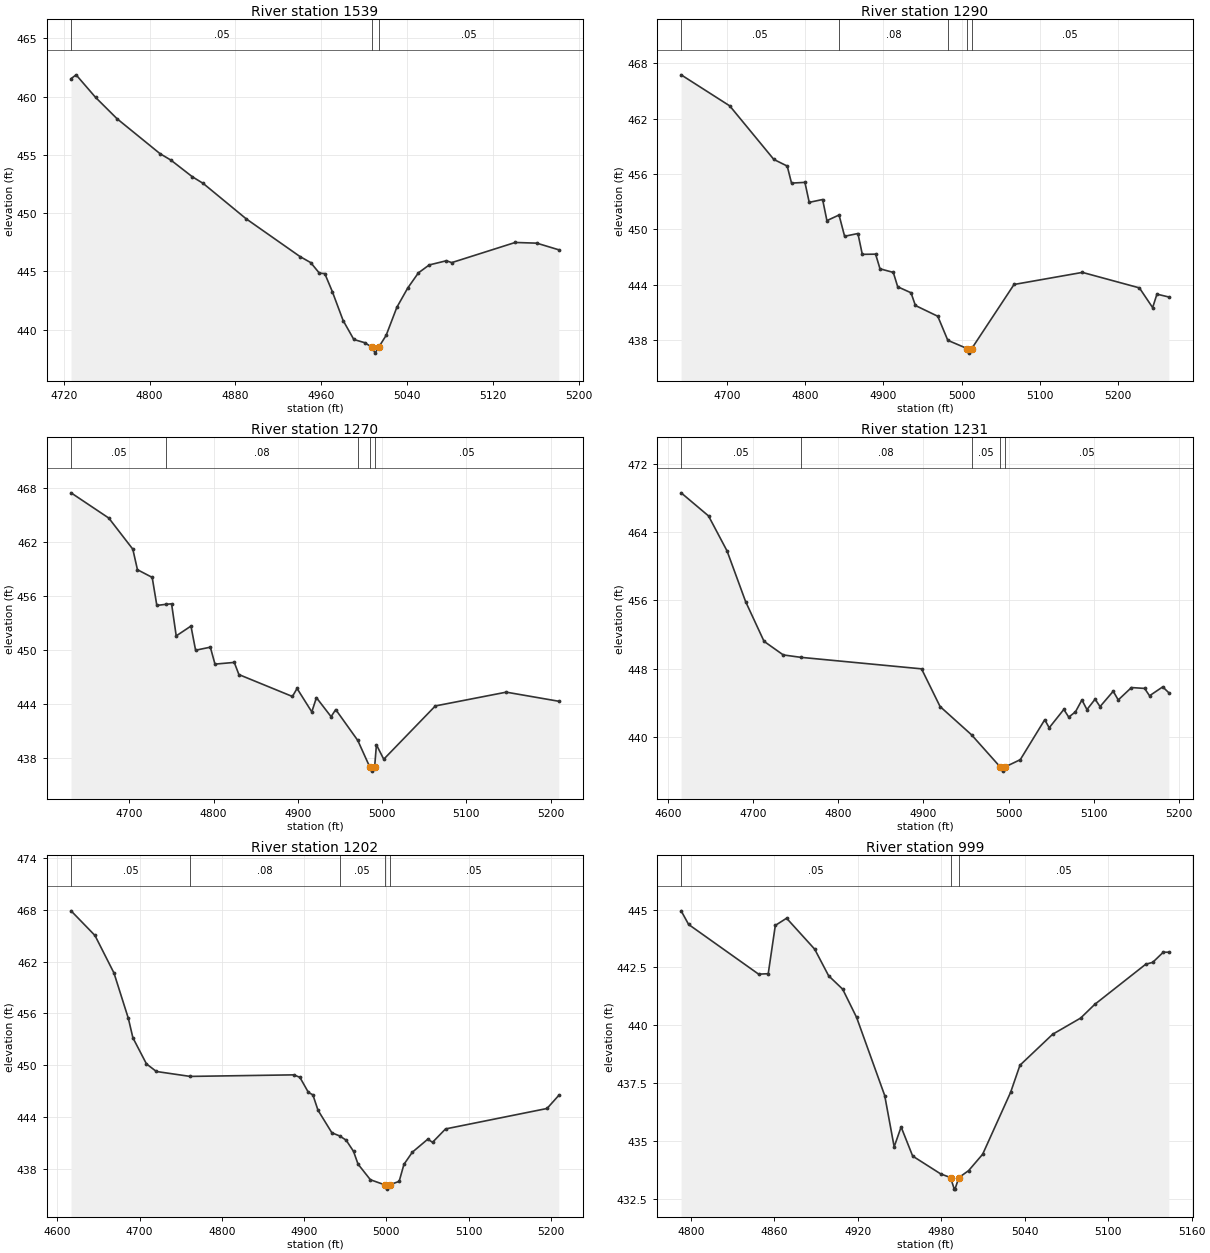
Type RM Length L Ch R = 1,1539,249,249,249
BEGIN DESCRIPTION:
UNT01854 IN SAND CR 3.0
END DESCRIPTION:
XS GIS Cut Line= 2
      3569319.39     10516496.49      3569772.51     10516535.56
#Sta/Elev= 30
  4726.7  461.54  4731.4  461.87  4749.5  459.94  4769.6  458.10  4809.7  455.10
  4819.8  454.55  4839.8  453.12  4849.9  452.55  4890.0  449.51  4940.2  446.27
  4950.2  445.75  4958.3  444.84  4963.3  444.81  4970.3  443.27  4980.4  440.78
  4990.4  439.15  5000.4  438.88  5007.5  438.48  5010.2  437.98  5013.5  438.48
  5020.5  439.50  5030.5  441.91  5040.6  443.56  5050.6  444.87  5060.7  445.55
  5076.7  445.91  5081.7  445.75  5140.9  447.48  5161.0  447.42  5181.5  446.85
#Mann=3,-1,0
  4726.7    0.05       0  5007.5    0.03       0  5013.5    0.05       0
Bank Sta=5007.5,5013.5
Exp/Cntr=0.3,0.1

Type RM Length L Ch R = 1,1290,20,20,20
BEGIN DESCRIPTION:
UNT01854 IN SAND CR 3.2
END DESCRIPTION:
XS GIS Cut Line= 4
      3569265.49     10516627.48      3569545.44     10516762.90
      3569660.02     10516778.53      3569835.84     10516865.78
#Sta/Elev= 30
  4641.8  466.77  4703.9  463.40  4760.2  457.59  4777.3  456.87  4782.8  455.02
  4799.9  455.10  4805.4  452.93  4822.5  453.24  4828.0  450.95  4843.5  451.56
  4850.6  449.25  4867.6  449.55  4873.2  447.29  4890.2  447.31  4895.8  445.72
  4912.8  445.33  4918.4  443.77  4935.4  443.12  4941.0  441.74  4969.6  440.57
  4982.4  437.96  5007.0  437.07  5009.7  436.57  5013.0  437.07  5067.0  444.02
  5154.3  445.33  5227.1  443.65  5244.0  441.51  5249.5  442.97  5264.7  442.66
#Mann=5,-1,0
  4641.8    0.05       0  4843.5    0.08       0  4982.4    0.05       0
  5007.0    0.03       0  5013.0    0.05       0
Bank Sta=5007,5013
Exp/Cntr=0.3,0.1

Type RM Length L Ch R = 1,1270,39,39,39
BEGIN DESCRIPTION:
UNT01854 IN SAND CR 3.1
END DESCRIPTION:
XS GIS Cut Line= 4
      3569251.16     10516645.71      3569540.23     10516778.53
      3569674.34     10516805.87      3569782.07     10516866.87
#Sta/Elev= 30
  4630.8  467.45  4675.6  464.65  4704.1  461.20  4709.6  458.92  4727.1  458.07
  4732.6  454.96  4743.2  455.08  4750.1  455.14  4755.6  451.58  4773.1  452.67
  4778.6  449.99  4796.1  450.33  4801.6  448.45  4824.5  448.64  4830.0  447.29
  4893.5  444.86  4899.0  445.75  4916.5  443.15  4922.0  444.73  4939.4  442.62
  4944.9  443.41  4971.1  439.98  4985.1  437.08  4987.8  436.58  4991.1  437.08
  4993.2  439.50  5001.9  437.90  5063.1  443.81  5147.3  445.34  5209.6  444.33
#Mann=5,-1,0
  4630.8    0.05       0  4743.2    0.08       0  4971.1    0.05       0
  4985.1    0.03       0  4991.1    0.05       0
Bank Sta=4985.1,4991.1
Exp/Cntr=0.3,0.1

Type RM Length L Ch R = 1,1231,29,29,29
BEGIN DESCRIPTION:
UNT01854 IN SAND CR 3.3
END DESCRIPTION:
XS GIS Cut Line= 4
      3569222.55     10516680.88      3569527.21     10516812.38
      3569630.07     10516838.42      3569745.97     10516908.74
#Sta/Elev= 30
  4615.0  468.59  4647.2  465.89  4669.0  461.79  4690.8  455.87  4712.5  451.21
  4735.1  449.62  4755.5  449.34  4897.7  447.99  4919.5  443.58  4956.5  440.27
  4990.1  436.52  4992.9  436.02  4996.1  436.52  5013.8  437.36  5042.6  442.04
  5047.8  441.09  5065.0  443.24  5070.8  442.34  5078.7  442.96  5086.3  444.35
  5092.2  443.22  5101.8  444.44  5107.6  443.57  5123.1  445.37  5129.0  444.35
  5144.5  445.80  5160.0  445.70  5165.8  444.84  5181.3  445.88  5188.5  445.19
#Mann=5,-1,0
  4615.0    0.05       0  4755.5    0.08       0  4956.5    0.05       0
  4990.1    0.03       0  4996.1    0.05       0
Bank Sta=4990.1,4996.1
Exp/Cntr=0.3,0.1

Type RM Length L Ch R = 1,1202,203,203,203
BEGIN DESCRIPTION:
UNT01854 IN SAND CR 3.4
END DESCRIPTION:
XS GIS Cut Line= 4
      3569218.57     10516705.59      3569523.30     10516843.63
      3569617.05     10516863.16      3569758.00     10516944.63
#Sta/Elev= 30
  4616.6  467.89  4645.7  465.03  4668.8  460.68  4686.3  455.41  4691.8  453.17
  4708.3  450.14  4720.4  449.26  4761.4  448.69  4887.6  448.87  4894.9  448.58
  4905.2  446.84  4910.7  446.55  4916.9  444.77  4933.8  442.15  4943.2  441.79
  4951.1  441.30  4960.1  440.00  4965.6  438.52  4980.6  436.71  4998.0  436.12
  5000.7  435.62  5004.0  436.12  5015.6  436.52  5021.4  438.49  5031.6  439.90
  5050.4  441.41  5056.2  441.05  5072.0  442.60  5195.4  444.97  5209.7  446.49
#Mann=5,-1,0
  4616.6    0.05       0  4761.4    0.08       0  4943.2    0.05       0
  4998.0    0.03       0  5004.0    0.05       0
Bank Sta=4998,5004
Exp/Cntr=0.3,0.1

Type RM Length L Ch R = 1,999,292,292,292
BEGIN DESCRIPTION:
UNT01854 IN SAND CR 2.0
END DESCRIPTION:
XS GIS Cut Line= 2
      3569336.74     10517073.79      3569685.09     10517034.97
#Sta/Elev= 30
  4793.1  444.95  4798.5  444.36  4848.8  442.21  4855.7  442.23  4860.8  444.32
  4868.9  444.63  4889.1  443.29  4899.1  442.14  4909.2  441.56  4919.2  440.34
  4939.4  436.96  4946.2  434.74  4951.2  435.60  4959.5  434.34  4979.6  433.57
  4986.7  433.41  4989.4  432.91  4989.9  432.91  4992.7  433.41  4999.7  433.71
  5009.8  434.42  5029.9  437.10  5036.6  438.27  5060.1  439.61  5080.2  440.31
  5090.3  440.90  5127.0  442.64  5132.0  442.72  5139.6  443.16  5143.6  443.16
#Mann=3,-1,0
  4793.1    0.05       0  4986.7    0.03       0  4992.7    0.05       0
Bank Sta=4986.7,4992.7
Exp/Cntr=0.3,0.1

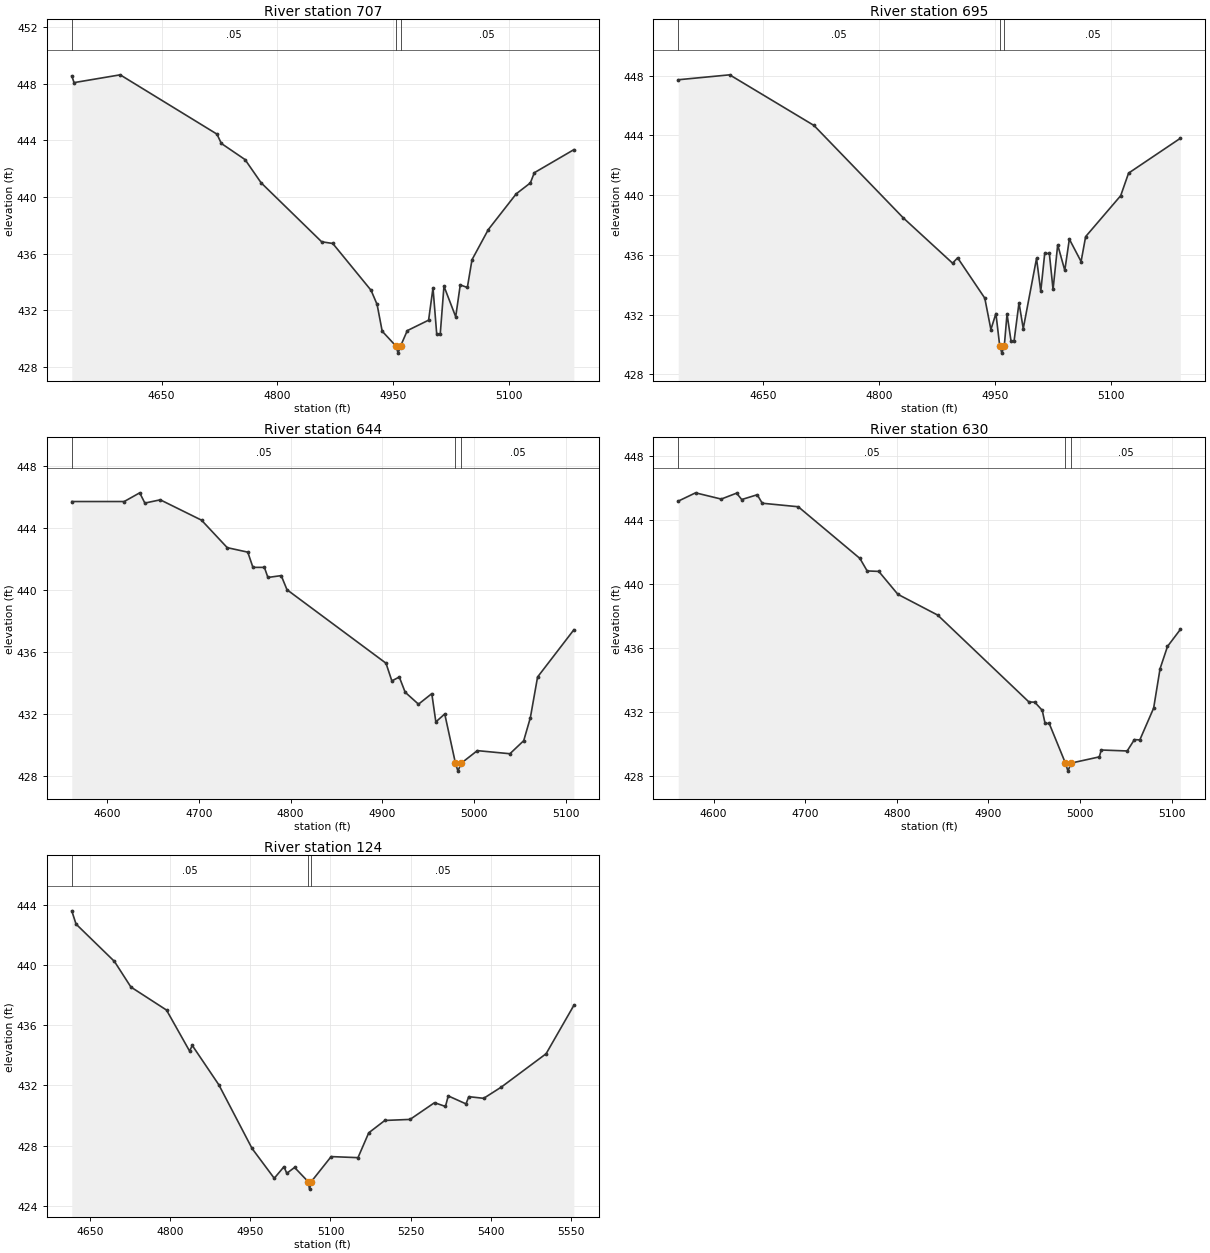
Type RM Length L Ch R = 1,707,12,12,12
BEGIN DESCRIPTION:
UNT01854 IN SAND CR 2.2
END DESCRIPTION:
XS GIS Cut Line= 6
      3569396.58     10517670.86      3569499.00     10517483.39
      3569637.54     10517310.93      3569675.73     10517292.70
      3569735.63     10517200.69      3569745.18     10517138.17
#Sta/Elev= 30
  4533.7  448.55  4536.7  448.08  4596.4  448.63  4721.7  444.44  4727.4  443.78
  4758.1  442.64  4778.9  441.00  4857.3  436.83  4871.7  436.71  4921.3  433.40
  4929.1  432.40  4935.7  430.51  4953.5  429.46  4956.3  428.96  4959.5  429.46
  4968.2  430.55  4995.8  431.29  5001.5  433.57  5006.3  430.32  5010.9  430.32
  5015.7  433.69  5030.9  431.53  5036.8  433.78  5046.0  433.60  5052.0  435.56
  5073.1  437.69  5109.3  440.22  5127.6  440.99  5132.7  441.71  5183.9  443.34
#Mann=3,-1,0
  4533.7    0.05       0  4953.5    0.03       0  4959.5    0.05       0
Bank Sta=4953.5,4959.5
Exp/Cntr=0.3,0.1

Type RM Length L Ch R = 1,695,51,51,51
BEGIN DESCRIPTION:
UNT01854 IN SAND CR 2.1
END DESCRIPTION:
XS GIS Cut Line= 6
      3569402.62     10517680.47      3569505.07     10517492.94
      3569643.61     10517320.48      3569681.81     10517302.25
      3569741.70     10517210.24      3569751.25     10517147.78
#Sta/Elev= 30
  4539.6  447.73  4606.2  448.06  4715.4  444.67  4830.9  438.49  4894.9  435.45
  4901.4  435.81  4936.6  433.11  4944.5  431.01  4951.0  432.08  4955.9  429.93
  4958.7  429.43  4961.9  429.93  4965.4  432.05  4970.6  430.23  4974.5  430.23
  4980.9  432.80  4986.4  431.07  5003.6  435.77  5009.1  433.57  5014.2  436.10
  5020.2  436.10  5025.0  433.69  5031.0  436.68  5040.2  434.97  5046.1  437.06
  5061.3  435.56  5067.2  437.23  5112.6  439.97  5122.8  441.48  5189.8  443.81
#Mann=3,-1,0
  4539.6    0.05       0  4955.9    0.03       0  4961.9    0.05       0
Bank Sta=4955.9,4961.9
Exp/Cntr=0.3,0.1

Type RM Length L Ch R = 1,644,14,14,14
BEGIN DESCRIPTION:
UNT01854 IN SAND CR 2.3
END DESCRIPTION:
XS GIS Cut Line= 5
      3569442.00     10517718.38      3569534.01     10517532.63
      3569652.06     10517379.57      3569699.81     10517344.84
      3569747.77     10517272.05
#Sta/Elev= 30
  4561.7  445.69  4618.8  445.69  4635.7  446.25  4641.3  445.59  4658.1  445.80
  4703.0  444.49  4731.0  442.72  4753.4  442.43  4759.0  441.45  4771.5  441.45
  4775.3  440.80  4789.8  440.92  4796.1  440.01  4903.9  435.28  4910.3  434.14
  4918.4  434.39  4924.8  433.41  4939.3  432.64  4953.8  433.32  4958.2  431.50
  4967.9  432.01  4979.6  428.83  4982.3  428.33  4985.6  428.83  5003.4  429.65
  5038.9  429.45  5053.9  430.29  5061.1  431.76  5069.0  434.39  5108.5  437.43
#Mann=3,-1,0
  4561.7    0.05       0  4979.6    0.03       0  4985.6    0.05       0
Bank Sta=4979.6,4985.6
Exp/Cntr=0.3,0.1

Type RM Length L Ch R = 1,630,506,506,506
BEGIN DESCRIPTION:
UNT01854 IN SAND CR 2.4
END DESCRIPTION:
XS GIS Cut Line= 5
      3569447.22     10517730.51      3569539.22     10517544.79
      3569657.27     10517391.72      3569705.01     10517357.00
      3569753.65     10517283.18
#Sta/Elev= 30
  4561.5  445.19  4580.4  445.71  4608.4  445.32  4625.2  445.69  4630.8  445.29
  4647.7  445.59  4653.2  445.06  4692.5  444.84  4759.8  441.61  4767.7  440.83
  4780.4  440.80  4801.2  439.37  4844.7  438.07  4944.3  432.64  4950.6  432.63
  4958.8  432.12  4961.9  431.30  4966.4  431.30  4984.1  428.82  4986.9  428.32
  4990.1  428.82  5021.1  429.21  5023.2  429.64  5051.5  429.58  5059.4  430.29
  5065.3  430.27  5080.4  432.26  5087.4  434.72  5095.5  436.11  5109.5  437.17
#Mann=3,-1,0
  4561.5    0.05       0  4984.1    0.03       0  4990.1    0.05       0
Bank Sta=4984.1,4990.1
Exp/Cntr=0.3,0.1

Type RM Length L Ch R = 1,124,0,0,0
BEGIN DESCRIPTION:
UNT01852 IN SAND CR 1.0
END DESCRIPTION:
XS GIS Cut Line= 5
      3569494.27     10517797.53      3569724.33     10517849.62
      3569895.77     10517802.96      3569913.13     10517604.39
      3569819.82     10517291.91
#Sta/Elev= 30
  4616.2  443.59  4624.2  442.71  4696.0  440.23  4726.8  438.53  4793.4  437.00
  4836.5  434.28  4841.6  434.65  4891.2  432.04  4953.4  427.81  4994.9  425.83
  5013.1  426.60  5018.3  426.16  5032.9  426.55  5058.2  425.61  5060.9  425.11
  5064.2  425.61  5101.3  427.27  5151.5  427.20  5171.6  428.85  5201.7  429.67
  5248.9  429.74  5294.6  430.85  5315.1  430.60  5320.3  431.30  5353.5  430.77
  5358.7  431.25  5386.6  431.14  5419.7  431.89  5503.3  434.10  5555.2  437.31
#Mann=3,-1,0
  4616.2    0.05       0  5058.2    0.03       0  5064.2    0.05       0
Bank Sta=5058.2,5064.2
Exp/Cntr=0.3,0.1

Chan Stop Cuts=-1