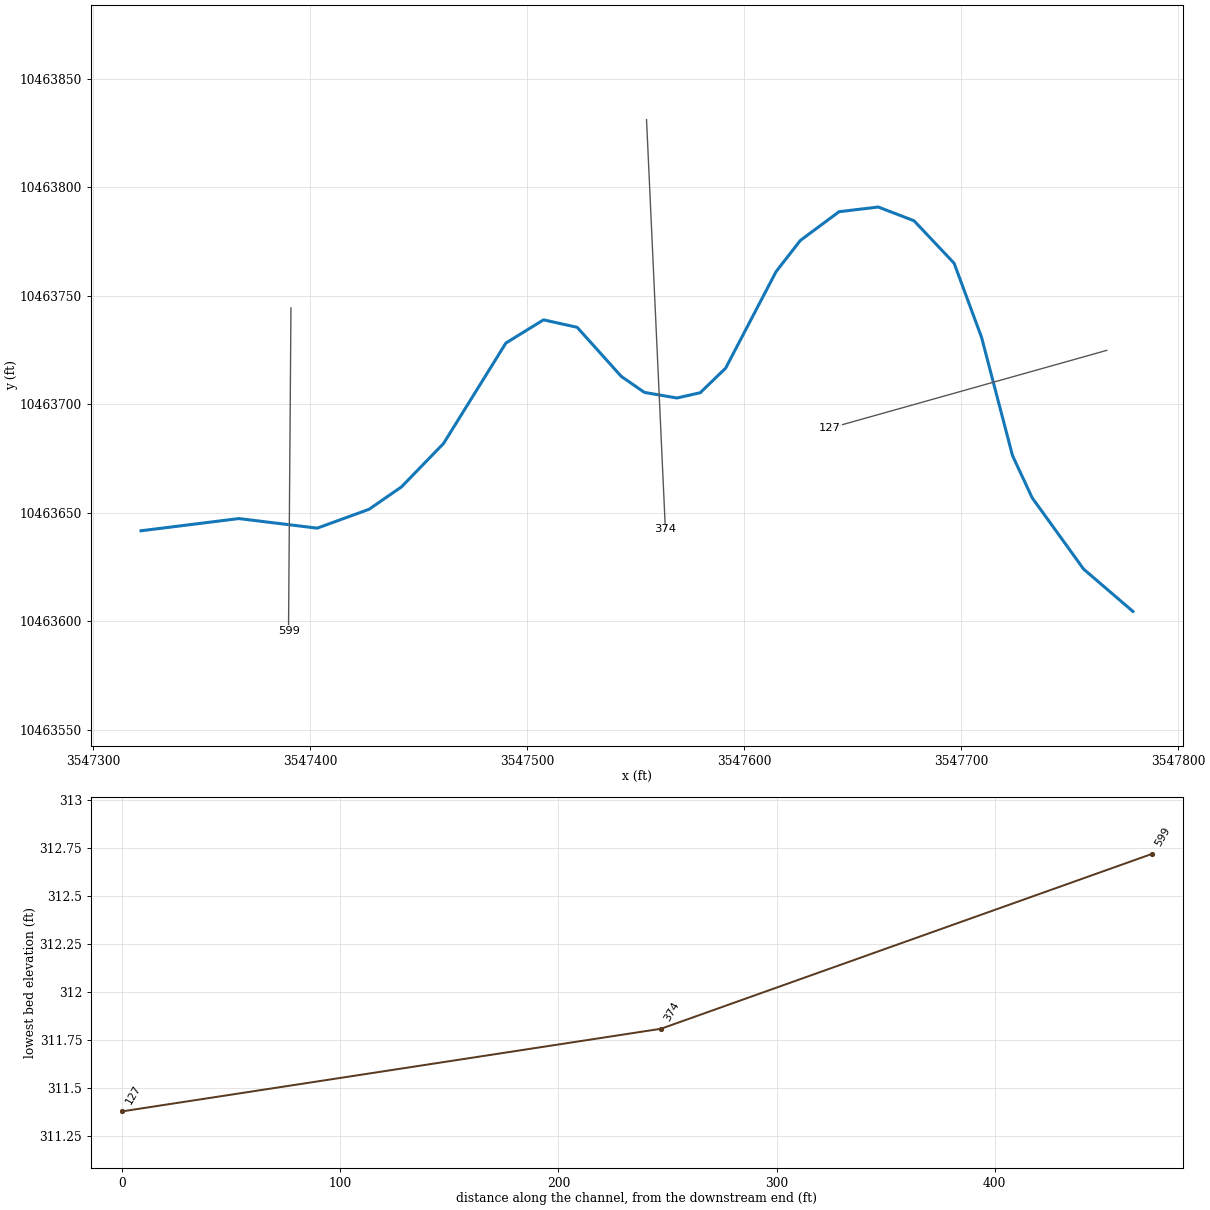
--- UNT0186 IN SAND CR.prj (project) ---

Proj Title=UNT0186 IN SAND CR Base Level Engineering
Current Plan=p01
Default Exp/Contr=0.3,0.1
English Units
Geom File=g01
Flow File=f01
Plan File=p01
BEGIN DESCRIPTION:
UNT0186 IN SAND CR
END DESCRIPTION:

--- UNT0186 IN SAND CR.p01 (plan) ---

Plan Title=Multiple Run
Short Identifier=Multiple
Geom File=g01
Flow File=f01
Subcritical Flow
K Sum by GR= 0
Std Step Tol= 0.01
Critical Tol= 0.01
Num of Std Step Trials= 20
Max Error Tol= 0.3
Flow Tol Ratio= 0.001
Split Flow NTrial= 30
Split Flow Tol= 0.02
Split Flow Ratio= 0.02
Log Output Level= 0
Friction Slope Method= 1
Unsteady Friction Slope Method= 2
Unsteady Bridges Friction Slope Method= 1
Parabolic Critical Depth
Global Vel Dist=  1 , 1 , 1
Global Log Level= 0
CheckData=True
Encroach Param= -1, 0, 0, 0
BEGIN DESCRIPTION:
Multiple Run
END DESCRIPTION:

--- UNT0186 IN SAND CR.f01 (steady flow) ---

Flow Title=Multiple
Number of Profiles=7
Profile Names=10-year,25-year,50-year,1pct_min,100-year,1pct_plu,500-year
River Rch & RM= UNT0186 IN SAND ,Reach-1,599
    2289    3263    4093    3733    5049    6828    7669
Boundary for River Rch & Prof#=UNT0186 IN SAND ,Reach-1,1
Up Type=0
Dn Type=3
Dn Slope=0.005
Boundary for River Rch & Prof#=UNT0186 IN SAND ,Reach-1,2
Up Type=0
Dn Type=3
Dn Slope=0.005
Boundary for River Rch & Prof#=UNT0186 IN SAND ,Reach-1,3
Up Type=0
Dn Type=3
Dn Slope=0.005
Boundary for River Rch & Prof#=UNT0186 IN SAND ,Reach-1,4
Up Type=0
Dn Type=3
Dn Slope=0.005
Boundary for River Rch & Prof#=UNT0186 IN SAND ,Reach-1,5
Up Type=0
Dn Type=3
Dn Slope=0.005
Boundary for River Rch & Prof#=UNT0186 IN SAND ,Reach-1,6
Up Type=0
Dn Type=3
Dn Slope=0.005
Boundary for River Rch & Prof#=UNT0186 IN SAND ,Reach-1,7
Up Type=0
Dn Type=3
Dn Slope=0.005

--- UNT0186 IN SAND CR.g01 (geometry) ---

Geom Title=Existing Conditions

River Reach=UNT0186 IN SAND ,Reach-1
Reach XY= 25
      3547322.11     10463641.64      3547367.15     10463647.26
      3547403.30     10463642.84      3547427.17     10463651.53
      3547442.11     10463661.84      3547461.51     10463681.85
      3547490.24     10463728.14      3547507.58     10463738.82
      3547523.08     10463735.38      3547543.40     10463712.76
      3547554.09     10463705.38      3547569.03     10463702.81
      3547579.78     10463705.24      3547591.49     10463716.56
      3547614.71     10463761.00      3547625.90     10463775.39
      3547643.74     10463788.64      3547661.81     10463790.80
      3547678.29     10463784.48      3547696.77     10463764.90
      3547709.41     10463730.77      3547723.66     10463676.30
      3547732.69     10463656.89      3547756.41     10463624.00
      3547779.16     10463604.47

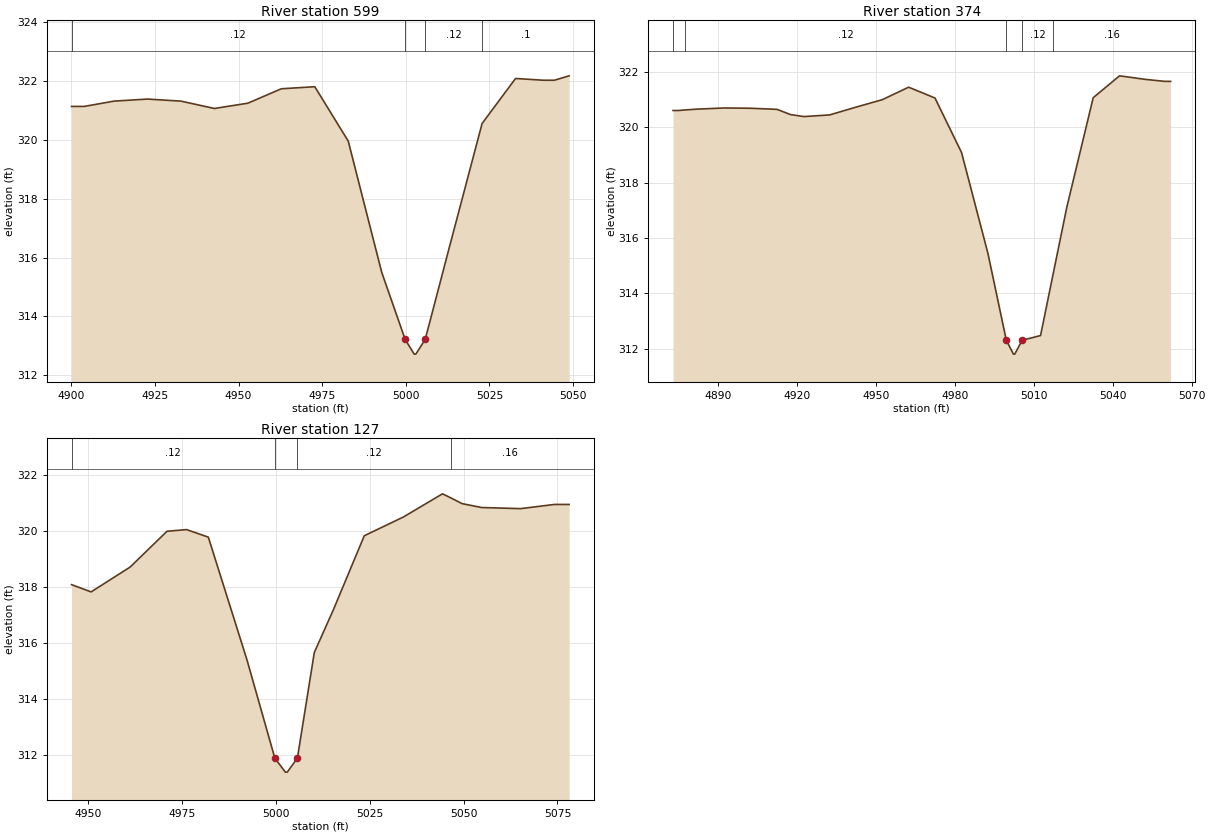
Type RM Length L Ch R = 1,599,225,225,225
BEGIN DESCRIPTION:
UNT0186 IN SAND CR 1.0
END DESCRIPTION:
XS GIS Cut Line= 3
      3547391.20     10463744.31      3547390.11     10463599.98
      3547390.11     10463595.61
#Sta/Elev= 21
  4900.1  321.14  4903.9  321.14  4912.8  321.32  4922.8  321.39  4932.8  321.32
  4942.8  321.07  4952.8  321.25  4962.8  321.74  4972.8  321.81  4982.8  319.96
  4992.8  315.50  4999.8  313.22  5002.5  312.72  5003.0  312.72  5005.8  313.22
  5012.8  316.26  5022.8  320.56  5032.8  322.09  5041.1  322.03  5044.4  322.03
  5048.8  322.18
#Mann=4,-1,0
  4900.1    0.12       0  4999.8    0.07       0  5005.8    0.12       0
  5022.8     0.1       0
Bank Sta=4999.8,5005.8
Exp/Cntr=0.3,0.1

Type RM Length L Ch R = 1,374,247,247,247
BEGIN DESCRIPTION:
UNT0186 IN SAND CR 2.0
END DESCRIPTION:
XS GIS Cut Line= 2
      3547555.04     10463831.08      3547563.72     10463642.28
#Sta/Elev= 28
  4873.0  320.60  4875.2  320.60  4877.7  320.62  4882.4  320.65  4892.5  320.69
  4902.5  320.68  4912.5  320.64  4917.7  320.45  4922.7  320.38  4932.5  320.44
  4942.5  320.72  4952.5  320.99  4962.5  321.44  4972.5  321.05  4982.6  319.08
  4992.6  315.45  4999.6  312.31  5002.3  311.81  5002.8  311.81  5005.6  312.31
  5012.6  312.48  5017.4  314.71  5022.6  317.12  5032.6  321.06  5042.6  321.85
  5052.6  321.72  5059.8  321.65  5062.0  321.65
#Mann=5,-1,0
  4873.0    0.16       0  4877.7    0.12       0  4999.6    0.07       0
  5005.6    0.12       0  5017.4    0.16       0
Bank Sta=4999.6,5005.6
Exp/Cntr=0.3,0.1

Type RM Length L Ch R = 1,127,0,0,0
BEGIN DESCRIPTION:
UNT0186 IN SAND CR 3.0
END DESCRIPTION:
XS GIS Cut Line= 2
      3547767.10     10463724.76      3547639.64     10463688.94
#Sta/Elev= 22
  4945.7  318.09  4950.9  317.83  4961.3  318.72  4971.1  320.00  4976.3  320.06
  4982.1  319.79  4992.4  315.39  4999.8  311.88  5002.6  311.38  5003.1  311.38
  5005.8  311.88  5010.3  315.66  5015.5  317.23  5023.6  319.84  5034.0  320.51
  5044.4  321.34  5046.7  321.19  5049.6  320.99  5054.8  320.85  5065.2  320.81
  5074.2  320.96  5078.1  320.96
#Mann=4,-1,0
  4945.7    0.12       0  4999.8    0.07       0  5005.8    0.12       0
  5046.7    0.16       0
Bank Sta=4999.8,5005.8
Exp/Cntr=0.3,0.1

Chan Stop Cuts=-1