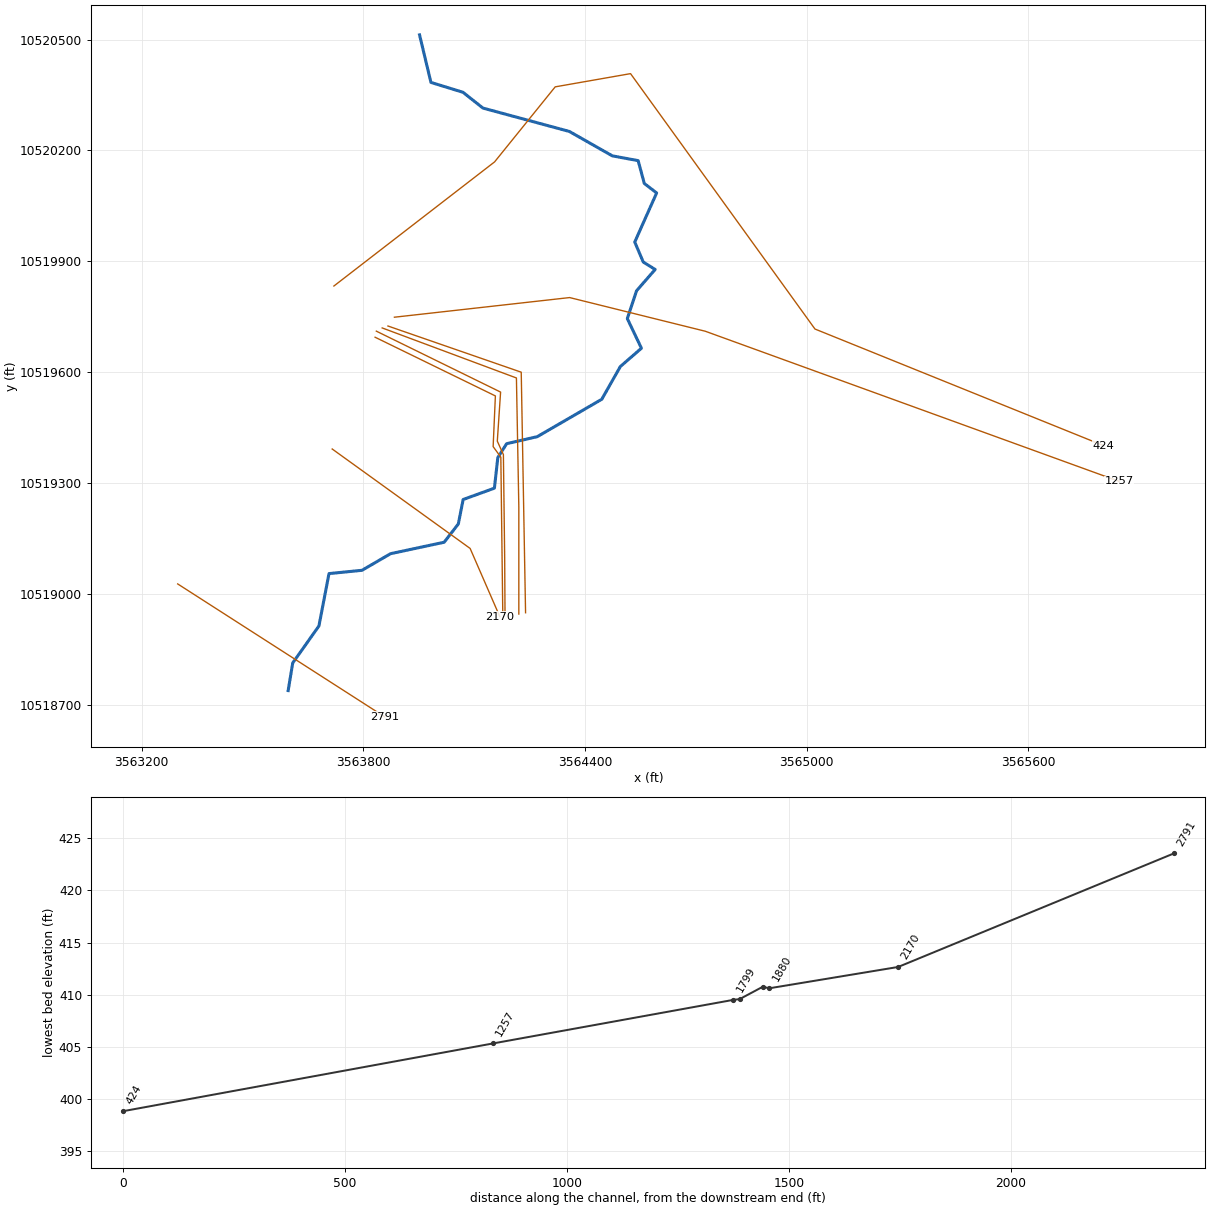
--- UNT01861 IN SAND CR.prj (project) ---

Proj Title=UNT01861 IN SAND CR Base Level Engineering
Current Plan=p01
Default Exp/Contr=0.3,0.1
English Units
Geom File=g01
Flow File=f01
Plan File=p01
Y Axis Title=Elevation
X Axis Title(PF)=Main Channel Distance
X Axis Title(XS)=Station
BEGIN DESCRIPTION:
UNT01861 IN SAND CR
END DESCRIPTION:
DSS Export Rating Curves= 0
DSS Export Rating Curve Sorted= 0
DSS Export Volume Flow Curves= 0
DXF OffsetX= 0
DXF OffsetY= 0
DXF ScaleX= 1
DXF ScaleY= 10

--- UNT01861 IN SAND CR.p01 (plan) ---

Plan Title=Multiple Run
Short Identifier=Multiple
Geom File=g01
Flow File=f01
Subcritical Flow
K Sum by GR= 0
Std Step Tol= 0.01
Critical Tol= 0.01
Num of Std Step Trials= 20
Max Error Tol= 0.3
Flow Tol Ratio= 0.001
Split Flow NTrial= 30
Split Flow Tol= 0.02
Split Flow Ratio= 0.02
Log Output Level= 0
Friction Slope Method= 1
Unsteady Friction Slope Method= 2
Unsteady Bridges Friction Slope Method= 1
Parabolic Critical Depth
Global Vel Dist=  1 , 1 , 1
Global Log Level= 0
CheckData=True
Encroach Param= -1, 0, 0, 0
BEGIN DESCRIPTION:
Multiple Run
END DESCRIPTION:

--- UNT01861 IN SAND CR.f01 (steady flow) ---

Flow Title=Multiple
Number of Profiles=7
Profile Names=10-year,25-year,50-year,1pct_min,100-year,1pct_plu,500-year
River Rch & RM= UNT01861 IN SAND,Reach-1,2791
     412     537     635     550     744    1007    1017
Boundary for River Rch & Prof#=UNT01861 IN SAND,Reach-1,1
Up Type=0
Dn Type=3
Dn Slope=0.005
Boundary for River Rch & Prof#=UNT01861 IN SAND,Reach-1,2
Up Type=0
Dn Type=3
Dn Slope=0.005
Boundary for River Rch & Prof#=UNT01861 IN SAND,Reach-1,3
Up Type=0
Dn Type=3
Dn Slope=0.005
Boundary for River Rch & Prof#=UNT01861 IN SAND,Reach-1,4
Up Type=0
Dn Type=3
Dn Slope=0.005
Boundary for River Rch & Prof#=UNT01861 IN SAND,Reach-1,5
Up Type=0
Dn Type=3
Dn Slope=0.005
Boundary for River Rch & Prof#=UNT01861 IN SAND,Reach-1,6
Up Type=0
Dn Type=3
Dn Slope=0.005
Boundary for River Rch & Prof#=UNT01861 IN SAND,Reach-1,7
Up Type=0
Dn Type=3
Dn Slope=0.005

--- UNT01861 IN SAND CR.g01 (geometry) ---

Geom Title=Existing Conditions
Program Version=4.10

River Reach=UNT01861 IN SAND,Reach-1
Reach XY= 30
      3563596.26     10518737.94      3563608.68     10518812.86
      3563679.53     10518912.82      3563706.81     10519054.66
       3563796.1     10519063.55       3563873.4      10519108.5
      3564018.46     10519139.49      3564056.81     10519188.98
      3564069.92      10519255.2      3564154.49     10519285.85
      3564163.67     10519368.48      3564187.54     10519406.24
      3564270.52     10519425.26      3564445.06     10519526.42
      3564495.45     10519615.17      3564552.42     10519664.59
      3564514.22      10519744.8      3564539.22     10519820.15
      3564589.57     10519877.79      3564557.28     10519897.93
      3564534.36     10519952.09      3564593.53     10520084.83
       3564560.2     10520110.52      3564543.53     10520172.33
      3564473.67     10520185.26      3564357.38     10520251.31
      3564123.27     10520314.64      3564069.65     10520357.25
       3563982.7       10520384.      3563951.89     10520512.72

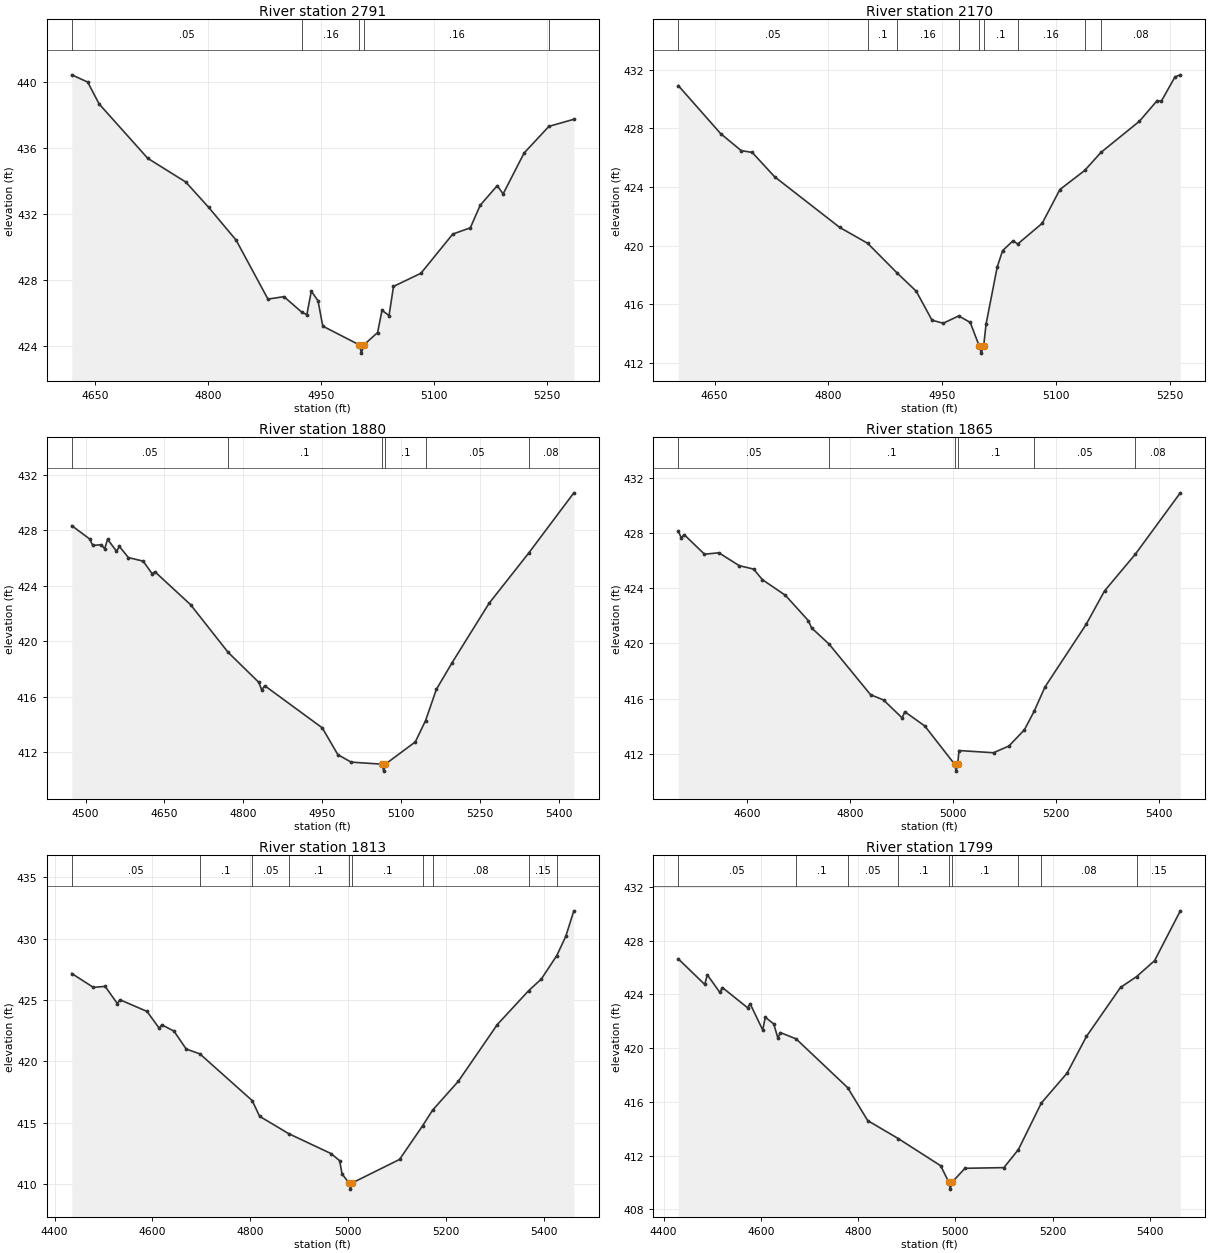
Type RM Length L Ch R = 1 ,2791    ,621,621,621
BEGIN DESCRIPTION:
UNT01861 IN SAND CR 4.0
END DESCRIPTION:
XS GIS Cut Line= 2
      3563297.27      10519026.7      3563857.63     10518666.95
#Sta/Elev= 30
  4619.5  440.44  4640.6     440  4655.8  438.67  4720.3  435.37  4770.7  433.93
  4801.1  432.39  4837.5   430.4  4879.7  426.82  4900.9  426.97    4925  426.01
  4931.3  425.88  4937.2   427.3  4946.1  426.72  4952.4  425.18  5000.9  424.04
  5003.7  423.54  5006.9  424.04  5025.1  424.79    5031  426.14  5040.3  425.82
  5046.2  427.59  5082.6  428.39  5124.8  430.77  5148.1  431.15  5161.2  432.52
  5183.8  433.71  5191.6  433.21  5219.4  435.69  5252.3  437.31  5285.4  437.74
#Mann= 5 ,-1 , 0
  4619.5     .05       0    4925     .16       0  5000.9     .07       0
  5006.9     .16       0  5252.3     .05       0
Bank Sta=5000.9,5006.9
XS Rating Curve= 0 ,0
Exp/Cntr=0.3,0.1

Type RM Length L Ch R = 1 ,2170    ,290,290,290
BEGIN DESCRIPTION:
UNT01861 IN SAND CR 3.0
END DESCRIPTION:
XS GIS Cut Line= 3
      3563715.47     10519391.86      3564088.77     10519122.74
      3564169.07     10518938.25
#Sta/Elev= 30
  4602.2  430.93    4658  427.65    4685  426.49  4699.7  426.36  4729.2   424.7
    4815  421.24  4851.7  420.16  4890.4  418.14  4915.7  416.89  4936.5  414.91
  4951.3   414.7  4971.6   415.2  4986.8  414.76  4998.6  413.16  5001.3  412.66
  5004.6  413.16  5007.7  414.64  5022.4  418.54  5029.5  419.66  5043.3  420.33
  5049.4  420.11  5081.6  421.52    5105  423.83  5137.6  425.13    5159  426.36
  5209.7  428.49  5233.1   429.9  5238.6  429.86  5256.6  431.52  5263.6  431.66
#Mann= 9 ,-1 , 0
  4602.2     .05       0  4851.7      .1       0  4890.4     .16       0
  4971.6      .1       0  4998.6     .07       0  5004.6      .1       0
  5049.4     .16       0  5137.6     .05       0    5159     .08       0
Bank Sta=4998.6,5004.6
XS Rating Curve= 0 ,0
Exp/Cntr=0.3,0.1

Type RM Length L Ch R = 1 ,1880    ,15,15,15
BEGIN DESCRIPTION:
UNT01861 IN SAND CR 3.2
END DESCRIPTION:
XS GIS Cut Line= 5
      3563831.58     10519694.37      3564157.13      10519535.5
      3564151.05     10519398.35      3564171.88      10519369.7
      3564177.09     10518950.39
#Sta/Elev= 30
  4473.9  428.33  4507.9  427.37  4513.9   426.9  4530.1  426.96  4536.4  426.66
    4542  427.35  4558.9  426.49  4564.5  426.83  4581.5  426.03  4609.6  425.77
  4626.5  424.87  4632.1     425  4699.7  422.63  4771.1  419.19  4829.3  417.03
  4834.8  416.49  4840.8  416.78  4950.1  413.74  4979.6  411.81  5004.8  411.27
  5063.9  411.12  5066.7  410.62  5069.9  411.12  5126.9  412.73  5146.4  414.27
  5166.9  416.52  5196.9  418.45  5266.9  422.72  5342.5  426.36  5428.2   430.7
#Mann= 6 ,-1 , 0
  4473.9     .05       0  4771.1      .1       0  5063.9     .07       0
  5069.9      .1       0  5146.4     .05       0  5342.5     .08       0
Bank Sta=5063.9,5069.9
XS Rating Curve= 0 ,0
Exp/Cntr=0.3,0.1

Type RM Length L Ch R = 1 ,1865    ,52,52,52
BEGIN DESCRIPTION:
UNT01861 IN SAND CR 3.1
END DESCRIPTION:
XS GIS Cut Line= 6
      3563834.89     10519710.83      3564171.23     10519545.92
      3564162.33      10519413.1      3564178.83     10519376.64
       3564182.3     10519095.39      3564183.17     10518948.69
#Sta/Elev= 30
  4466.2  428.12  4472.2  427.65  4477.8  427.87  4517.2  426.46  4545.2  426.56
  4584.7  425.63  4612.7  425.38  4629.6  424.62  4674.6  423.48  4719.3  421.64
  4725.2  421.13  4759.2  419.96    4840  416.29  4865.1  415.91  4901.4  414.61
  4906.4  415.06  4945.3  414.03  5003.3  411.26  5006.1  410.76  5009.3  411.26
  5011.8  412.25  5078.9  412.09  5108.9  412.58  5138.9  413.75  5158.1  415.11
  5178.9  416.85  5258.9  421.38  5294.6   423.8  5354.3  426.45  5441.9   430.9
#Mann= 6 ,-1 , 0
  4466.2     .05       0  4759.2      .1       0  5003.3     .07       0
  5009.3      .1       0  5158.1     .05       0  5354.3     .08       0
Bank Sta=5003.3,5009.3
XS Rating Curve= 0 ,0
Exp/Cntr=0.3,0.1

Type RM Length L Ch R = 1 ,1813    ,14,14,14
BEGIN DESCRIPTION:
UNT01861 IN SAND CR 3.3
END DESCRIPTION:
XS GIS Cut Line= 4
      3563850.75     10519719.54      3564214.07     10519584.11
      3564220.58     10519235.15      3564220.58     10518945.11
#Sta/Elev= 30
  4435.1  427.16  4479.2  426.03  4503.3  426.11  4528.3  424.71  4533.6  425.02
  4588.9  424.07  4613.9   422.7  4619.2  422.98  4644.2  422.46  4669.2     421
    4697  420.61  4804.1   416.8  4819.2  415.52  4878.8   414.1  4965.3  412.48
  4982.9   411.9  4987.9  410.81  5002.3  410.08  5005.1  409.58  5008.3  410.08
  5105.4     412  5152.5  414.74    5173  416.02  5225.4  418.36  5305.4     423
  5369.2  425.75  5395.4  426.71    5427  428.62  5445.4  430.19  5461.9  432.27
#Mann= 10 ,-1 , 0
  4435.1     .05       0    4697      .1       0  4804.1     .05       0
  4878.8      .1       0  5002.3     .07       0  5008.3      .1       0
  5152.5     .05       0    5173     .08       0  5369.2     .15       0
    5427     .08       0
Bank Sta=5002.3,5008.3
XS Rating Curve= 0 ,0
Exp/Cntr=0.3,0.1

Type RM Length L Ch R = 1 ,1799    ,542,542,542
BEGIN DESCRIPTION:
UNT01861 IN SAND CR 3.4
END DESCRIPTION:
XS GIS Cut Line= 3
      3563866.39     10519724.74      3564227.09     10519599.74
      3564238.81     10518948.69
#Sta/Elev= 30
    4430  426.65  4484.5  424.74  4489.8  425.46  4515.6  424.15  4520.9  424.51
  4572.6  423.01  4577.9  423.31  4603.8  421.35  4609.1   422.3  4626.6   421.8
  4634.9  420.76  4640.2  421.16  4672.5  420.69  4778.6  417.06  4819.8  414.61
  4882.8  413.27  4969.9  411.25  4986.9  410.01  4989.6  409.51  4992.9  410.01
  5019.9  411.06  5099.9  411.11  5129.7  412.45    5177  415.92  5229.9  418.14
  5269.9  420.88  5339.9  424.52  5373.1  425.33  5409.9  426.51  5462.9  430.22
#Mann= 9 ,-1 , 0
    4430     .05       0  4672.5      .1       0  4778.6     .05       0
  4882.8      .1       0  4986.9     .07       0  4992.9      .1       0
  5129.7     .05       0    5177     .08       0  5373.1     .15       0
Bank Sta=4986.9,4992.9
XS Rating Curve= 0 ,0
Exp/Cntr=0.3,0.1

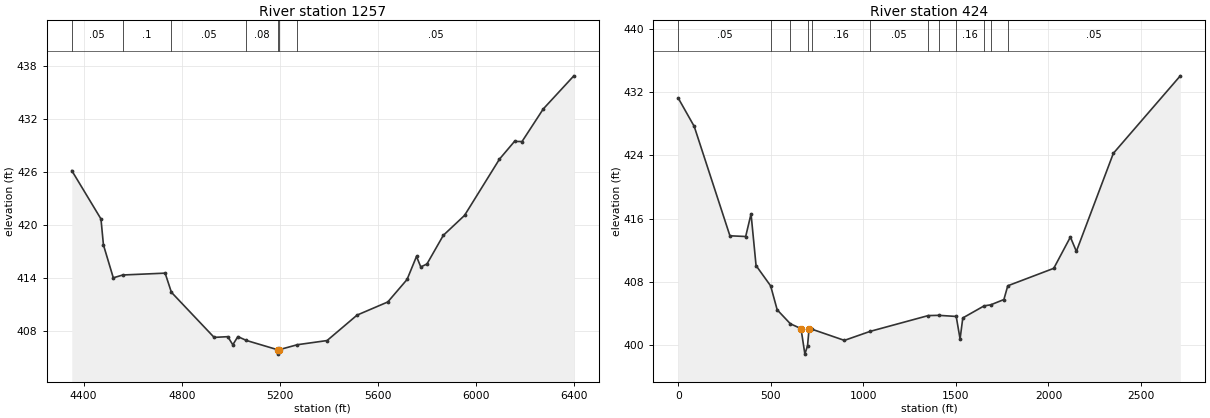
Type RM Length L Ch R = 1 ,1257    ,833,833,833
BEGIN DESCRIPTION:
UNT01861 IN SAND CR 2.0
END DESCRIPTION:
XS GIS Cut Line= 4
      3563883.85     10519748.57      3564358.09     10519801.72
      3564725.28     10519710.57      3565845.02     10519304.34
#Sta/Elev= 30
  4351.5  426.16  4470.5  420.67  4480.6  417.72  4520.8  413.99  4559.5  414.31
  4732.1  414.52  4757.6  412.35  4931.8  407.23  4987.4  407.31    5008  406.39
  5028.6  407.32  5063.5  406.88  5190.5  405.83  5193.2  405.33  5196.5  405.83
  5271.5   406.4  5392.2  406.87  5514.6  409.76  5639.8  411.25  5718.3   413.8
  5756.8  416.42  5774.2  415.22  5799.4  415.56  5866.1  418.81  5952.6  421.07
  6095.1  427.46  6156.3  429.47  6186.9  429.45  6273.5  433.15  6398.2  436.91
#Mann= 7 ,-1 , 0
  4351.5     .05       0  4559.5      .1       0  4757.6     .05       0
  5063.5     .08       0  5190.5     .03       0  5196.5     .08       0
  5271.5     .05       0
Bank Sta=5190.5,5196.5
XS Rating Curve= 0 ,0
Exp/Cntr=0.3,0.1

Type RM Length L Ch R = 1 ,424     ,0,0,0
BEGIN DESCRIPTION:
UNT01861 IN SAND CR 1.0
END DESCRIPTION:
XS GIS Cut Line= 6
      3563720.07     10519832.97      3564154.96     10520168.91
      3564319.03     10520372.03      3564522.93     10520407.82
      3565022.09     10519716.58      3565802.69     10519401.24
#Sta/Elev= 30
       0  431.25    86.3  427.67   279.2  413.82   364.3  413.73   393.3  416.59
   420.4  410.05   499.2  407.48   534.5  404.45   605.8  402.68   663.3  402.07
   684.1  398.84   698.5   399.9   706.5  401.98   720.2  402.01   897.6  400.58
  1036.7  401.72  1350.7  403.72  1407.7  403.75  1501.6  403.61  1522.5  400.76
  1537.2  403.42  1652.5  404.95  1688.1  405.08  1759.2  405.75  1780.1  407.49
  2028.5   409.7  2118.4  413.66  2150.7  411.85  2350.5  424.26  2712.2  434.07
#Mann= 12 ,-1 , 0
       0     .05       0   499.2     .08       0   605.8     .16       0
   698.5     .07       0   720.2     .16       0  1036.7     .05       0
  1350.7     .16       0  1407.7     .05       0  1501.6     .16       0
  1652.5     .05       0  1688.1     .16       0  1780.1     .05       0
Bank Sta=663.3,706.5
XS Rating Curve= 0 ,0
Exp/Cntr=0.3,0.1

Chan Stop Cuts=-1
Use User Specified Reach Order=0
Composite Channel Slope=5