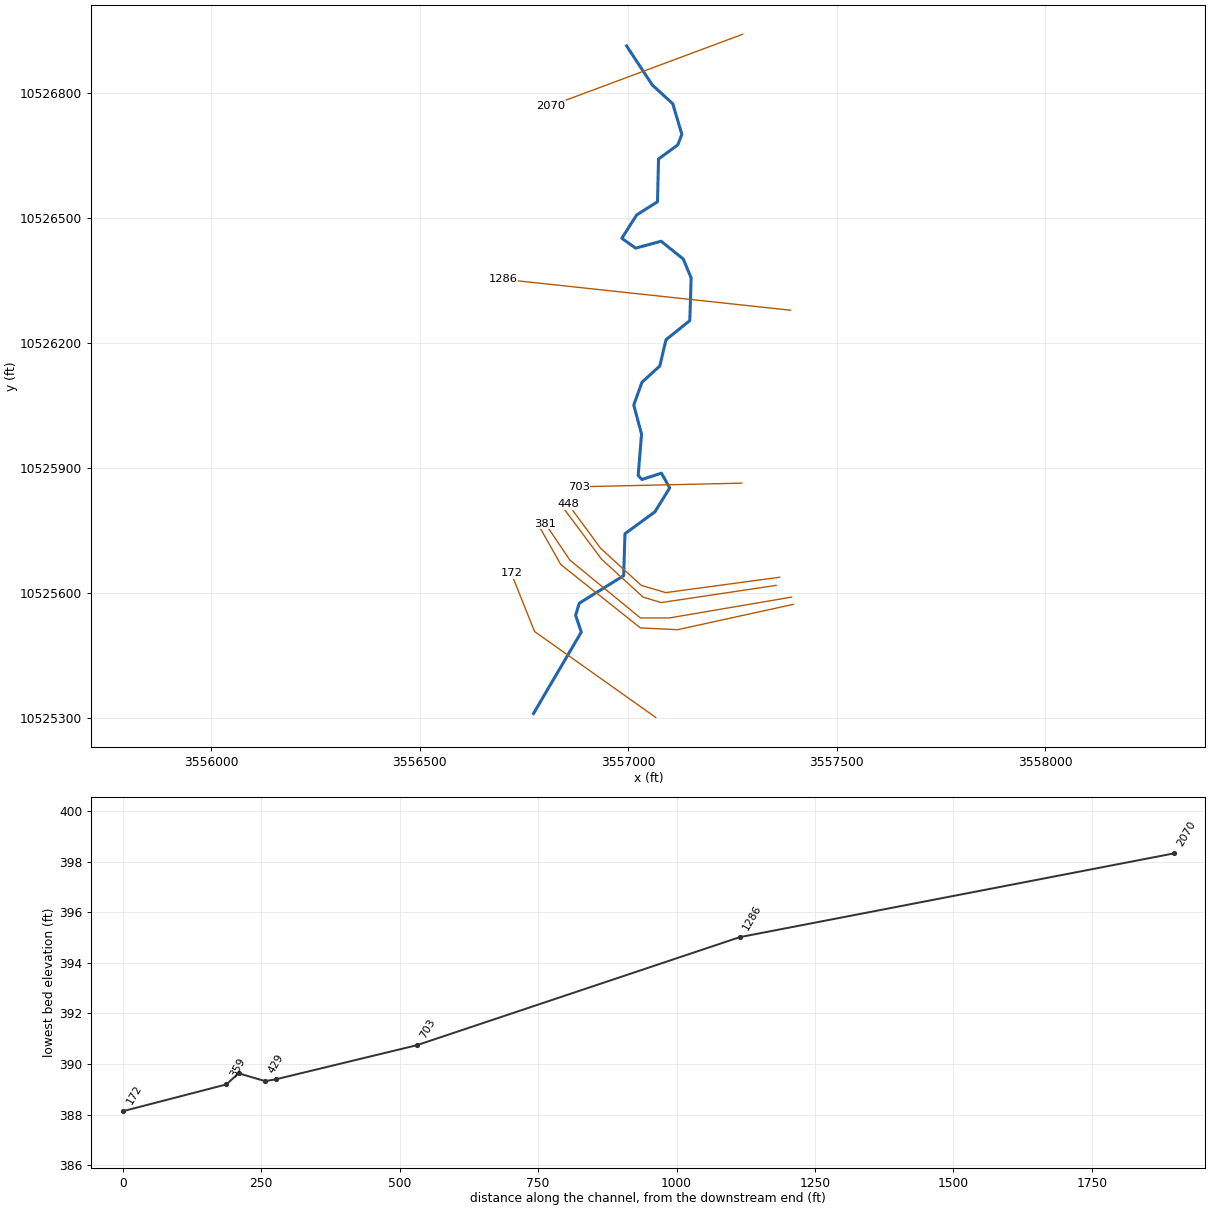
--- UNT01869 IN SAND CR.prj (project) ---

Proj Title=UNT01869 IN SAND CR Base Level Engineering
Current Plan=p01
Default Exp/Contr=0.3,0.1
English Units
Geom File=g01
Flow File=f01
Plan File=p01
BEGIN DESCRIPTION:
UNT01869 IN SAND CR
END DESCRIPTION:

--- UNT01869 IN SAND CR.p01 (plan) ---

Plan Title=Multiple Run
Short Identifier=Multiple
Geom File=g01
Flow File=f01
Subcritical Flow
K Sum by GR= 0
Std Step Tol= 0.01
Critical Tol= 0.01
Num of Std Step Trials= 20
Max Error Tol= 0.3
Flow Tol Ratio= 0.001
Split Flow NTrial= 30
Split Flow Tol= 0.02
Split Flow Ratio= 0.02
Log Output Level= 0
Friction Slope Method= 1
Unsteady Friction Slope Method= 2
Unsteady Bridges Friction Slope Method= 1
Parabolic Critical Depth
Global Vel Dist=  1 , 1 , 1
Global Log Level= 0
CheckData=True
Encroach Param= -1, 0, 0, 0
BEGIN DESCRIPTION:
Multiple Run
END DESCRIPTION:

--- UNT01869 IN SAND CR.f01 (steady flow) ---

Flow Title=Multiple
Number of Profiles=7
Profile Names=10-year,25-year,50-year,1pct_min,100-year,1pct_plu,500-year
River Rch & RM= UNT01869 IN SAND,Reach-1,2070
     341     436     510     438     592     800     790
Boundary for River Rch & Prof#=UNT01869 IN SAND,Reach-1,1
Up Type=0
Dn Type=3
Dn Slope=0.005
Boundary for River Rch & Prof#=UNT01869 IN SAND,Reach-1,2
Up Type=0
Dn Type=3
Dn Slope=0.005
Boundary for River Rch & Prof#=UNT01869 IN SAND,Reach-1,3
Up Type=0
Dn Type=3
Dn Slope=0.005
Boundary for River Rch & Prof#=UNT01869 IN SAND,Reach-1,4
Up Type=0
Dn Type=3
Dn Slope=0.005
Boundary for River Rch & Prof#=UNT01869 IN SAND,Reach-1,5
Up Type=0
Dn Type=3
Dn Slope=0.005
Boundary for River Rch & Prof#=UNT01869 IN SAND,Reach-1,6
Up Type=0
Dn Type=3
Dn Slope=0.005
Boundary for River Rch & Prof#=UNT01869 IN SAND,Reach-1,7
Up Type=0
Dn Type=3
Dn Slope=0.005

--- UNT01869 IN SAND CR.g01 (geometry) ---

Geom Title=Existing Conditions

River Reach=UNT01869 IN SAND,Reach-1
Reach XY= 30
      3556995.81     10526912.73      3557057.30     10526819.29
      3557106.53     10526773.99      3557128.41     10526700.67
      3557118.59     10526675.43      3557072.37     10526641.53
      3557069.94     10526538.99      3557019.86     10526507.30
      3556984.36     10526451.31      3557017.52     10526427.72
      3557078.54     10526444.29      3557131.68     10526401.72
      3557150.60     10526356.36      3557147.45     10526254.02
      3557090.24     10526207.90      3557075.46     10526145.03
      3557032.62     10526105.94      3557012.96     10526051.30
      3557031.68     10525981.45      3557023.54     10525882.35
      3557032.51     10525872.79      3557079.39     10525887.90
      3557099.18     10525852.48      3557063.76     10525795.19
      3556991.89     10525742.59      3556988.76     10525642.06
      3556882.28     10525575.98      3556873.51     10525546.99
      3556887.07     10525506.67      3556772.45     10525311.25

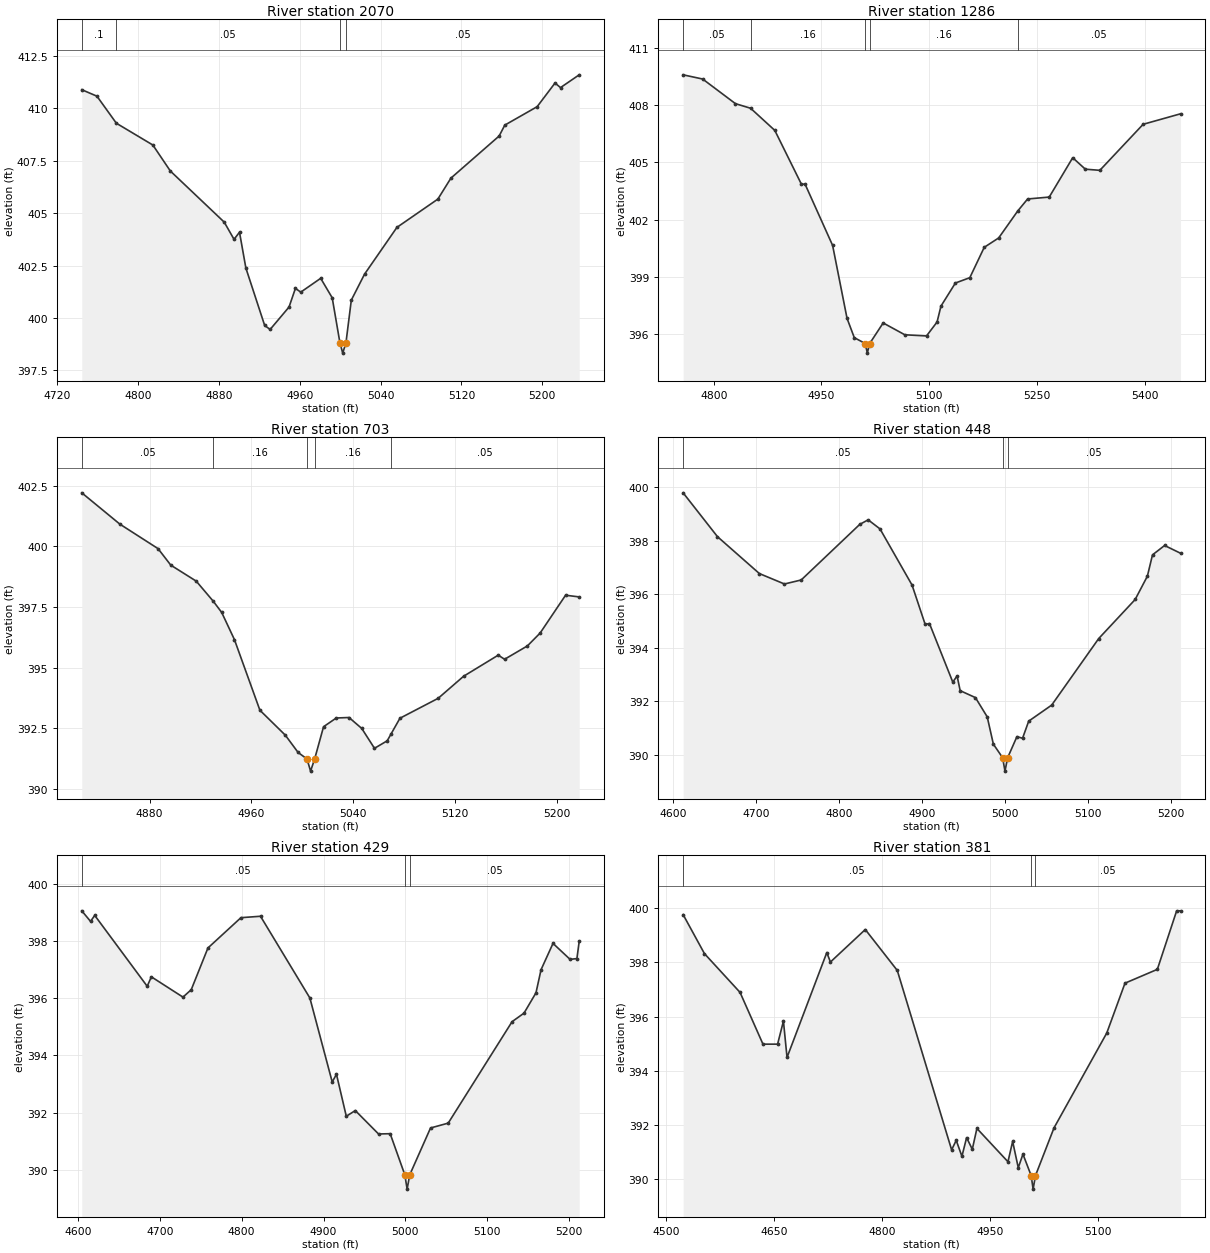
Type RM Length L Ch R = 1,2070,784,784,784
BEGIN DESCRIPTION:
UNT01869 IN SAND CR 4.0
END DESCRIPTION:
XS GIS Cut Line= 2
      3557274.16     10526940.79      3556813.16     10526768.90
#Sta/Elev= 30
  4744.5  410.89  4759.5  410.58  4778.7  409.29  4814.8  408.25  4832.1  407.01
  4885.4  404.57  4895.1  403.75  4900.5  404.09  4906.8  402.38  4925.4  399.64
  4930.8  399.45  4949.5  400.52  4955.8  401.41  4961.1  401.23  4980.8  401.89
  4992.2  400.96  4999.8  398.82  5002.6  398.32  5005.8  398.82  5011.1  400.85
  5024.2  402.09  5056.2  404.32  5096.7  405.67  5109.6  406.67  5157.3  408.68
  5162.9  409.20  5194.9  410.08  5212.6  411.21  5218.0  410.99  5236.5  411.60
#Mann=4,-1,0
  4744.5     0.1       0  4778.7    0.05       0  4999.8    0.03       0
  5005.8    0.05       0
Bank Sta=4999.8,5005.8
Exp/Cntr=0.3,0.1

Type RM Length L Ch R = 1,1286,583,583,583
BEGIN DESCRIPTION:
UNT01869 IN SAND CR 3.0
END DESCRIPTION:
XS GIS Cut Line= 2
      3557389.12     10526278.78      3556700.31     10526353.00
#Sta/Elev= 30
  4757.3  409.58  4784.5  409.36  4830.2  408.07  4851.3  407.83  4885.0  406.67
  4922.1  403.85  4927.1  403.86  4965.5  400.65  4985.6  396.83  4995.7  395.82
  5011.1  395.51  5013.8  395.01  5017.1  395.51  5035.9  396.59  5066.1  395.97
  5096.3  395.91  5111.0  396.64  5116.4  397.47  5136.5  398.68  5156.6  398.96
  5176.7  400.55  5196.8  401.04  5223.3  402.45  5237.1  403.08  5267.2  403.18
  5299.9  405.24  5317.5  404.64  5337.7  404.58  5398.0  406.99  5450.1  407.54
#Mann=5,-1,0
  4757.3    0.05       0  4851.3    0.16       0  5011.1    0.07       0
  5017.1    0.16       0  5223.3    0.05       0
Bank Sta=5011.1,5017.1
Exp/Cntr=0.3,0.1

Type RM Length L Ch R = 1,703,255,255,255
BEGIN DESCRIPTION:
UNT01869 IN SAND CR 2.0
END DESCRIPTION:
XS GIS Cut Line= 2
      3557271.97     10525863.96      3556881.37     10525855.28
#Sta/Elev= 30
  4826.8  402.21  4856.7  400.92  4886.7  399.91  4896.7  399.23  4916.7  398.57
  4930.1  397.74  4936.7  397.28  4946.7  396.16  4966.7  393.25  4986.7  392.22
  4996.7  391.51  5003.7  391.24  5006.5  390.74  5009.7  391.24  5016.7  392.57
  5026.7  392.93  5036.7  392.95  5046.7  392.50  5056.7  391.68  5066.7  391.99
  5069.7  392.27  5076.7  392.92  5106.7  393.74  5126.7  394.65  5153.9  395.52
  5158.9  395.35  5176.8  395.90  5186.8  396.43  5206.8  397.99  5217.5  397.92
#Mann=5,-1,0
  4826.8    0.05       0  4930.1    0.16       0  5003.7    0.07       0
  5009.7    0.16       0  5069.7    0.05       0
Bank Sta=5003.7,5009.7
Exp/Cntr=0.3,0.1

Type RM Length L Ch R = 1,448,19,19,19
BEGIN DESCRIPTION:
UNT01869 IN SAND CR 1.3
END DESCRIPTION:
XS GIS Cut Line= 5
      3557363.09     10525638.26      3557089.66     10525601.37
      3557031.07     10525618.73      3556933.41     10525707.71
      3556856.22     10525812.77
#Sta/Elev= 30
  4612.3  399.80  4653.7  398.16  4704.2  396.78  4734.4  396.39  4754.6  396.54
  4825.2  398.62  4835.3  398.79  4849.6  398.45  4888.2  396.35  4904.0  394.88
  4909.2  394.91  4937.3  392.72  4942.5  392.95  4946.2  392.40  4964.6  392.14
  4978.8  391.42  4986.2  390.40  4997.4  389.89  5000.2  389.39  5003.4  389.89
  5014.6  390.68  5021.4  390.62  5028.8  391.26  5056.5  391.86  5113.2  394.35
  5157.1  395.81  5171.8  396.68  5178.0  397.48  5192.6  397.83  5211.8  397.54
#Mann=3,-1,0
  4612.3    0.05       0  4997.4    0.03       0  5003.4    0.05       0
Bank Sta=4997.4,5003.4
Exp/Cntr=0.3,0.1

Type RM Length L Ch R = 1,429,48,48,48
BEGIN DESCRIPTION:
UNT01869 IN SAND CR 2.1
END DESCRIPTION:
XS GIS Cut Line= 5
      3557354.38     10525618.72      3557078.81     10525577.50
      3557035.41     10525590.52      3556935.58     10525681.66
      3556846.84     10525800.71
#Sta/Elev= 30
  4604.7  399.06  4615.4  398.69  4620.5  398.90  4684.6  396.42  4689.7  396.75
  4728.3  396.04  4738.4  396.30  4758.8  397.76  4799.1  398.82  4823.0  398.87
  4883.3  396.01  4910.6  393.07  4915.8  393.34  4927.8  391.87  4938.8  392.07
  4967.2  391.25  4981.4  391.26  4999.3  389.82  5002.1  389.32  5005.3  389.82
  5030.7  391.46  5052.3  391.63  5130.3  395.18  5144.9  395.48  5159.5  396.19
  5165.7  397.00  5180.3  397.92  5201.2  397.36  5209.5  397.39  5212.3  397.99
#Mann=3,-1,0
  4604.7    0.05       0  4999.3    0.03       0  5005.3    0.05       0
Bank Sta=4999.3,5005.3
Exp/Cntr=0.3,0.1

Type RM Length L Ch R = 1,381,22,22,22
BEGIN DESCRIPTION:
UNT01869 IN SAND CR 1.1
END DESCRIPTION:
XS GIS Cut Line= 5
      3557391.33     10525590.52      3557098.34     10525540.61
      3557028.90     10525540.61      3556859.63     10525679.49
      3556801.06     10525766.27
#Sta/Elev= 30
  4524.1  399.76  4553.7  398.32  4603.1  396.89  4634.9  394.98  4655.2  394.98
  4663.3  395.83  4668.3  394.49  4723.5  398.36  4728.5  398.01  4776.9  399.21
  4821.3  397.70  4896.7  391.08  4903.1  391.43  4911.0  390.84  4917.5  391.53
  4925.4  391.10  4931.8  391.87  4974.9  390.64  4981.4  391.39  4989.2  390.42
  4995.7  390.92  5007.1  390.13  5009.8  389.63  5013.1  390.13  5038.8  391.89
  5112.0  395.39  5137.3  397.23  5182.2  397.74  5209.0  399.90  5214.4  399.90
#Mann=3,-1,0
  4524.1    0.05       0  5007.1    0.03       0  5013.1    0.05       0
Bank Sta=5007.1,5013.1
Exp/Cntr=0.3,0.1

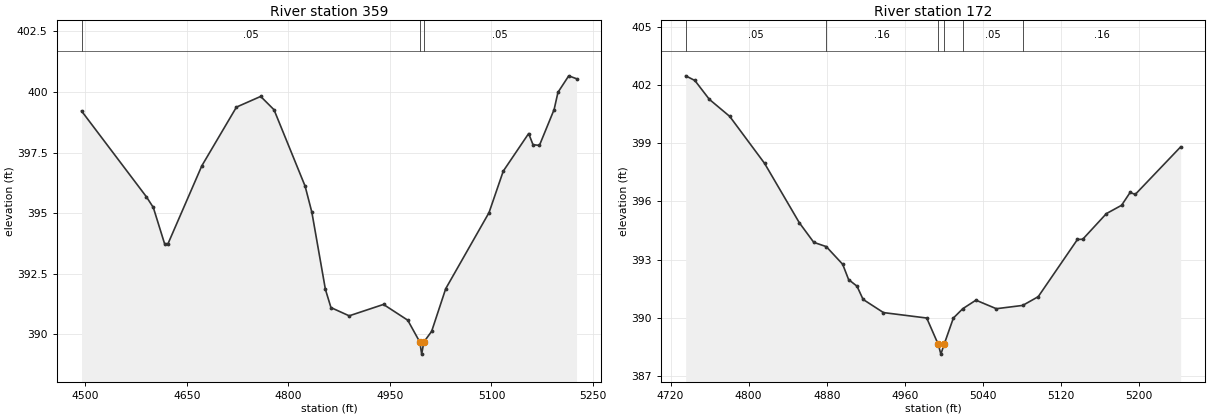
Type RM Length L Ch R = 1,359,187,187,187
BEGIN DESCRIPTION:
UNT01869 IN SAND CR 1.2
END DESCRIPTION:
XS GIS Cut Line= 5
      3557395.65     10525573.16      3557117.88     10525512.39
      3557028.90     10525516.73      3556837.93     10525668.64
      3556782.01     10525767.58
#Sta/Elev= 30
  4494.5  399.22  4590.3  395.68  4600.5  395.24  4617.2  393.74  4622.3  393.75
  4672.2  396.96  4723.3  399.38  4759.1  399.82  4778.8  399.27  4824.7  396.12
  4834.7  395.04  4854.7  391.86  4862.9  391.11  4889.8  390.77  4940.5  391.24
  4976.3  390.59  4994.1  389.69  4996.9  389.19  5000.1  389.69  5011.6  390.13
  5032.4  391.89  5096.4  395.03  5117.4  396.74  5154.9  398.29  5161.3  397.83
  5170.8  397.80  5192.5  399.28  5198.2  399.99  5214.1  400.67  5225.6  400.55
#Mann=3,-1,0
  4494.5    0.05       0  4994.1    0.03       0  5000.1    0.05       0
Bank Sta=4994.1,5000.1
Exp/Cntr=0.3,0.1

Type RM Length L Ch R = 1,172,0,0,0
BEGIN DESCRIPTION:
UNT01869 IN SAND CR 1.0
END DESCRIPTION:
XS GIS Cut Line= 3
      3557065.77     10525301.90      3556774.99     10525508.05
      3556719.08     10525647.84
#Sta/Elev= 30
  4735.5  402.47  4744.9  402.23  4759.7  401.26  4780.6  400.38  4816.3  397.96
  4851.9  394.90  4866.7  393.89  4879.5  393.67  4896.3  392.76  4902.4  391.97
  4911.0  391.63  4917.2  390.95  4938.1  390.27  4982.4  389.99  4994.2  388.63
  4996.9  388.13  5000.2  388.63  5009.7  389.99  5019.3  390.47  5032.8  390.91
  5053.7  390.47  5080.7  390.64  5096.6  391.09  5136.8  394.04  5142.2  394.05
  5166.4  395.37  5182.0  395.80  5190.7  396.46  5196.0  396.36  5242.5  398.81
#Mann=6,-1,0
  4735.5    0.05       0  4879.5    0.16       0  4994.2    0.07       0
  5000.2    0.16       0  5019.3    0.05       0  5080.7    0.16       0
Bank Sta=4994.2,5000.2
Exp/Cntr=0.3,0.1

Chan Stop Cuts=-1