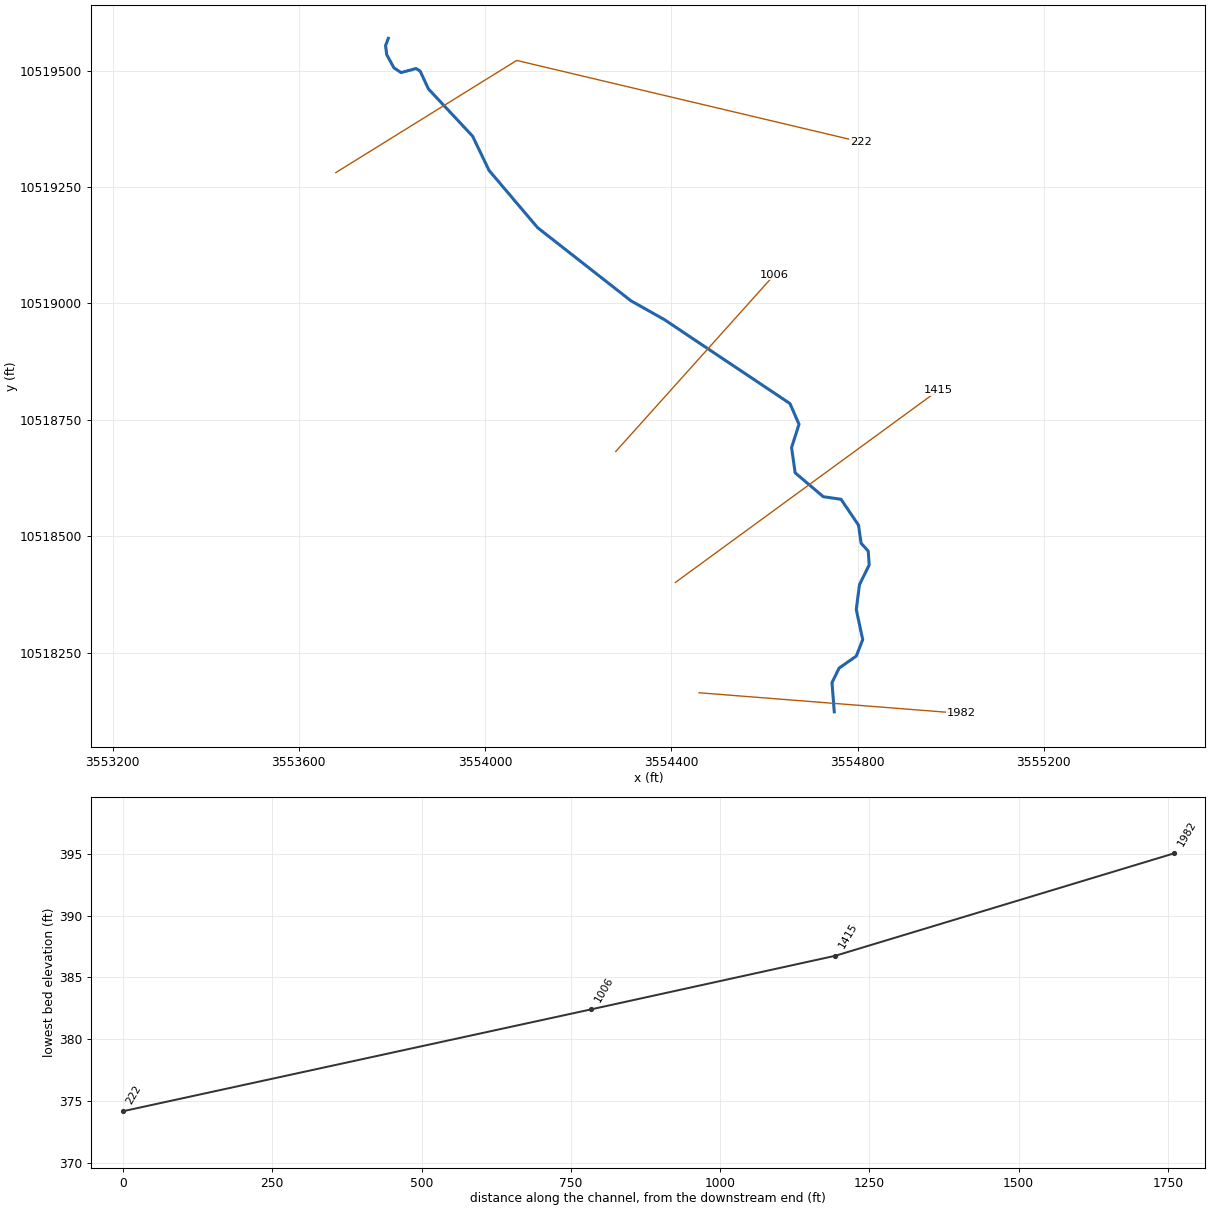
--- UNT01877 IN SAND CR.prj (project) ---

Proj Title=UNT01877 IN SAND CR Base Level Engineering
Current Plan=p01
Default Exp/Contr=0.3,0.1
English Units
Geom File=g01
Flow File=f01
Plan File=p01
BEGIN DESCRIPTION:
UNT01877 IN SAND CR
END DESCRIPTION:

--- UNT01877 IN SAND CR.p01 (plan) ---

Plan Title=Multiple Run
Short Identifier=Multiple
Geom File=g01
Flow File=f01
Subcritical Flow
K Sum by GR= 0
Std Step Tol= 0.01
Critical Tol= 0.01
Num of Std Step Trials= 20
Max Error Tol= 0.3
Flow Tol Ratio= 0.001
Split Flow NTrial= 30
Split Flow Tol= 0.02
Split Flow Ratio= 0.02
Log Output Level= 0
Friction Slope Method= 1
Unsteady Friction Slope Method= 2
Unsteady Bridges Friction Slope Method= 1
Parabolic Critical Depth
Global Vel Dist=  1 , 1 , 1
Global Log Level= 0
CheckData=True
Encroach Param= -1, 0, 0, 0
BEGIN DESCRIPTION:
Multiple Run
END DESCRIPTION:

--- UNT01877 IN SAND CR.f01 (steady flow) ---

Flow Title=Multiple
Number of Profiles=7
Profile Names=10-year,25-year,50-year,1pct_min,100-year,1pct_plu,500-year
River Rch & RM= UNT01877 IN SAND,Reach-1,1982
     191     235     268     225     304     411     387
Boundary for River Rch & Prof#=UNT01877 IN SAND,Reach-1,1
Up Type=0
Dn Type=3
Dn Slope=0.005
Boundary for River Rch & Prof#=UNT01877 IN SAND,Reach-1,2
Up Type=0
Dn Type=3
Dn Slope=0.005
Boundary for River Rch & Prof#=UNT01877 IN SAND,Reach-1,3
Up Type=0
Dn Type=3
Dn Slope=0.005
Boundary for River Rch & Prof#=UNT01877 IN SAND,Reach-1,4
Up Type=0
Dn Type=3
Dn Slope=0.005
Boundary for River Rch & Prof#=UNT01877 IN SAND,Reach-1,5
Up Type=0
Dn Type=3
Dn Slope=0.005
Boundary for River Rch & Prof#=UNT01877 IN SAND,Reach-1,6
Up Type=0
Dn Type=3
Dn Slope=0.005
Boundary for River Rch & Prof#=UNT01877 IN SAND,Reach-1,7
Up Type=0
Dn Type=3
Dn Slope=0.005

--- UNT01877 IN SAND CR.g01 (geometry) ---

Geom Title=Existing Conditions

River Reach=UNT01877 IN SAND,Reach-1
Reach XY= 30
      3554749.88     10518123.09      3554745.02     10518185.59
      3554760.29     10518216.84      3554797.10     10518242.53
      3554810.99     10518277.95      3554797.10     10518342.53
      3554804.04     10518396.00      3554824.88     10518438.36
      3554822.79     10518468.23      3554807.52     10518484.89
      3554801.96     10518523.78      3554764.46     10518579.34
      3554726.27     10518584.89      3554665.85     10518636.28
      3554658.21     10518690.45      3554674.18     10518740.45
      3554654.74     10518784.89      3554384.60     10518965.45
      3554313.07     10519005.73      3554112.72     10519162.67
      3554008.56     10519285.59      3553973.14     10519359.20
      3553878.35     10519460.59      3553860.64     10519498.78
      3553851.96     10519504.34      3553819.67     10519495.66
      3553804.39     10519505.73      3553788.77     10519534.20
      3553786.34     10519553.64      3553792.33     10519569.18

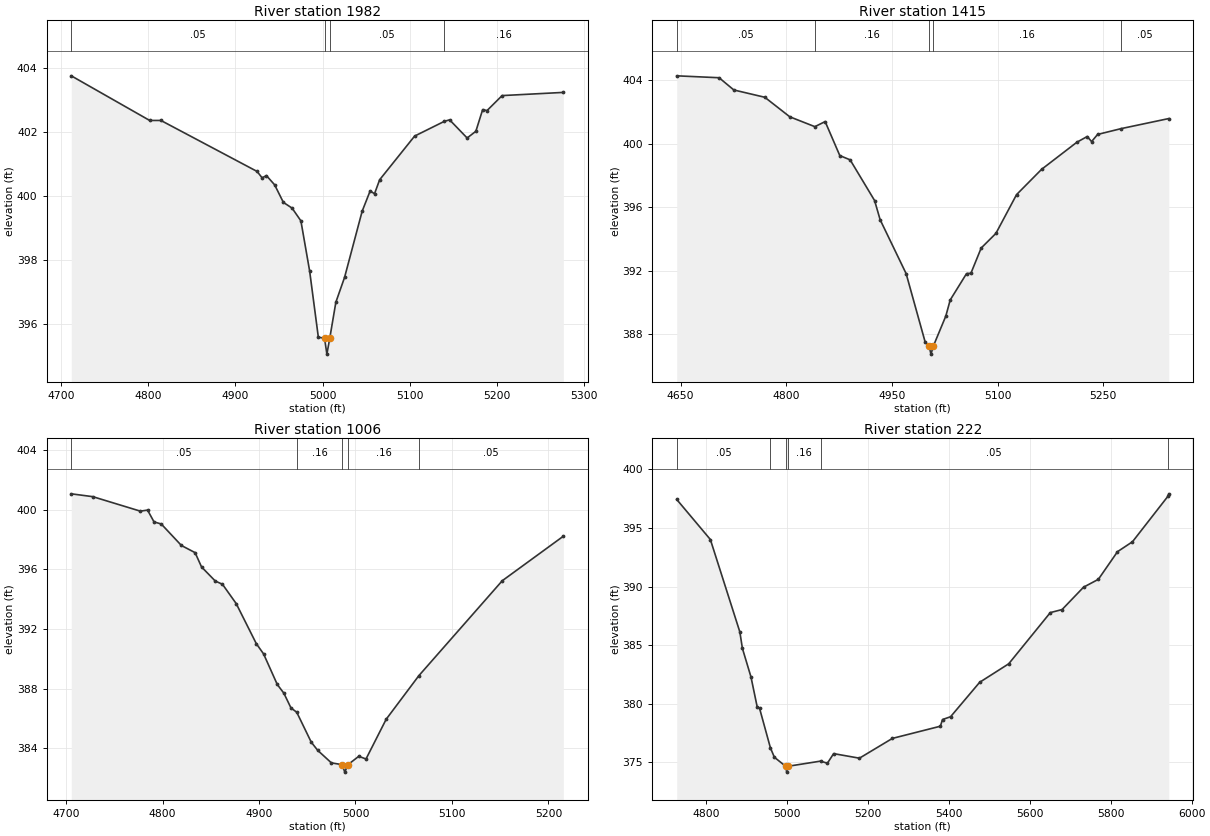
Type RM Length L Ch R = 1,1982,567,567,567
BEGIN DESCRIPTION:
UNT01877 IN SAND CR 4.0
END DESCRIPTION:
XS GIS Cut Line= 2
      3554459.64     10518163.86      3555022.10     10518119.60
#Sta/Elev= 30
  4711.9  403.77  4801.8  402.37  4814.7  402.37  4925.0  400.77  4930.7  400.57
  4935.7  400.64  4945.1  400.35  4955.1  399.80  4965.1  399.62  4975.2  399.22
  4985.2  397.65  4995.2  395.57  5002.3  395.54  5005.0  395.04  5008.3  395.54
  5015.3  396.67  5025.3  397.45  5045.4  399.52  5054.6  400.16  5059.6  400.07
  5065.5  400.51  5105.6  401.88  5139.5  402.34  5145.7  402.39  5165.8  401.82
  5175.8  402.03  5183.6  402.71  5188.6  402.68  5205.9  403.15  5276.1  403.25
#Mann=4,-1,0
  4711.9    0.05       0  5002.3    0.03       0  5008.3    0.05       0
  5139.5    0.16       0
Bank Sta=5002.3,5008.3
Exp/Cntr=0.3,0.1

Type RM Length L Ch R = 1,1415,409,409,409
BEGIN DESCRIPTION:
UNT01877 IN SAND CR 4.1
END DESCRIPTION:
XS GIS Cut Line= 2
      3554408.85     10518400.86      3554973.06     10518813.16
#Sta/Elev= 30
  4644.4  404.27  4704.6  404.15  4725.5  403.38  4769.5  402.92  4805.0  401.69
  4840.6  401.07  4855.2  401.39  4876.0  399.25  4890.7  398.98  4925.4  396.42
  4933.3  395.21  4970.2  391.82  4997.3  387.50  5002.8  387.25  5005.5  386.75
  5008.8  387.25  5026.6  389.15  5032.8  390.16  5056.0  391.82  5062.2  391.84
  5076.8  393.43  5097.7  394.35  5127.0  396.79  5162.5  398.38  5212.7  400.09
  5227.4  400.45  5233.6  400.13  5242.1  400.58  5275.9  400.95  5343.2  401.58
#Mann=5,-1,0
  4644.4    0.05       0  4840.6    0.16       0  5002.8    0.07       0
  5008.8    0.16       0  5275.9    0.05       0
Bank Sta=5002.8,5008.8
Exp/Cntr=0.3,0.1

Type RM Length L Ch R = 1,1006,784,784,784
BEGIN DESCRIPTION:
UNT01877 IN SAND CR 2.0
END DESCRIPTION:
XS GIS Cut Line= 2
      3554280.61     10518681.89      3554621.32     10519061.65
#Sta/Elev= 30
  4705.3  401.05  4727.6  400.86  4776.9  399.89  4784.4  399.96  4791.1  399.17
  4798.6  399.03  4819.5  397.59  4833.7  397.11  4840.4  396.15  4854.6  395.21
  4862.1  394.99  4876.3  393.70  4897.2  391.01  4904.7  390.33  4918.9  388.28
  4925.7  387.70  4933.1  386.71  4939.1  386.42  4954.1  384.42  4960.8  383.87
  4975.0  383.03  4986.2  382.91  4988.9  382.41  4992.2  382.91  5003.4  383.47
  5010.9  383.29  5031.8  385.95  5065.7  388.87  5152.2  395.23  5215.5  398.21
#Mann=5,-1,0
  4705.3    0.05       0  4939.1    0.16       0  4986.2    0.07       0
  4992.2    0.16       0  5065.7    0.05       0
Bank Sta=4986.2,4992.2
Exp/Cntr=0.3,0.1

Type RM Length L Ch R = 1,222,0,0,0
BEGIN DESCRIPTION:
UNT01877 IN SAND CR 1.0
END DESCRIPTION:
XS GIS Cut Line= 3
      3553679.48     10519280.83      3554067.92     10519521.71
      3554807.11     10519346.64
#Sta/Elev= 30
  4726.7  397.44  4809.9  394.02  4882.8  386.13  4889.1  384.73  4910.3  382.29
  4925.7  379.73  4931.6  379.60  4958.5  376.22  4968.2  375.43  4996.0  374.66
  4998.7  374.16  5002.0  374.66  5082.4  375.10  5099.3  374.92  5114.7  375.74
  5178.5  375.35  5260.0  377.04  5378.7  378.08  5383.9  378.65  5403.9  378.89
  5475.8  381.83  5547.7  383.41  5650.5  387.78  5679.6  388.04  5732.7  389.95
  5769.3  390.62  5816.6  392.98  5853.7  393.83  5941.5  397.72  5943.4  397.92
#Mann=6,-1,0
  4726.7    0.05       0  4958.5    0.16       0  4996.0    0.07       0
  5002.0    0.16       0  5082.4    0.05       0  5941.5     0.1       0
Bank Sta=4996,5002
Exp/Cntr=0.3,0.1

Chan Stop Cuts=-1