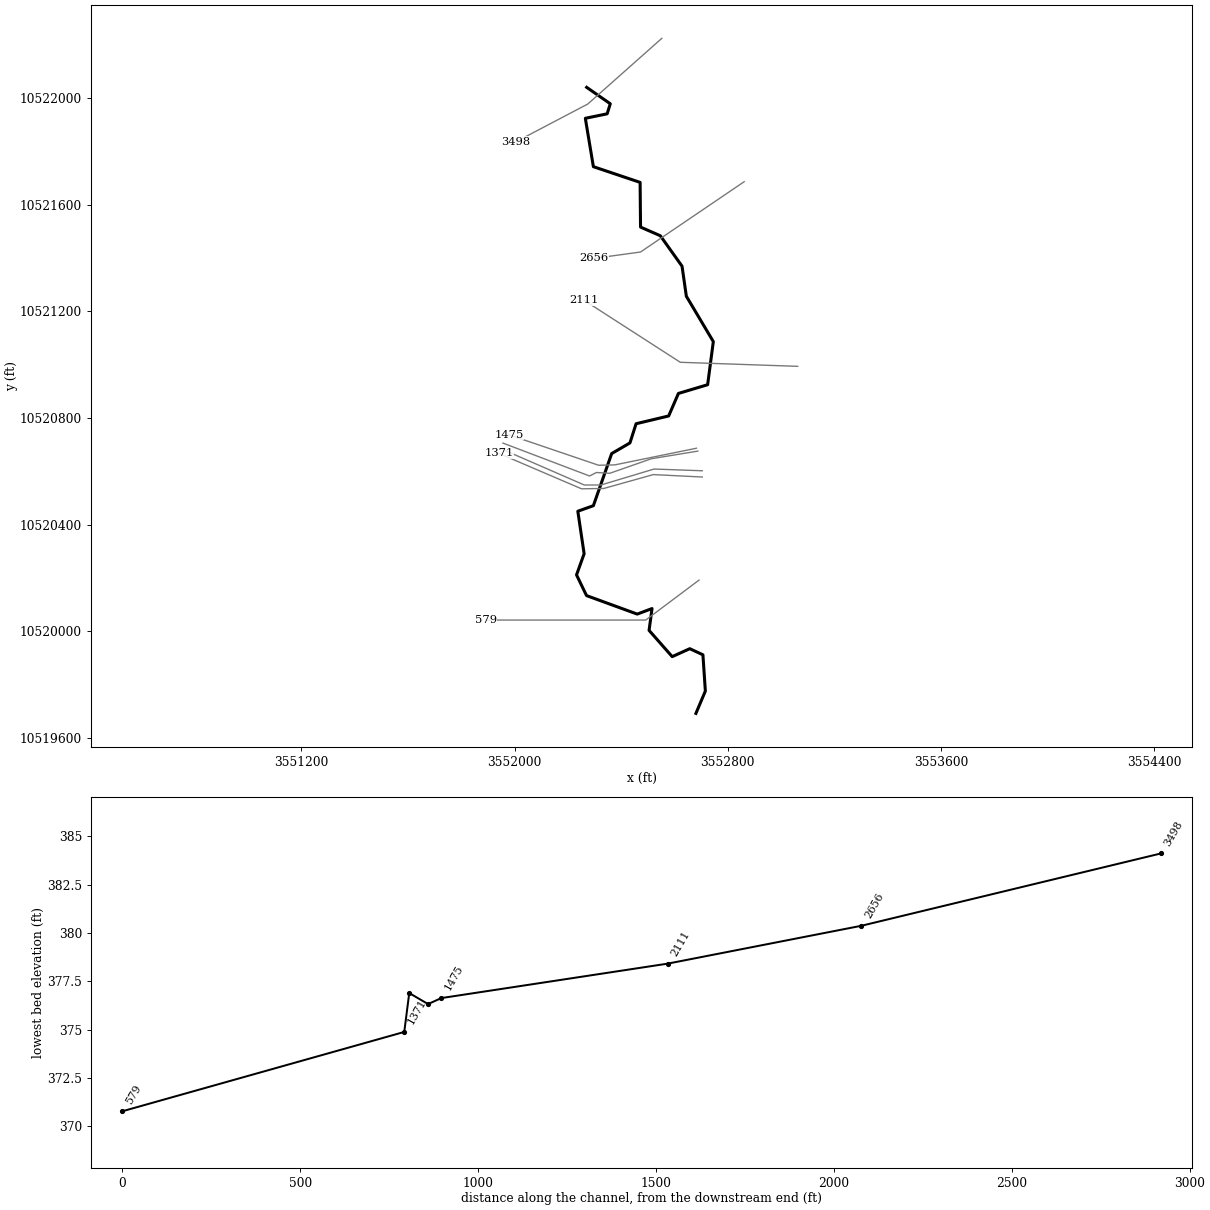
--- UNT01878 IN SAND CR.prj (project) ---

Proj Title=UNT01878 IN SAND CR Base Level Engineering
Current Plan=p01
Default Exp/Contr=0.3,0.1
English Units
Geom File=g01
Flow File=f01
Plan File=p01
BEGIN DESCRIPTION:
UNT01878 IN SAND CR
END DESCRIPTION:

--- UNT01878 IN SAND CR.p01 (plan) ---

Plan Title=Multiple Run
Short Identifier=Multiple
Geom File=g01
Flow File=f01
Subcritical Flow
K Sum by GR= 0
Std Step Tol= 0.01
Critical Tol= 0.01
Num of Std Step Trials= 20
Max Error Tol= 0.3
Flow Tol Ratio= 0.001
Split Flow NTrial= 30
Split Flow Tol= 0.02
Split Flow Ratio= 0.02
Log Output Level= 0
Friction Slope Method= 1
Unsteady Friction Slope Method= 2
Unsteady Bridges Friction Slope Method= 1
Parabolic Critical Depth
Global Vel Dist=  1 , 1 , 1
Global Log Level= 0
CheckData=True
Encroach Param= -1, 0, 0, 0
BEGIN DESCRIPTION:
Multiple Run
END DESCRIPTION:

--- UNT01878 IN SAND CR.f01 (steady flow) ---

Flow Title=Multiple
Number of Profiles=7
Profile Names=10-year,25-year,50-year,1pct_min,100-year,1pct_plu,500-year
River Rch & RM= UNT01878 IN SAND,Reach-1,3498
     855    1168    1425    1271    1718    2324    2489
Boundary for River Rch & Prof#=UNT01878 IN SAND,Reach-1,1
Up Type=0
Dn Type=3
Dn Slope=0.005
Boundary for River Rch & Prof#=UNT01878 IN SAND,Reach-1,2
Up Type=0
Dn Type=3
Dn Slope=0.005
Boundary for River Rch & Prof#=UNT01878 IN SAND,Reach-1,3
Up Type=0
Dn Type=3
Dn Slope=0.005
Boundary for River Rch & Prof#=UNT01878 IN SAND,Reach-1,4
Up Type=0
Dn Type=3
Dn Slope=0.005
Boundary for River Rch & Prof#=UNT01878 IN SAND,Reach-1,5
Up Type=0
Dn Type=3
Dn Slope=0.005
Boundary for River Rch & Prof#=UNT01878 IN SAND,Reach-1,6
Up Type=0
Dn Type=3
Dn Slope=0.005
Boundary for River Rch & Prof#=UNT01878 IN SAND,Reach-1,7
Up Type=0
Dn Type=3
Dn Slope=0.005

--- UNT01878 IN SAND CR.g01 (geometry) ---

Geom Title=Existing Conditions

River Reach=UNT01878 IN SAND,Reach-1
Reach XY= 30
      3552270.47     10522041.43      3552359.12     10521979.67
      3552347.32     10521942.01      3552265.47     10521925.16
      3552295.66     10521743.60      3552471.00     10521684.63
      3552472.67     10521516.82      3552546.95     10521484.26
      3552628.34     10521370.08      3552644.55     10521257.23
      3552745.78     10521086.98      3552724.43     10520925.09
      3552614.77     10520892.34      3552578.21     10520807.79
      3552455.91     10520778.62      3552432.91     10520706.57
      3552364.33     10520666.64      3552295.64     10520470.96
      3552237.31     10520450.12      3552260.92     10520290.40
      3552232.44     10520211.23      3552269.94     10520133.46
      3552460.22     10520064.01      3552515.78     10520084.85
      3552504.67     10520002.90      3552591.47     10519904.29
      3552657.44     10519934.15      3552706.75     10519911.23
      3552715.89     10519775.12      3552680.49     10519691.34

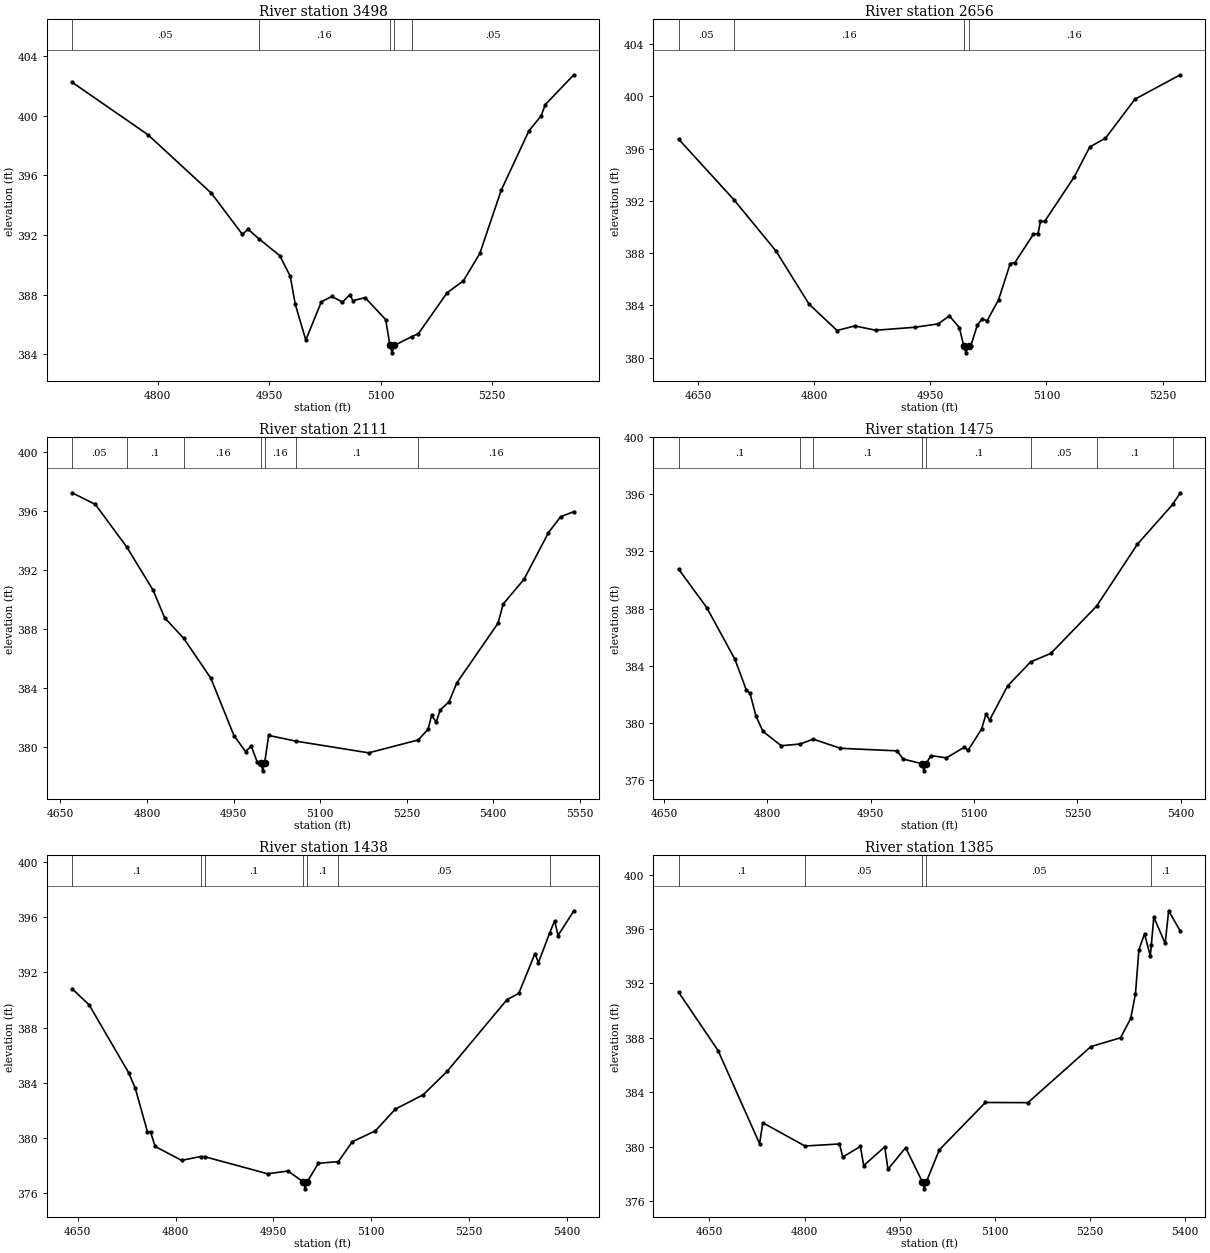
Type RM Length L Ch R = 1,3498,842,842,842
BEGIN DESCRIPTION:
UNT01878 IN SAND CR 6.1
END DESCRIPTION:
XS GIS Cut Line= 3
      3552552.51     10522225.36      3552274.70     10521978.80
      3552005.65     10521837.38
#Sta/Elev= 30
  4684.8  402.25  4787.0  398.73  4872.3  394.81  4914.1  392.05  4921.6  392.40
  4935.9  391.77  4964.3  390.63  4978.5  389.24  4985.2  387.37  4999.4  384.97
  5020.3  387.53  5034.5  387.89  5048.7  387.51  5058.6  388.00  5062.9  387.61
  5079.2  387.81  5106.9  386.34  5112.7  384.61  5115.4  384.11  5118.7  384.61
  5142.1  385.20  5151.0  385.40  5189.5  388.13  5211.5  388.94  5233.6  390.77
  5262.5  395.02  5299.7  398.99  5316.1  399.99  5321.7  400.75  5360.2  402.75
#Mann=5,-1,0
  4684.8    0.05       0  4935.9    0.16       0  5112.7    0.07       0
  5118.7    0.16       0  5142.1    0.05       0
Bank Sta=5112.7,5118.7
Exp/Cntr=0.3,0.1

Type RM Length L Ch R = 1,2656,545,545,545
BEGIN DESCRIPTION:
UNT01878 IN SAND CR 6.0
END DESCRIPTION:
XS GIS Cut Line= 3
      3552861.50     10521687.13      3552472.62     10521423.25
      3552296.34     10521399.05
#Sta/Elev= 30
  4625.0  396.74  4696.4  392.10  4750.9  388.16  4793.5  384.10  4829.7  382.08
  4852.6  382.43  4879.7  382.10  4930.5  382.33  4960.4  382.59  4974.7  383.20
  4987.5  382.31  4993.4  380.87  4996.1  380.37  4999.4  380.87  5002.4  380.91
  5011.0  382.53  5017.4  382.97  5023.4  382.82  5038.3  384.45  5053.3  387.21
  5059.3  387.28  5083.2  389.45  5089.2  389.50  5092.3  390.43  5097.7  390.43
  5135.9  393.84  5156.0  396.14  5176.2  396.80  5214.3  399.79  5272.9  401.66
#Mann=4,-1,0
  4625.0    0.05       0  4696.4    0.16       0  4993.4    0.07       0
  4999.4    0.16       0
Bank Sta=4993.4,4999.4
Exp/Cntr=0.3,0.1

Type RM Length L Ch R = 1,2111,636,636,636
BEGIN DESCRIPTION:
UNT01878 IN SAND CR 4.0
END DESCRIPTION:
XS GIS Cut Line= 3
      3553062.45     10520994.07      3552621.88     10521009.27
      3552261.66     10521241.45
#Sta/Elev= 30
  4670.3  397.25  4710.7  396.46  4764.8  393.59  4810.7  390.65  4830.7  388.78
  4863.9  387.38  4910.8  384.68  4950.8  380.80  4970.8  379.72  4980.8  380.08
  4990.8  379.04  4997.8  378.91  5000.6  378.41  5003.8  378.91  5010.9  380.81
  5058.3  380.42  5184.2  379.63  5269.9  380.50  5287.1  381.22  5293.1  382.16
  5301.2  381.72  5308.3  382.55  5323.4  383.08  5336.9  384.37  5408.3  388.41
  5417.2  389.71  5453.5  391.40  5495.7  394.55  5516.8  395.63  5539.7  395.97
#Mann=7,-1,0
  4670.3    0.05       0  4764.8     0.1       0  4863.9    0.16       0
  4997.8    0.07       0  5003.8    0.16       0  5058.3     0.1       0
  5269.9    0.16       0
Bank Sta=4997.8,5003.8
Exp/Cntr=0.3,0.1

Type RM Length L Ch R = 1,1475,37,37,37
BEGIN DESCRIPTION:
UNT01878 IN SAND CR 3.3
END DESCRIPTION:
XS GIS Cut Line= 4
      3552682.22     10520686.66      3552376.24     10520624.16
      3552315.04     10520622.86      3551979.02     10520737.03
#Sta/Elev= 30
  4670.9  390.77  4711.8  388.07  4752.7  384.45  4769.5  382.27  4774.6  382.06
  4783.3  380.47  4793.5  379.39  4820.0  378.39  4847.5  378.51  4866.5  378.85
  4905.8  378.21  4987.8  378.03  4997.3  377.45  5024.3  377.13  5027.1  376.63
  5030.3  377.13  5037.3  377.70  5059.8  377.54  5085.9  378.29  5091.1  378.06
  5110.9  379.57  5117.2  380.60  5122.5  380.19  5148.6  382.58  5182.0  384.26
  5211.4  384.86  5277.8  388.17  5336.9  392.50  5388.1  395.29  5399.3  396.11
#Mann=8,-1,0
  4670.9     0.1       0  4847.5    0.16       0  4866.5     0.1       0
  5024.3    0.07       0  5030.3     0.1       0  5182.0    0.05       0
  5277.8     0.1       0  5388.1    0.16       0
Bank Sta=5024.3,5030.3
Exp/Cntr=0.3,0.1

Type RM Length L Ch R = 1,1438,53,53,53
BEGIN DESCRIPTION:
UNT01878 IN SAND CR 3.0
END DESCRIPTION:
XS GIS Cut Line= 6
      3552687.71     10520675.86      3552513.22     10520647.21
      3552356.97     10520592.52      3552307.23     10520595.52
      3552281.19     10520582.50      3551956.37     10520705.93
#Sta/Elev= 30
  4641.5  390.81  4667.5  389.65  4728.3  384.72  4738.4  383.59  4756.9  380.47
  4761.9  380.41  4768.8  379.39  4809.3  378.38  4838.5  378.66  4844.5  378.65
  4941.2  377.41  4972.3  377.61  4995.8  376.82  4998.5  376.32  5001.8  376.82
  5018.8  378.17  5049.5  378.29  5070.8  379.73  5106.3  380.52  5136.7  382.09
  5179.5  383.13  5216.1  384.82  5307.9  390.02  5325.9  390.47  5350.7  393.35
  5356.0  392.70  5373.0  394.81  5380.8  395.72  5386.1  394.66  5410.3  396.45
#Mann=7,-1,0
  4641.5     0.1       0  4838.5    0.16       0  4844.5     0.1       0
  4995.8    0.07       0  5001.8     0.1       0  5049.5    0.05       0
  5373.0     0.1       0
Bank Sta=4995.8,5001.8
Exp/Cntr=0.3,0.1

Type RM Length L Ch R = 1,1385,14,14,14
BEGIN DESCRIPTION:
UNT01878 IN SAND CR 3.1
END DESCRIPTION:
XS GIS Cut Line= 5
      3552704.32     10520602.03      3552523.37     10520608.54
      3552324.15     10520548.64      3552261.65     10520548.64
      3551950.43     10520684.07
#Sta/Elev= 30
  4601.3  391.36  4663.6  387.06  4729.1  380.21  4734.1  381.75  4800.6  380.04
  4855.0  380.19  4860.2  379.23  4888.0  380.01  4893.2  378.60  4926.3  379.98
  4931.5  378.33  4959.3  379.92  4985.8  377.39  4988.6  376.89  4991.8  377.39
  5012.4  379.76  5085.1  383.24  5152.1  383.23  5251.3  387.35  5298.1  388.00
  5314.1  389.42  5321.6  391.24  5327.0  394.48  5335.9  395.64  5345.0  394.01
  5346.6  394.84  5350.5  396.87  5368.4  394.94  5373.9  397.34  5392.3  395.84
#Mann=5,-1,0
  4601.3     0.1       0  4800.6    0.05       0  4985.8   0.035       0
  4991.8    0.05       0  5346.6     0.1       0
Bank Sta=4985.8,4991.8
Exp/Cntr=0.3,0.1

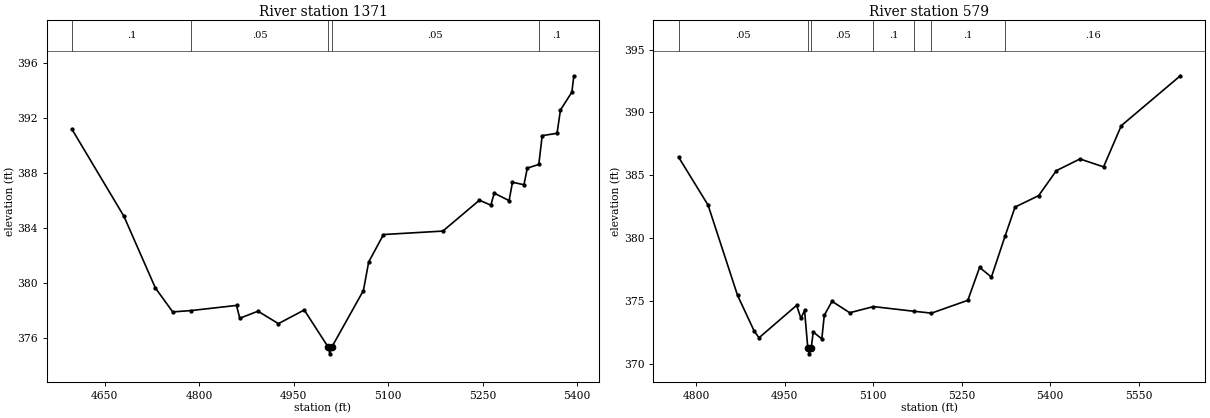
Type RM Length L Ch R = 1,1371,792,792,792
BEGIN DESCRIPTION:
UNT01878 IN SAND CR 3.2
END DESCRIPTION:
XS GIS Cut Line= 5
      3552704.39     10520578.59      3552520.77     10520587.71
      3552334.57     10520535.62      3552251.24     10520534.32
      3551941.89     10520666.90
#Sta/Elev= 30
  4597.9  391.15  4680.3  384.85  4730.3  379.65  4757.8  377.92  4787.4  378.02
  4859.1  378.39  4864.3  377.46  4893.2  377.97  4925.7  377.07  4966.7  378.06
  5004.6  375.38  5007.3  374.88  5010.6  375.38  5060.7  379.47  5069.1  381.54
  5092.6  383.53  5186.9  383.78  5245.0  386.02  5263.1  385.66  5268.5  386.53
  5292.1  385.99  5297.5  387.32  5315.7  387.14  5321.1  388.35  5339.3  388.61
  5344.7  390.70  5368.3  390.87  5373.7  392.56  5391.8  393.85  5395.0  395.04
#Mann=5,-1,0
  4597.9     0.1       0  4787.4    0.05       0  5004.6   0.035       0
  5010.6    0.05       0  5339.3     0.1       0
Bank Sta=5004.6,5010.6
Exp/Cntr=0.3,0.1

Type RM Length L Ch R = 1,579,0,0,0
BEGIN DESCRIPTION:
UNT01878 IN SAND CR 1.0
END DESCRIPTION:
XS GIS Cut Line= 3
      3552692.09     10520191.63      3552492.11     10520041.64
      3551892.09     10520041.64
#Sta/Elev= 30
  4770.3  386.44  4820.3  382.62  4870.3  375.43  4898.4  372.60  4906.7  372.06
  4970.3  374.64  4977.6  373.61  4983.8  374.23  4989.2  371.28  4991.9  370.78
  4995.2  371.28  4998.4  372.52  5013.0  371.97  5017.2  373.85  5030.3  374.96
  5060.3  374.05  5100.5  374.54  5168.6  374.17  5198.8  374.02  5260.3  375.04
  5280.3  377.66  5300.3  376.89  5323.5  380.16  5340.3  382.46  5380.3  383.37
  5410.3  385.36  5450.3  386.29  5490.3  385.66  5520.3  388.94  5620.3  392.91
#Mann=7,-1,0
  4770.3    0.05       0  4989.2   0.035       0  4995.2    0.05       0
  5100.5     0.1       0  5168.6    0.05       0  5198.8     0.1       0
  5323.5    0.16       0
Bank Sta=4989.2,4995.2
Exp/Cntr=0.3,0.1

Chan Stop Cuts=-1