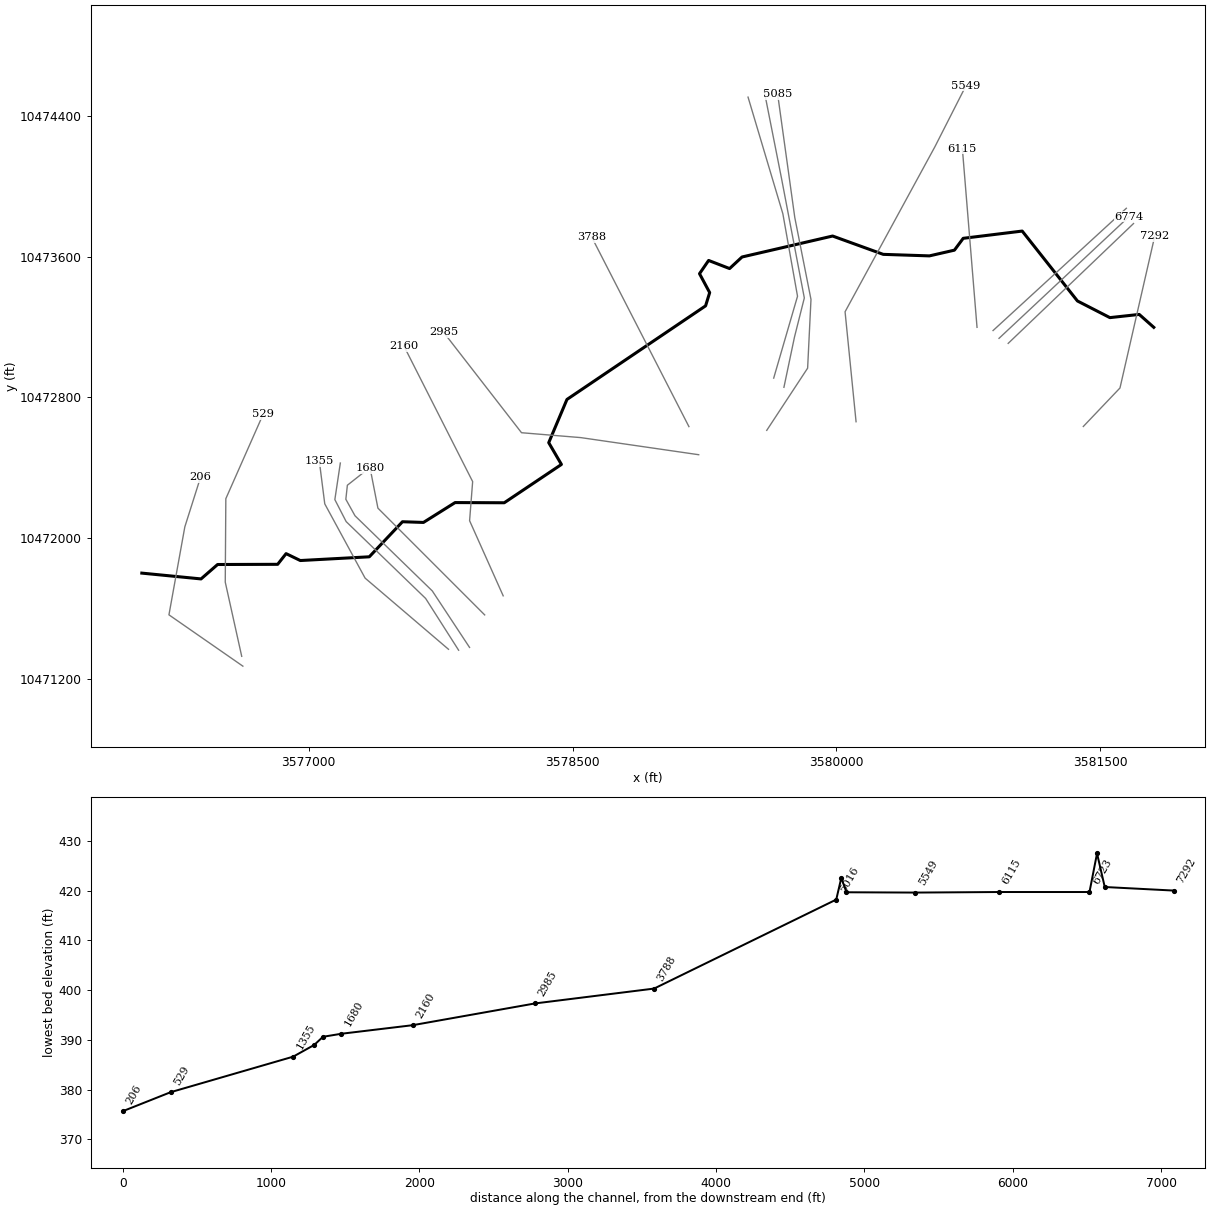
--- UNT0189 IN SAND CR.prj (project) ---

Proj Title=UNT0189 IN SAND CR Base Level Engineering
Current Plan=p01
Default Exp/Contr=0.3,0.1
English Units
Geom File=g01
Flow File=f01
Plan File=p01
BEGIN DESCRIPTION:
UNT0189 IN SAND CR
END DESCRIPTION:

--- UNT0189 IN SAND CR.p01 (plan) ---

Plan Title=Multiple Run
Short Identifier=Multiple
Geom File=g01
Flow File=f01
Subcritical Flow
K Sum by GR= 0
Std Step Tol= 0.01
Critical Tol= 0.01
Num of Std Step Trials= 20
Max Error Tol= 0.3
Flow Tol Ratio= 0.001
Split Flow NTrial= 30
Split Flow Tol= 0.02
Split Flow Ratio= 0.02
Log Output Level= 0
Friction Slope Method= 1
Unsteady Friction Slope Method= 2
Unsteady Bridges Friction Slope Method= 1
Parabolic Critical Depth
Global Vel Dist=  1 , 1 , 1
Global Log Level= 0
CheckData=True
Encroach Param= -1, 0, 0, 0
BEGIN DESCRIPTION:
Multiple Run
END DESCRIPTION:

--- UNT0189 IN SAND CR.f01 (steady flow) ---

Flow Title=Multiple
Number of Profiles=7
Profile Names=10-year,25-year,50-year,1pct_min,100-year,1pct_plu,500-year
River Rch & RM= UNT0189 IN SAND ,Reach-1,7292
     966    1332    1634    1464    1980    2677    2897
River Rch & RM= UNT0189 IN SAND ,Reach-1,6115
    1568    2214    2761    2507    3391    4586    5106
Boundary for River Rch & Prof#=UNT0189 IN SAND ,Reach-1,1
Up Type=0
Dn Type=3
Dn Slope=0.005
Boundary for River Rch & Prof#=UNT0189 IN SAND ,Reach-1,2
Up Type=0
Dn Type=3
Dn Slope=0.005
Boundary for River Rch & Prof#=UNT0189 IN SAND ,Reach-1,3
Up Type=0
Dn Type=3
Dn Slope=0.005
Boundary for River Rch & Prof#=UNT0189 IN SAND ,Reach-1,4
Up Type=0
Dn Type=3
Dn Slope=0.005
Boundary for River Rch & Prof#=UNT0189 IN SAND ,Reach-1,5
Up Type=0
Dn Type=3
Dn Slope=0.005
Boundary for River Rch & Prof#=UNT0189 IN SAND ,Reach-1,6
Up Type=0
Dn Type=3
Dn Slope=0.005
Boundary for River Rch & Prof#=UNT0189 IN SAND ,Reach-1,7
Up Type=0
Dn Type=3
Dn Slope=0.005

--- UNT0189 IN SAND CR.g01 (geometry) ---

Geom Title=Existing Conditions

River Reach=UNT0189 IN SAND ,Reach-1
Reach XY= 30
      3581803.59     10473198.46      3581720.77     10473271.90
      3581554.11     10473253.67      3581369.69     10473348.33
      3581055.73     10473745.64      3580720.44     10473704.41
      3580670.53     10473637.13      3580528.38     10473604.58
      3580265.80     10473613.26      3579978.25     10473717.43
      3579463.43     10473598.28      3579392.64     10473532.55
      3579273.47     10473578.65      3579221.75     10473503.36
      3579279.50     10473395.89      3579256.25     10473320.57
      3578468.34     10472788.63      3578364.76     10472543.00
      3578437.01     10472419.22      3578112.08     10472201.49
      3577832.53     10472202.51      3577652.84     10472089.67
      3577533.51     10472093.62      3577344.97     10471894.32
      3576952.95     10471873.14      3576872.05     10471912.37
      3576824.13     10471851.61      3576482.81     10471850.57
      3576388.72     10471768.62      3576052.11     10471801.64

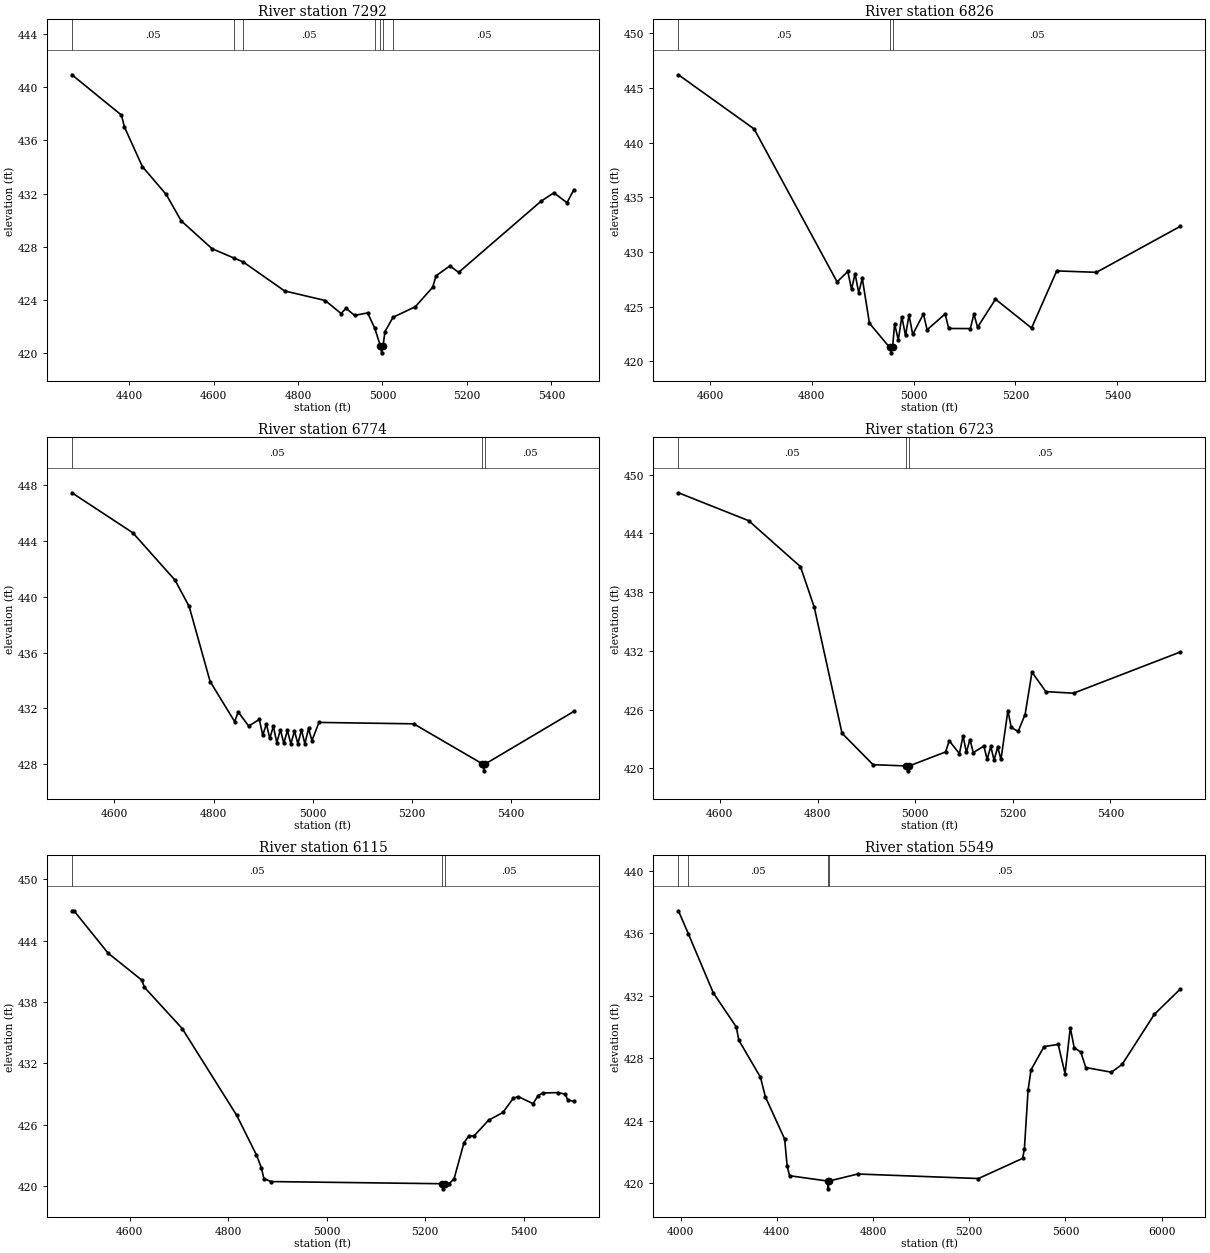
Type RM Length L Ch R = 1,7292,466,466,466
BEGIN DESCRIPTION:
UNT0189 IN SAND CR 11.8
END DESCRIPTION:
XS GIS Cut Line= 3
      3581403.12     10472635.11      3581611.45     10472853.85
      3581809.16     10473717.54
#Sta/Elev= 30
  4264.9  440.92  4382.1  437.89  4389.0  437.01  4431.5  434.03  4488.1  431.93
  4523.3  429.96  4596.5  427.86  4647.6  427.17  4670.5  426.86  4768.2  424.69
  4864.3  423.97  4902.1  422.99  4913.5  423.39  4934.0  422.85  4964.8  423.04
  4981.8  421.88  4995.2  420.54  4997.9  420.04  5001.2  420.54  5005.8  421.63
  5024.9  422.71  5077.6  423.50  5118.7  424.96  5126.9  425.83  5159.7  426.57
  5180.2  426.08  5375.1  431.42  5405.9  432.06  5436.7  431.31  5453.0  432.29
#Mann=7,-1,0
  4264.9    0.05       0  4647.6    0.16       0  4670.5    0.05       0
  4981.8    0.07       0  4995.2    0.07       0  5001.2    0.07       0
  5024.9    0.05       0
Bank Sta=4995.2,5001.2
Exp/Cntr=0.3,0.1

Type RM Length L Ch R = 1,6826,52,52,52
BEGIN DESCRIPTION:
UNT0189 IN SAND CR 11.7
END DESCRIPTION:
XS GIS Cut Line= 2
      3580976.09     10473107.31      3581688.37     10473788.40
#Sta/Elev= 30
  4538.2  446.21  4686.9  441.25  4849.8  427.25  4870.8  428.21  4878.1  426.57
  4885.0  428.01  4892.2  426.26  4899.2  427.59  4913.3  423.47  4952.8  421.26
  4955.5  420.76  4958.8  421.26  4962.7  423.44  4969.9  421.92  4976.8  424.07
  4984.1  422.35  4991.0  424.23  4998.2  422.44  5019.3  424.32  5026.5  422.87
  5061.8  424.32  5069.0  422.99  5111.4  422.98  5118.4  424.31  5125.6  423.10
  5160.8  425.67  5231.6  423.03  5281.0  428.26  5359.0  428.13  5523.7  432.34
#Mann=3,-1,0
  4538.2    0.05       0  4952.8    0.03       0  4958.8    0.05       0
Bank Sta=4952.8,4958.8
Exp/Cntr=0.3,0.1

Type RM Length L Ch R = 1,6774,51,51,51
BEGIN DESCRIPTION:
UNT0189 IN SAND CR 11.5
END DESCRIPTION:
XS GIS Cut Line= 2
      3580923.98     10473135.93      3581662.52     10473827.66
#Sta/Elev= 30
  4514.6  447.45  4637.4  444.58  4722.4  441.19  4750.8  439.31  4793.2  433.92
  4842.6  431.05  4849.9  431.74  4870.9  430.73  4892.4  431.20  4899.3  430.07
  4906.6  430.88  4913.4  429.85  4920.7  430.71  4927.6  429.54  4934.9  430.47
  4941.7  429.49  4949.1  430.42  4955.9  429.45  4963.2  430.38  4970.1  429.46
  4977.4  430.45  4984.2  429.45  4991.6  430.56  4998.4  429.68  5012.6  430.99
  5203.6  430.89  5342.2  428.02  5345.0  427.52  5348.2  428.02  5526.5  431.78
#Mann=3,-1,0
  4514.6    0.05       0  5342.2    0.03       0  5348.2    0.05       0
Bank Sta=5342.2,5348.2
Exp/Cntr=0.3,0.1

Type RM Length L Ch R = 1,6723,608,608,608
BEGIN DESCRIPTION:
UNT0189 IN SAND CR 11.6
END DESCRIPTION:
XS GIS Cut Line= 2
      3580890.12     10473180.20      3581647.52     10473875.13
#Sta/Elev= 30
  4515.1  448.15  4659.0  445.30  4765.1  440.60  4793.4  436.44  4850.2  423.59
  4913.7  420.38  4981.6  420.25  4984.3  419.75  4987.6  420.25  5062.3  421.68
  5069.7  422.82  5090.6  421.51  5098.0  423.32  5104.8  421.64  5112.2  422.95
  5119.0  421.61  5140.6  422.28  5147.4  420.94  5154.8  422.24  5161.6  420.84
  5168.9  422.17  5175.7  420.92  5189.9  425.91  5196.7  424.18  5210.9  423.78
  5225.1  425.50  5239.2  429.83  5267.6  427.84  5324.3  427.68  5543.0  431.89
#Mann=3,-1,0
  4515.1    0.05       0  4981.6   0.033       0  4987.6    0.05       0
Bank Sta=4981.6,4987.6
Exp/Cntr=0.3,0.1

Type RM Length L Ch R = 1,6115,566,566,566
BEGIN DESCRIPTION:
UNT0189 IN SAND CR 11.4
END DESCRIPTION:
XS GIS Cut Line= 2
      3580798.98     10473198.45      3580715.65     10474214.03
#Sta/Elev= 30
  4482.9  446.92  4487.0  446.92  4556.3  442.78  4624.9  440.14  4629.9  439.45
  4706.8  435.41  4817.2  426.95  4857.3  423.08  4867.4  421.82  4872.6  420.74
  4887.4  420.46  5233.6  420.25  5236.3  419.75  5239.6  420.25  5248.7  420.26
  5258.7  420.73  5278.8  424.25  5288.8  424.93  5298.8  424.90  5328.9  426.46
  5357.9  427.21  5379.1  428.62  5389.1  428.76  5419.2  428.07  5429.3  428.87
  5439.3  429.12  5469.4  429.15  5484.3  429.01  5489.5  428.44  5501.9  428.29
#Mann=3,-1,0
  4482.9    0.05       0  5233.6   0.033       0  5239.6    0.05       0
Bank Sta=5233.6,5239.6
Exp/Cntr=0.3,0.1

Type RM Length L Ch R = 1,5549,464,464,464
BEGIN DESCRIPTION:
UNT0189 IN SAND CR 11.3
END DESCRIPTION:
XS GIS Cut Line= 4
      3580111.49     10472661.93      3580048.99     10473286.98
      3580559.40     10474224.48      3580736.47     10474572.64
#Sta/Elev= 30
  3991.1  437.45  4032.8  435.96  4136.1  432.19  4231.6  430.01  4242.1  429.16
  4332.1  426.79  4352.6  425.53  4432.6  422.83  4443.1  421.10  4453.1  420.48
  4610.9  420.14  4613.6  419.64  4616.9  420.14  4736.8  420.59  5238.2  420.30
  5421.6  421.59  5429.1  422.17  5444.4  425.94  5456.7  427.26  5510.8  428.75
  5569.6  428.89  5598.2  427.02  5620.0  429.96  5636.2  428.68  5663.7  428.40
  5684.3  427.41  5791.0  427.11  5835.5  427.61  5969.0  430.81  6077.3  432.44
#Mann=4,-1,0
  3991.1     0.1       0  4032.8    0.05       0  4610.9   0.033       0
  4616.9    0.05       0
Bank Sta=4610.9,4616.9
Exp/Cntr=0.3,0.1

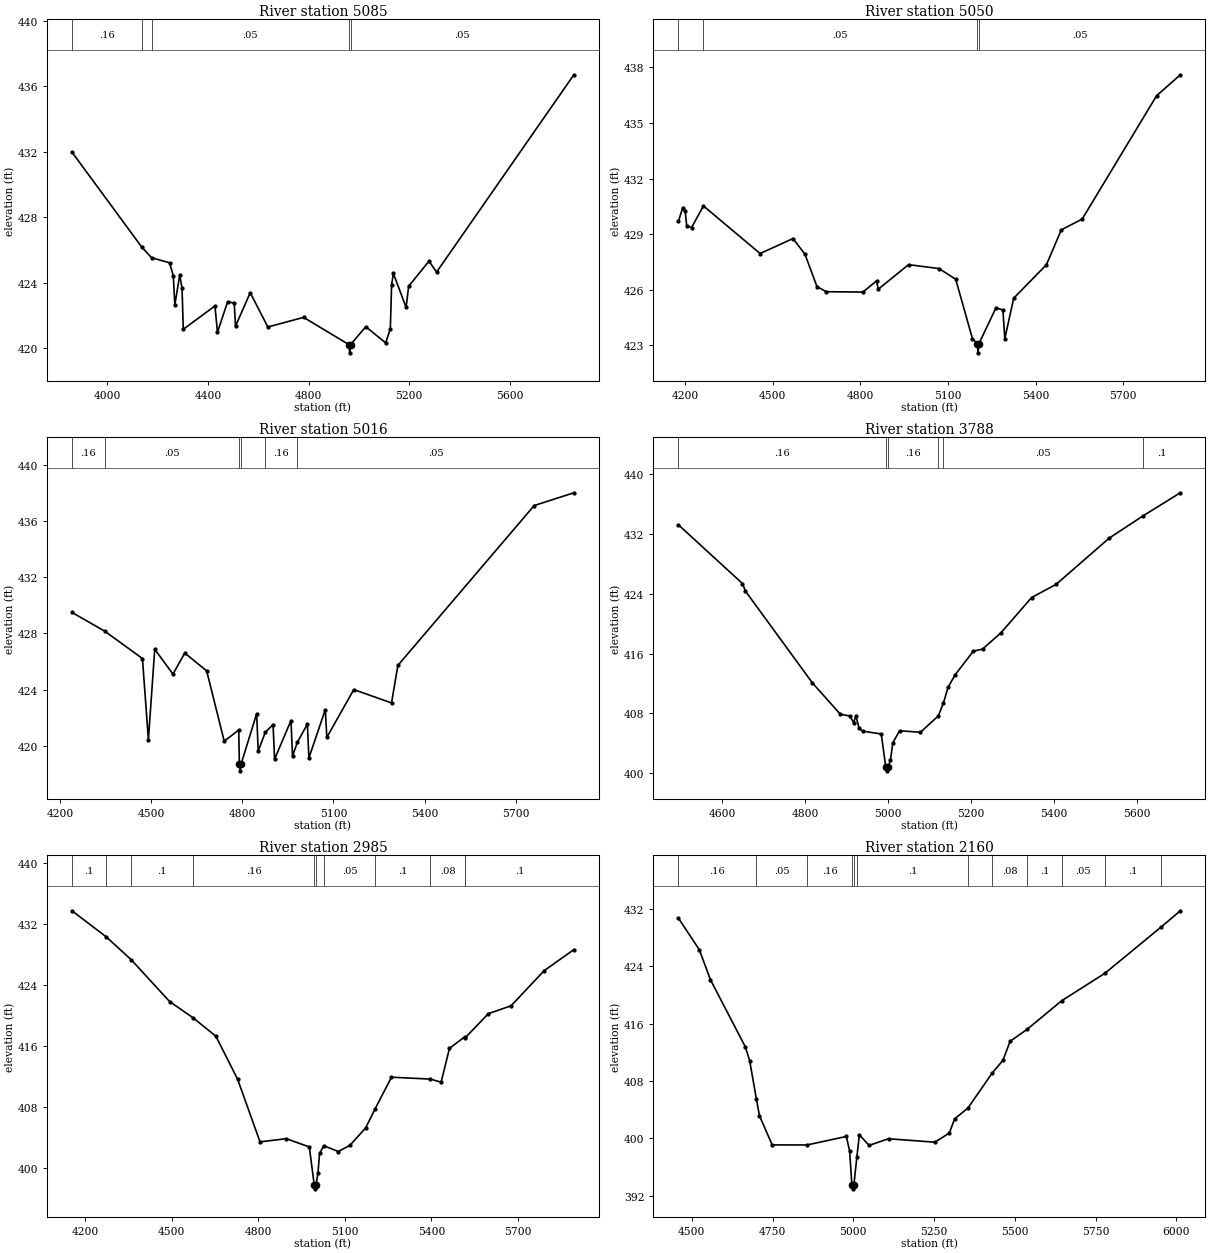
Type RM Length L Ch R = 1,5085,35,35,35
BEGIN DESCRIPTION:
UNT0189 IN SAND CR 11.2
END DESCRIPTION:
XS GIS Cut Line= 5
      3579603.88     10472613.00      3579836.18     10472966.43
      3579855.28     10473357.05      3579763.27     10473822.33
      3579666.04     10474521.99
#Sta/Elev= 30
  3859.7  431.98  4137.1  426.17  4176.1  425.52  4247.4  425.21  4262.5  424.42
  4268.5  422.62  4287.9  424.45  4297.2  423.68  4302.2  421.14  4428.0  422.57
  4438.0  420.96  4478.1  422.81  4504.7  422.75  4509.7  421.33  4568.2  423.38
  4638.3  421.28  4780.3  421.87  4960.8  420.20  4963.6  419.70  4966.8  420.20
  5027.6  421.30  5106.5  420.31  5125.0  421.17  5130.1  423.85  5137.1  424.56
  5187.7  422.48  5197.8  423.77  5278.6  425.31  5308.9  424.64  5854.4  436.71
#Mann=5,-1,0
  3859.7    0.16       0  4137.1     0.1       0  4176.1    0.05       0
  4960.8   0.033       0  4966.8    0.05       0
Bank Sta=4960.8,4966.8
Exp/Cntr=0.3,0.1

Type RM Length L Ch R = 1,5050,34,34,34
BEGIN DESCRIPTION:
UNT0189 IN SAND CR 11.1
END DESCRIPTION:
XS GIS Cut Line= 5
      3579701.54     10472857.68      3579761.44     10473142.86
      3579817.43     10473365.52      3579687.22     10474047.81
      3579589.56     10474541.34
#Sta/Elev= 30
  4177.1  429.69  4191.4  430.40  4200.3  430.25  4205.4  429.46  4222.0  429.35
  4262.8  430.52  4457.0  427.95  4569.5  428.76  4610.6  427.91  4651.7  426.16
  4683.8  425.89  4808.9  425.87  4855.9  426.48  4861.0  426.02  4965.2  427.35
  5069.5  427.14  5126.7  426.56  5183.9  423.36  5200.2  423.09  5202.9  422.59
  5206.2  423.09  5264.3  425.01  5288.2  424.91  5294.8  423.36  5325.3  425.54
  5437.4  427.35  5488.3  429.23  5559.7  429.81  5814.6  436.47  5895.8  437.60
#Mann=4,-1,0
  4177.1     0.1       0  4262.8    0.05       0  5200.2   0.033       0
  5206.2    0.05       0
Bank Sta=5200.2,5206.2
Exp/Cntr=0.3,0.1

Type RM Length L Ch R = 1,5016,1228,1228,1228
BEGIN DESCRIPTION:
UNT0189 IN SAND CR 11.0
END DESCRIPTION:
XS GIS Cut Line= 4
      3579643.37     10472909.93      3579778.78     10473375.19
      3579695.45     10473843.94      3579497.60     10474506.89
#Sta/Elev= 30
  4239.0  429.50  4346.6  428.17  4471.1  426.22  4490.7  420.45  4511.6  426.88
  4571.6  425.11  4610.4  426.61  4682.6  425.34  4740.3  420.34  4788.1  421.13
  4790.2  418.73  4792.9  418.23  4796.2  418.73  4847.2  422.30  4852.2  419.64
  4875.6  420.97  4901.1  421.52  4906.2  419.06  4960.2  421.81  4965.2  419.28
  4981.4  420.27  5014.1  421.55  5019.2  419.15  5073.1  422.58  5078.2  420.61
  5166.9  424.01  5291.2  423.06  5312.1  425.73  5760.8  437.10  5891.5  438.01
#Mann=6,-1,0
  4239.0    0.16       0  4346.6    0.05       0  4790.2   0.035       0
  4796.2    0.05       0  4875.6    0.16       0  4981.4    0.05       0
Bank Sta=4790.2,4796.2
Exp/Cntr=0.3,0.1

Type RM Length L Ch R = 1,3788,803,803,803
BEGIN DESCRIPTION:
UNT0189 IN SAND CR 8.0
END DESCRIPTION:
XS GIS Cut Line= 2
      3579161.54     10472634.27      3578609.47     10473710.64
#Sta/Elev= 30
  4495.1  433.26  4649.5  425.40  4656.7  424.38  4818.1  412.09  4885.5  407.89
  4908.0  407.67  4917.4  406.79  4923.0  407.67  4930.5  406.02  4939.6  405.63
  4984.0  405.26  4994.9  400.82  4997.6  400.32  5000.9  400.82  5006.2  401.78
  5011.8  404.07  5028.3  405.69  5078.4  405.48  5121.6  407.68  5133.8  409.40
  5144.9  411.48  5161.5  413.14  5205.9  416.34  5228.1  416.62  5272.5  418.80
  5346.3  423.52  5405.7  425.30  5533.2  431.47  5614.2  434.43  5704.8  437.55
#Mann=6,-1,0
  4495.1    0.16       0  4994.9    0.07       0  5000.9    0.16       0
  5121.6     0.1       0  5133.8    0.05       0  5614.2     0.1       0
Bank Sta=4994.9,5000.9
Exp/Cntr=0.3,0.1

Type RM Length L Ch R = 1,2985,825,825,825
BEGIN DESCRIPTION:
UNT0189 IN SAND CR 6.0
END DESCRIPTION:
XS GIS Cut Line= 4
      3579217.10     10472474.54      3578546.96     10472571.76
      3578210.16     10472599.54      3577766.38     10473171.59
#Sta/Elev= 30
  4154.2  433.69  4271.7  430.32  4359.3  427.30  4492.7  421.82  4573.0  419.72
  4652.9  417.29  4728.1  411.67  4805.9  403.47  4896.4  403.89  4976.7  402.81
  4993.8  397.83  4996.5  397.33  4999.8  397.83  5006.8  399.42  5012.1  401.96
  5026.7  402.97  5077.0  402.21  5117.2  403.02  5171.8  405.29  5204.9  407.81
  5261.4  411.93  5396.0  411.68  5433.4  411.28  5462.3  415.70  5514.6  417.19
  5517.5  417.11  5597.2  420.24  5676.0  421.27  5790.0  425.85  5893.3  428.61
#Mann=11,-1,0
  4154.2     0.1       0  4271.7    0.16       0  4359.3     0.1       0
  4573.0    0.16       0  4993.8    0.07       0  4999.8    0.16       0
  5026.7    0.05       0  5204.9     0.1       0  5396.0    0.08       0
  5514.6    0.05       0  5517.5     0.1       0
Bank Sta=4993.8,4999.8
Exp/Cntr=0.3,0.1

Type RM Length L Ch R = 1,2160,480,480,480
BEGIN DESCRIPTION:
UNT0189 IN SAND CR 4.0
END DESCRIPTION:
XS GIS Cut Line= 4
      3578105.97     10471672.50      3577915.02     10472099.54
      3577932.38     10472321.76      3577542.12     10473091.61
#Sta/Elev= 30
  4458.7  430.72  4523.5  426.31  4557.9  422.12  4665.9  412.76  4679.4  410.81
  4700.2  405.45  4709.7  403.15  4749.0  399.08  4856.7  399.07  4978.7  400.26
  4988.8  398.18  4995.8  393.45  4998.6  392.95  5001.8  393.45  5011.2  397.42
  5018.9  400.48  5049.0  399.01  5109.1  399.94  5252.6  399.46  5297.2  400.73
  5313.8  402.71  5355.1  404.23  5429.8  409.09  5463.2  410.87  5485.6  413.54
  5537.7  415.19  5645.6  419.21  5778.8  423.02  5953.0  429.48  6012.5  431.75
#Mann=12,-1,0
  4458.7    0.16       0  4700.2    0.05       0  4856.7    0.16       0
  4995.8    0.07       0  5001.8    0.16       0  5011.2     0.1       0
  5355.1    0.05       0  5429.8    0.08       0  5537.7     0.1       0
  5645.6    0.05       0  5778.8     0.1       0  5953.0    0.05       0
Bank Sta=4995.8,5001.8
Exp/Cntr=0.3,0.1

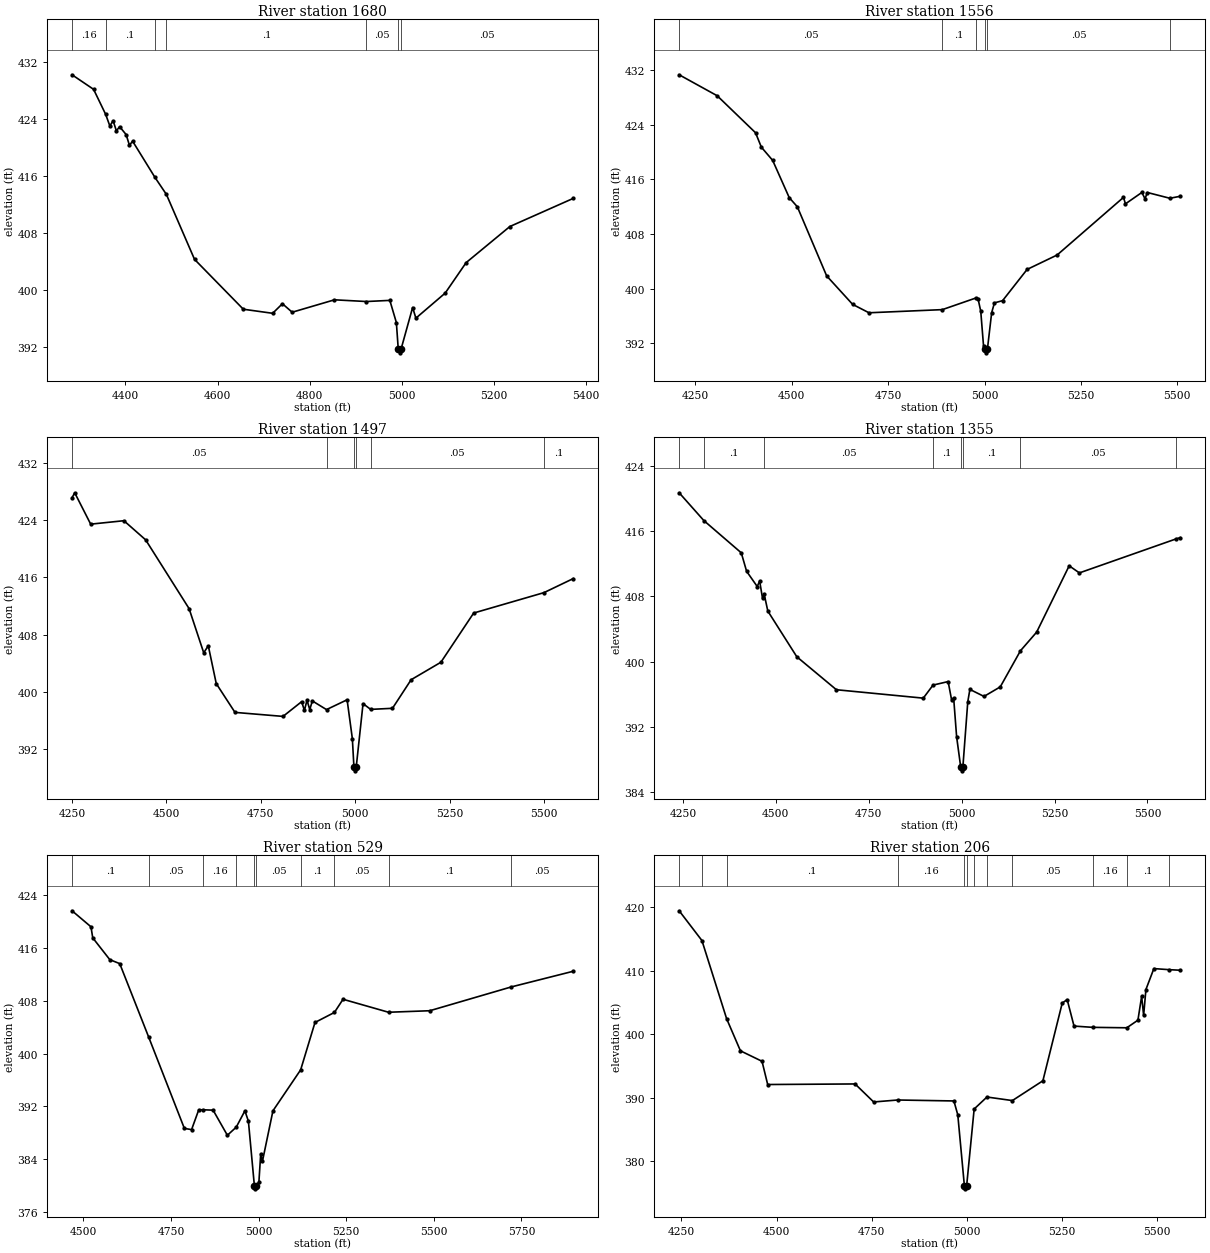
Type RM Length L Ch R = 1,1680,124,124,124
BEGIN DESCRIPTION:
UNT0189 IN SAND CR 3.3
END DESCRIPTION:
XS GIS Cut Line= 3
      3578000.73     10471564.12      3577393.99     10472170.86
      3577349.80     10472397.03
#Sta/Elev= 30
  4284.0  430.19  4330.8  428.15  4357.0  424.65  4366.1  423.02  4373.2  423.76
  4380.3  422.33  4387.3  422.92  4401.5  421.81  4408.6  420.32  4415.6  420.88
  4464.0  415.82  4488.9  413.43  4550.0  404.33  4656.0  397.34  4719.7  396.77
  4740.9  398.11  4762.1  396.92  4854.0  398.66  4923.4  398.42  4974.2  398.58
  4988.4  395.47  4992.5  391.73  4995.2  391.23  4998.5  391.73  5023.7  397.58
  5030.8  396.09  5094.4  399.60  5139.9  403.87  5234.9  408.93  5372.5  412.87
#Mann=7,-1,0
  4284.0    0.16       0  4357.0     0.1       0  4464.0    0.16       0
  4488.9     0.1       0  4923.4    0.05       0  4992.5   0.035       0
  4998.5    0.05       0
Bank Sta=4992.5,4998.5
Exp/Cntr=0.3,0.1

Type RM Length L Ch R = 1,1556,59,59,59
BEGIN DESCRIPTION:
UNT0189 IN SAND CR 3.1
END DESCRIPTION:
XS GIS Cut Line= 6
      3577914.80     10471379.22      3577703.02     10471700.37
      3577263.78     10472127.46      3577211.70     10472221.21
      3577220.38     10472301.07      3577310.68     10472372.26
#Sta/Elev= 30
  4208.0  431.29  4306.7  428.22  4406.1  422.81  4421.2  420.70  4450.5  418.77
  4493.4  413.33  4514.5  411.98  4590.5  401.88  4657.9  397.71  4700.3  396.48
  4890.6  396.94  4977.0  398.63  4983.3  398.49  4990.2  396.71  4997.4  391.64
  5001.4  391.12  5004.1  390.62  5007.4  391.12  5018.5  396.49  5025.7  397.93
  5046.8  398.25  5110.4  402.82  5188.3  404.93  5360.4  413.36  5365.5  412.41
  5408.1  414.08  5416.1  413.16  5422.5  414.07  5480.6  413.23  5507.9  413.52
#Mann=6,-1,0
  4208.0    0.05       0  4890.6     0.1       0  4977.0    0.05       0
  5001.4   0.035       0  5007.4    0.05       0  5480.6     0.1       0
Bank Sta=5001.4,5007.4
Exp/Cntr=0.3,0.1

Type RM Length L Ch R = 1,1497,142,142,142
BEGIN DESCRIPTION:
UNT0189 IN SAND CR 3.0
END DESCRIPTION:
XS GIS Cut Line= 5
      3577852.66     10471363.41      3577665.17     10471657.66
      3577213.44     10472094.47      3577149.20     10472219.47
      3577180.36     10472427.22
#Sta/Elev= 30
  4249.8  427.11  4256.9  427.80  4299.2  423.42  4387.2  423.90  4444.8  421.23
  4559.9  411.63  4598.7  405.46  4610.8  406.44  4631.9  401.16  4681.5  397.14
  4808.8  396.58  4858.2  398.64  4865.4  397.41  4872.4  398.84  4879.6  397.53
  4886.5  398.74  4924.0  397.53  4978.6  398.90  4992.5  393.47  4996.7  389.48
  4999.5  388.98  5002.7  389.48  5020.8  398.36  5041.0  397.56  5098.8  397.71
  5148.2  401.70  5227.1  404.14  5313.9  411.01  5500.2  413.86  5577.7  415.82
#Mann=6,-1,0
  4249.8    0.05       0  4924.0     0.1       0  4996.7    0.07       0
  5002.7     0.1       0  5041.0    0.05       0  5500.2     0.1       0
Bank Sta=4996.7,5002.7
Exp/Cntr=0.3,0.1

Type RM Length L Ch R = 1,1355,826,826,826
BEGIN DESCRIPTION:
UNT0189 IN SAND CR 3.2
END DESCRIPTION:
XS GIS Cut Line= 4
      3577795.00     10471368.80      3577321.08     10471773.29
      3577091.91     10472195.16      3577060.87     10472438.33
#Sta/Elev= 30
  4240.1  420.70  4306.6  417.29  4407.2  413.34  4421.5  411.08  4450.1  409.21
  4456.6  409.89  4464.3  407.78  4468.7  408.30  4478.6  406.20  4556.6  400.60
  4663.1  396.56  4896.8  395.53  4923.1  397.13  4963.7  397.56  4972.8  395.36
  4978.5  395.57  4986.5  390.80  4997.4  387.12  5000.1  386.62  5003.4  387.12
  5016.5  395.08  5022.2  396.60  5060.2  395.74  5103.9  396.91  5158.3  401.34
  5201.8  403.62  5289.3  411.75  5316.8  410.88  5577.1  415.05  5588.4  415.20
#Mann=8,-1,0
  4240.1    0.05       0  4306.6     0.1       0  4468.7    0.05       0
  4923.1     0.1       0  4997.4    0.07       0  5003.4     0.1       0
  5158.3    0.05       0  5577.1     0.1       0
Bank Sta=4997.4,5003.4
Exp/Cntr=0.3,0.1

Type RM Length L Ch R = 1,529,323,323,323
BEGIN DESCRIPTION:
UNT0189 IN SAND CR 1.0
END DESCRIPTION:
XS GIS Cut Line= 4
      3576619.87     10471328.73      3576526.38     10471750.24
      3576529.60     10472224.54      3576741.42     10472703.75
#Sta/Elev= 30
  4467.7  421.67  4521.7  419.24  4526.8  417.56  4575.5  414.25  4603.8  413.65
  4686.3  402.51  4788.2  388.64  4808.8  388.46  4829.2  391.46  4840.7  391.47
  4870.2  391.41  4910.9  387.60  4936.2  388.83  4960.9  391.31  4970.9  389.74
  4987.9  379.97  4990.6  379.47  4993.9  379.97  5000.9  380.53  5006.0  384.77
  5011.0  383.66  5040.9  391.31  5120.0  397.53  5160.9  404.72  5216.3  406.24
  5240.9  408.24  5370.7  406.27  5488.3  406.50  5720.7  410.11  5897.7  412.49
#Mann=10,-1,0
  4467.7     0.1       0  4686.3    0.05       0  4840.7    0.16       0
  4936.2    0.05       0  4987.9    0.03       0  4993.9    0.05       0
  5120.0     0.1       0  5216.3    0.05       0  5370.7     0.1       0
  5720.7    0.05       0
Bank Sta=4987.9,4993.9
Exp/Cntr=0.3,0.1

Type RM Length L Ch R = 1,206,0,0,0
BEGIN DESCRIPTION:
UNT0189 IN SAND CR 1.1
END DESCRIPTION:
XS GIS Cut Line= 4
      3576626.45     10471272.83      3576206.32     10471564.49
      3576296.60     10472064.49      3576386.48     10472347.96
#Sta/Elev= 30
  4244.1  419.46  4303.9  414.77  4368.8  402.45  4405.1  397.39  4461.8  395.74
  4476.7  392.08  4706.3  392.17  4755.1  389.33  4818.3  389.64  4966.0  389.49
  4976.2  387.30  4993.5  376.14  4996.3  375.64  4999.5  376.14  5019.2  388.22
  5052.8  390.11  5119.6  389.55  5199.8  392.67  5250.6  404.91  5263.6  405.47
  5281.6  401.29  5330.9  401.09  5420.3  401.02  5449.5  402.22  5459.3  405.99
  5464.5  402.97  5470.5  407.05  5491.4  410.35  5531.2  410.18  5561.0  410.09
#Mann=12,-1,0
  4244.1     0.1       0  4303.9    0.05       0  4368.8     0.1       0
  4818.3    0.16       0  4993.5    0.07       0  4999.5    0.16       0
  5019.2    0.05       0  5052.8    0.16       0  5119.6    0.05       0
  5330.9    0.16       0  5420.3     0.1       0  5531.2    0.16       0
Bank Sta=4993.5,4999.5
Exp/Cntr=0.3,0.1

Chan Stop Cuts=-1