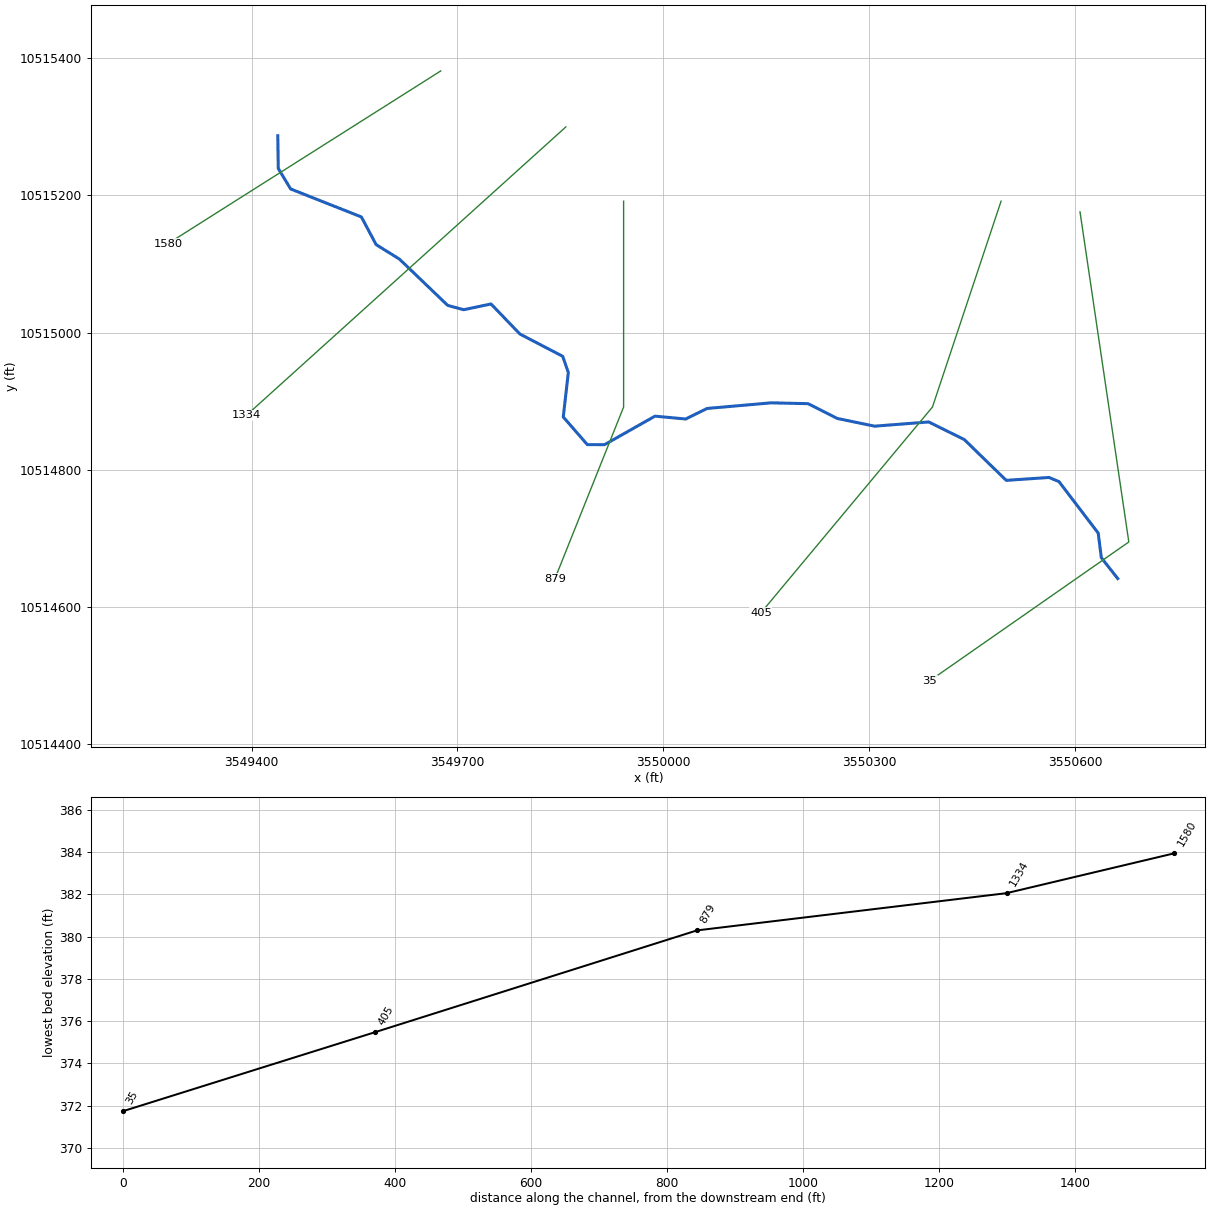
--- UNT01895 IN SAND CR.prj (project) ---

Proj Title=UNT01895 IN SAND CR Base Level Engineering
Current Plan=p01
Default Exp/Contr=0.3,0.1
English Units
Geom File=g01
Flow File=f01
Plan File=p01
BEGIN DESCRIPTION:
UNT01895 IN SAND CR
END DESCRIPTION:

--- UNT01895 IN SAND CR.p01 (plan) ---

Plan Title=Multiple Run
Short Identifier=Multiple
Geom File=g01
Flow File=f01
Subcritical Flow
K Sum by GR= 0
Std Step Tol= 0.01
Critical Tol= 0.01
Num of Std Step Trials= 20
Max Error Tol= 0.3
Flow Tol Ratio= 0.001
Split Flow NTrial= 30
Split Flow Tol= 0.02
Split Flow Ratio= 0.02
Log Output Level= 0
Friction Slope Method= 1
Unsteady Friction Slope Method= 2
Unsteady Bridges Friction Slope Method= 1
Parabolic Critical Depth
Global Vel Dist=  1 , 1 , 1
Global Log Level= 0
CheckData=True
Encroach Param= -1, 0, 0, 0
BEGIN DESCRIPTION:
Multiple Run
END DESCRIPTION:

--- UNT01895 IN SAND CR.f01 (steady flow) ---

Flow Title=Multiple
Number of Profiles=7
Profile Names=10-year,25-year,50-year,1pct_min,100-year,1pct_plu,500-year
River Rch & RM= UNT01895 IN SAND,Reach-1,1580
     441     575     680     589     796    1076    1086
Boundary for River Rch & Prof#=UNT01895 IN SAND,Reach-1,1
Up Type=0
Dn Type=3
Dn Slope=0.005
Boundary for River Rch & Prof#=UNT01895 IN SAND,Reach-1,2
Up Type=0
Dn Type=3
Dn Slope=0.005
Boundary for River Rch & Prof#=UNT01895 IN SAND,Reach-1,3
Up Type=0
Dn Type=3
Dn Slope=0.005
Boundary for River Rch & Prof#=UNT01895 IN SAND,Reach-1,4
Up Type=0
Dn Type=3
Dn Slope=0.005
Boundary for River Rch & Prof#=UNT01895 IN SAND,Reach-1,5
Up Type=0
Dn Type=3
Dn Slope=0.005
Boundary for River Rch & Prof#=UNT01895 IN SAND,Reach-1,6
Up Type=0
Dn Type=3
Dn Slope=0.005
Boundary for River Rch & Prof#=UNT01895 IN SAND,Reach-1,7
Up Type=0
Dn Type=3
Dn Slope=0.005

--- UNT01895 IN SAND CR.g01 (geometry) ---

Geom Title=Existing Conditions

River Reach=UNT01895 IN SAND,Reach-1
Reach XY= 30
      3549438.24     10515286.94      3549438.93     10515239.28
      3549456.98     10515209.40      3549560.06     10515168.62
      3549581.51     10515128.30      3549615.50     10515107.19
      3549685.85     10515039.70      3549709.08     10515033.44
      3549748.91     10515041.81      3549791.01     10514998.05
      3549853.40     10514965.51      3549861.54     10514941.90
      3549854.18     10514877.14      3549889.23     10514836.88
      3549914.28     10514836.77      3549987.83     10514878.34
      3550032.56     10514874.18      3550063.80     10514889.56
      3550157.21     10514897.75      3550210.98     10514896.51
      3550253.43     10514874.99      3550307.80     10514863.75
      3550386.74     10514869.88      3550438.55     10514844.17
      3550499.62     10514784.78      3550561.93     10514788.99
      3550576.49     10514782.93      3550633.63     10514707.91
      3550638.13     10514672.09      3550662.11     10514641.64

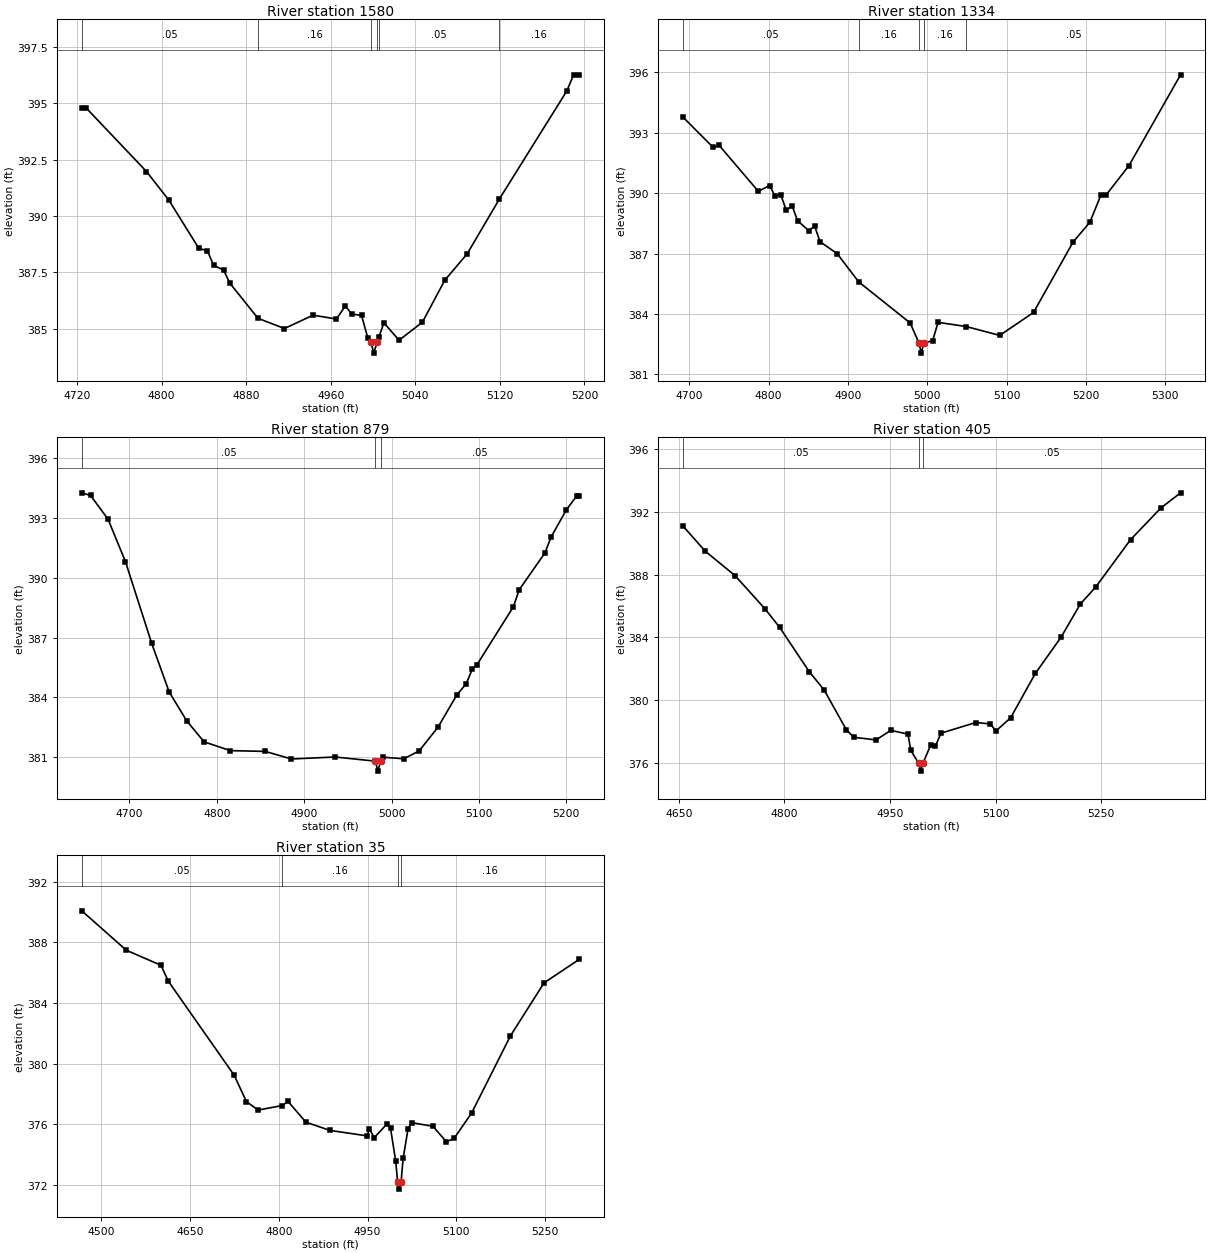
Type RM Length L Ch R = 1,1580,246,246,246
BEGIN DESCRIPTION:
UNT01895 IN SAND CR 3.0
END DESCRIPTION:
XS GIS Cut Line= 2
      3549675.63     10515381.38      3549278.11     10515129.68
#Sta/Elev= 30
  4724.6  394.77  4729.0  394.77  4785.8  391.97  4807.0  390.70  4835.3  388.57
  4843.4  388.46  4849.3  387.82  4858.7  387.61  4864.6  387.03  4891.3  385.47
  4916.3  385.02  4943.4  385.61  4965.5  385.44  4973.9  386.02  4979.9  385.66
  4989.2  385.60  4995.1  384.61  4998.0  384.43  5000.8  383.93  5004.0  384.43
  5005.5  384.63  5010.4  385.27  5024.7  384.50  5046.8  385.30  5068.0  387.16
  5089.2  388.33  5119.7  390.76  5183.3  395.53  5189.8  396.25  5195.1  396.25
#Mann=6,-1,0
  4724.6    0.05       0  4891.3    0.16       0  4998.0    0.07       0
  5004.0    0.16       0  5005.5    0.05       0  5119.7    0.16       0
Bank Sta=4998,5004
Exp/Cntr=0.3,0.1

Type RM Length L Ch R = 1,1334,455,455,455
BEGIN DESCRIPTION:
UNT01895 IN SAND CR 3.1
END DESCRIPTION:
XS GIS Cut Line= 2
      3549857.93     10515299.79      3549392.65     10514879.65
#Sta/Elev= 30
  4692.4  393.77  4730.4  392.27  4737.9  392.37  4787.2  390.09  4801.4  390.38
  4808.2  389.86  4815.6  389.91  4822.4  389.14  4829.8  389.37  4836.6  388.63
  4850.7  388.14  4858.2  388.36  4864.9  387.59  4886.6  386.99  4913.7  385.59
  4978.5  383.55  4989.7  382.55  4992.5  382.05  4995.7  382.55  5006.9  382.67
  5013.7  383.58  5049.4  383.37  5091.4  382.93  5134.0  384.07  5184.0  387.58
  5205.0  388.55  5219.2  389.93  5225.9  389.93  5254.3  391.37  5319.3  395.88
#Mann=5,-1,0
  4692.4    0.05       0  4913.7    0.16       0  4989.7    0.07       0
  4995.7    0.16       0  5049.4    0.05       0
Bank Sta=4989.7,4995.7
Exp/Cntr=0.3,0.1

Type RM Length L Ch R = 1,879,474,474,474
BEGIN DESCRIPTION:
UNT01895 IN SAND CR 2.0
END DESCRIPTION:
XS GIS Cut Line= 3
      3549942.11     10515191.66      3549942.11     10514891.64
      3549842.10     10514641.62
#Sta/Elev= 30
  4645.5  394.27  4655.5  394.14  4675.5  392.95  4695.5  390.81  4725.5  386.71
  4745.5  384.27  4765.5  382.82  4785.5  381.76  4815.5  381.32  4855.5  381.28
  4885.5  380.90  4935.5  381.00  4981.6  380.79  4984.3  380.29  4987.6  380.79
  4989.9  380.99  5014.2  380.91  5031.7  381.31  5053.2  382.50  5074.8  384.12
  5085.5  384.68  5092.3  385.40  5097.7  385.63  5139.4  388.54  5146.1  389.40
  5175.7  391.26  5182.5  392.04  5200.0  393.41  5212.1  394.12  5214.8  394.12
#Mann=3,-1,0
  4645.5    0.05       0  4981.6    0.03       0  4987.6    0.05       0
Bank Sta=4981.6,4987.6
Exp/Cntr=0.3,0.1

Type RM Length L Ch R = 1,405,370,370,370
BEGIN DESCRIPTION:
UNT01895 IN SAND CR 1.0
END DESCRIPTION:
XS GIS Cut Line= 3
      3550492.10     10515191.62      3550392.11     10514891.64
      3550142.12     10514591.66
#Sta/Elev= 30
  4656.0  391.09  4687.6  389.49  4729.8  387.94  4771.9  385.84  4793.0  384.65
  4835.2  381.81  4856.3  380.65  4887.9  378.11  4898.4  377.63  4930.0  377.46
  4951.1  378.07  4975.5  377.83  4979.4  376.80  4990.7  375.97  4993.4  375.47
  4996.7  375.97  5008.0  377.16  5014.5  377.07  5022.3  377.89  5071.8  378.57
  5092.6  378.48  5100.4  378.03  5121.3  378.87  5156.4  381.70  5192.8  384.00
  5220.2  386.12  5242.3  387.22  5291.8  390.24  5334.7  392.25  5362.7  393.22
#Mann=3,-1,0
  4656.0    0.05       0  4990.7    0.03       0  4996.7    0.05       0
Bank Sta=4990.7,4996.7
Exp/Cntr=0.3,0.1

Type RM Length L Ch R = 1,35,0,0,0
BEGIN DESCRIPTION:
UNT01895 IN SAND CR 1.01
END DESCRIPTION:
XS GIS Cut Line= 3
      3550607.10     10515176.09      3550678.22     10514694.98
      3550388.21     10514492.75
#Sta/Elev= 30
  4467.4  390.08  4542.7  387.48  4601.2  386.49  4613.4  385.45  4724.6  379.25
  4745.4  377.51  4765.1  376.95  4806.0  377.25  4815.6  377.52  4845.9  376.15
  4886.4  375.61  4949.1  375.25  4952.9  375.72  4961.2  375.13  4982.6  376.03
  4988.7  375.76  4997.5  373.57  5000.6  372.24  5003.3  371.74  5006.6  372.24
  5010.0  373.77  5018.4  375.73  5024.5  376.12  5060.3  375.88  5083.1  374.86
  5096.0  375.08  5125.7  376.76  5191.2  381.84  5247.9  385.33  5307.3  386.88
#Mann=4,-1,0
  4467.4    0.05       0  4806.0    0.16       0  5000.6    0.07       0
  5006.6    0.16       0
Bank Sta=5000.6,5006.6
Exp/Cntr=0.3,0.1

Chan Stop Cuts=-1