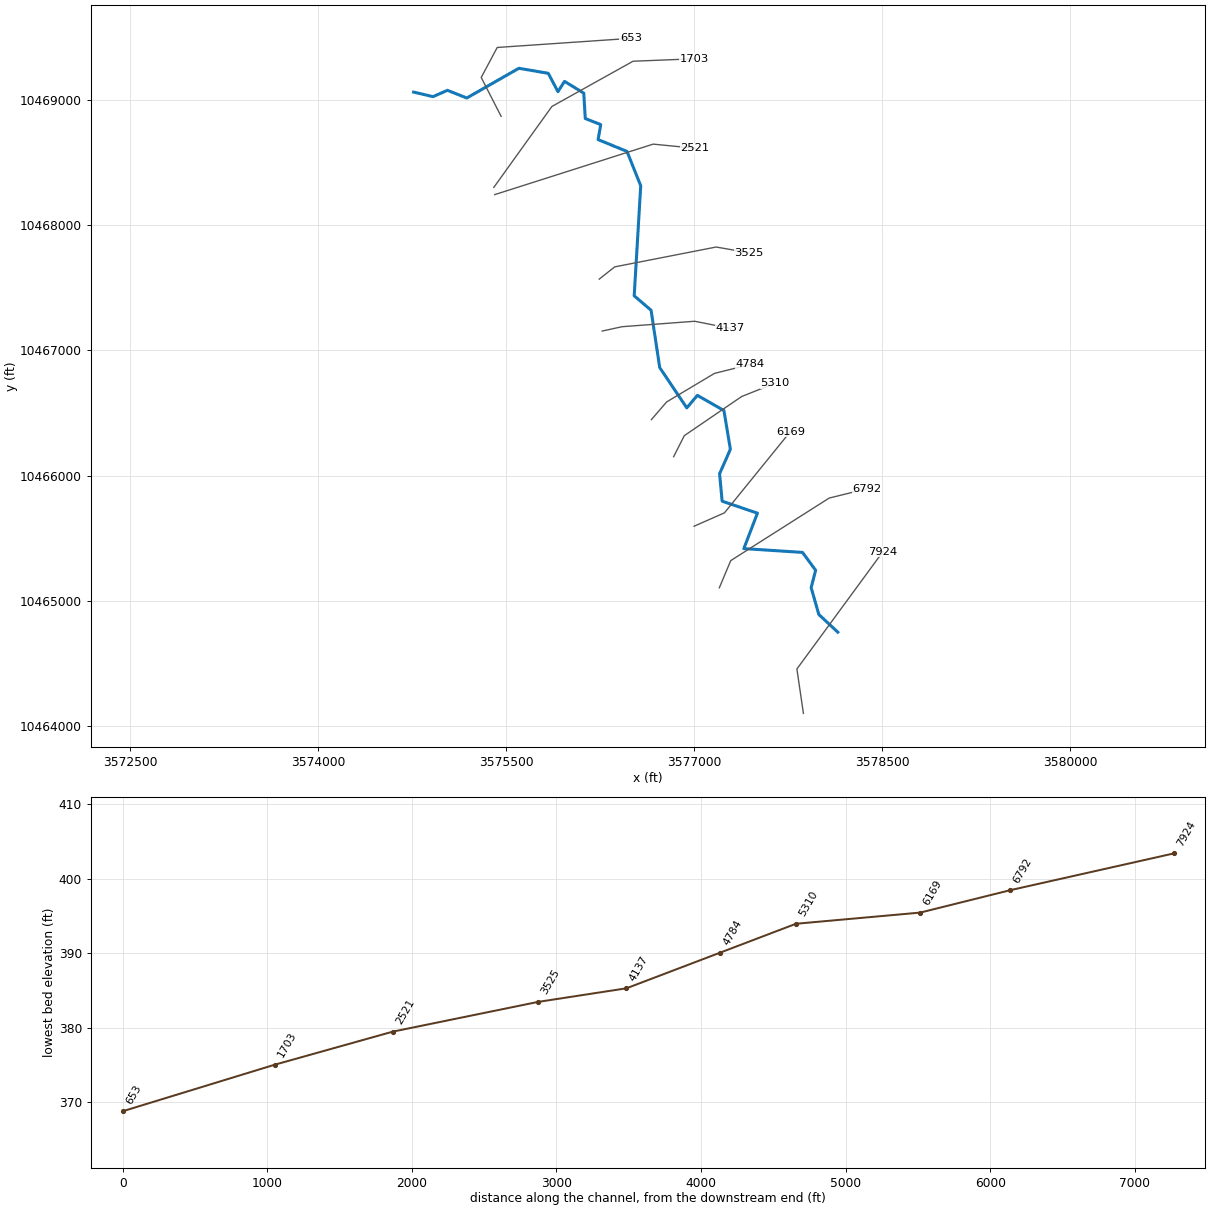
--- UNT0190 IN SAND CR.prj (project) ---

Proj Title=UNT0190 IN SAND CR Base Level Engineering
Current Plan=p01
Default Exp/Contr=0.3,0.1
English Units
Geom File=g01
Flow File=f01
Plan File=p01
BEGIN DESCRIPTION:
UNT0190 IN SAND CR
END DESCRIPTION:

--- UNT0190 IN SAND CR.p01 (plan) ---

Plan Title=Multiple Run
Short Identifier=Multiple
Geom File=g01
Flow File=f01
Subcritical Flow
K Sum by GR= 0
Std Step Tol= 0.01
Critical Tol= 0.01
Num of Std Step Trials= 20
Max Error Tol= 0.3
Flow Tol Ratio= 0.001
Split Flow NTrial= 30
Split Flow Tol= 0.02
Split Flow Ratio= 0.02
Log Output Level= 0
Friction Slope Method= 1
Unsteady Friction Slope Method= 2
Unsteady Bridges Friction Slope Method= 1
Parabolic Critical Depth
Global Vel Dist=  1 , 1 , 1
Global Log Level= 0
CheckData=True
Encroach Param= -1, 0, 0, 0
BEGIN DESCRIPTION:
Multiple Run
END DESCRIPTION:

--- UNT0190 IN SAND CR.f01 (steady flow) ---

Flow Title=Multiple
Number of Profiles=7
Profile Names=10-year,25-year,50-year,1pct_min,100-year,1pct_plu,500-year
River Rch & RM= UNT0190 IN SAND ,Reach-1,7924
    1427    1994    2469    2227    3012    4074    4473
Boundary for River Rch & Prof#=UNT0190 IN SAND ,Reach-1,1
Up Type=0
Dn Type=3
Dn Slope=0.005
Boundary for River Rch & Prof#=UNT0190 IN SAND ,Reach-1,2
Up Type=0
Dn Type=3
Dn Slope=0.005
Boundary for River Rch & Prof#=UNT0190 IN SAND ,Reach-1,3
Up Type=0
Dn Type=3
Dn Slope=0.005
Boundary for River Rch & Prof#=UNT0190 IN SAND ,Reach-1,4
Up Type=0
Dn Type=3
Dn Slope=0.005
Boundary for River Rch & Prof#=UNT0190 IN SAND ,Reach-1,5
Up Type=0
Dn Type=3
Dn Slope=0.005
Boundary for River Rch & Prof#=UNT0190 IN SAND ,Reach-1,6
Up Type=0
Dn Type=3
Dn Slope=0.005
Boundary for River Rch & Prof#=UNT0190 IN SAND ,Reach-1,7
Up Type=0
Dn Type=3
Dn Slope=0.005

--- UNT0190 IN SAND CR.g01 (geometry) ---

Geom Title=Existing Conditions

River Reach=UNT0190 IN SAND ,Reach-1
Reach XY= 30
      3578147.38     10464751.81      3577995.53     10464893.05
      3577934.50     10465107.15      3577970.14     10465245.71
      3577865.54     10465388.41      3577397.37     10465418.75
      3577505.90     10465701.47      3577224.17     10465797.22
      3577203.66     10466015.80      3577289.83     10466211.52
      3577238.55     10466520.28      3577026.40     10466641.60
      3576942.11     10466541.64      3576725.96     10466863.33
      3576657.12     10467320.72      3576522.41     10467436.23
      3576574.51     10468314.11      3576465.14     10468588.07
      3576234.23     10468682.51      3576255.41     10468802.30
      3576132.15     10468850.57      3576119.82     10469053.22
      3575966.36     10469147.24      3575913.95     10469064.73
      3575836.87     10469211.39      3575602.03     10469251.57
      3575186.73     10469014.37      3575031.94     10469075.88
      3574917.22     10469025.23      3574762.11     10469061.64

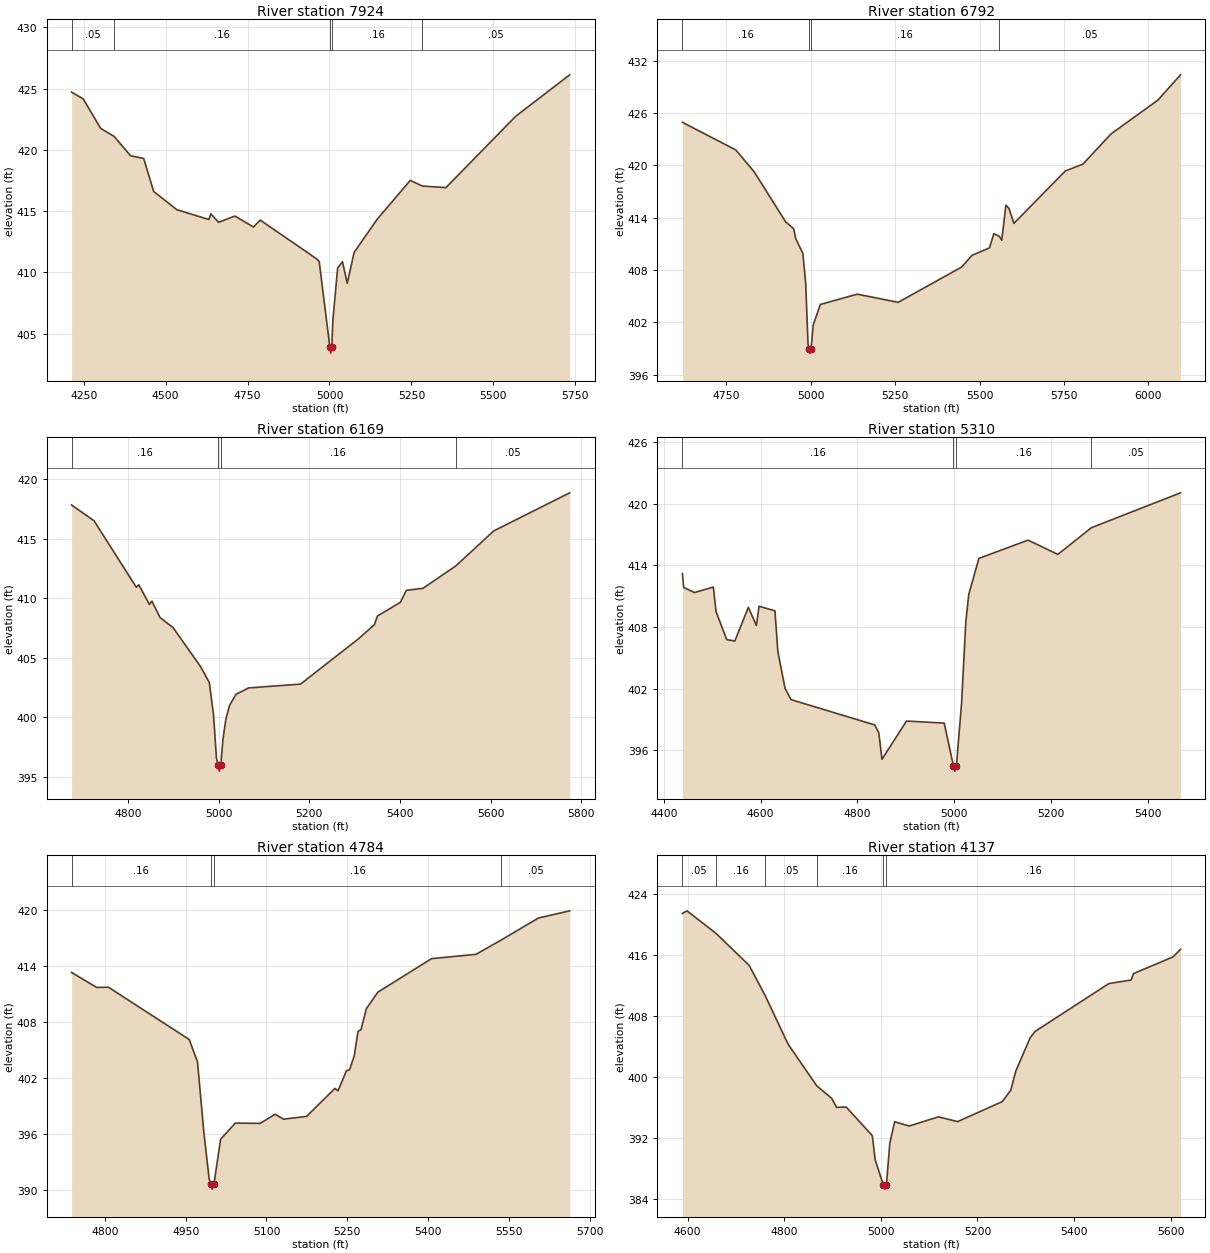
Type RM Length L Ch R = 1,7924,1132,1132,1132
BEGIN DESCRIPTION:
UNT0190 IN SAND CR 14.0
END DESCRIPTION:
XS GIS Cut Line= 3
      3577872.68     10464103.93      3577820.60     10464458.09
      3578507.60     10465394.91
#Sta/Elev= 30
  4213.2  424.72  4248.9  424.16  4301.9  421.76  4343.1  421.10  4393.4  419.52
  4433.3  419.30  4463.6  416.61  4534.3  415.12  4632.1  414.32  4638.3  414.78
  4661.5  414.09  4711.6  414.60  4768.0  413.71  4788.8  414.27  4960.2  411.12
  4968.7  410.89  5001.2  403.91  5003.9  403.41  5007.2  403.91  5010.4  406.09
  5025.0  410.36  5039.7  410.87  5054.3  409.11  5075.2  411.63  5146.2  414.36
  5246.5  417.51  5283.8  417.05  5355.3  416.92  5568.4  422.75  5732.9  426.13
#Mann=5,-1,0
  4213.2    0.05       0  4343.1    0.16       0  5001.2    0.07       0
  5007.2    0.16       0  5283.8    0.05       0
Bank Sta=5001.2,5007.2
Exp/Cntr=0.3,0.1

Type RM Length L Ch R = 1,6792,623,623,623
BEGIN DESCRIPTION:
UNT0190 IN SAND CR 13.0
END DESCRIPTION:
XS GIS Cut Line= 4
      3577201.59     10465105.92      3577292.75     10465322.97
      3578078.34     10465822.10      3578377.43     10465895.79
#Sta/Elev= 30
  4620.7  424.93  4778.8  421.76  4833.0  419.26  4926.4  413.51  4950.1  412.73
  4956.1  411.61  4977.3  409.88  4985.7  406.41  4992.5  399.56  4995.5  398.97
  4998.2  398.47  5001.5  398.97  5007.8  401.67  5029.0  404.05  5138.2  405.23
  5259.3  404.29  5447.7  408.35  5477.8  409.68  5529.5  410.53  5542.5  412.17
  5558.2  411.87  5565.9  411.42  5578.1  415.42  5587.1  415.07  5601.8  413.34
  5753.9  419.35  5806.0  420.13  5889.0  423.59  6027.6  427.46  6094.9  430.37
#Mann=4,-1,0
  4620.7    0.16       0  4995.5    0.07       0  5001.5    0.16       0
  5558.2    0.05       0
Bank Sta=4995.5,5001.5
Exp/Cntr=0.3,0.1

Type RM Length L Ch R = 1,6169,859,859,859
BEGIN DESCRIPTION:
UNT0190 IN SAND CR 11.0
END DESCRIPTION:
XS GIS Cut Line= 3
      3577000.27     10465597.28      3577242.49     10465704.07
      3577767.84     10466351.65
#Sta/Elev= 30
  4675.8  417.82  4725.4  416.49  4818.7  410.90  4824.1  411.12  4847.5  409.46
  4852.9  409.75  4870.8  408.37  4899.6  407.52  4960.2  404.25  4979.6  402.90
  4988.9  400.18  4995.4  396.56  4998.8  395.96  5001.6  395.46  5004.8  395.96
  5009.8  398.18  5016.2  399.85  5024.2  400.98  5038.5  401.91  5066.2  402.45
  5180.8  402.77  5308.7  406.58  5343.8  407.77  5350.3  408.49  5401.0  409.64
  5414.2  410.65  5450.9  410.82  5522.9  412.69  5607.0  415.64  5774.4  418.84
#Mann=4,-1,0
  4675.8    0.16       0  4998.8    0.07       0  5004.8    0.16       0
  5522.9    0.05       0
Bank Sta=4998.8,5004.8
Exp/Cntr=0.3,0.1

Type RM Length L Ch R = 1,5310,526,526,526
BEGIN DESCRIPTION:
UNT0190 IN SAND CR 9.0
END DESCRIPTION:
XS GIS Cut Line= 4
      3576837.00     10466151.93      3576922.20     10466319.97
      3577380.10     10466632.47      3577647.03     10466738.81
#Sta/Elev= 30
  4438.1  413.22  4440.8  411.86  4463.1  411.36  4502.1  411.90  4507.7  409.50
  4529.9  406.77  4546.6  406.64  4574.5  409.92  4591.1  408.15  4596.7  410.03
  4629.5  409.58  4635.4  405.64  4650.3  402.04  4662.7  400.93  4835.9  398.46
  4844.3  397.69  4850.8  395.11  4901.6  398.84  4979.5  398.64  4998.7  394.46
  5001.4  393.96  5004.7  394.46  5015.4  400.54  5024.2  408.50  5030.3  411.18
  5051.3  414.69  5152.9  416.47  5214.6  415.08  5283.9  417.68  5468.2  421.08
#Mann=4,-1,0
  4438.1    0.16       0  4998.7    0.07       0  5004.7    0.16       0
  5283.9    0.05       0
Bank Sta=4998.7,5004.7
Exp/Cntr=0.3,0.1

Type RM Length L Ch R = 1,4784,647,647,647
BEGIN DESCRIPTION:
UNT0190 IN SAND CR 7.0
END DESCRIPTION:
XS GIS Cut Line= 4
      3576659.61     10466448.01      3576781.14     10466589.07
      3577163.08     10466816.93      3577448.37     10466888.25
#Sta/Elev= 30
  4738.1  413.27  4784.7  411.67  4806.6  411.69  4956.6  406.09  4972.0  403.68
  4983.8  396.13  4993.5  391.22  4996.4  390.57  4999.1  390.07  5002.4  390.57
  5014.9  395.42  5042.2  397.14  5088.4  397.11  5116.1  398.09  5131.7  397.56
  5174.5  397.86  5227.1  400.85  5232.9  400.59  5248.5  402.74  5254.3  402.85
  5263.1  404.36  5269.9  406.94  5275.7  407.16  5285.5  409.39  5306.9  411.16
  5406.6  414.75  5489.1  415.21  5535.5  416.73  5605.1  419.10  5663.1  419.87
#Mann=4,-1,0
  4738.1    0.16       0  4996.4    0.07       0  5002.4    0.16       0
  5535.5    0.05       0
Bank Sta=4996.4,5002.4
Exp/Cntr=0.3,0.1

Type RM Length L Ch R = 1,4137,612,612,612
BEGIN DESCRIPTION:
UNT0190 IN SAND CR 6.0
END DESCRIPTION:
XS GIS Cut Line= 4
      3576267.18     10467154.75      3576425.60     10467189.47
      3577005.02     10467232.87      3577287.69     10467176.77
#Sta/Elev= 30
  4589.2  421.47  4598.7  421.82  4658.5  418.88  4727.3  414.67  4760.5  410.71
  4808.0  404.32  4867.4  398.85  4898.3  397.21  4908.3  396.03  4928.4  396.06
  4982.4  392.31  4988.5  389.11  5005.6  385.79  5008.4  385.29  5011.6  385.79
  5018.6  391.29  5028.7  394.14  5058.7  393.57  5119.5  394.78  5159.0  394.15
  5251.6  396.78  5269.3  398.29  5279.4  400.77  5309.4  405.17  5319.5  405.99
  5472.2  412.27  5518.3  412.74  5523.4  413.59  5604.7  415.76  5620.6  416.76
#Mann=6,-1,0
  4589.2    0.05       0  4658.5    0.16       0  4760.5    0.05       0
  4867.4    0.16       0  5005.6    0.07       0  5011.6    0.16       0
Bank Sta=5005.6,5011.6
Exp/Cntr=0.3,0.1

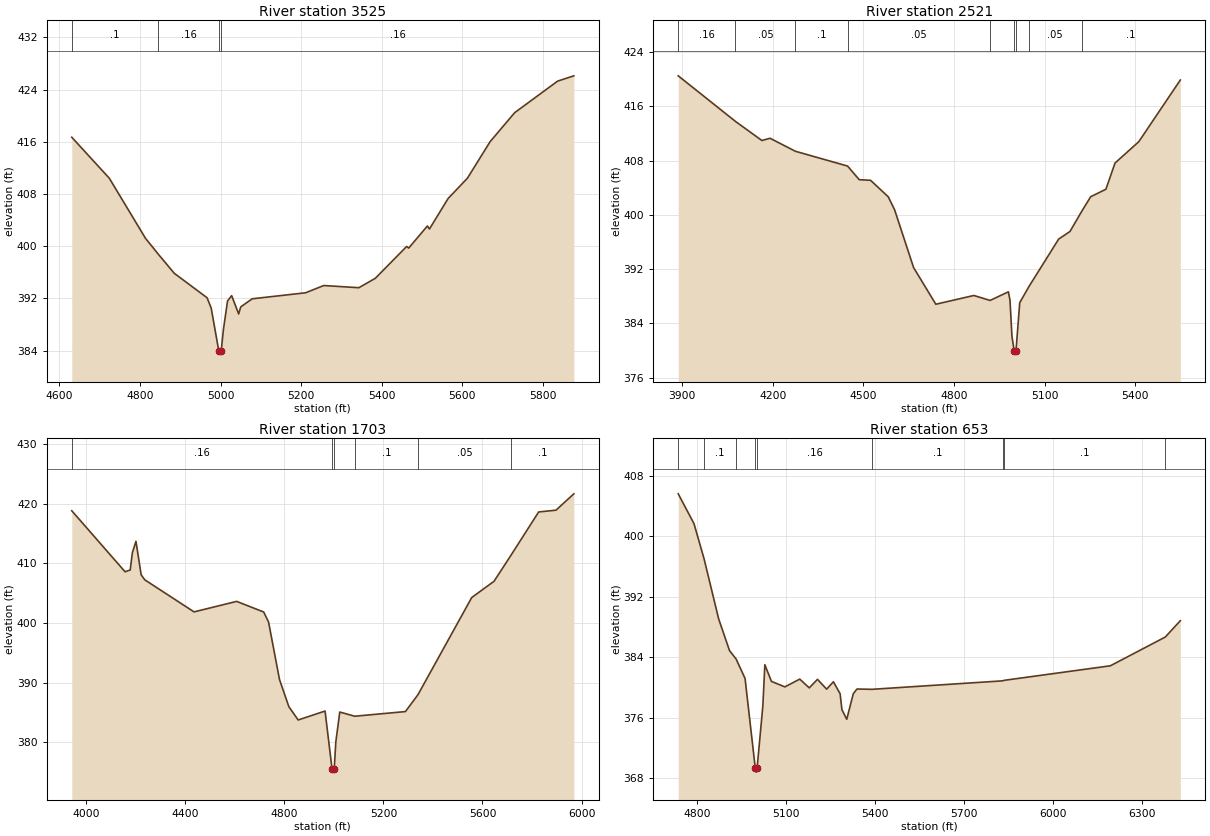
Type RM Length L Ch R = 1,3525,1004,1004,1004
BEGIN DESCRIPTION:
UNT0190 IN SAND CR 5.0
END DESCRIPTION:
XS GIS Cut Line= 4
      3576243.32     10467569.26      3576367.00     10467666.90
      3577176.47     10467825.32      3577436.91     10467779.74
#Sta/Elev= 30
  4630.5  416.70  4723.8  410.41  4813.7  401.20  4845.7  398.75  4885.0  395.85
  4966.5  392.10  4976.7  390.53  4995.6  383.96  4998.3  383.46  5001.6  383.96
  5007.3  387.33  5017.4  391.62  5027.6  392.42  5045.0  389.61  5050.1  390.70
  5078.6  391.94  5211.1  392.86  5256.1  393.97  5343.5  393.64  5384.3  395.08
  5462.1  399.96  5467.2  399.71  5513.6  403.10  5518.7  402.63  5565.2  407.32
  5612.9  410.41  5669.4  416.02  5730.3  420.46  5837.1  425.30  5877.3  426.11
#Mann=4,-1,0
  4630.5     0.1       0  4845.7    0.16       0  4995.6    0.07       0
  5001.6    0.16       0
Bank Sta=4995.6,5001.6
Exp/Cntr=0.3,0.1

Type RM Length L Ch R = 1,2521,818,818,818
BEGIN DESCRIPTION:
UNT0190 IN SAND CR 3.0
END DESCRIPTION:
XS GIS Cut Line= 3
      3575409.99     10468243.66      3576673.86     10468646.43
      3577007.13     10468613.45
#Sta/Elev= 30
  3887.2  420.52  4076.5  413.80  4164.0  410.98  4191.0  411.31  4275.0  409.39
  4447.6  407.21  4486.1  405.20  4523.6  405.11  4582.1  402.68  4603.1  400.77
  4666.1  392.23  4739.6  386.83  4865.5  388.12  4919.2  387.39  4979.8  388.66
  4985.0  387.42  4991.5  382.08  4998.9  379.97  5001.7  379.47  5004.9  379.97
  5017.2  387.05  5047.2  389.40  5146.1  396.44  5183.5  397.56  5221.9  400.50
  5252.1  402.69  5302.4  403.79  5332.5  407.65  5411.3  410.81  5548.6  419.90
#Mann=9,-1,0
  3887.2    0.16       0  4076.5    0.05       0  4275.0     0.1       0
  4447.6    0.05       0  4919.2     0.1       0  4998.9    0.07       0
  5004.9     0.1       0  5047.2    0.05       0  5221.9     0.1       0
Bank Sta=4998.9,5004.9
Exp/Cntr=0.3,0.1

Type RM Length L Ch R = 1,1703,1050,1050,1050
BEGIN DESCRIPTION:
UNT0190 IN SAND CR 2.0
END DESCRIPTION:
XS GIS Cut Line= 4
      3575402.15     10468301.10      3575865.70     10468946.95
      3576513.23     10469307.89      3577004.13     10469327.42
#Sta/Elev= 30
  3941.3  418.83  4156.5  408.61  4177.4  408.90  4185.9  411.78  4200.5  413.71
  4221.6  408.09  4236.3  407.25  4435.2  401.88  4607.2  403.64  4716.4  401.86
  4736.1  400.17  4780.2  390.55  4817.9  386.00  4855.6  383.76  4964.2  385.26
  4992.5  375.52  4995.2  375.02  4998.5  375.52  5001.9  376.03  5007.7  380.10
  5023.7  385.09  5083.9  384.39  5288.8  385.17  5339.4  388.00  5556.6  404.29
  5646.6  407.01  5716.7  411.48  5826.8  418.63  5896.8  418.93  5968.9  421.67
#Mann=6,-1,0
  3941.3    0.16       0  4992.5    0.07       0  4998.5    0.16       0
  5083.9     0.1       0  5339.4    0.05       0  5716.7     0.1       0
Bank Sta=4992.5,4998.5
Exp/Cntr=0.3,0.1

Type RM Length L Ch R = 1,653,0,0,0
BEGIN DESCRIPTION:
UNT0190 IN SAND CR 1.0
END DESCRIPTION:
XS GIS Cut Line= 4
      3575460.54     10468868.16      3575301.68     10469178.07
      3575429.28     10469417.65      3576496.99     10469490.57
#Sta/Elev= 30
  4737.6  405.58  4790.5  401.65  4824.4  397.01  4873.7  389.04  4910.1  384.86
  4932.5  383.73  4962.5  381.17  4997.0  369.28  4999.7  368.78  5003.0  369.28
  5022.4  377.53  5029.1  382.98  5051.3  380.78  5096.5  380.05  5146.6  381.08
  5178.7  379.92  5206.3  381.05  5237.2  379.75  5259.9  380.73  5282.5  379.14
  5288.5  377.04  5304.8  375.77  5326.8  379.15  5339.2  379.77  5389.9  379.73
  5829.7  380.85  5835.1  380.92  6192.1  382.84  6376.8  386.64  6427.5  388.80
#Mann=9,-1,0
  4737.6    0.16       0  4824.4     0.1       0  4932.5    0.16       0
  4997.0    0.07       0  5003.0    0.16       0  5389.9     0.1       0
  5829.7    0.05       0  5835.1     0.1       0  6376.8    0.05       0
Bank Sta=4997,5003
Exp/Cntr=0.3,0.1

Chan Stop Cuts=-1