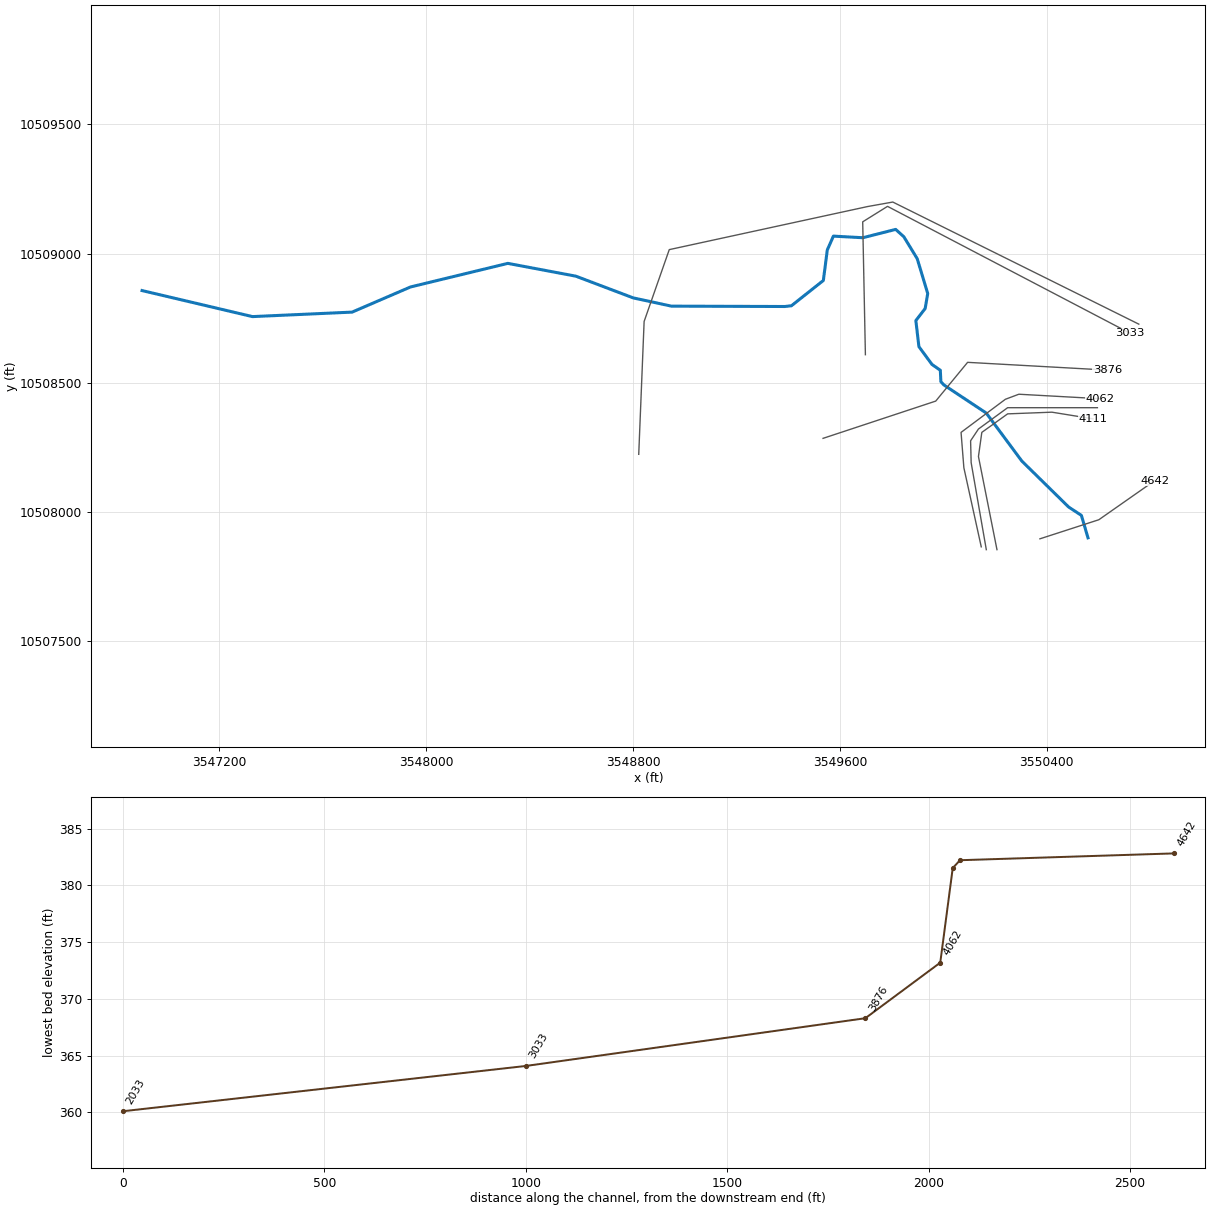
--- UNT01904 IN SAND CR.prj (project) ---

Proj Title=UNT01904 IN SAND CR Base Level Engineering
Current Plan=p01
Default Exp/Contr=0.3,0.1
English Units
Geom File=g01
Flow File=f01
Plan File=p01
BEGIN DESCRIPTION:
UNT01904 IN SAND CR
END DESCRIPTION:

--- UNT01904 IN SAND CR.p01 (plan) ---

Plan Title=Multiple Run
Short Identifier=Multiple
Geom File=g01
Flow File=f01
Subcritical Flow
K Sum by GR= 0
Std Step Tol= 0.01
Critical Tol= 0.01
Num of Std Step Trials= 20
Max Error Tol= 0.3
Flow Tol Ratio= 0.001
Split Flow NTrial= 30
Split Flow Tol= 0.02
Split Flow Ratio= 0.02
Log Output Level= 0
Friction Slope Method= 1
Unsteady Friction Slope Method= 2
Unsteady Bridges Friction Slope Method= 1
Parabolic Critical Depth
Global Vel Dist=  1 , 1 , 1
Global Log Level= 0
CheckData=True
Encroach Param= -1, 0, 0, 0
BEGIN DESCRIPTION:
Multiple Run
END DESCRIPTION:

--- UNT01904 IN SAND CR.f01 (steady flow) ---

Flow Title=Multiple
Number of Profiles=7
Profile Names=10-year,25-year,50-year,1pct_min,100-year,1pct_plu,500-year
River Rch & RM= UNT01904 IN SAND,Reach-1,4642
     523     694     831     728     985    1332    1378
Boundary for River Rch & Prof#=UNT01904 IN SAND,Reach-1,1
Up Type=0
Dn Type=3
Dn Slope=0.005
Boundary for River Rch & Prof#=UNT01904 IN SAND,Reach-1,2
Up Type=0
Dn Type=3
Dn Slope=0.005
Boundary for River Rch & Prof#=UNT01904 IN SAND,Reach-1,3
Up Type=0
Dn Type=3
Dn Slope=0.005
Boundary for River Rch & Prof#=UNT01904 IN SAND,Reach-1,4
Up Type=0
Dn Type=3
Dn Slope=0.005
Boundary for River Rch & Prof#=UNT01904 IN SAND,Reach-1,5
Up Type=0
Dn Type=3
Dn Slope=0.005
Boundary for River Rch & Prof#=UNT01904 IN SAND,Reach-1,6
Up Type=0
Dn Type=3
Dn Slope=0.005
Boundary for River Rch & Prof#=UNT01904 IN SAND,Reach-1,7
Up Type=0
Dn Type=3
Dn Slope=0.005

--- UNT01904 IN SAND CR.g01 (geometry) ---

Geom Title=Existing Conditions

River Reach=UNT01904 IN SAND,Reach-1
Reach XY= 30
      3550559.48     10507900.79      3550533.95     10507987.61
      3550484.63     10508019.91      3550303.42     10508197.90
      3550165.99     10508383.34      3550001.93     10508492.19
      3549990.47     10508504.69      3549988.39     10508548.96
      3549956.09     10508571.36      3549905.57     10508640.11
      3549893.73     10508741.01      3549929.67     10508787.46
      3549939.67     10508845.56      3549898.98     10508980.36
      3549847.35     10509065.03      3549815.78     10509093.64
      3549688.75     10509061.40      3549574.87     10509067.65
      3549551.25     10509014.17      3549535.98     10508896.12
      3549412.37     10508798.20      3549386.67     10508795.42
      3548948.48     10508796.81      3548800.56     10508828.76
      3548578.69     10508912.75      3548315.66     10508962.23
      3547939.24     10508870.96      3547713.54     10508773.73
      3547328.12     10508756.37      3546901.04     10508857.07

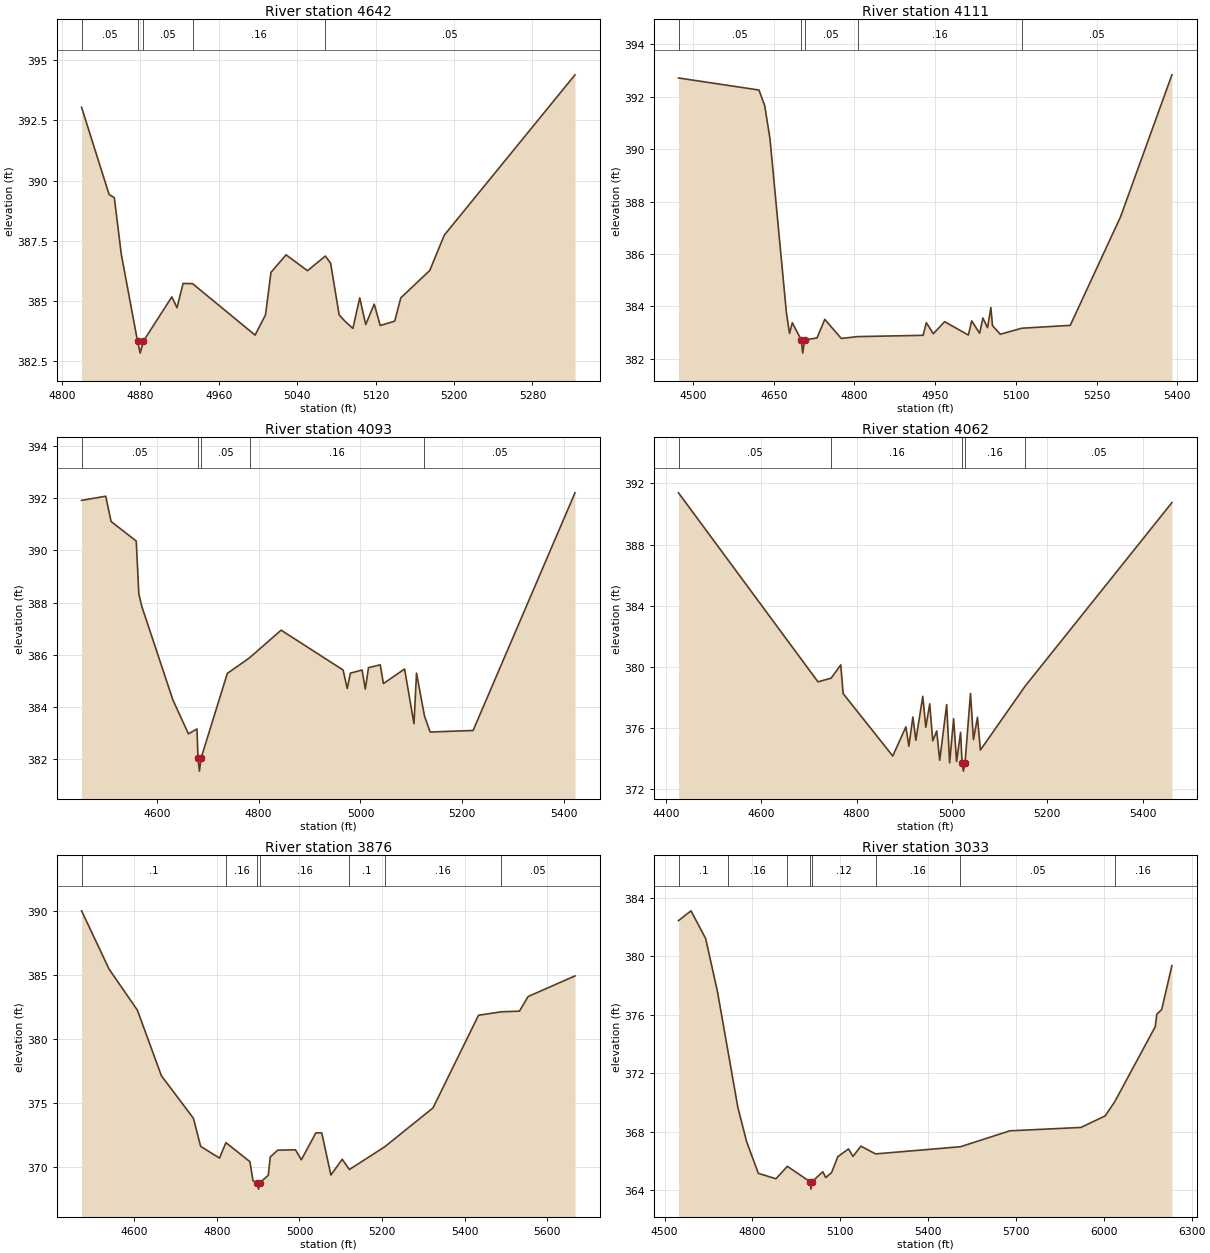
Type RM Length L Ch R = 1,4642,531,531,531
BEGIN DESCRIPTION:
UNT01904 IN SAND CR 4.0
END DESCRIPTION:
XS GIS Cut Line= 3
      3550373.57     10507896.95      3550601.43     10507970.73
      3550817.79     10508122.18
#Sta/Elev= 30
  4819.9  393.05  4848.0  389.42  4853.3  389.29  4860.4  386.94  4877.0  383.32
  4879.7  382.82  4883.0  383.32  4912.0  385.16  4917.3  384.71  4923.5  385.72
  4933.2  385.71  4997.0  383.57  5007.6  384.41  5013.2  386.18  5028.6  386.91
  5050.5  386.25  5068.7  386.86  5074.1  386.56  5082.8  384.41  5088.9  384.14
  5096.8  383.85  5103.8  385.12  5109.9  384.01  5118.6  384.86  5124.7  383.97
  5139.5  384.15  5145.7  385.12  5175.3  386.26  5190.1  387.73  5323.5  394.40
#Mann=5,-1,0
  4819.9    0.05       0  4877.0    0.07       0  4883.0    0.05       0
  4933.2    0.16       0  5068.7    0.05       0
Bank Sta=4877,4883
Exp/Cntr=0.3,0.1

Type RM Length L Ch R = 1,4111,18,18,18
BEGIN DESCRIPTION:
UNT01904 IN SAND CR 3.0
END DESCRIPTION:
XS GIS Cut Line= 6
      3550207.46     10507855.01      3550135.84     10508215.27
      3550148.86     10508308.58      3550248.69     10508380.20
      3550420.13     10508386.71      3550578.91     10508360.96
#Sta/Elev= 30
  4473.1  392.72  4622.6  392.26  4633.3  391.66  4643.0  390.41  4673.6  383.76
  4679.4  382.97  4684.5  383.38  4701.2  382.72  4703.9  382.22  4707.2  382.72
  4730.5  382.80  4744.9  383.51  4775.5  382.78  4805.7  382.85  4927.6  382.90
  4933.6  383.38  4946.6  382.96  4967.5  383.42  5011.7  382.91  5017.8  383.45
  5032.6  382.98  5038.7  383.56  5047.3  383.19  5053.5  383.96  5056.5  383.27
  5070.9  382.94  5110.8  383.17  5201.0  383.28  5294.4  387.42  5389.9  392.84
#Mann=5,-1,0
  4473.1    0.05       0  4701.2    0.07       0  4707.2    0.05       0
  4805.7    0.16       0  5110.8    0.05       0
Bank Sta=4701.2,4707.2
Exp/Cntr=0.3,0.1

Type RM Length L Ch R = 1,4093,31,31,31
BEGIN DESCRIPTION:
UNT01904 IN SAND CR 3.2
END DESCRIPTION:
XS GIS Cut Line= 6
      3550166.23     10507854.99      3550107.63     10508191.39
      3550105.46     10508276.03      3550135.84     10508321.60
      3550248.69     10508404.07      3550595.93     10508404.07
#Sta/Elev= 30
  4452.5  391.92  4499.9  392.08  4510.4  391.11  4559.8  390.36  4564.9  388.33
  4570.9  387.84  4631.8  384.26  4662.3  382.96  4679.0  383.15  4681.1  382.03
  4683.8  381.53  4687.1  382.03  4738.6  385.28  4782.3  385.88  4844.2  386.94
  4965.9  385.41  4974.0  384.70  4980.2  385.29  5003.1  385.41  5009.5  384.68
  5015.7  385.50  5038.8  385.61  5045.0  384.89  5086.6  385.45  5105.0  383.35
  5110.0  385.29  5125.6  383.65  5136.8  383.03  5221.1  383.09  5421.1  392.21
#Mann=5,-1,0
  4452.5    0.05       0  4681.1    0.07       0  4687.1    0.05       0
  4782.3    0.16       0  5125.6    0.05       0
Bank Sta=4681.1,4687.1
Exp/Cntr=0.3,0.1

Type RM Length L Ch R = 1,4062,186,186,186
BEGIN DESCRIPTION:
UNT01904 IN SAND CR 3.3
END DESCRIPTION:
XS GIS Cut Line= 6
      3550146.69     10507865.88      3550079.42     10508171.86
      3550068.57     10508308.58      3550240.01     10508436.62
      3550292.09     10508456.15      3550606.78     10508438.79
#Sta/Elev= 30
  4426.5  391.39  4719.1  379.03  4746.7  379.27  4766.9  380.14  4771.9  378.26
  4876.0  374.18  4903.6  376.09  4909.8  374.82  4918.2  376.73  4924.4  375.21
  4939.0  378.08  4945.3  376.06  4953.6  377.59  4959.9  375.17  4968.2  375.82
  4974.5  373.90  4989.1  377.54  4995.3  373.73  5003.7  376.62  5009.9  373.82
  5018.3  375.73  5021.5  373.69  5024.2  373.19  5027.5  373.69  5039.1  378.27
  5045.3  375.25  5053.7  376.71  5059.9  374.57  5153.5  378.74  5461.7  390.75
#Mann=5,-1,0
  4426.5    0.05       0  4746.7    0.16       0  5021.5    0.07       0
  5027.5    0.16       0  5153.5    0.05       0
Bank Sta=5021.5,5027.5
Exp/Cntr=0.3,0.1

Type RM Length L Ch R = 1,3876,843,843,843
BEGIN DESCRIPTION:
UNT01904 IN SAND CR 3.1
END DESCRIPTION:
XS GIS Cut Line= 4
      3549534.80     10508285.51      3549970.60     10508429.61
      3550093.86     10508579.49      3550635.57     10508549.40
#Sta/Elev= 30
  4472.0  390.01  4538.5  385.47  4607.2  382.26  4665.4  377.14  4743.0  373.82
  4760.5  371.63  4806.2  370.71  4821.7  371.92  4879.9  370.43  4887.4  368.94
  4898.0  368.79  4900.7  368.29  4904.0  368.79  4924.4  369.37  4929.2  370.80
  4947.2  371.33  4990.2  371.36  5004.5  370.58  5039.7  372.68  5054.0  372.68
  5076.1  369.39  5103.6  370.62  5120.9  369.82  5206.4  371.59  5323.6  374.63
  5433.8  381.86  5489.4  382.13  5533.0  382.18  5554.0  383.32  5667.6  384.93
#Mann=7,-1,0
  4472.0     0.1       0  4821.7    0.16       0  4898.0    0.07       0
  4904.0    0.16       0  5120.9     0.1       0  5206.4    0.16       0
  5489.4    0.05       0
Bank Sta=4898,4904
Exp/Cntr=0.3,0.1

Type RM Length L Ch R = 1,3033,1000,1000,1000
BEGIN DESCRIPTION:
UNT01904 IN SAND CR 2.1
END DESCRIPTION:
XS GIS Cut Line= 4
      3549698.61     10508608.99      3549688.19     10509122.90
      3549784.18     10509182.73      3550721.71     10508692.27
#Sta/Elev= 30
  4547.4  382.45  4590.1  383.12  4640.1  381.22  4680.1  377.63  4716.4  373.51
  4750.1  369.67  4780.1  367.32  4820.1  365.16  4880.1  364.79  4919.2  365.64
  4997.1  364.58  4999.9  364.08  5003.1  364.58  5040.2  365.27  5050.2  364.87
  5070.2  365.21  5091.4  366.30  5128.0  366.83  5143.4  366.32  5170.4  367.02
  5220.3  366.49  5510.3  366.98  5679.1  368.07  5921.9  368.30  6004.6  369.09
  6037.3  370.06  6175.5  375.19  6181.1  376.05  6197.6  376.37  6232.6  379.37
#Mann=8,-1,0
  4547.4     0.1       0  4716.4    0.16       0  4919.2    0.12       0
  4997.1    0.07       0  5003.1    0.12       0  5220.3    0.16       0
  5510.3    0.05       0  6037.3    0.16       0
Bank Sta=4997.1,5003.1
Exp/Cntr=0.3,0.1

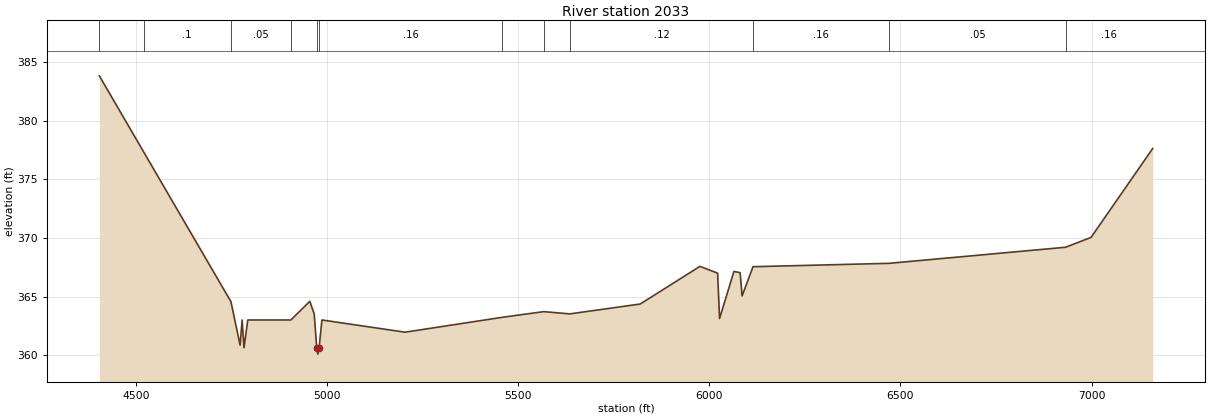
Type RM Length L Ch R = 1,2033,0,0,0
BEGIN DESCRIPTION:
UNT01904 IN SAND CR 1.1
END DESCRIPTION:
XS GIS Cut Line= 6
      3548821.97     10508223.73      3548842.81     10508737.61
      3548940.03     10509015.39      3549707.39     10509182.06
      3549804.61     10509199.42      3550756.04     10508727.18
#Sta/Elev= 30
  4404.9  383.81  4520.5  377.34  4749.1  364.56  4773.1  360.85  4778.3  363.00
  4783.3  360.63  4793.1  363.00  4905.8  363.00  4955.3  364.59  4966.8  363.52
  4973.5  360.59  4976.2  360.09  4979.5  360.59  4987.0  363.00  5204.4  361.96
  5459.0  363.23  5566.8  363.71  5635.6  363.52  5819.4  364.36  5975.6  367.57
  6021.8  366.99  6026.9  363.13  6064.5  367.14  6080.7  367.03  6085.8  365.05
  6114.4  367.54  6470.8  367.83  6932.0  369.20  6998.4  370.04  7159.7  377.62
#Mann=12,-1,0
  4404.9    0.05       0  4520.5     0.1       0  4749.1    0.05       0
  4905.8    0.16       0  4973.5    0.07       0  4979.5    0.16       0
  5459.0    0.12       0  5566.8    0.16       0  5635.6    0.12       0
  6114.4    0.16       0  6470.8    0.05       0  6932.0    0.16       0
Bank Sta=4973.5,4979.5
Exp/Cntr=0.3,0.1

Chan Stop Cuts=-1