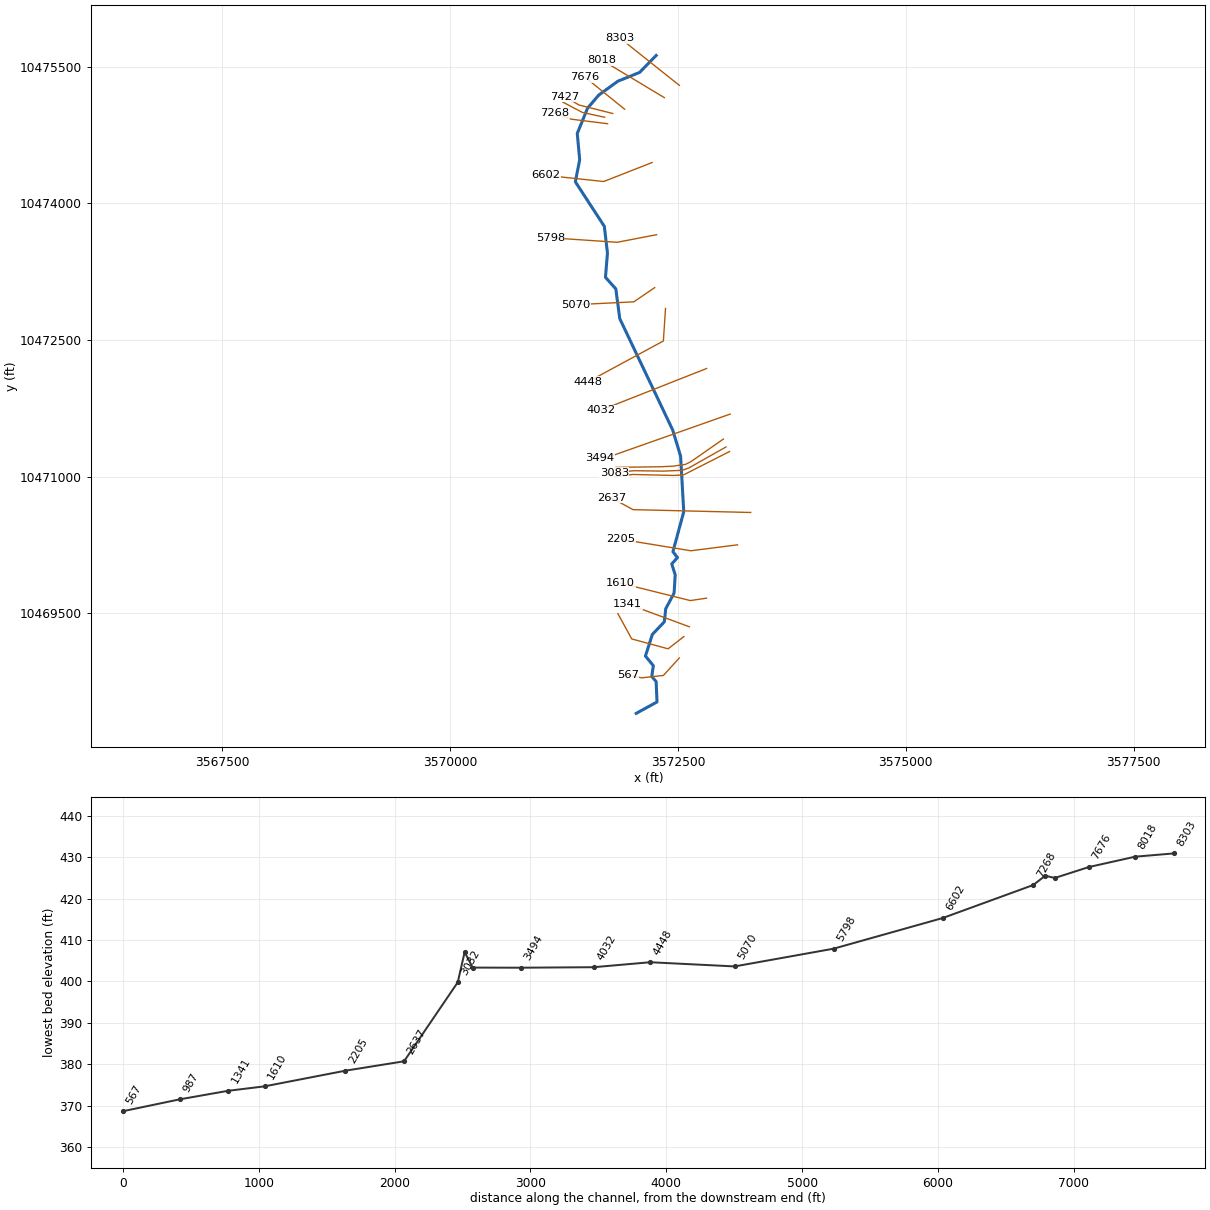
--- UNT0191 IN SAND CR.prj (project) ---

Proj Title=UNT0191 IN SAND CR Base Level Engineering
Current Plan=p01
Default Exp/Contr=0.3,0.1
English Units
Geom File=g01
Flow File=f01
Plan File=p01
Y Axis Title=Elevation
X Axis Title(PF)=Main Channel Distance
X Axis Title(XS)=Station
BEGIN DESCRIPTION:
UNT0191 IN SAND CR
END DESCRIPTION:
DSS Export Rating Curves= 0
DSS Export Rating Curve Sorted= 0
DSS Export Volume Flow Curves= 0
DXF OffsetX= 0
DXF OffsetY= 0
DXF ScaleX= 1
DXF ScaleY= 10

--- UNT0191 IN SAND CR.p01 (plan) ---

Plan Title=Multiple Run
Short Identifier=Multiple
Geom File=g01
Flow File=f01
Subcritical Flow
K Sum by GR= 0
Std Step Tol= 0.01
Critical Tol= 0.01
Num of Std Step Trials= 20
Max Error Tol= 0.3
Flow Tol Ratio= 0.001
Split Flow NTrial= 30
Split Flow Tol= 0.02
Split Flow Ratio= 0.02
Log Output Level= 0
Friction Slope Method= 1
Unsteady Friction Slope Method= 2
Unsteady Bridges Friction Slope Method= 1
Parabolic Critical Depth
Global Vel Dist=  1 , 1 , 1
Global Log Level= 0
CheckData=True
Encroach Param= -1, 0, 0, 0
BEGIN DESCRIPTION:
Multiple Run
END DESCRIPTION:

--- UNT0191 IN SAND CR.f01 (steady flow) ---

Flow Title=Multiple
Number of Profiles=7
Profile Names=10-year,25-year,50-year,1pct_min,100-year,1pct_plu,500-year
River Rch & RM= UNT0191 IN SAND ,Reach-1,8303
    1087    1515    1873    1690    2286    3092    3397
River Rch & RM= UNT0191 IN SAND ,Reach-1,7676
    1524    2160    2700    2462    3330    4503    5051
Boundary for River Rch & Prof#=UNT0191 IN SAND ,Reach-1,1
Up Type=0
Dn Type=3
Dn Slope=0.005
Boundary for River Rch & Prof#=UNT0191 IN SAND ,Reach-1,2
Up Type=0
Dn Type=3
Dn Slope=0.005
Boundary for River Rch & Prof#=UNT0191 IN SAND ,Reach-1,3
Up Type=0
Dn Type=3
Dn Slope=0.005
Boundary for River Rch & Prof#=UNT0191 IN SAND ,Reach-1,4
Up Type=0
Dn Type=3
Dn Slope=0.005
Boundary for River Rch & Prof#=UNT0191 IN SAND ,Reach-1,5
Up Type=0
Dn Type=3
Dn Slope=0.005
Boundary for River Rch & Prof#=UNT0191 IN SAND ,Reach-1,6
Up Type=0
Dn Type=3
Dn Slope=0.005
Boundary for River Rch & Prof#=UNT0191 IN SAND ,Reach-1,7
Up Type=0
Dn Type=3
Dn Slope=0.005

--- UNT0191 IN SAND CR.g01 (geometry) ---

Geom Title=Existing Conditions
Program Version=4.10

River Reach=UNT0191 IN SAND ,Reach-1
Reach XY= 30
      3572260.71     10475622.24      3572078.93     10475435.78
      3571839.07      10475338.6      3571629.46     10475185.91
      3571507.52     10475042.68      3571394.86      10474766.1
      3571421.38     10474476.84       3571373.7     10474235.73
      3571691.69     10473746.89      3571726.33      10473451.7
      3571704.32      10473187.4      3571817.85     10473060.25
      3571861.25     10472733.65      3572442.11     10471511.64
      3572528.82     10471224.91      3572563.54     10470614.78
      3572444.68     10470176.06      3572494.69      10470111.7
      3572431.91     10470041.68      3572469.46     10469921.63
      3572457.75     10469722.35      3572365.95     10469550.06
       3572350.4      10469406.2      3572218.67     10469267.75
      3572143.07      10469030.5      3572229.38     10468925.95
      3572212.46     10468806.78      3572260.19     10468751.04
      3572270.17     10468527.02      3572042.11     10468401.64

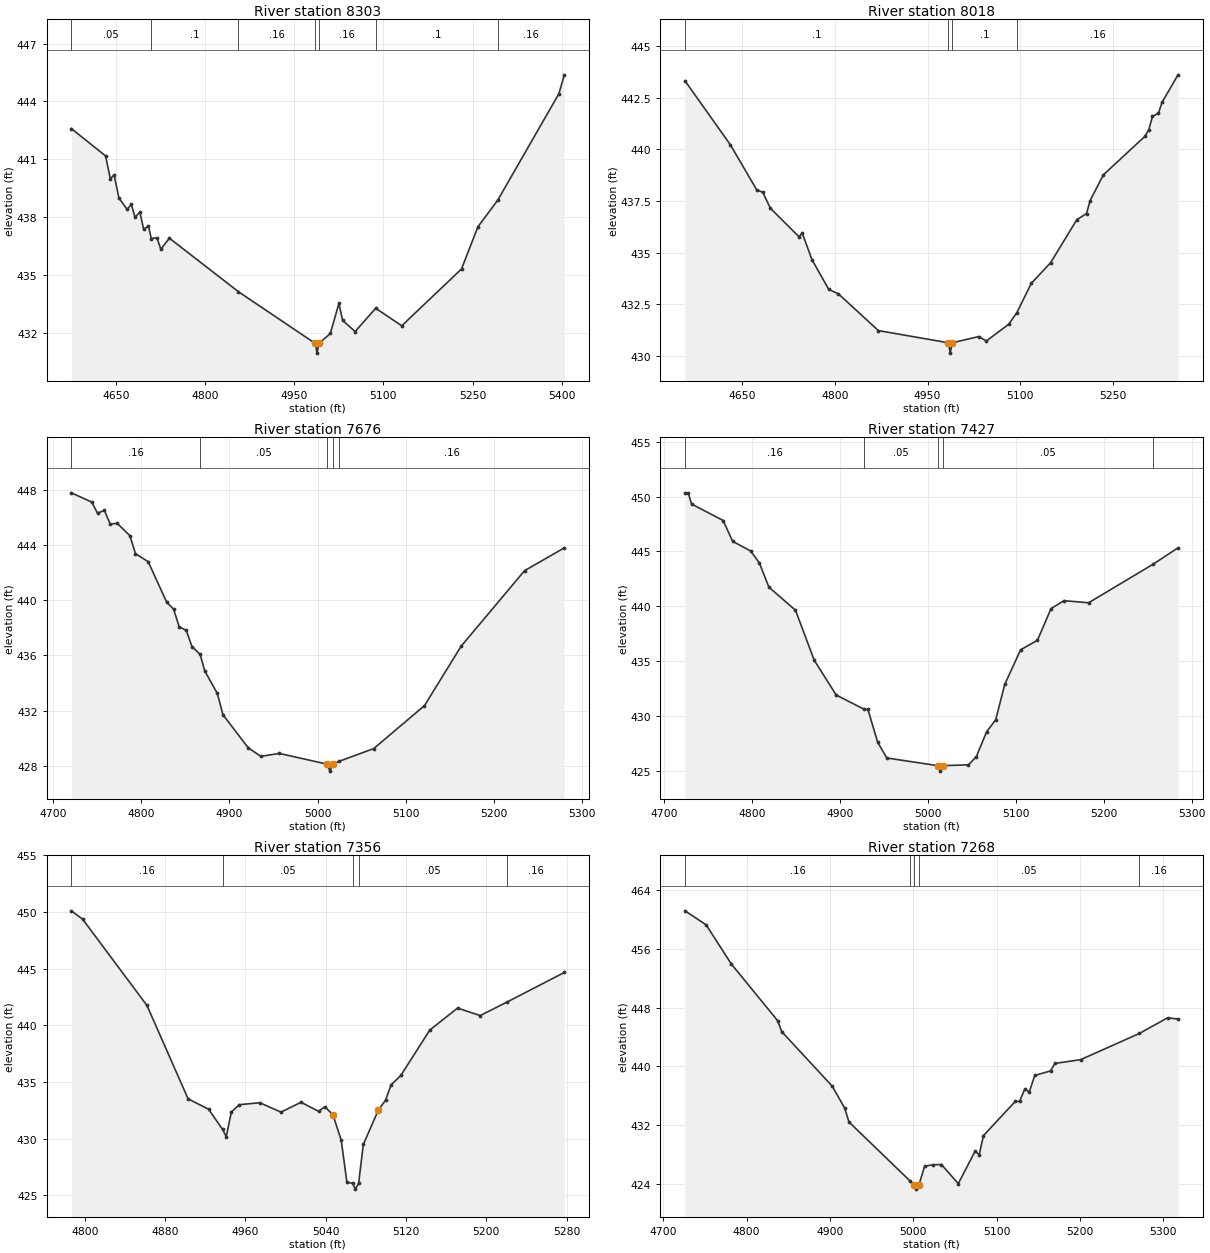
Type RM Length L Ch R = 1 ,8303    ,285,285,285
BEGIN DESCRIPTION:
UNT0191 IN SAND CR 17.2
END DESCRIPTION:
XS GIS Cut Line= 2
      3572515.55     10475293.48      3571866.86     10475809.83
#Sta/Elev= 30
  4575.3  442.59  4632.9  441.17  4640.9  439.98  4647.3  440.18  4655.3  438.99
  4669.2  438.39  4676.1  438.66  4682.5  437.98  4690.6  438.26    4697  437.35
    4705  437.54  4709.7  436.88  4719.4  436.92  4725.8  436.32  4740.2   436.9
  4856.3  434.12  4985.7  431.43  4988.5  430.93  4991.7  431.43  5010.9  431.95
  5025.3  433.51  5031.7  432.63  5052.6  432.05  5087.2  433.26    5131  432.35
  5231.5   435.3  5259.1  437.49  5292.4  438.87  5395.3   444.4  5404.4  445.38
#Mann= 7 ,-1 , 0
  4575.3     .05       0  4709.7      .1       0  4856.3     .16       0
  4985.7     .07       0  4991.7     .16       0  5087.2      .1       0
  5292.4     .16       0
Bank Sta=4985.7,4991.7
XS Rating Curve= 0 ,0
Exp/Cntr=0.3,0.1

Type RM Length L Ch R = 1 ,8018    ,342,342,342
BEGIN DESCRIPTION:
UNT0191 IN SAND CR 17.1
END DESCRIPTION:
XS GIS Cut Line= 2
      3572350.65     10475158.91      3571665.98     10475570.58
#Sta/Elev= 30
  4556.9  443.31  4630.6  440.21  4673.3  438.03    4683  437.92  4695.2  437.15
  4741.3  435.78  4747.1  435.93  4762.7  434.66  4789.9  433.22  4805.4  433.01
  4870.3  431.23  4983.9  430.64  4986.7  430.14  4989.9  430.64  5032.7  430.94
  5045.3  430.73  5081.3  431.53  5094.7   432.1  5118.2  433.52  5149.3  434.51
    5192   436.6  5207.6  436.89  5213.4  437.52  5234.8  438.76    5302  440.62
  5308.6  440.95  5314.4  441.59  5324.1  441.74    5330  442.27  5355.8   443.6
#Mann= 4 ,-1 , 0
  4556.9      .1       0  4983.9     .07       0  4989.9      .1       0
  5094.7     .16       0
Bank Sta=4983.9,4989.9
XS Rating Curve= 0 ,0
Exp/Cntr=0.3,0.1

Type RM Length L Ch R = 1 ,7676    ,249,249,249
BEGIN DESCRIPTION:
UNT0191 IN SAND CR 17.0
END DESCRIPTION:
XS GIS Cut Line= 2
      3571914.81     10475031.73      3571479.94     10475383.28
#Sta/Elev= 30
  4720.6  447.76  4743.8  447.09  4750.3  446.29  4758.2  446.49  4764.7  445.49
  4772.6  445.56    4787  444.66  4793.4  443.36  4807.8  442.78  4828.6  439.87
  4836.6  439.35    4843  438.07    4851  437.81  4857.4  436.64  4866.8  436.07
  4871.8   434.9  4886.2  433.25  4892.6  431.71  4921.3  429.31  4935.7   428.7
  4956.5  428.91  5011.1  428.13  5013.8  427.63  5017.1  428.13  5024.7  428.35
  5063.6  429.26  5121.2  432.37  5162.8  436.67  5234.7  442.13  5279.8  443.78
#Mann= 5 ,-1 , 0
  4720.6     .16       0  4866.8     .05       0  5011.1    .033       0
  5017.1     .05       0  5024.7     .16       0
Bank Sta=5011.1,5017.1
XS Rating Curve= 0 ,0
Exp/Cntr=0.3,0.1

Type RM Length L Ch R = 1 ,7427    ,71,71,71
BEGIN DESCRIPTION:
UNT0191 IN SAND CR 16.1
END DESCRIPTION:
XS GIS Cut Line= 3
      3571784.58     10474984.87      3571412.19     10475078.62
      3571261.17     10475169.75
#Sta/Elev= 30
  4724.1  450.34  4727.7  450.34  4731.6  449.32  4767.5  447.82  4778.2  445.93
  4798.8  445.04  4808.6  443.96  4819.5  441.75  4849.7  439.65    4871   435.1
    4896  431.93    4928  430.62    4932  430.62  4943.2  427.62  4953.5   426.2
  5011.2   425.5  5013.9     425  5017.2   425.5  5046.3  425.57  5055.3  426.32
  5066.9  428.57  5077.3  429.68  5087.6   432.9  5105.6  436.05  5124.7  436.91
  5140.2   439.8  5154.9  440.52  5182.9  440.33    5256  443.83  5284.5  445.33
#Mann= 5 ,-1 , 0
  4724.1     .16       0    4928     .05       0  5011.2    .033       0
  5017.2     .05       0    5256     .16       0
Bank Sta=5011.2,5017.2
XS Rating Curve= 0 ,0
Exp/Cntr=0.3,0.1

Type RM Length L Ch R = 1 ,7356    ,88,88,88
BEGIN DESCRIPTION:
UNT0191 IN SAND CR 16.0
END DESCRIPTION:
XS GIS Cut Line= 3
      3571695.88     10474943.84      3571452.77     10474995.93
      3571237.93     10475108.78
#Sta/Elev= 30
  4786.5  450.09  4797.7  449.36  4861.9  441.74  4902.9   433.5  4923.3  432.59
  4937.2  430.81  4940.9  430.17    4946  432.35    4954  432.99  4974.4  433.16
  4995.4  432.33  5015.4   433.2  5032.9  432.41  5039.1  432.81  5047.2   432.1
  5055.5  429.85  5061.1  426.16  5066.8  426.04  5069.5  425.54  5072.8  426.04
  5077.5  429.48  5092.4   432.5  5099.6  433.38  5105.2  434.74  5114.9  435.57
  5143.7  439.57  5171.4  441.51    5194  440.85  5220.8  442.05  5277.8  444.65
#Mann= 5 ,-1 , 0
  4786.5     .16       0  4937.2     .05       0  5066.8    .035       0
  5072.8     .05       0  5220.8     .16       0
Bank Sta=5047.2,5092.4
XS Rating Curve= 0 ,0
Exp/Cntr=0.3,0.1

Type RM Length L Ch R = 1 ,7268    ,666,666,666
BEGIN DESCRIPTION:
UNT0191 IN SAND CR 16.2
END DESCRIPTION:
XS GIS Cut Line= 3
      3571727.33     10474872.88      3571331.46     10474922.37
      3571150.32     10474987.06
#Sta/Elev= 30
  4726.2   461.2  4751.5   459.3  4781.9  453.94  4837.2  446.26  4842.3  444.74
  4902.8  437.32  4917.8  434.32  4922.9  432.44    4996  424.43  5000.6   423.8
  5003.3   423.3  5006.6   423.8  5013.6  426.42  5023.7  426.62  5033.8  426.65
    5054  424.05    5074  428.44  5079.1  428.01  5084.2  430.59  5122.3  435.24
  5127.5  435.24  5133.8  436.96  5139.1  436.52  5145.7  438.78  5164.6   439.4
  5169.9  440.42  5200.7  440.93  5271.2   444.5    5305  446.63  5317.5  446.46
#Mann= 5 ,-1 , 0
  4726.2     .16       0    4996     .05       0  5000.6    .035       0
  5006.6     .05       0  5271.2     .16       0
Bank Sta=5000.6,5006.6
XS Rating Curve= 0 ,0
Exp/Cntr=0.3,0.1

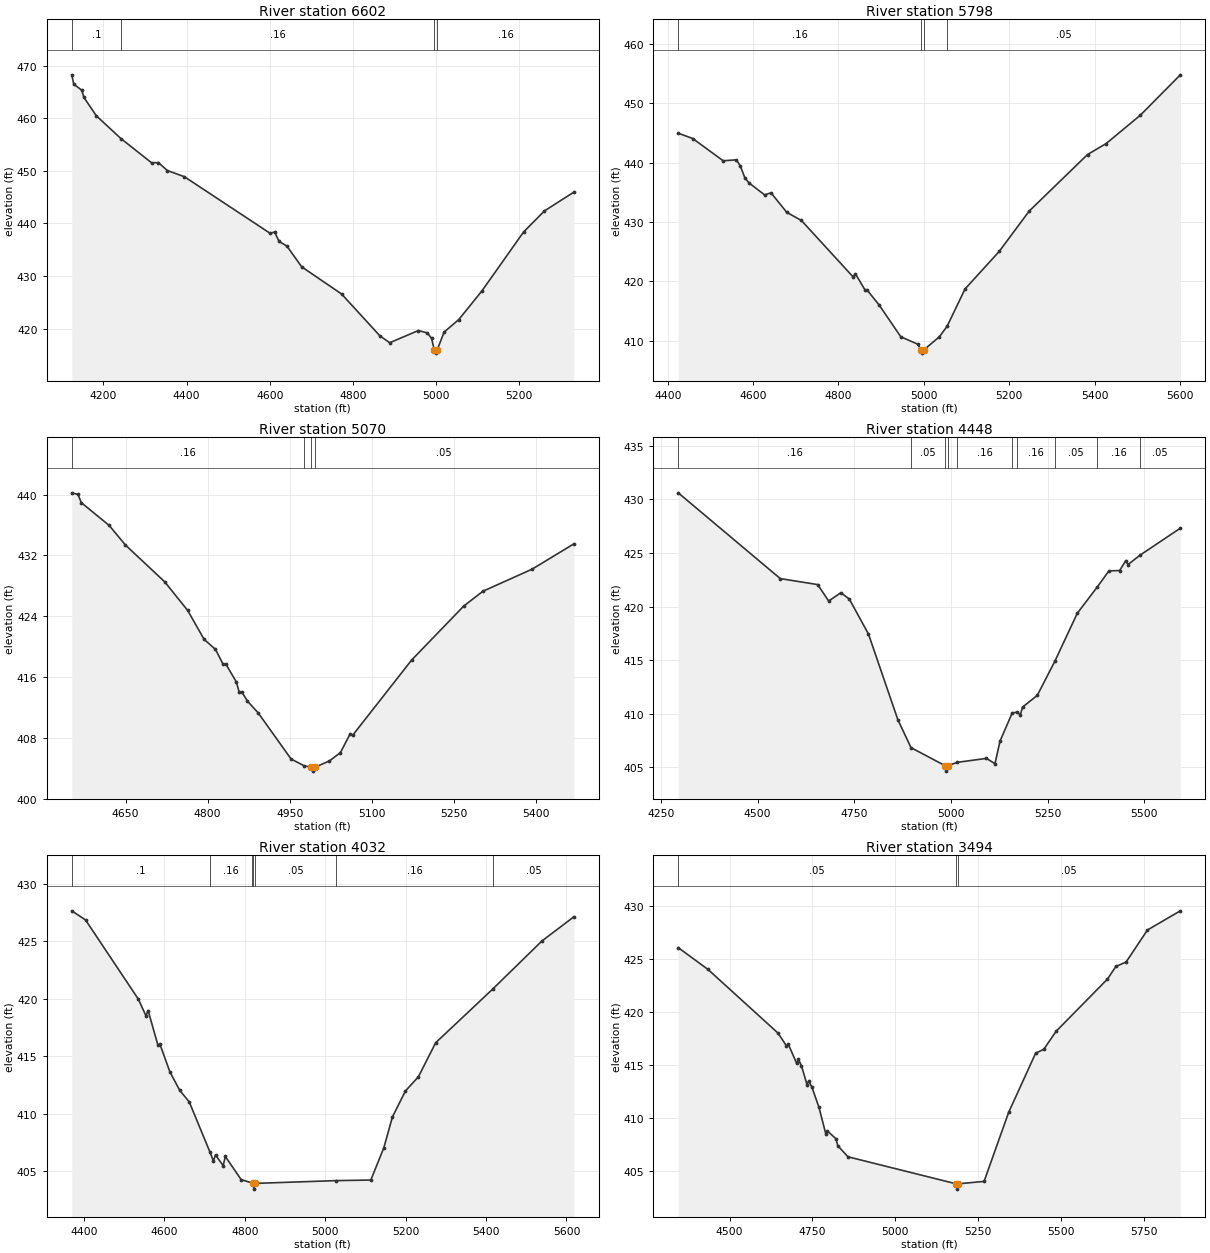
Type RM Length L Ch R = 1 ,6602    ,804,804,804
BEGIN DESCRIPTION:
UNT0191 IN SAND CR 15.0
END DESCRIPTION:
XS GIS Cut Line= 3
      3572216.04     10474446.69      3571684.79     10474238.36
      3571051.94     10474306.07
#Sta/Elev= 30
  4123.9  468.25  4128.8  466.46  4147.8  465.34  4153.2  463.94    4183  460.46
  4242.1  456.13  4315.9  451.52  4332.2  451.56  4353.7  450.05  4394.6  448.88
  4600.7  438.12  4611.5  438.36  4622.3  436.58  4641.4  435.66  4676.6  431.75
  4772.5  426.58  4864.8  418.61  4888.3  417.31  4957.1  419.62  4978.8  419.18
  4988.9  418.14  4995.9  415.83  4998.7  415.33  5001.9  415.83  5019.1  419.33
  5054.3  421.71  5109.6  427.12  5210.1  438.36  5260.4  442.38    5331  445.94
#Mann= 4 ,-1 , 0
  4123.9      .1       0  4242.1     .16       0  4995.9     .07       0
  5001.9     .16       0
Bank Sta=4995.9,5001.9
XS Rating Curve= 0 ,0
Exp/Cntr=0.3,0.1

Type RM Length L Ch R = 1 ,5798    ,728,728,728
BEGIN DESCRIPTION:
UNT0191 IN SAND CR 13.0
END DESCRIPTION:
XS GIS Cut Line= 3
      3572265.51     10473655.02      3571833.23     10473571.69
      3571098.83     10473621.17
#Sta/Elev= 30
  4424.7  444.94  4458.7  444.05    4530   440.3  4560.6  440.46  4570.1  439.45
  4580.9  437.41  4591.1  436.54  4627.1  434.56    4642  434.91    4679  431.62
  4713.3  430.25  4834.6  420.74  4839.7  421.29    4863  418.47    4868  418.47
  4896.1  415.95  4946.2  410.67  4986.3  409.41  4993.4  408.42  4996.1  407.92
  4999.4  408.42  5036.4  410.67  5054.6  412.43  5096.6  418.72  5176.8  425.05
  5246.9  431.83  5383.6  441.35  5427.3   443.2  5507.5  447.98    5601  454.77
#Mann= 4 ,-1 , 0
  4424.7     .16       0  4993.4     .07       0  4999.4     .16       0
  5054.6     .05       0
Bank Sta=4993.4,4999.4
XS Rating Curve= 0 ,0
Exp/Cntr=0.3,0.1

Type RM Length L Ch R = 1 ,5070    ,622,622,622
BEGIN DESCRIPTION:
UNT0191 IN SAND CR 11.0
END DESCRIPTION:
XS GIS Cut Line= 3
       3572244.7      10473074.3      3572015.52     10472918.04
      3571375.96     10472886.85
#Sta/Elev= 30
  4551.7  440.22  4563.1  440.01  4569.1  438.93    4620  435.94  4649.8  433.36
  4721.6  428.52  4763.6  424.76  4793.5  420.97  4814.4  419.64  4828.1  417.72
  4833.3  417.72  4852.5  415.36  4857.7  414.03  4862.7  414.04  4872.5  412.87
  4892.6  411.28  4952.6  405.23  4976.6  404.34  4989.7  404.14  4992.4  403.64
  4995.7  404.14  5022.7  404.98  5042.7  406.07  5060.4  408.52  5065.4  408.38
  5172.9  418.24  5268.2  425.34  5303.1  427.28  5393.2  430.19  5469.4  433.51
#Mann= 4 ,-1 , 0
  4551.7     .16       0  4976.6     .05       0  4989.7    .035       0
  4995.7     .05       0
Bank Sta=4989.7,4995.7
XS Rating Curve= 0 ,0
Exp/Cntr=0.3,0.1

Type RM Length L Ch R = 1 ,4448    ,416,416,416
BEGIN DESCRIPTION:
UNT0191 IN SAND CR 9.0
END DESCRIPTION:
XS GIS Cut Line= 3
      3572363.37      10472845.1      3572339.93     10472488.28
      3571511.79     10472040.36
#Sta/Elev= 30
  4294.5  430.61  4558.5  422.61  4655.4  422.05  4683.7  420.52  4715.4  421.29
  4737.2   420.7  4786.7  417.44  4862.8  409.44  4896.8  406.84  4985.4  405.15
  4988.2  404.65  4991.4  405.15  5016.7  405.47  5092.1  405.84    5114  405.34
  5127.1  407.45  5158.7  410.08  5172.1  410.15  5179.6  409.88  5185.3  410.62
  5223.4  411.71  5268.7  414.88  5327.1  419.38  5378.8  421.83  5408.9  423.33
  5436.5  423.36  5452.7  424.29  5458.4  423.92  5488.8  424.78  5593.6  427.31
#Mann= 10 ,-1 , 0
  4294.5     .16       0  4896.8     .05       0  4985.4    .033       0
  4991.4     .05       0  5016.7     .16       0  5158.7     .05       0
  5172.1     .16       0  5268.7     .05       0  5378.8     .16       0
  5488.8     .05       0
Bank Sta=4985.4,4991.4
XS Rating Curve= 0 ,0
Exp/Cntr=0.3,0.1

Type RM Length L Ch R = 1 ,4032    ,538,538,538
BEGIN DESCRIPTION:
UNT0191 IN SAND CR 9.1
END DESCRIPTION:
XS GIS Cut Line= 2
      3572813.91     10472186.21      3571652.47     10471727.89
#Sta/Elev= 30
  4369.8  427.65    4404  426.86  4535.2  419.98  4554.2  418.53  4559.6  418.98
    4584  415.98  4589.3  416.03  4613.7  413.66  4638.1  412.05    4662  411.03
  4712.9  406.72    4722   405.9  4727.3  406.42  4746.3  405.49  4751.7  406.29
    4791  404.28  4817.5  403.99  4820.3  403.95    4823  403.45  4826.3  403.95
  5026.8  404.19  5113.5  404.24  5145.8  407.04  5167.3  409.73  5199.5  411.98
  5231.8  413.22  5274.8  416.18    5417  420.86  5539.1  425.03  5618.4  427.13
#Mann= 7 ,-1 , 0
  4369.8      .1       0  4712.9     .16       0  4817.5     .05       0
  4820.3    .033       0  4826.3     .05       0  5026.8     .16       0
    5417     .05       0
Bank Sta=4820.3,4826.3
XS Rating Curve= 0 ,0
Exp/Cntr=0.3,0.1

Type RM Length L Ch R = 1 ,3494    ,352,352,352
BEGIN DESCRIPTION:
UNT0191 IN SAND CR 7.0
END DESCRIPTION:
XS GIS Cut Line= 3
      3573072.78     10471686.26      3571736.88     10471214.92
      3571637.93     10471209.71
#Sta/Elev= 30
  4345.1  426.11    4435  424.05  4646.3  418.05  4671.9  416.84  4677.2  417.01
  4702.8  415.18  4708.1  415.57    4717  414.98  4733.8  413.19  4739.1  413.55
  4748.8  412.93    4770  411.04  4790.3  408.57  4795.6  408.81  4821.3  408.08
  4826.6  407.43  4857.5  406.38  5184.2  403.83  5186.9  403.33  5190.2  403.83
  5268.4  404.06  5342.6  410.57    5424  416.15  5448.7  416.52  5485.9  418.22
  5640.6  423.13  5666.2  424.33  5697.1  424.75  5761.6  427.77  5860.8  429.58
#Mann= 3 ,-1 , 0
  4345.1     .05       0  5184.2    .033       0  5190.2     .05       0
Bank Sta=5184.2,5190.2
XS Rating Curve= 0 ,0
Exp/Cntr=0.3,0.1

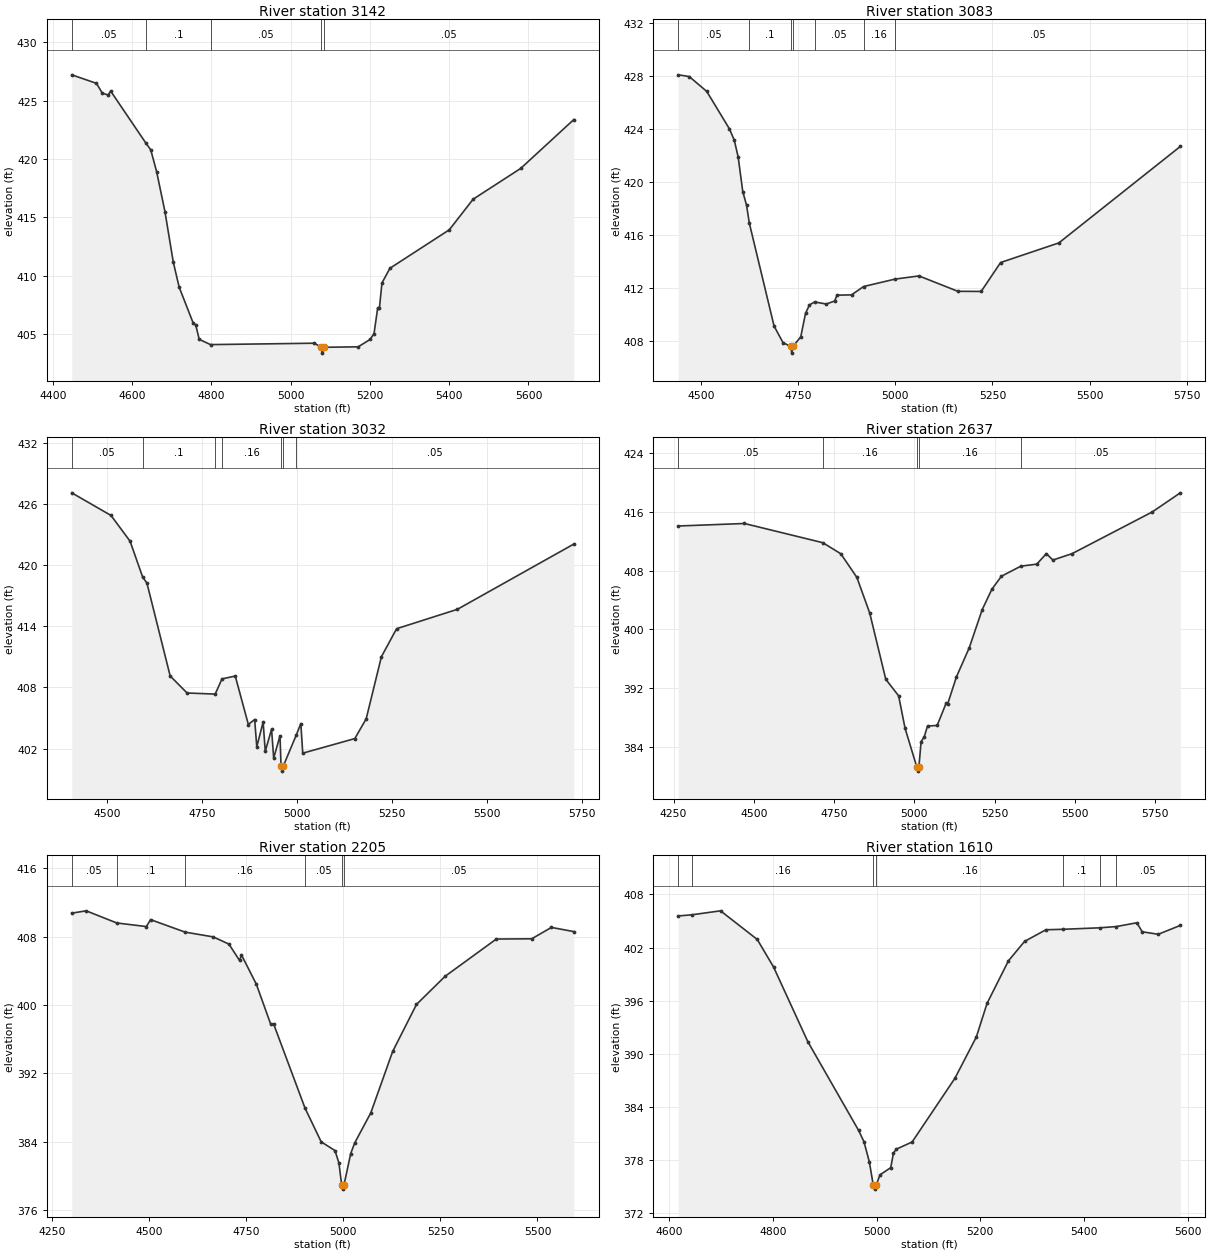
Type RM Length L Ch R = 1 ,3142    ,59,59,59
BEGIN DESCRIPTION:
UNT0191 IN SAND CR 6.1
END DESCRIPTION:
XS GIS Cut Line= 6
      3572998.57     10471411.97      3572642.66     10471164.57
       3572581.9     10471134.19      3572445.18     10471114.66
      3572308.46     10471108.15      3571817.97     10471101.64
#Sta/Elev= 30
  4447.6  427.21  4509.9  426.48  4524.7  425.64  4539.6  425.48  4545.7  425.82
  4635.2  421.33  4646.9  420.78  4661.8   418.9  4682.7  415.49  4703.7  411.17
  4718.5  409.02  4754.3  405.91  4760.4  405.77  4769.2  404.54  4797.7  404.09
  5059.9  404.21  5077.1  403.86  5079.8  403.36  5083.1  403.86  5170.3   403.9
  5200.3  404.53  5210.3  405.03  5219.6  407.25    5224  407.25  5230.3  409.37
  5250.3  410.63  5400.3  413.93  5460.3  416.55  5580.4  419.19  5714.5  423.38
#Mann= 5 ,-1 , 0
  4447.6     .05       0  4635.2      .1       0  4797.7     .05       0
  5077.1    .033       0  5083.1     .05       0
Bank Sta=5077.1,5083.1
XS Rating Curve= 0 ,0
Exp/Cntr=0.3,0.1

Type RM Length L Ch R = 1 ,3083    ,51,51,51
BEGIN DESCRIPTION:
UNT0191 IN SAND CR 6.0
END DESCRIPTION:
XS GIS Cut Line= 6
      3573026.78     10471325.16       3572618.2     10471094.57
      3572545.78     10471069.05      3572341.01      10471060.4
      3572017.66     10471064.75      3571800.62     10471043.04
#Sta/Elev= 30
  4441.2  428.08  4469.5  427.95  4514.6  426.83  4572.9  424.01  4585.4  423.16
  4595.5  421.88  4607.3  419.28  4617.2  418.23  4624.1  416.91  4687.9  409.14
  4710.7   407.9  4730.6   407.6  4733.4   407.1  4736.6   407.6  4756.6  408.33
  4768.8  410.09  4778.9  410.73  4792.2  410.96  4822.3   410.8  4843.9  411.03
  4849.7  411.47  4887.2  411.49  4918.3  412.12  4999.1  412.68  5060.9  412.92
    5161  411.76    5221  411.75    5271  413.93    5421  415.41  5733.6  422.68
#Mann= 7 ,-1 , 0
  4441.2     .05       0  4624.1      .1       0  4730.6     .03       0
  4736.6      .1       0  4792.2     .05       0  4918.3     .16       0
  4999.1     .05       0
Bank Sta=4730.6,4736.6
XS Rating Curve= 0 ,0
Exp/Cntr=0.3,0.1

Type RM Length L Ch R = 1 ,3032    ,395,395,395
BEGIN DESCRIPTION:
UNT0191 IN SAND CR 6.2
END DESCRIPTION:
XS GIS Cut Line= 5
      3573065.84     10471275.25      3572562.37     10471019.17
      3572456.03     10471012.66      3572002.47     10471023.51
      3571807.18     10470997.47
#Sta/Elev= 30
    4407  427.08  4510.4  424.86  4560.5  422.34  4593.4  418.85    4605  418.22
  4666.1  409.13  4710.6  407.46  4784.7  407.35  4802.5  408.84  4837.5  409.12
    4872  404.37  4888.6  404.86  4894.2  402.19  4910.9  404.61  4916.5  401.74
  4933.1  403.91  4938.7  401.08  4955.4  403.27    4958   400.3  4960.7   399.8
    4964   400.3  4998.4  403.36  5010.2  404.46  5015.2  401.56  5152.3  402.99
  5182.3  404.93  5222.4  411.02  5262.4  413.76  5422.4  415.66  5729.1  422.06
#Mann= 7 ,-1 , 0
    4407     .05       0  4593.4      .1       0  4784.7     .05       0
  4802.5     .16       0    4958     .03       0    4964     .16       0
  4998.4     .05       0
Bank Sta=4958,4964
XS Rating Curve= 0 ,0
Exp/Cntr=0.3,0.1

Type RM Length L Ch R = 1 ,2637    ,432,432,432
BEGIN DESCRIPTION:
UNT0191 IN SAND CR 5.0
END DESCRIPTION:
XS GIS Cut Line= 3
      3573298.09     10470606.41      3572006.38     10470637.66
      3571768.09     10470767.17
#Sta/Elev= 30
  4264.6  414.06  4470.6   414.4  4714.7  411.79  4770.7  410.29  4820.7  407.08
  4860.8  402.23  4910.8  393.22  4950.8  390.97  4970.8  386.57  5007.8  381.23
  5010.6  380.73  5013.8  381.23  5020.8  384.73  5030.8  385.43  5040.8  386.86
  5070.8  386.94  5098.5  389.94  5103.5  389.86  5130.8  393.54  5170.8  397.51
  5210.9  402.67  5240.9  405.44  5270.9  407.23  5331.4   408.6  5380.9  408.87
  5410.9  410.31  5430.9  409.43  5490.9   410.3  5740.5  415.97  5827.9  418.57
#Mann= 5 ,-1 , 0
  4264.6     .05       0  4714.7     .16       0  5007.8     .07       0
  5013.8     .16       0  5331.4     .05       0
Bank Sta=5007.8,5013.8
XS Rating Curve= 0 ,0
Exp/Cntr=0.3,0.1

Type RM Length L Ch R = 1 ,2205    ,595,595,595
BEGIN DESCRIPTION:
UNT0191 IN SAND CR 4.0
END DESCRIPTION:
XS GIS Cut Line= 3
      3573153.52     10470251.37      3572641.39     10470186.27
      3571875.16     10470311.81
#Sta/Elev= 30
  4300.9  410.74    4338  411.01  4416.7  409.59  4492.9  409.17  4503.9  409.98
  4592.7  408.52  4665.2  407.96  4705.5  407.12  4732.8  405.21  4737.9  405.85
  4776.1  402.43  4812.8  397.79  4820.5  397.79  4901.5  387.93  4943.1  383.99
  4978.6  382.97  4988.7  381.53  4995.8  378.96  4998.6  378.46  5001.8  378.96
  5019.1  382.62  5029.2  383.85  5070.8  387.38  5127.1  394.56  5188.4  400.06
  5262.3  403.36    5394  407.71  5485.2  407.74  5535.9  409.07  5593.6  408.58
#Mann= 6 ,-1 , 0
  4300.9     .05       0  4416.7      .1       0  4592.7     .16       0
  4901.5     .05       0  4995.8    .035       0  5001.8     .05       0
Bank Sta=4995.8,5001.8
XS Rating Curve= 0 ,0
Exp/Cntr=0.3,0.1

Type RM Length L Ch R = 1 ,1610    ,269,269,269
BEGIN DESCRIPTION:
UNT0191 IN SAND CR 3.1
END DESCRIPTION:
XS GIS Cut Line= 3
      3572812.77     10469665.73      3572634.81     10469639.68
      3571870.88     10469830.67
#Sta/Elev= 30
    4618  405.57  4644.1   405.7  4699.5  406.15  4770.3  402.91  4801.8  399.78
  4867.7  391.35  4965.6  381.31  4975.9  380.03  4986.2  377.76  4993.6  375.18
  4996.3  374.68  4999.6  375.18  5006.8   376.3  5027.4  377.11  5032.6  378.74
  5037.8  379.19  5068.6  380.01  5151.1  387.22  5192.3  391.88    5213  395.69
  5254.2   400.5  5285.2  402.69  5326.4  404.01  5358.9  404.06  5430.1  404.23
  5461.9  404.37  5501.6   404.8  5511.9  403.78  5542.8   403.5  5585.3   404.5
#Mann= 7 ,-1 , 0
    4618     .05       0  4644.1     .16       0  4993.6     .07       0
  4999.6     .16       0  5358.9      .1       0  5430.1     .16       0
  5461.9     .05       0
Bank Sta=4993.6,4999.6
XS Rating Curve= 0 ,0
Exp/Cntr=0.3,0.1

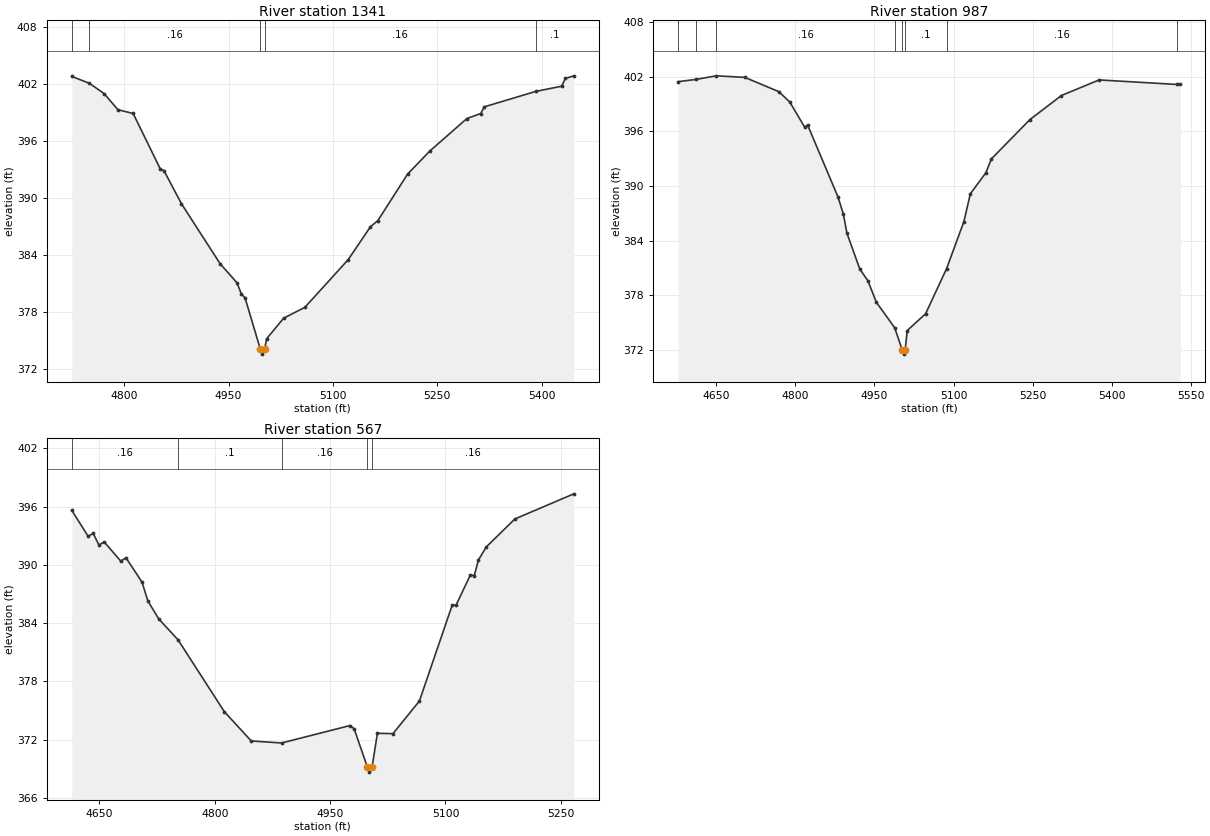
Type RM Length L Ch R = 1 ,1341    ,354,354,354
BEGIN DESCRIPTION:
UNT0191 IN SAND CR 3.0
END DESCRIPTION:
XS GIS Cut Line= 2
       3572624.9     10469352.07      3571947.83     10469601.63
#Sta/Elev= 30
  4724.6  402.81    4750  402.08  4771.1     401  4790.9  399.31  4812.8  398.91
  4851.8  393.08  4857.1   392.9  4882.3  389.41  4937.8  383.11  4962.1   381.1
  4968.3  379.93  4973.6  379.53  4995.7   374.1  4998.5   373.6  5001.7   374.1
  5004.7  375.22  5029.1  377.38  5059.6  378.52  5121.9  383.54  5153.9     387
  5164.5  387.64  5207.2  392.53  5239.2  394.96  5292.5  398.38  5312.3   398.9
  5317.6  399.61  5391.4  401.23  5428.7  401.78    5434  402.59  5446.2  402.87
#Mann= 5 ,-1 , 0
  4724.6     .05       0    4750     .16       0  4995.7     .07       0
  5001.7     .16       0  5391.4      .1       0
Bank Sta=4995.7,5001.7
XS Rating Curve= 0 ,0
Exp/Cntr=0.3,0.1

Type RM Length L Ch R = 1 ,987     ,420,420,420
BEGIN DESCRIPTION:
UNT0191 IN SAND CR 2.0
END DESCRIPTION:
XS GIS Cut Line= 4
      3572565.35     10469244.71      3572391.75     10469110.17
      3571992.45     10469218.68      3571840.55     10469496.44
#Sta/Elev= 30
    4579  401.46  4611.8   401.7  4650.9   402.1  4704.9  401.93  4769.1  400.37
    4790  399.23  4818.6  396.43  4823.7  396.71  4881.2  388.82  4891.5  386.91
  4898.1  384.84  4922.6  380.88  4937.9   379.6  4953.7  377.26  4988.6  374.44
  5002.5  372.05  5005.3  371.55  5008.5  372.05  5012.3  374.14    5047  375.98
  5086.8  380.94  5119.5   386.1  5131.7  389.15    5161  391.45  5171.5  392.98
  5244.3  397.29  5304.1  399.94  5375.4  401.65  5523.5  401.15    5529  401.15
#Mann= 8 ,-1 , 0
    4579     .16       0  4611.8     .05       0  4650.9     .16       0
  4988.6      .1       0  5002.5     .07       0  5008.5      .1       0
  5086.8     .16       0  5523.5      .1       0
Bank Sta=5002.5,5008.5
XS Rating Curve= 0 ,0
Exp/Cntr=0.3,0.1

Type RM Length L Ch R = 1 ,567     ,0,0,0
BEGIN DESCRIPTION:
UNT0191 IN SAND CR 1.0
END DESCRIPTION:
XS GIS Cut Line= 4
       3572514.2     10469009.17      3572340.61     10468818.22
      3572104.07     10468791.64      3571950.02     10468820.38
#Sta/Elev= 30
  4614.1  395.62  4635.3  392.96    4642  393.24  4649.5  392.04  4656.2  392.38
  4677.8  390.39  4684.6  390.74  4705.5  388.22    4713   386.3  4727.2  384.44
  4752.3  382.29  4812.3  374.91  4847.4  371.88  4886.9  371.67  4976.1  373.47
  4981.3  373.12  4998.5  369.17  5001.2  368.67  5004.5  369.17  5011.5  372.67
  5031.7  372.63  5066.1  375.99  5108.7  385.85  5113.7  385.85  5132.5  388.99
  5137.5   388.9  5142.7  390.49  5152.9  391.84  5190.2  394.73  5266.9  397.32
#Mann= 5 ,-1 , 0
  4614.1     .16       0  4752.3      .1       0  4886.9     .16       0
  4998.5     .07       0  5004.5     .16       0
Bank Sta=4998.5,5004.5
XS Rating Curve= 0 ,0
Exp/Cntr=0.3,0.1

Chan Stop Cuts=-1
Use User Specified Reach Order=0
Composite Channel Slope=5