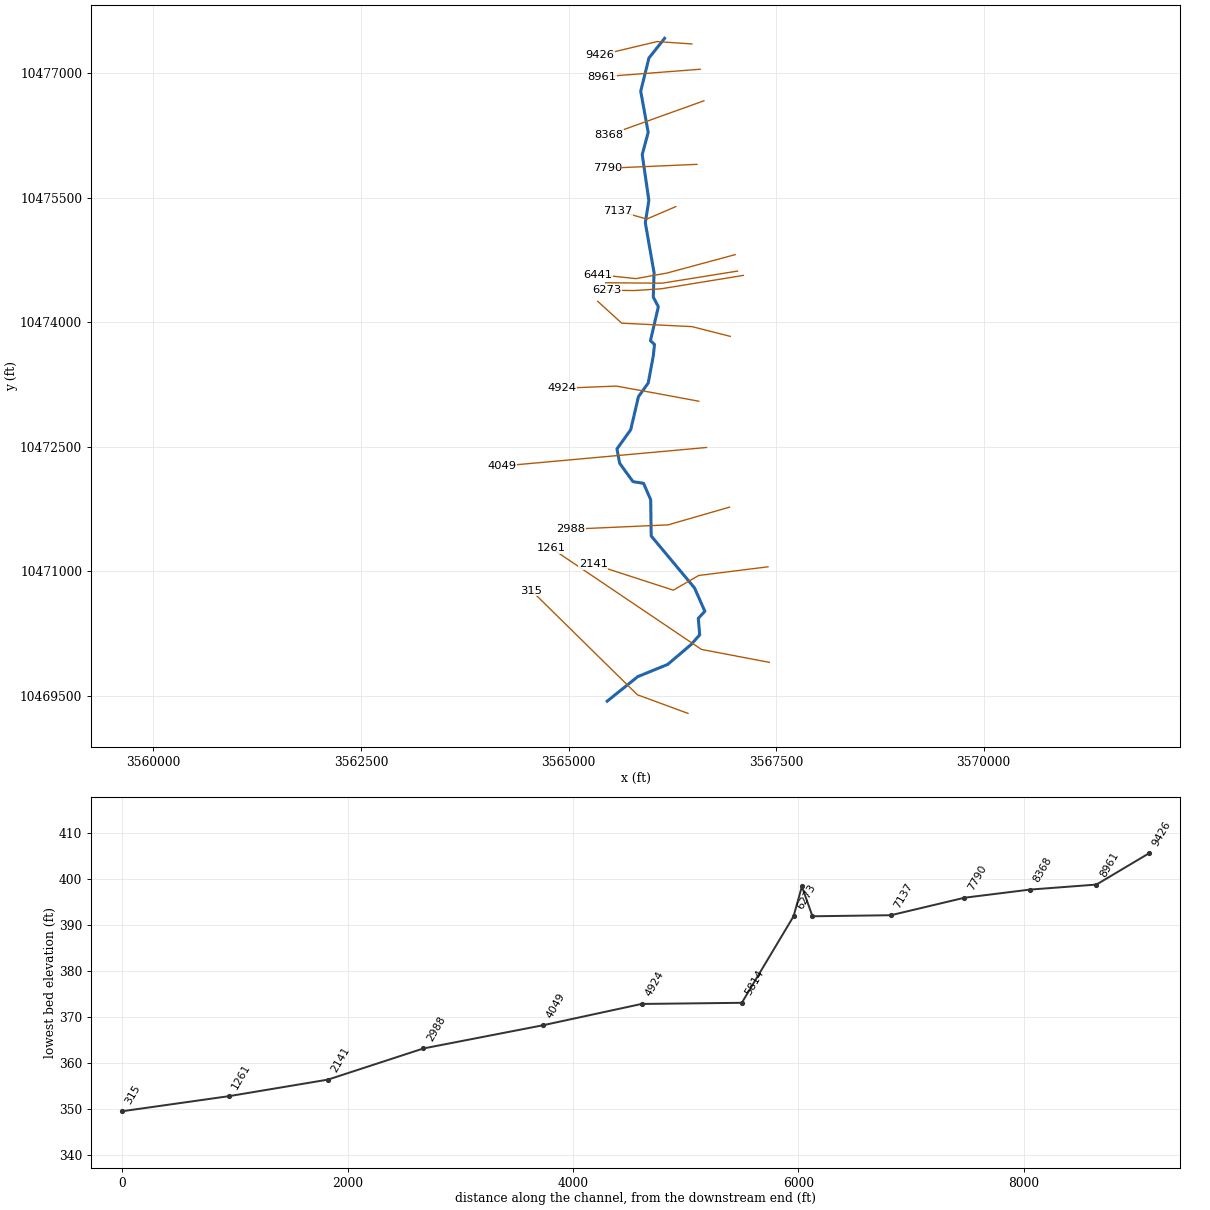
--- UNT0193 IN SAND CR.prj (project) ---

Proj Title=UNT0193 IN SAND CR Base Level Engineering
Current Plan=p01
Default Exp/Contr=0.3,0.1
English Units
Geom File=g01
Flow File=f01
Plan File=p01
BEGIN DESCRIPTION:
UNT0193 IN SAND CR
END DESCRIPTION:

--- UNT0193 IN SAND CR.p01 (plan) ---

Plan Title=Multiple Run
Short Identifier=Multiple
Geom File=g01
Flow File=f01
Subcritical Flow
K Sum by GR= 0
Std Step Tol= 0.01
Critical Tol= 0.01
Num of Std Step Trials= 20
Max Error Tol= 0.3
Flow Tol Ratio= 0.001
Split Flow NTrial= 30
Split Flow Tol= 0.02
Split Flow Ratio= 0.02
Log Output Level= 0
Friction Slope Method= 1
Unsteady Friction Slope Method= 2
Unsteady Bridges Friction Slope Method= 1
Parabolic Critical Depth
Global Vel Dist=  1 , 1 , 1
Global Log Level= 0
CheckData=True
Encroach Param= -1, 0, 0, 0
BEGIN DESCRIPTION:
Multiple Run
END DESCRIPTION:

--- UNT0193 IN SAND CR.f01 (steady flow) ---

Flow Title=Multiple
Number of Profiles=7
Profile Names=10-year,25-year,50-year,1pct_min,100-year,1pct_plu,500-year
River Rch & RM= UNT0193 IN SAND ,Reach-1,9426
    1051    1458    1799    1620    2190    2962    3239
River Rch & RM= UNT0193 IN SAND ,Reach-1,7137
    1659    2354    2944    2684    3629    4908    5503
Boundary for River Rch & Prof#=UNT0193 IN SAND ,Reach-1,1
Up Type=0
Dn Type=3
Dn Slope=0.005
Boundary for River Rch & Prof#=UNT0193 IN SAND ,Reach-1,2
Up Type=0
Dn Type=3
Dn Slope=0.005
Boundary for River Rch & Prof#=UNT0193 IN SAND ,Reach-1,3
Up Type=0
Dn Type=3
Dn Slope=0.005
Boundary for River Rch & Prof#=UNT0193 IN SAND ,Reach-1,4
Up Type=0
Dn Type=3
Dn Slope=0.005
Boundary for River Rch & Prof#=UNT0193 IN SAND ,Reach-1,5
Up Type=0
Dn Type=3
Dn Slope=0.005
Boundary for River Rch & Prof#=UNT0193 IN SAND ,Reach-1,6
Up Type=0
Dn Type=3
Dn Slope=0.005
Boundary for River Rch & Prof#=UNT0193 IN SAND ,Reach-1,7
Up Type=0
Dn Type=3
Dn Slope=0.005

--- UNT0193 IN SAND CR.g01 (geometry) ---

Geom Title=Existing Conditions

River Reach=UNT0193 IN SAND ,Reach-1
Reach XY= 30
      3566156.67     10477418.80      3565968.08     10477181.13
      3565869.34     10476781.82      3565959.40     10476285.94
      3565887.79     10476019.02      3565967.49     10475466.13
      3565924.78     10475197.56      3566030.00     10474595.89
      3566020.88     10474301.62      3566081.89     10474185.49
      3565986.79     10473776.48      3566035.29     10473731.30
      3566021.52     10473596.89      3565959.92     10473267.28
      3565842.11     10473101.64      3565748.52     10472702.98
      3565582.98     10472472.26      3565616.48     10472298.63
      3565775.61     10472078.91      3565903.96     10472058.00
      3565989.54     10471860.56      3565995.61     10471423.75
      3566517.78     10470797.86      3566642.12     10470516.82
      3566563.16     10470431.74      3566579.91     10470232.68
      3566475.70     10470115.80      3566194.73     10469876.69
      3565833.14     10469729.15      3565465.77     10469434.04

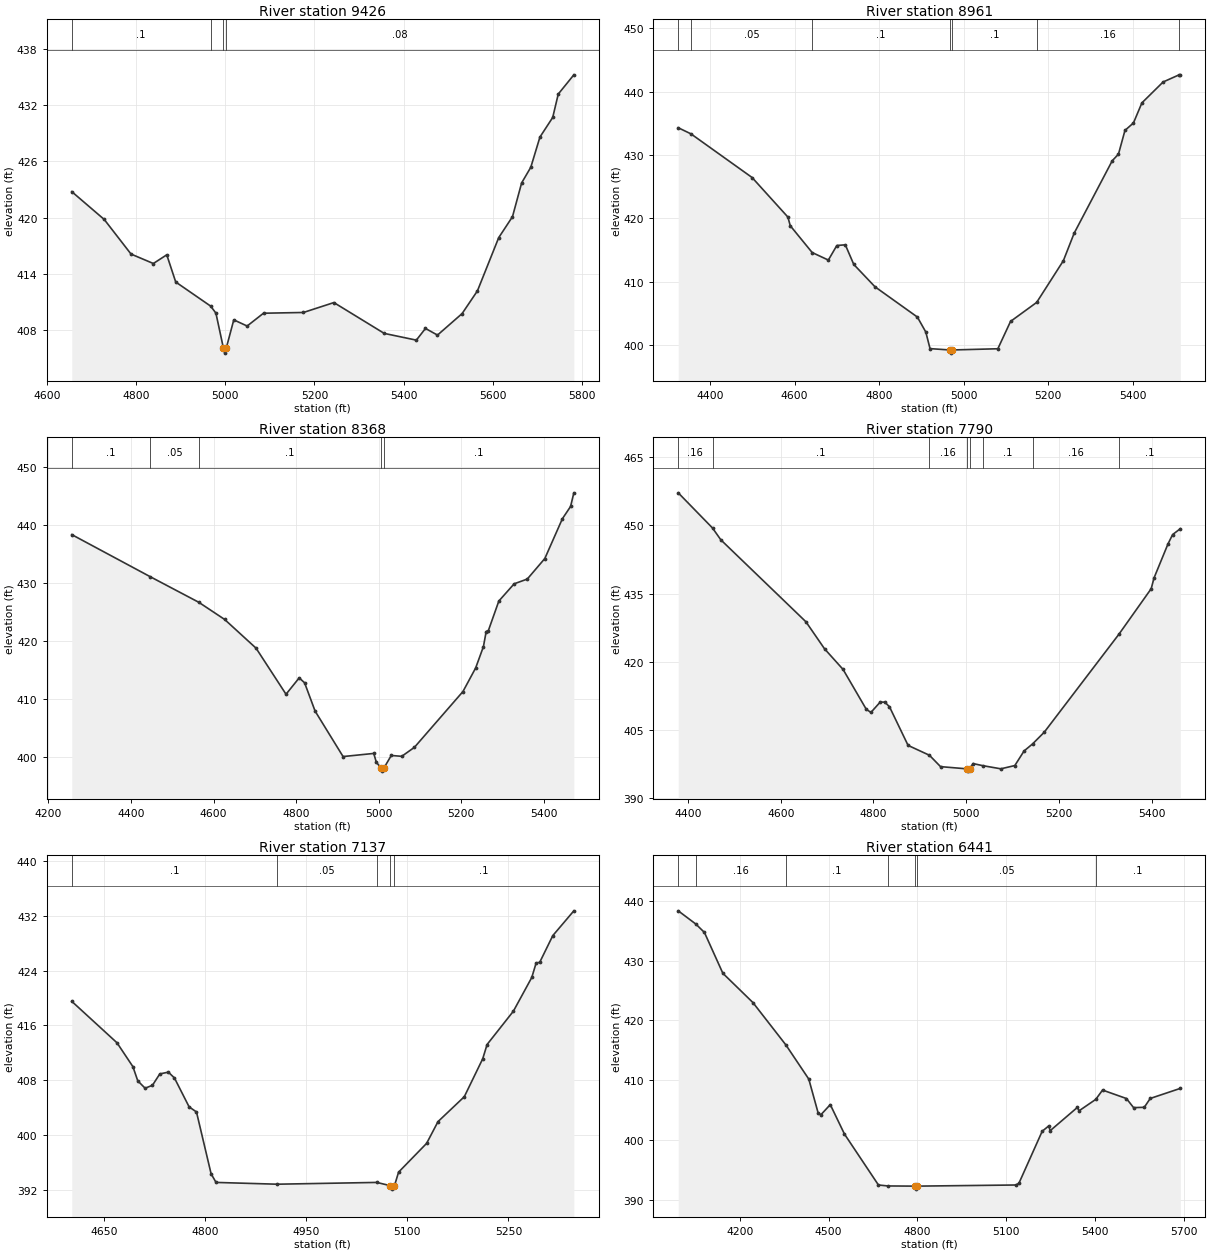
Type RM Length L Ch R = 1,9426,465,465,465
BEGIN DESCRIPTION:
UNT0193 IN SAND CR 15.3
END DESCRIPTION:
XS GIS Cut Line= 3
      3566484.81     10477351.21      3566068.15     10477379.86
      3565378.09     10477216.42
#Sta/Elev= 30
  4655.3  422.77  4728.2  419.79  4788.3  416.09  4838.4  415.08  4868.5  416.01
  4888.6  413.10  4967.0  410.52  4978.8  409.77  4995.8  405.99  4998.6  405.49
  5001.8  405.99  5018.9  409.05  5048.9  408.39  5085.6  409.76  5175.2  409.84
  5243.6  410.90  5356.6  407.60  5428.6  406.88  5449.1  408.13  5476.1  407.42
  5531.3  409.72  5565.7  412.15  5613.5  417.85  5644.4  420.09  5664.9  423.70
  5685.5  425.38  5706.0  428.61  5734.7  430.71  5747.1  433.21  5782.1  435.27
#Mann=4,-1,0
  4655.3     0.1       0  4967.0    0.08       0  4995.8    0.07       0
  5001.8    0.08       0
Bank Sta=4995.8,5001.8
Exp/Cntr=0.3,0.1

Type RM Length L Ch R = 1,8961,593,593,593
BEGIN DESCRIPTION:
UNT0193 IN SAND CR 15.4
END DESCRIPTION:
XS GIS Cut Line= 2
      3566586.40     10477046.53      3565401.50     10476955.38
#Sta/Elev= 30
  4324.4  434.32  4354.4  433.36  4499.2  426.46  4584.0  420.21  4589.5  418.85
  4641.4  414.61  4679.7  413.42  4699.8  415.72  4719.9  415.83  4739.9  412.73
  4790.1  409.20  4890.4  404.42  4910.4  402.05  4920.4  399.43  4967.2  399.22
  4969.9  398.72  4973.2  399.22  5080.9  399.41  5111.0  403.73  5172.8  406.73
  5236.0  413.32  5261.5  417.66  5351.7  429.11  5366.4  430.15  5381.8  433.90
  5401.9  435.08  5421.9  438.25  5472.1  441.55  5509.0  442.65  5512.8  442.68
#Mann=7,-1,0
  4324.4     0.1       0  4354.4    0.05       0  4641.4     0.1       0
  4967.2    0.07       0  4973.2     0.1       0  5172.8    0.16       0
  5509.0     0.1       0
Bank Sta=4967.2,4973.2
Exp/Cntr=0.3,0.1

Type RM Length L Ch R = 1,8368,578,578,578
BEGIN DESCRIPTION:
UNT0193 IN SAND CR 15.2
END DESCRIPTION:
XS GIS Cut Line= 2
      3566630.61     10476666.30      3565485.97     10476255.27
#Sta/Elev= 30
  4256.4  438.38  4445.8  431.15  4564.0  426.72  4626.7  423.76  4702.8  418.81
  4775.4  410.87  4807.3  413.69  4820.4  412.84  4845.8  407.97  4913.6  400.13
  4987.9  400.67  4994.2  399.14  5006.2  398.12  5008.9  397.62  5012.2  398.12
  5030.4  400.32  5055.7  400.17  5086.4  401.72  5204.0  411.34  5234.7  415.39
  5253.6  419.08  5260.2  421.67  5265.5  421.83  5290.9  426.93  5328.0  429.90
  5359.8  430.72  5402.3  434.26  5444.8  441.11  5464.7  443.23  5472.6  445.58
#Mann=5,-1,0
  4256.4     0.1       0  4445.8    0.05       0  4564.0     0.1       0
  5006.2    0.07       0  5012.2     0.1       0
Bank Sta=5006.2,5012.2
Exp/Cntr=0.3,0.1

Type RM Length L Ch R = 1,7790,653,653,653
BEGIN DESCRIPTION:
UNT0193 IN SAND CR 15.1
END DESCRIPTION:
XS GIS Cut Line= 2
      3566547.29     10475900.69      3565465.51     10475853.88
#Sta/Elev= 30
  4378.9  457.19  4452.8  449.44  4470.8  446.83  4654.3  428.77  4694.4  422.82
  4734.4  418.27  4784.5  409.48  4794.5  408.80  4814.5  411.08  4824.5  411.06
  4834.5  410.04  4874.6  401.53  4920.6  399.36  4944.6  396.85  5001.7  396.36
  5004.4  395.86  5007.7  396.36  5014.7  397.53  5035.4  397.07  5074.7  396.37
  5104.8  397.09  5124.8  400.31  5143.0  401.85  5168.2  404.43  5329.3  426.03
  5398.9  436.06  5405.0  438.43  5435.1  445.92  5445.1  447.99  5461.7  449.28
#Mann=8,-1,0
  4378.9    0.16       0  4452.8     0.1       0  4920.6    0.16       0
  5001.7    0.07       0  5007.7    0.16       0  5035.4     0.1       0
  5143.0    0.16       0  5329.3     0.1       0
Bank Sta=5001.7,5007.7
Exp/Cntr=0.3,0.1

Type RM Length L Ch R = 1,7137,696,696,696
BEGIN DESCRIPTION:
UNT0193 IN SAND CR 15.0
END DESCRIPTION:
XS GIS Cut Line= 3
      3566292.13     10475391.65      3565942.11     10475241.64
      3565592.13     10475341.64
#Sta/Elev= 30
  4602.3  419.51  4669.4  413.45  4693.0  409.96  4700.2  407.89  4711.1  406.81
  4722.0  407.24  4732.9  408.90  4745.6  409.16  4754.6  408.31  4776.4  404.08
  4787.3  403.34  4809.0  394.30  4816.3  393.04  4906.8  392.78  5054.8  393.04
  5075.0  392.56  5077.8  392.06  5081.0  392.56  5087.1  394.54  5128.7  398.75
  5145.6  401.93  5184.6  405.57  5211.9  411.11  5218.4  413.20  5257.4  418.07
  5284.7  423.00  5291.2  425.13  5296.4  425.20  5315.9  429.12  5347.1  432.74
#Mann=5,-1,0
  4602.3     0.1       0  4906.8    0.05       0  5054.8     0.1       0
  5075.0   0.033       0  5081.0     0.1       0
Bank Sta=5075,5081
Exp/Cntr=0.3,0.1

Type RM Length L Ch R = 1,6441,94,94,94
BEGIN DESCRIPTION:
UNT0193 IN SAND CR 14.0
END DESCRIPTION:
XS GIS Cut Line= 4
      3567007.47     10474813.14      3566187.20     10474591.80
      3565812.20     10474524.09      3565351.22     10474573.58
#Sta/Elev= 30
  3992.6  438.30  4052.0  436.09  4081.0  434.69  4143.2  427.87  4244.7  422.98
  4356.0  415.90  4433.2  410.20  4464.3  404.62  4473.8  404.24  4505.7  405.94
  4553.6  401.02  4668.2  392.52  4700.4  392.36  4792.7  392.33  4795.4  391.83
  4798.7  392.33  5131.9  392.52  5142.1  392.79  5220.8  401.49  5242.8  402.38
  5247.8  401.59  5339.9  405.49  5345.0  404.90  5401.7  406.82  5424.5  408.37
  5505.0  406.96  5529.2  405.44  5565.3  405.49  5585.4  406.97  5686.9  408.65
#Mann=7,-1,0
  3992.6     0.1       0  4052.0    0.16       0  4356.0     0.1       0
  4700.4    0.05       0  4792.7   0.033       0  4798.7    0.05       0
  5401.7     0.1       0
Bank Sta=4792.7,4798.7
Exp/Cntr=0.3,0.1

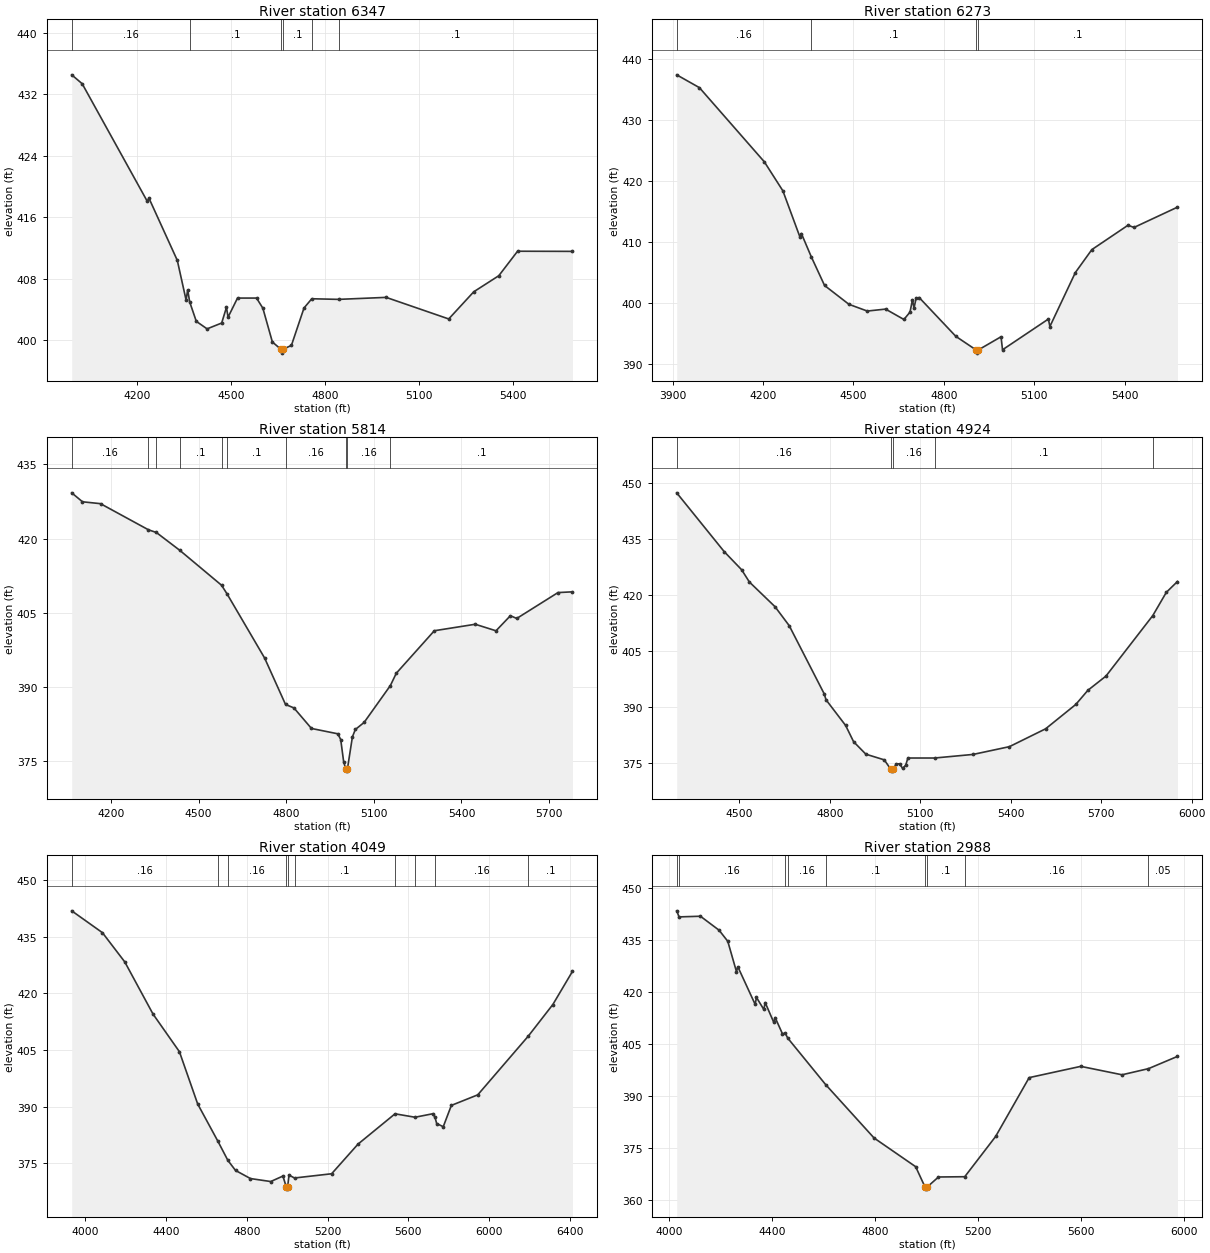
Type RM Length L Ch R = 1,6347,74,74,74
BEGIN DESCRIPTION:
UNT0193 IN SAND CR 13.1
END DESCRIPTION:
XS GIS Cut Line= 3
      3567035.21     10474615.01      3566126.32     10474469.17
      3565446.86     10474474.38
#Sta/Elev= 30
  3990.7  434.55  4024.2  433.39  4232.4  418.06  4237.4  418.50  4328.1  410.39
  4356.2  405.22  4361.3  406.56  4367.6  404.99  4388.8  402.45  4423.3  401.47
  4469.9  402.23  4485.2  404.27  4490.3  402.99  4520.5  405.48  4581.3  405.48
  4601.5  404.16  4631.9  399.76  4659.3  398.81  4662.0  398.31  4665.3  398.81
  4692.7  399.31  4733.0  404.19  4757.8  405.39  4843.4  405.31  4995.4  405.57
  5195.4  402.76  5275.4  406.30  5355.4  408.39  5415.4  411.58  5590.7  411.56
#Mann=6,-1,0
  3990.7    0.16       0  4367.6     0.1       0  4659.3    0.07       0
  4665.3     0.1       0  4757.8    0.05       0  4843.4     0.1       0
Bank Sta=4659.3,4665.3
Exp/Cntr=0.3,0.1

Type RM Length L Ch R = 1,6273,459,459,459
BEGIN DESCRIPTION:
UNT0193 IN SAND CR 13.0
END DESCRIPTION:
XS GIS Cut Line= 4
      3567106.47     10474563.15      3566116.89     10474401.70
      3565796.58     10474380.86      3565458.05     10474383.47
#Sta/Elev= 30
  3913.3  437.39  3988.7  435.29  4204.3  423.14  4265.8  418.39  4322.1  410.87
  4327.2  411.40  4360.0  407.60  4404.1  402.90  4485.1  399.81  4545.9  398.71
  4606.7  399.03  4667.5  397.33  4687.8  398.54  4695.9  400.57  4701.0  399.19
  4708.0  400.80  4718.2  400.92  4839.8  394.57  4907.7  392.32  4910.4  391.82
  4913.7  392.32  4989.9  394.50  4994.9  392.37  5147.1  397.40  5152.1  396.18
  5236.7  405.02  5291.4  408.77  5411.4  412.76  5431.4  412.40  5575.5  415.72
#Mann=4,-1,0
  3913.3    0.16       0  4360.0     0.1       0  4907.7    0.07       0
  4913.7     0.1       0
Bank Sta=4907.7,4913.7
Exp/Cntr=0.3,0.1

Type RM Length L Ch R = 1,5814,890,890,890
BEGIN DESCRIPTION:
UNT0193 IN SAND CR 12.0
END DESCRIPTION:
XS GIS Cut Line= 4
      3566947.65     10473828.77      3566486.68     10473945.97
      3565640.33     10473987.63      3565351.28     10474250.64
#Sta/Elev= 30
  4066.0  429.25  4102.9  427.44  4164.6  427.06  4328.7  421.78  4355.7  421.24
  4435.8  417.64  4578.9  410.58  4598.2  408.78  4726.4  395.86  4797.8  386.50
  4826.5  385.80  4886.6  381.65  4976.7  380.57  4986.7  379.41  4996.8  374.91
  5003.8  373.53  5006.5  373.03  5009.8  373.53  5026.8  379.97  5036.8  381.44
  5066.8  382.87  5156.6  390.31  5177.0  392.81  5307.1  401.39  5447.2  402.70
  5518.2  401.38  5567.5  404.43  5589.1  403.87  5730.3  409.10  5779.8  409.25
#Mann=10,-1,0
  4066.0    0.16       0  4328.7     0.1       0  4355.7    0.16       0
  4435.8     0.1       0  4578.9    0.16       0  4598.2     0.1       0
  4797.8    0.16       0  5003.8    0.07       0  5009.8    0.16       0
  5156.6     0.1       0
Bank Sta=5003.8,5009.8
Exp/Cntr=0.3,0.1

Type RM Length L Ch R = 1,4924,875,875,875
BEGIN DESCRIPTION:
UNT0193 IN SAND CR 10.0
END DESCRIPTION:
XS GIS Cut Line= 4
      3566569.01     10473047.30      3566018.08     10473149.65
      3565574.24     10473229.59      3564925.20     10473203.63
#Sta/Elev= 30
  4292.0  447.30  4449.6  431.55  4507.5  426.69  4533.0  423.43  4618.1  416.81
  4665.2  411.73  4781.6  393.42  4787.2  391.89  4852.4  385.00  4878.7  380.66
  4919.4  377.32  4980.4  375.80  5002.2  373.28  5004.9  372.78  5008.2  373.28
  5021.0  374.70  5031.2  374.74  5041.3  373.52  5051.5  374.34  5058.8  376.29
  5147.2  376.29  5275.0  377.25  5395.5  379.33  5515.6  384.11  5615.7  390.63
  5655.8  394.42  5715.8  398.23  5871.2  414.44  5916.0  420.65  5952.9  423.55
#Mann=5,-1,0
  4292.0    0.16       0  5002.2    0.07       0  5008.2    0.16       0
  5147.2     0.1       0  5871.2    0.16       0
Bank Sta=5002.2,5008.2
Exp/Cntr=0.3,0.1

Type RM Length L Ch R = 1,4049,1061,1061,1061
BEGIN DESCRIPTION:
UNT0193 IN SAND CR 8.0
END DESCRIPTION:
XS GIS Cut Line= 2
      3566662.82     10472490.01      3564195.55     10472266.18
#Sta/Elev= 30
  3934.2  441.86  4086.3  436.07  4196.9  428.32  4336.6  414.51  4467.1  404.55
  4557.5  390.70  4657.6  380.82  4707.0  375.75  4744.7  373.10  4818.5  370.95
  4918.9  370.16  4979.2  371.61  4996.3  368.65  4999.0  368.15  5002.3  368.65
  5009.3  371.87  5036.5  371.10  5220.2  372.22  5350.7  380.07  5533.9  388.10
  5632.8  387.19  5722.2  388.13  5731.7  387.14  5739.9  385.53  5772.4  384.68
  5812.6  390.33  5943.1  393.12  6193.2  408.68  6314.7  417.05  6411.6  425.81
#Mann=10,-1,0
  3934.2    0.16       0  4657.6     0.1       0  4707.0    0.16       0
  4996.3    0.07       0  5002.3    0.16       0  5036.5     0.1       0
  5533.9    0.05       0  5632.8     0.1       0  5731.7    0.16       0
  6193.2     0.1       0
Bank Sta=4996.3,5002.3
Exp/Cntr=0.3,0.1

Type RM Length L Ch R = 1,2988,847,847,847
BEGIN DESCRIPTION:
UNT0193 IN SAND CR 6.0
END DESCRIPTION:
XS GIS Cut Line= 3
      3566938.83     10471771.26      3566199.24     10471557.71
      3565027.39     10471505.63
#Sta/Elev= 30
  4030.5  443.38  4039.7  441.63  4122.6  441.82  4195.1  437.78  4228.7  434.59
  4262.4  425.83  4267.6  427.26  4334.8  416.41  4340.0  418.40  4368.5  414.93
  4373.7  416.93  4407.3  411.18  4412.5  412.59  4440.9  407.90  4451.3  408.14
  4461.1  406.69  4608.3  393.27  4796.2  377.86  4957.6  369.58  4994.6  363.61
  4997.4  363.11  5000.6  363.61  5046.2  366.61  5148.1  366.69  5267.9  378.30
  5398.0  395.27  5598.2  398.52  5758.4  396.09  5860.9  397.86  5973.3  401.39
#Mann=9,-1,0
  4030.5     0.1       0  4039.7    0.16       0  4451.3     0.1       0
  4461.1    0.16       0  4608.3     0.1       0  4994.6    0.07       0
  5000.6     0.1       0  5148.1    0.16       0  5860.9    0.05       0
Bank Sta=4994.6,5000.6
Exp/Cntr=0.3,0.1

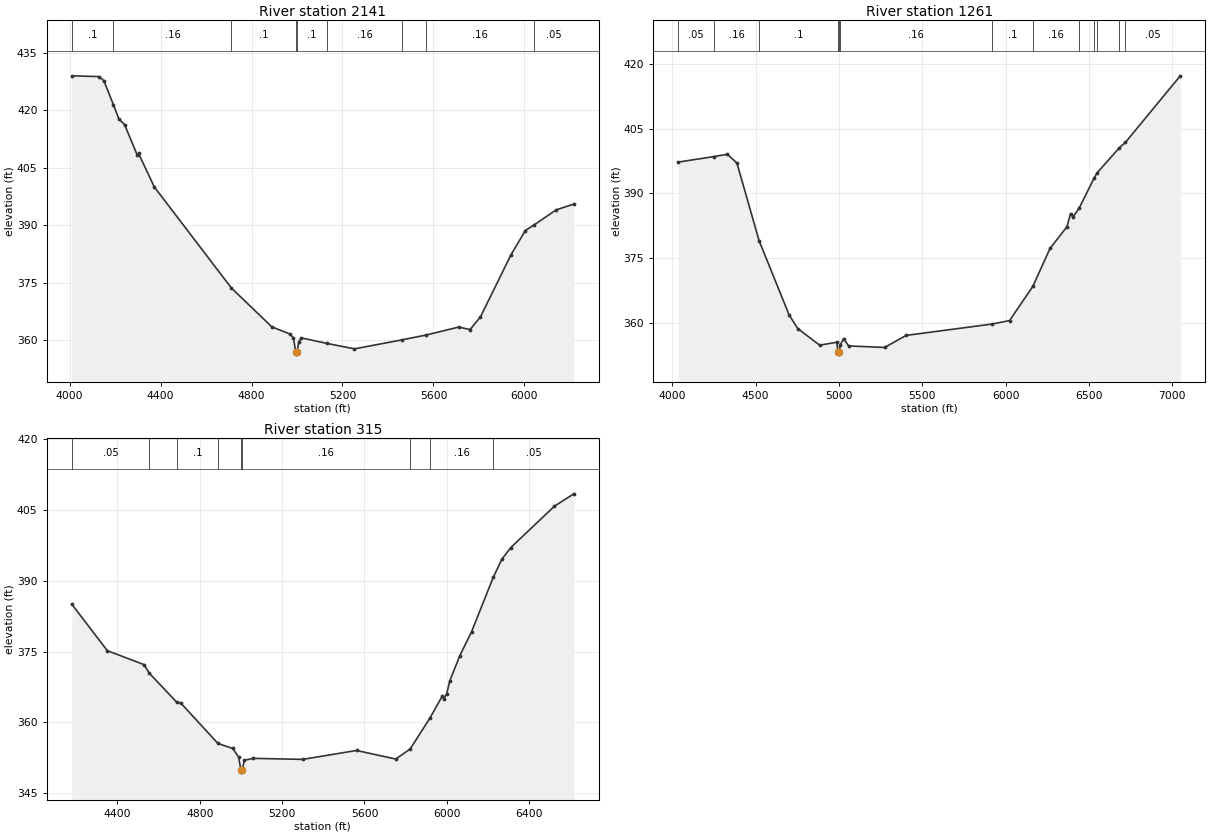
Type RM Length L Ch R = 1,2141,880,880,880
BEGIN DESCRIPTION:
UNT0193 IN SAND CR 4.0
END DESCRIPTION:
XS GIS Cut Line= 4
      3567402.40     10471052.51      3566569.03     10470948.34
      3566261.74     10470771.25      3565298.17     10471083.77
#Sta/Elev= 30
  4009.7  428.97  4130.9  428.77  4151.1  427.65  4192.9  421.41  4217.4  417.62
  4241.8  416.26  4298.0  408.23  4303.1  408.73  4372.8  399.95  4711.8  373.58
  4889.7  363.44  4970.2  361.57  4984.5  360.51  4994.5  356.84  4997.2  356.34
  5000.5  356.84  5007.5  359.53  5019.1  360.57  5133.3  359.12  5252.6  357.71
  5460.2  360.05  5565.5  361.30  5710.8  363.40  5761.0  362.76  5806.7  366.07
  5939.9  382.16  6003.8  388.59  6043.0  390.08  6139.5  393.99  6217.2  395.50
#Mann=9,-1,0
  4009.7     0.1       0  4192.9    0.16       0  4711.8     0.1       0
  4994.5    0.07       0  5000.5     0.1       0  5133.3    0.16       0
  5460.2     0.1       0  5565.5    0.16       0  6043.0    0.05       0
Bank Sta=4994.5,5000.5
Exp/Cntr=0.3,0.1

Type RM Length L Ch R = 1,1261,946,946,946
BEGIN DESCRIPTION:
UNT0193 IN SAND CR 3.0
END DESCRIPTION:
XS GIS Cut Line= 3
      3567417.98     10469901.47      3566600.28     10470057.71
      3564793.00     10471276.45
#Sta/Elev= 30
  4036.0  397.25  4249.1  398.53  4331.1  399.07  4388.2  397.03  4520.9  379.06
  4700.8  361.87  4752.9  358.67  4884.4  354.82  4986.3  355.49  4996.0  353.24
  4998.7  352.74  5002.0  353.24  5008.1  354.86  5028.3  356.36  5058.3  354.64
  5274.1  354.29  5403.1  357.08  5918.4  359.71  6023.6  360.51  6163.4  368.44
  6266.5  377.23  6368.4  382.29  6389.5  385.29  6404.4  384.50  6442.4  386.66
  6530.8  393.52  6548.3  394.72  6680.8  400.50  6718.7  401.81  7048.3  417.25
#Mann=13,-1,0
  4036.0    0.05       0  4249.1    0.16       0  4520.9     0.1       0
  4996.0    0.07       0  5002.0     0.1       0  5008.1    0.16       0
  5918.4     0.1       0  6163.4    0.16       0  6442.4    0.05       0
  6530.8    0.16       0  6548.3    0.05       0  6680.8    0.16       0
  6718.7    0.05       0
Bank Sta=4996,5002
Exp/Cntr=0.3,0.1

Type RM Length L Ch R = 1,315,0,0,0
BEGIN DESCRIPTION:
UNT0193 IN SAND CR 1.0
END DESCRIPTION:
XS GIS Cut Line= 3
      3566438.82     10469286.88      3565829.45     10469510.84
      3564553.44     10470766.02
#Sta/Elev= 30
  4178.0  385.07  4350.8  375.21  4528.3  372.27  4555.1  370.42  4688.2  364.27
  4707.2  364.13  4888.0  355.55  4960.3  354.48  4988.6  352.64  4999.7  349.97
  5002.5  349.47  5005.7  349.97  5016.9  351.99  5059.3  352.39  5299.7  352.17
  5561.3  354.06  5752.2  352.24  5821.9  354.38  5917.2  360.87  5978.5  365.64
  5985.6  365.03  5999.8  366.11  6013.9  368.75  6063.4  374.18  6119.9  379.18
  6225.6  390.77  6268.4  394.65  6310.8  397.06  6523.0  405.84  6617.1  408.45
#Mann=9,-1,0
  4178.0    0.05       0  4555.1    0.16       0  4688.2     0.1       0
  4888.0    0.16       0  4999.7    0.07       0  5005.7    0.16       0
  5821.9     0.1       0  5917.2    0.16       0  6225.6    0.05       0
Bank Sta=4999.7,5005.7
Exp/Cntr=0.3,0.1

Chan Stop Cuts=-1