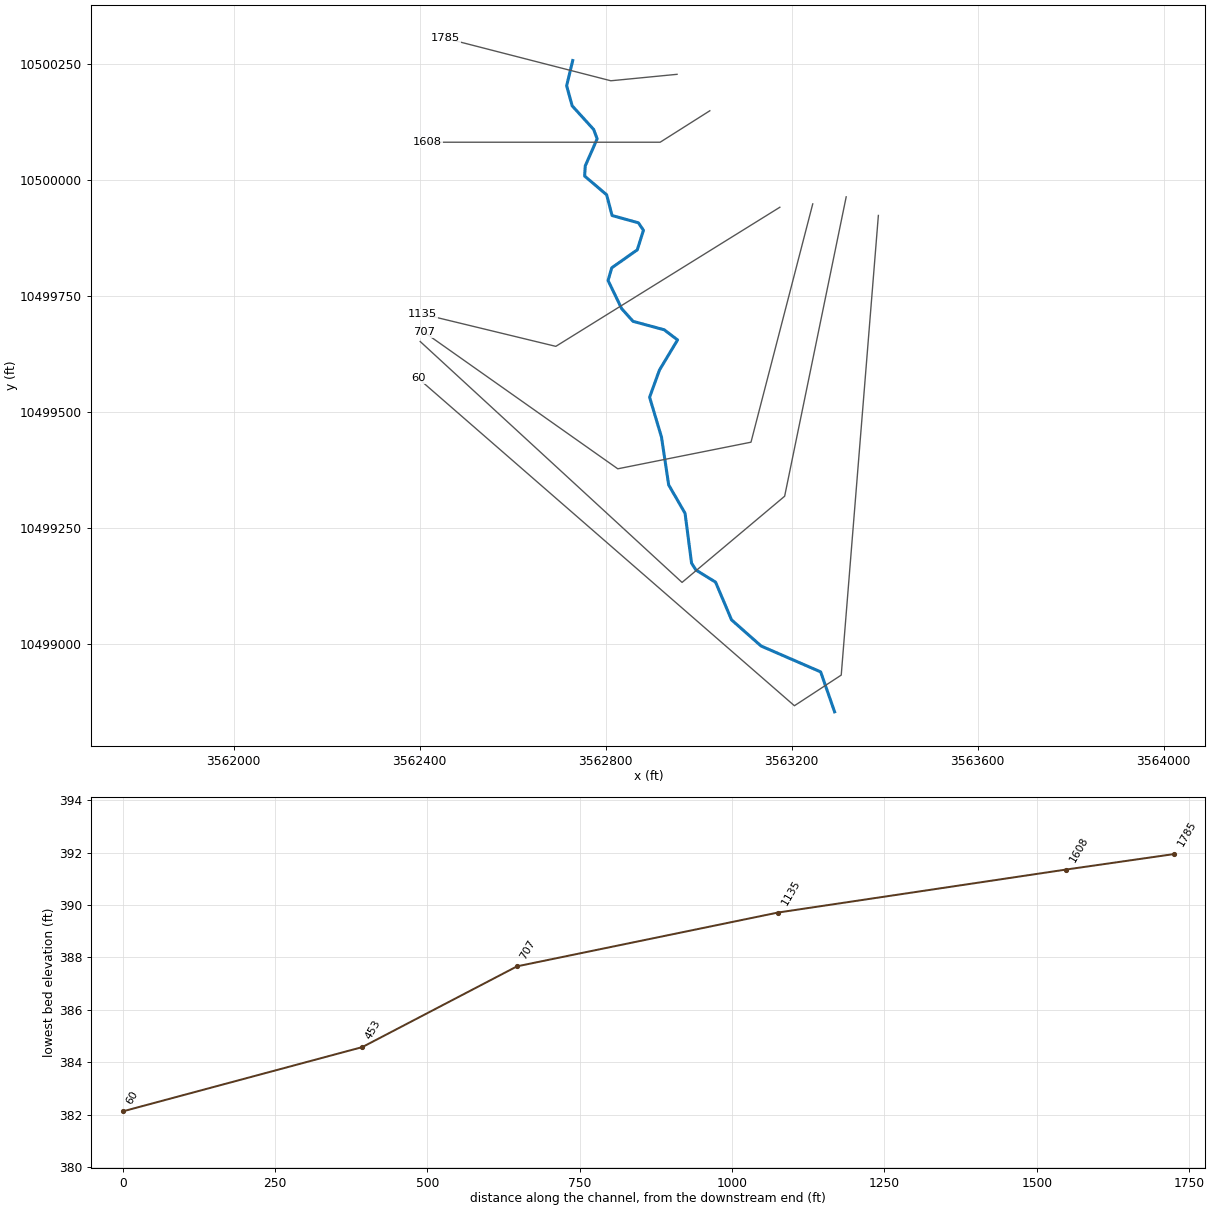
--- UNT02009 IN SAND CR.prj (project) ---

Proj Title=UNT02009 IN SAND CR Base Level Engineering
Current Plan=p01
Default Exp/Contr=0.3,0.1
English Units
Geom File=g01
Flow File=f01
Plan File=p01
Y Axis Title=Elevation
X Axis Title(PF)=Main Channel Distance
X Axis Title(XS)=Station
BEGIN DESCRIPTION:
UNT02009 IN SAND CR
END DESCRIPTION:
DSS Export Rating Curves= 0
DSS Export Rating Curve Sorted= 0
DSS Export Volume Flow Curves= 0
DXF OffsetX= 0
DXF OffsetY= 0
DXF ScaleX= 1
DXF ScaleY= 10

--- UNT02009 IN SAND CR.p01 (plan) ---

Plan Title=Multiple Run
Short Identifier=Multiple
Geom File=g01
Flow File=f01
Subcritical Flow
K Sum by GR= 0
Std Step Tol= 0.01
Critical Tol= 0.01
Num of Std Step Trials= 20
Max Error Tol= 0.3
Flow Tol Ratio= 0.001
Split Flow NTrial= 30
Split Flow Tol= 0.02
Split Flow Ratio= 0.02
Log Output Level= 0
Friction Slope Method= 1
Unsteady Friction Slope Method= 2
Unsteady Bridges Friction Slope Method= 1
Parabolic Critical Depth
Global Vel Dist=  1 , 1 , 1
Global Log Level= 0
CheckData=True
Encroach Param= -1, 0, 0, 0
BEGIN DESCRIPTION:
Multiple Run
END DESCRIPTION:

--- UNT02009 IN SAND CR.f01 (steady flow) ---

Flow Title=Multiple
Program Version=4.10
Number of Profiles= 7
Profile Names=10-year,25-year,50-year,1pct_min,100-year,1pct_plu,500-year
River Rch & RM=UNT02009 IN SAND,Reach-1         ,1785
     365     472     554     478     646     874     873
Boundary for River Rch & Prof#=UNT02009 IN SAND,Reach-1         , 1
Up Type= 0
Dn Type= 3
Dn Slope=0.005
Boundary for River Rch & Prof#=UNT02009 IN SAND,Reach-1         , 2
Up Type= 0
Dn Type= 3
Dn Slope=0.005
Boundary for River Rch & Prof#=UNT02009 IN SAND,Reach-1         , 3
Up Type= 0
Dn Type= 3
Dn Slope=0.005
Boundary for River Rch & Prof#=UNT02009 IN SAND,Reach-1         , 4
Up Type= 0
Dn Type= 3
Dn Slope=0.005
Boundary for River Rch & Prof#=UNT02009 IN SAND,Reach-1         , 5
Up Type= 0
Dn Type= 3
Dn Slope=0.005
Boundary for River Rch & Prof#=UNT02009 IN SAND,Reach-1         , 6
Up Type= 0
Dn Type= 3
Dn Slope=0.005
Boundary for River Rch & Prof#=UNT02009 IN SAND,Reach-1         , 7
Up Type= 0
Dn Type= 3
Dn Slope=0.005
DSS Import GetInterval= 0
DSS Import GetPeak= 0
DSS Import FillOption= 0

--- UNT02009 IN SAND CR.g01 (geometry) ---

Geom Title=Existing Conditions
Program Version=4.10

River Reach=UNT02009 IN SAND,Reach-1
Reach XY= 30
      3562728.93     10500256.66      3562715.85     10500202.25
      3562727.76     10500159.12       3562774.1     10500108.04
      3562781.46     10500087.95      3562755.87      10500029.7
      3562754.54     10500007.89      3562801.86     10499967.55
      3562813.57     10499922.96       3562870.2     10499907.24
      3562881.06     10499891.15      3562867.77      10499849.1
      3562812.85     10499810.32      3562804.95     10499783.03
      3562834.25     10499722.36      3562858.68     10499695.14
      3562925.67     10499676.92      3562954.43     10499655.09
      3562915.48     10499590.35      3562894.26     10499531.68
      3562919.79      10499446.1      3562935.29     10499342.96
      3562970.51     10499281.88      3562984.49     10499174.46
      3562993.94     10499159.66      3563036.13     10499133.62
       3563070.5     10499052.37      3563134.04     10498996.12
      3563262.17     10498940.39      3563292.11      10498854.4

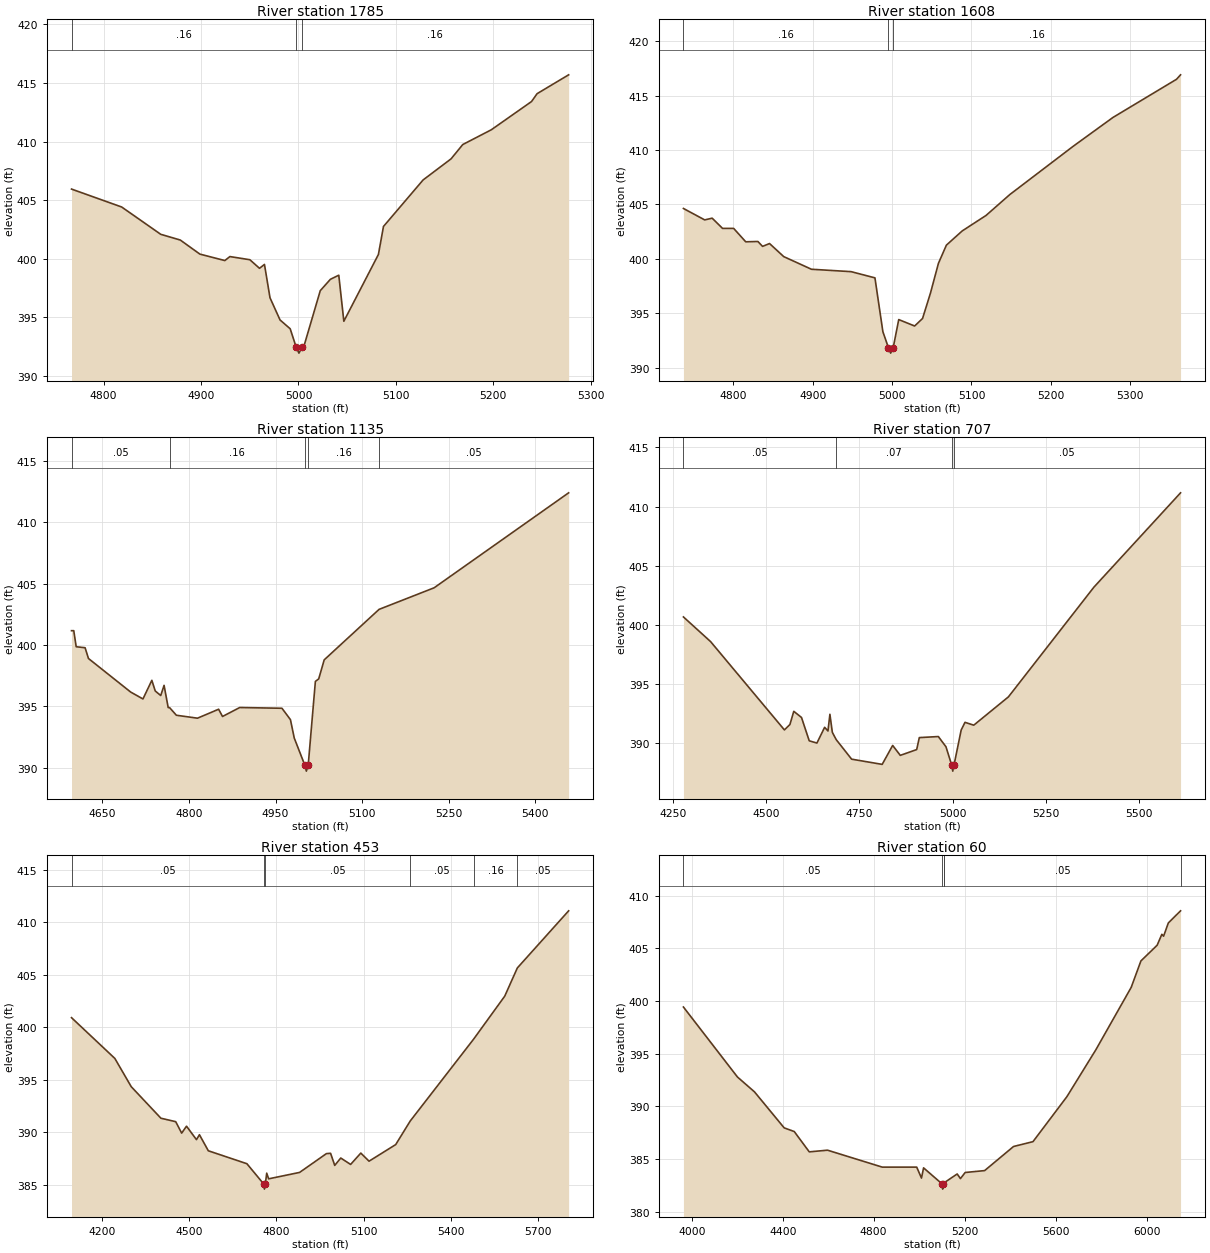
Type RM Length L Ch R = 1 ,1785    ,177,177,177
BEGIN DESCRIPTION:
UNT02009 IN SAND CR 2.0
END DESCRIPTION:
XS GIS Cut Line= 3
      3562953.32     10500226.94      3562810.91     10500213.05
      3562455.18     10500304.57
#Sta/Elev= 30
    4767  405.94  4818.5  404.41  4858.6  402.08  4878.7  401.59  4898.8  400.39
  4924.4  399.84  4929.6  400.18  4950.1  399.91    4960  399.18  4965.1  399.51
  4970.8  396.66  4981.1  394.77  4991.5  394.02  4997.7  392.44  5000.5  391.94
  5003.7  392.44  5005.9  392.61  5022.4  397.27  5032.8  398.24  5041.4  398.59
  5046.6  394.66  5082.1  400.36  5087.3  402.75    5128  406.72  5156.7  408.52
  5168.7  409.74    5198     411  5239.3  413.41    5245  414.08  5277.4  415.69
#Mann= 3 ,-1 , 0
    4767     .16       0  4997.7     .07       0  5003.7     .16       0
Bank Sta=4997.7,5003.7
XS Rating Curve= 0 ,0
Exp/Cntr=0.3,0.1

Type RM Length L Ch R = 1 ,1608    ,473,473,473
BEGIN DESCRIPTION:
UNT02009 IN SAND CR 2.2
END DESCRIPTION:
XS GIS Cut Line= 3
      3563023.78     10500148.48      3562916.98     10500080.75
      3562417.04     10500080.75
#Sta/Elev= 30
  4737.1  404.63  4763.9  403.58  4773.3  403.74  4786.4   402.8  4800.4   402.8
  4815.6  401.57  4830.9   401.6  4836.8  401.15  4845.6  401.41  4863.5  400.21
  4898.4  399.05  4948.4  398.83  4978.4  398.26  4988.4  393.32  4995.4  391.85
  4998.2  391.35  5001.4  391.85  5008.4  394.43  5028.4  393.84  5038.4  394.53
  5048.4  396.87  5058.4  399.59  5068.4  401.26  5088.4  402.57  5118.4  403.99
  5148.4  405.91  5228.4  410.35  5278.4  412.99  5358.4  416.49  5363.5   416.9
#Mann= 3 ,-1 , 0
  4737.1     .16       0  4995.4     .07       0  5001.4     .16       0
Bank Sta=4995.4,5001.4
XS Rating Curve= 0 ,0
Exp/Cntr=0.3,0.1

Type RM Length L Ch R = 1 ,1135    ,428,428,428
BEGIN DESCRIPTION:
UNT02009 IN SAND CR 1.0
END DESCRIPTION:
XS GIS Cut Line= 3
      3563174.35     10499940.74      3562692.59     10499641.26
      3562406.63     10499710.59
#Sta/Elev= 30
  4596.5  401.17  4600.4  401.17  4604.6  399.86    4620  399.78  4625.9   398.9
  4699.1  396.16  4720.3   395.6  4735.7  397.12  4741.6  396.25  4751.1  395.88
  4756.9  396.71    4764   394.9  4766.5  394.89  4778.2  394.27  4814.8  394.03
  4851.4  394.76  4858.2  394.17    4888   394.9  4961.2  394.84  4975.9  393.91
  4982.5  392.41  5000.7  390.21  5003.5  389.71  5006.7  390.21  5019.1  397.03
  5024.9  397.24  5034.4  398.79  5129.5  402.91  5224.9  404.67    5458  412.42
#Mann= 5 ,-1 , 0
  4596.5     .05       0  4766.5     .16       0  5000.7     .07       0
  5006.7     .16       0  5129.5     .05       0
Bank Sta=5000.7,5006.7
XS Rating Curve= 0 ,0
Exp/Cntr=0.3,0.1

Type RM Length L Ch R = 1 ,707     ,254,254,254
BEGIN DESCRIPTION:
UNT02009 IN SAND CR 2.1
END DESCRIPTION:
XS GIS Cut Line= 4
      3563245.11     10499947.94       3563112.3     10499434.92
      3562825.84     10499377.63      3562409.14     10499671.92
#Sta/Elev= 30
  4278.4  400.68  4351.1   398.6    4549  391.14  4563.8   391.6  4574.1  392.71
  4594.8  392.19  4615.5  390.22  4636.1  390.03  4656.8  391.36  4665.7  391.05
  4670.9  392.46  4677.4  390.94  4687.8  390.32  4729.1  388.67    4811  388.23
  4839.1  389.83  4859.5  388.99  4903.5  389.48  4910.5  390.49  4961.5  390.58
  4981.9  389.72  4997.4  388.16  5000.1  387.66  5003.4  388.16  5022.7  391.13
  5032.9  391.78  5056.4  391.54  5149.3  393.93  5378.3  403.19  5610.6  411.16
#Mann= 4 ,-1 , 0
  4278.4     .05       0  4687.8     .07       0  4997.4     .07       0
  5003.4     .05       0
Bank Sta=4997.4,5003.4
XS Rating Curve= 0 ,0
Exp/Cntr=0.3,0.1

Type RM Length L Ch R = 1 ,453     ,393,393,393
BEGIN DESCRIPTION:
UNT02009 IN SAND CR 1.11
END DESCRIPTION:
XS GIS Cut Line= 4
      3563317.06     10499963.15      3563184.68     10499318.59
      3562964.05     10499133.04      3562400.89      10499651.7
#Sta/Elev= 30
  4094.2   400.9  4243.4  397.02  4299.9  394.33    4402  391.33    4453     391
  4473.5  389.91  4490.2  390.57  4524.5  389.29  4534.7  389.76  4565.3  388.23
  4698.1     387  4755.7  385.08  4758.4  384.58  4761.7  385.08  4766.4   386.1
    4773  385.56  4879.6  386.17    4972  387.96  4986.3  387.99  5000.6  386.84
  5021.4  387.54  5055.3  386.93  5090.4  388.01  5118.8  387.24  5210.6  388.82
  5260.5  391.06    5479  398.86  5586.1  402.95  5629.4  405.63  5806.1  411.07
#Mann= 6 ,-1 , 0
  4094.2     .05       0  4755.7    .035       0  4761.7     .05       0
  5260.5     .05       0    5479     .16       0  5629.4     .05       0
Bank Sta=4755.7,4761.7
XS Rating Curve= 0 ,0
Exp/Cntr=0.3,0.1

Type RM Length L Ch R = 1 ,60      ,0,0,0
BEGIN DESCRIPTION:
UNT02009 IN SAND CR 1.1
END DESCRIPTION:
XS GIS Cut Line= 4
      3563386.25     10499923.11      3563306.38     10498933.48
      3563205.69     10498867.51      3562396.91     10499572.15
#Sta/Elev= 30
  3963.6  399.43  4201.2  392.78  4276.1  391.37  4406.5  387.95  4450.9   387.6
  4516.9  385.67  4597.1  385.83  4837.9  384.22  4989.3  384.22  5010.4  383.18
  5019.5  384.15  5100.7  382.63  5103.5  382.13  5106.7  382.63  5110.3  382.74
  5167.3  383.57  5181.6  383.13  5202.4  383.71  5287.9  383.89  5415.1  386.18
  5500.6  386.64  5649.6  390.91  5776.8  395.36  5932.5   401.3  5975.2  403.81
  6046.5   405.3  6067.3  406.34  6074.9  406.16  6095.8  407.42  6149.5  408.57
#Mann= 5 ,-1 , 0
  3963.6     .05       0  5100.7     .03       0  5110.3     .16       0
  5110.3     .05       0  6149.5     .16       0
Bank Sta=5100.7,5106.7
XS Rating Curve= 0 ,0
Exp/Cntr=0.3,0.1

Chan Stop Cuts=-1
Use User Specified Reach Order=0
Composite Channel Slope=5