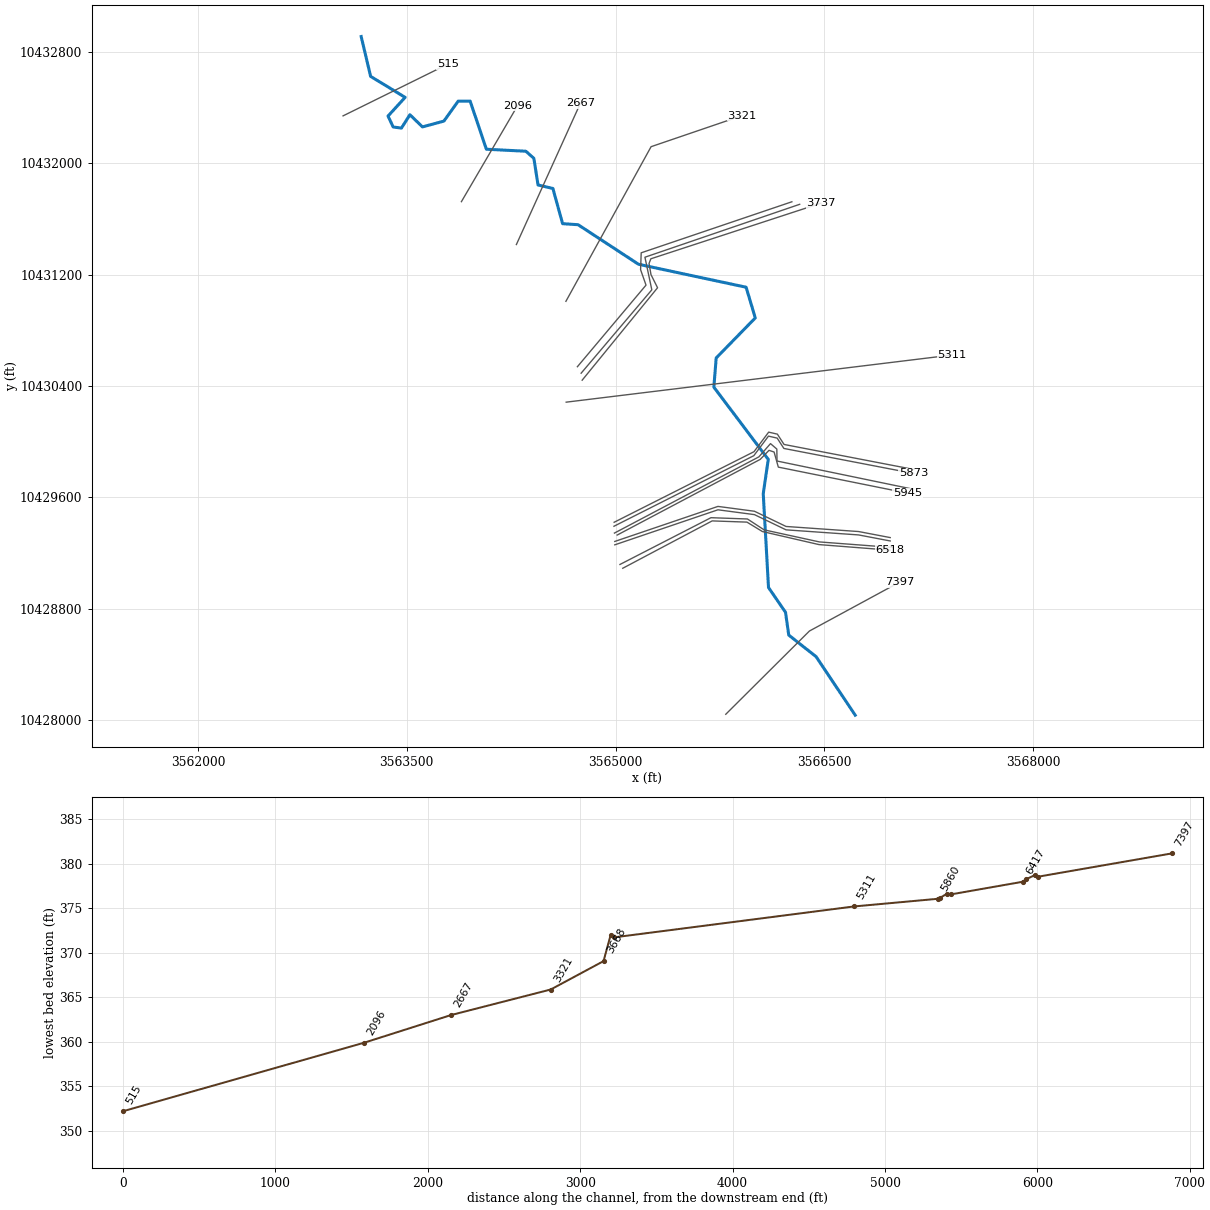
--- UNT0204 IN SAND CR.prj (project) ---

Proj Title=UNT0204 IN SAND CR Base Level Engineering
Current Plan=p01
Default Exp/Contr=0.3,0.1
English Units
Geom File=g01
Flow File=f01
Plan File=p01
Y Axis Title=Elevation
X Axis Title(PF)=Main Channel Distance
X Axis Title(XS)=Station
BEGIN DESCRIPTION:
UNT0204 IN SAND CR
END DESCRIPTION:
DSS Export Rating Curves= 0
DSS Export Rating Curve Sorted= 0
DSS Export Volume Flow Curves= 0
DXF OffsetX= 0
DXF OffsetY= 0
DXF ScaleX= 1
DXF ScaleY= 10

--- UNT0204 IN SAND CR.p01 (plan) ---

Plan Title=Multiple Run
Short Identifier=Multiple
Geom File=g01
Flow File=f01
Subcritical Flow
K Sum by GR= 0
Std Step Tol= 0.01
Critical Tol= 0.01
Num of Std Step Trials= 20
Max Error Tol= 0.3
Flow Tol Ratio= 0.001
Split Flow NTrial= 30
Split Flow Tol= 0.02
Split Flow Ratio= 0.02
Log Output Level= 0
Friction Slope Method= 1
Unsteady Friction Slope Method= 2
Unsteady Bridges Friction Slope Method= 1
Parabolic Critical Depth
Global Vel Dist=  1 , 1 , 1
Global Log Level= 0
CheckData=True
Encroach Param= -1, 0, 0, 0
BEGIN DESCRIPTION:
Multiple Run
END DESCRIPTION:

--- UNT0204 IN SAND CR.f01 (steady flow) ---

Flow Title=Multiple
Number of Profiles=7
Profile Names=10-year,25-year,50-year,1pct_min,100-year,1pct_plu,500-year
River Rch & RM= UNT0204 IN SAND ,Reach-1,7397
     910    1239    1507    1338    1809    2447    2598
Boundary for River Rch & Prof#=UNT0204 IN SAND ,Reach-1,1
Up Type=0
Dn Type=3
Dn Slope=0.005
Boundary for River Rch & Prof#=UNT0204 IN SAND ,Reach-1,2
Up Type=0
Dn Type=3
Dn Slope=0.005
Boundary for River Rch & Prof#=UNT0204 IN SAND ,Reach-1,3
Up Type=0
Dn Type=3
Dn Slope=0.005
Boundary for River Rch & Prof#=UNT0204 IN SAND ,Reach-1,4
Up Type=0
Dn Type=3
Dn Slope=0.005
Boundary for River Rch & Prof#=UNT0204 IN SAND ,Reach-1,5
Up Type=0
Dn Type=3
Dn Slope=0.005
Boundary for River Rch & Prof#=UNT0204 IN SAND ,Reach-1,6
Up Type=0
Dn Type=3
Dn Slope=0.005
Boundary for River Rch & Prof#=UNT0204 IN SAND ,Reach-1,7
Up Type=0
Dn Type=3
Dn Slope=0.005

--- UNT0204 IN SAND CR.g01 (geometry) ---

Geom Title=Existing Conditions
Program Version=4.10

River Reach=UNT0204 IN SAND ,Reach-1
Reach XY= 30
      3566722.27     10428035.21      3566441.12     10428455.74
      3566244.77     10428610.42       3566221.4     10428774.31
      3566099.19      10428952.6       3566061.4     10429626.64
      3566097.42     10429873.17      3565706.34     10430392.43
      3565723.34     10430602.04      3566004.13     10430889.55
      3565938.27     10431110.29      3565164.83     10431275.41
      3564731.15     10431559.41       3564619.6     10431567.03
       3564549.8     10431819.96      3564443.02     10431845.13
      3564413.08     10432036.75       3564355.4     10432087.49
      3564071.92     10432101.86      3563955.27     10432447.63
      3563869.25     10432447.29      3563766.32     10432303.86
       3563612.4     10432262.42      3563522.49     10432349.84
      3563461.15     10432253.46      3563402.18     10432261.95
      3563365.17     10432340.24      3563488.12     10432474.56
      3563240.17     10432625.32      3563172.11     10432911.64

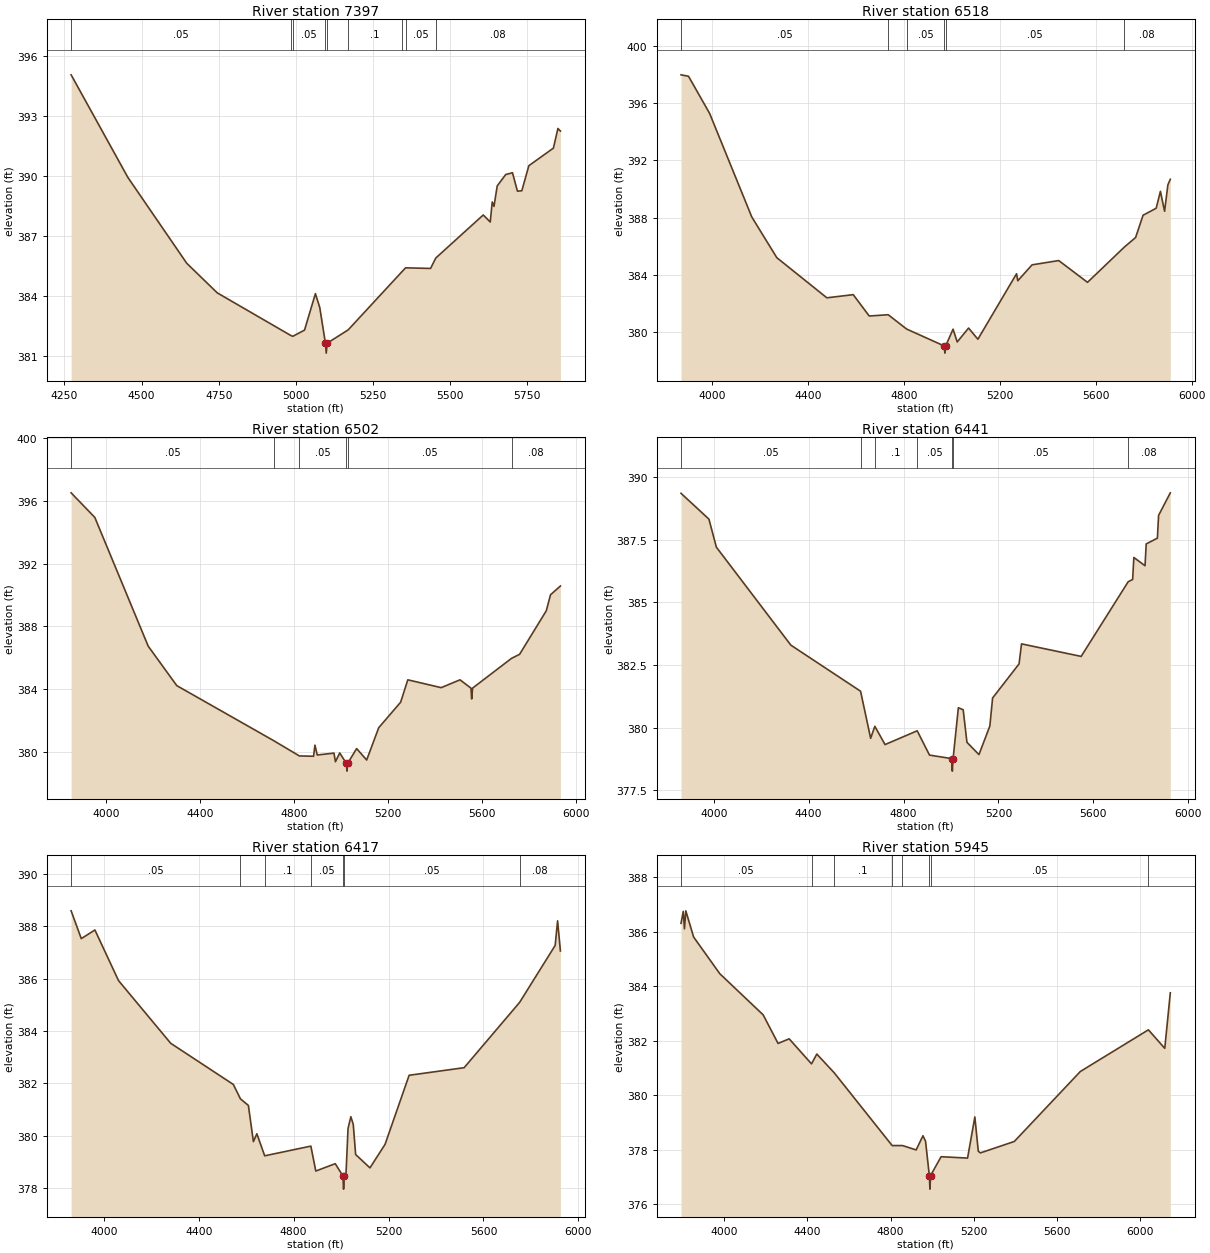
Type RM Length L Ch R = 1 ,7397    ,879,879,879
BEGIN DESCRIPTION:
UNT0204 IN SAND CR 12.0
END DESCRIPTION:
XS GIS Cut Line= 3
      3565792.14     10428041.68      3566392.99     10428639.69
      3567042.09     10428991.63
#Sta/Elev= 30
  4271.5  395.06  4455.3  389.94  4646.2  385.65  4745.2  384.17  4983.8  382.04
  4990.1     382  5028.1  382.31  5063.4  384.13  5077.5  383.44  5095.8  381.66
  5098.5  381.16  5101.8  381.66  5169.5  382.32  5343.5  385.22  5355.7  385.42
  5436.7  385.39  5453.6  385.91  5607.4  388.06  5630.1  387.71  5636.6  388.71
  5642.3  388.49  5652.7  389.51  5680.3  390.08  5702.2  390.17  5718.3  389.25
  5732.5  389.27  5755.2  390.52  5834.9   391.4  5849.5  392.38  5857.6  392.25
#Mann= 9 ,-1 , 0
  4271.5     .05       0  4983.8      .1       0  4990.1     .05       0
  5095.8     .03       0  5101.8     .05       0  5169.5      .1       0
  5343.5     .08       0  5355.7     .05       0  5453.6     .08       0
Bank Sta=5095.8,5101.8
XS Rating Curve= 0 ,0
Exp/Cntr=0.3,0.1

Type RM Length L Ch R = 1 ,6518    ,16,16,16
BEGIN DESCRIPTION:
UNT0204 IN SAND CR 10.1
END DESCRIPTION:
XS GIS Cut Line= 6
      3565051.87     10429090.83      3565694.23      10429431.1
      3565944.23     10429422.42      3566055.34     10429354.71
      3566461.59     10429260.96        3566972.     10429221.03
#Sta/Elev= 30
  3870.6  397.96  3901.8  397.86  3989.8  395.27  4165.7  388.04  4270.1   385.2
  4478.7   382.4  4588.7  382.62  4655.4  381.13  4734.5  381.22  4811.4  380.22
  4968.1  379.04  4970.9  378.54  4974.1  379.04    5005  380.21  5022.4  379.32
  5069.7  380.29  5108.5  379.51  5269.8  384.08    5275  383.59  5334.4   384.7
  5445.7     385  5565.7  383.48  5718.7  385.93  5766.3  386.61  5797.3  388.16
    5852  388.65  5869.7  389.83  5887.1  388.44  5900.8  390.28    5911  390.67
#Mann= 6 ,-1 , 0
  3870.6     .05       0  4734.5      .1       0  4811.4     .05       0
  4968.1     .03       0  4974.1     .05       0  5718.7     .08       0
Bank Sta=4968.1,4974.1
XS Rating Curve= 0 ,0
Exp/Cntr=0.3,0.1

Type RM Length L Ch R = 1 ,6502    ,61,61,61
BEGIN DESCRIPTION:
UNT0204 IN SAND CR 10.0
END DESCRIPTION:
XS GIS Cut Line= 6
      3565031.86     10429118.23      3565685.55     10429454.19
       3565947.7     10429444.99      3566067.49     10429366.86
      3566465.06     10429280.06      3566992.82     10429240.13
#Sta/Elev= 30
  3850.9  396.52  3951.8  394.95  4179.2  386.73  4300.9  384.21  4713.2   380.7
  4823.1  379.72  4883.6   379.7  4889.4  380.41  4899.3  379.78  4970.5   379.9
  4976.7  379.35    4995  379.91  5023.1  379.25  5025.8  378.75  5029.1  379.25
    5067  380.19  5109.8  379.46    5161  381.52  5254.4  383.15    5285  384.58
  5427.3  384.08  5507.3  384.58  5554.1  384.05    5557  383.36  5560.8  384.05
  5726.7  385.95  5761.2  386.21  5874.9  388.99  5892.8  390.01    5935  390.57
#Mann= 6 ,-1 , 0
  3850.9     .05       0  4713.2      .1       0  4823.1     .05       0
  5023.1     .03       0  5029.1     .05       0  5726.7     .08       0
Bank Sta=5023.1,5029.1
XS Rating Curve= 0 ,0
Exp/Cntr=0.3,0.1

Type RM Length L Ch R = 1 ,6441    ,24,24,24
BEGIN DESCRIPTION:
UNT0204 IN SAND CR 10.2
END DESCRIPTION:
XS GIS Cut Line= 6
      3564994.55     10429259.22      3565735.89     10429510.96
      3565998.05     10429476.24      3566225.48     10429366.86
      3566746.31     10429330.41      3566973.73     10429287.01
#Sta/Elev= 30
    3862  389.35  3979.6  388.32    4011   387.2  4324.9  383.29  4618.8  381.45
  4661.3  379.57  4678.9  380.05  4721.9  379.32  4857.5  379.87  4909.4   378.9
  5002.8  378.76  5005.5  378.26  5008.8  378.76    5031  380.79  5051.3  380.71
  5067.2  379.41  5117.8  378.92  5163.7  380.06  5175.3  381.18  5286.8  382.54
  5297.2  383.34  5548.6  382.84  5746.8  385.82  5765.6  385.91  5770.7  386.79
  5817.8  386.46  5822.8  387.33  5869.9  387.56    5875  388.47  5924.4  389.37
#Mann= 7 ,-1 , 0
    3862     .05       0  4618.8     .08       0  4678.9      .1       0
  4857.5     .05       0  5002.8     .03       0  5008.8     .05       0
  5746.8     .08       0
Bank Sta=5002.8,5008.8
XS Rating Curve= 0 ,0
Exp/Cntr=0.3,0.1

Type RM Length L Ch R = 1 ,6417    ,472,472,472
BEGIN DESCRIPTION:
UNT0204 IN SAND CR 10.3
END DESCRIPTION:
XS GIS Cut Line= 6
      3564994.59     10429283.54      3565735.89     10429535.27
      3565998.05     10429500.55      3566225.48     10429391.17
      3566746.31     10429354.71      3566973.77      10429311.3
#Sta/Elev= 30
  3861.9  388.58  3904.7  387.52  3962.2  387.85  4061.7  385.92  4281.7  383.53
  4545.7  381.96  4575.7  381.41  4609.1  381.16  4630.2  379.78  4644.8  380.08
  4677.8  379.24  4872.4  379.61  4893.2  378.66  4975.2  378.94  5007.6  378.47
  5010.3  377.97  5013.6  378.47  5020.7  378.58  5029.1  380.28    5041  380.73
  5051.1  380.44  5061.2  379.29  5121.5  378.78  5185.3  379.68  5286.6  382.31
  5518.5   382.6  5752.4  385.09  5902.2  387.26  5912.4   388.2  5924.3  387.05
#Mann= 7 ,-1 , 0
  3861.9     .05       0  4575.7     .08       0  4677.8      .1       0
  4872.4     .05       0  5007.6     .03       0  5013.6     .05       0
  5752.4     .08       0
Bank Sta=5007.6,5013.6
XS Rating Curve= 0 ,0
Exp/Cntr=0.3,0.1

Type RM Length L Ch R = 1 ,5945    ,25,25,25
BEGIN DESCRIPTION:
UNT0204 IN SAND CR 9.3
END DESCRIPTION:
XS GIS Cut Line= 6
      3565011.73     10429329.39      3566039.54     10429873.16
      3566102.91     10429938.26      3566139.36     10429926.11
      3566169.75      10429817.6      3567098.68     10429630.43
#Sta/Elev= 30
  3791.1  386.31  3801.9  386.75  3807.6  386.11  3814.2  386.77  3851.6  385.81
  3977.9  384.46  4186.7  382.95  4258.4   381.9  4311.9  382.07  4419.6  381.15
  4445.1  381.51  4529.1  380.82  4807.9  378.15  4857.7  378.15  4923.5  377.99
  4956.3  378.51  4968.7  378.31    4987  377.05  4989.8  376.55    4993  377.05
  5043.6  377.74  5171.1  377.69  5206.2   379.2  5222.8  377.94    5233  377.88
  5396.2   378.3  5714.3  380.87    6042   382.4  6120.9  381.72  6147.6  383.76
#Mann= 8 ,-1 , 0
  3791.1     .05       0  4419.6     .08       0  4529.1      .1       0
  4807.9     .08       0  4857.7     .05       0    4987     .03       0
    4993     .05       0    6042     .08       0
Bank Sta=4987,4993
XS Rating Curve= 0 ,0
Exp/Cntr=0.3,0.1

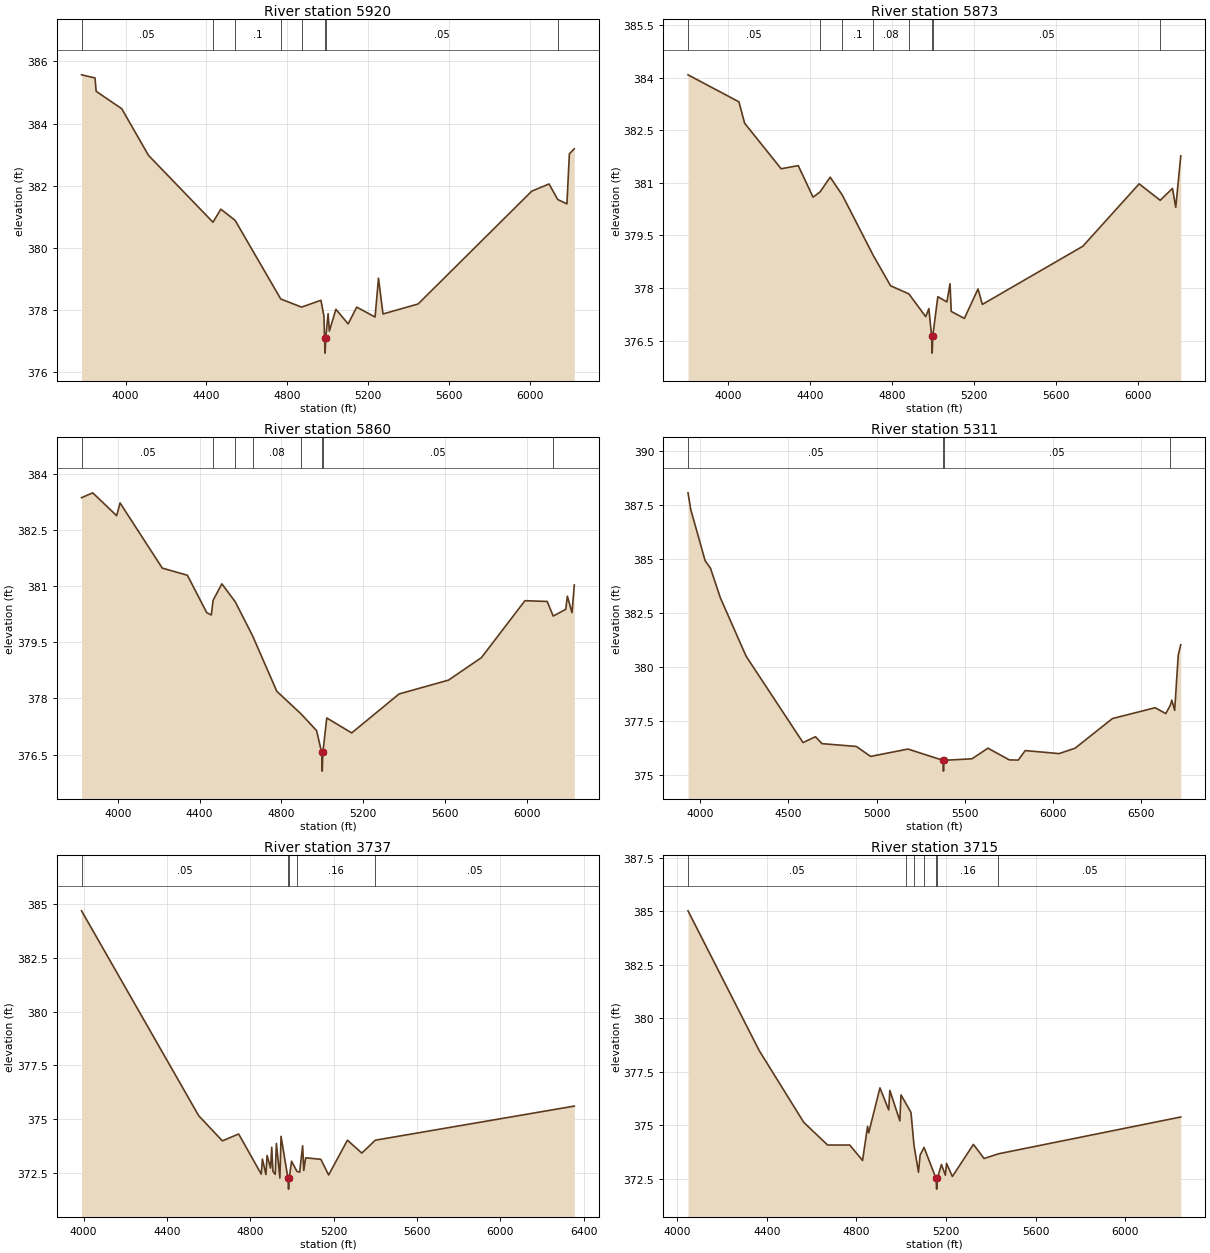
Type RM Length L Ch R = 1 ,5920    ,47,47,47
BEGIN DESCRIPTION:
UNT0204 IN SAND CR 9.0
END DESCRIPTION:
XS GIS Cut Line= 6
        3564992.     10429343.62      3566030.12     10429891.39
      3566113.45     10429986.44      3566159.03     10429947.38
      3566160.33     10429861.44       3567127.8     10429661.05
#Sta/Elev= 30
  3782.8  385.57  3849.3  385.47    3855  385.04  3981.5  384.48  4113.6  382.98
  4432.2  380.83    4471  381.25  4541.7  380.89  4767.2  378.36  4870.1   378.1
  4965.7  378.32  4980.3  377.82  4983.5  377.12  4986.3  376.62  4989.5  377.12
  5001.1  377.89  5007.3  377.33  5039.7  378.03  5100.2  377.56  5142.5   378.1
  5233.2  377.78  5250.1  379.03  5272.4  377.88  5445.7   378.2  6007.6  381.83
    6093  382.06  6135.8  381.56  6181.2  381.42  6193.3  383.03  6217.7  383.19
#Mann= 8 ,-1 , 0
  3782.8     .05       0  4432.2     .08       0  4541.7      .1       0
  4767.2     .08       0  4870.1     .05       0  4983.5     .03       0
  4989.5     .05       0  6135.8     .08       0
Bank Sta=4983.5,4989.5
XS Rating Curve= 0 ,0
Exp/Cntr=0.3,0.1

Type RM Length L Ch R = 1 ,5873    ,13,13,13
BEGIN DESCRIPTION:
UNT0204 IN SAND CR 9.1
END DESCRIPTION:
XS GIS Cut Line= 6
      3564988.64     10429392.68      3565993.53     10429899.72
        3566099.     10430040.35       3566161.5     10430026.02
      3566209.68      10429951.8      3567141.93     10429772.12
#Sta/Elev= 30
  3802.6  384.08  4051.4  383.31  4079.3   382.7  4257.7   381.4  4341.3  381.49
  4413.8  380.59  4448.1  380.74  4497.4  381.16  4556.6  380.65  4707.7  378.93
  4792.9  378.06  4882.2  377.83  4964.4  377.18  4979.8  377.41    4993  376.64
  4995.8  376.14    4999  376.64  5023.6  377.75  5067.9   377.6  5083.2  378.12
  5089.1  377.33  5153.2  377.13  5220.1  377.97  5241.2  377.53  5732.5  379.19
  6007.5  380.97  6110.4   380.5  6170.4  380.84  6186.4   380.3    6211  381.77
#Mann= 8 ,-1 , 0
  3802.6     .05       0  4448.1     .08       0  4556.6      .1       0
  4707.7     .08       0  4882.2     .05       0    4993     .03       0
    4999     .05       0  6110.4     .08       0
Bank Sta=4993,4999
XS Rating Curve= 0 ,0
Exp/Cntr=0.3,0.1

Type RM Length L Ch R = 1 ,5860    ,549,549,549
BEGIN DESCRIPTION:
UNT0204 IN SAND CR 9.2
END DESCRIPTION:
XS GIS Cut Line= 6
      3564989.95     10429421.32      3565994.83     10429928.37
       3566100.3     10430068.99       3566162.8     10430054.67
      3566210.98     10429980.45      3567143.24     10429800.77
#Sta/Elev= 30
  3823.1  383.36  3877.6  383.49  3994.7  382.88  4011.4  383.22  4217.7  381.48
  4340.3  381.29  4435.1  380.29  4457.4  380.23  4465.9  380.62  4508.8  381.06
  4574.4  380.58  4659.3  379.67  4777.6  378.19  4895.7  377.59    4972  377.14
  4996.6  376.56  4999.4  376.06  5002.6  376.56  5021.6  377.48  5143.4  377.08
  5374.9  378.12  5616.7  378.49  5777.5  379.09  5990.1  380.61  6098.9  380.59
  6128.4   380.2  6189.6  380.38  6197.6  380.73  6220.2  380.29  6231.5  381.03
#Mann= 8 ,-1 , 0
  3823.1     .05       0  4465.9     .08       0  4574.4      .1       0
  4659.3     .08       0  4895.7     .05       0  4996.6     .03       0
  5002.6     .05       0  6128.4     .08       0
Bank Sta=4996.6,5002.6
XS Rating Curve= 0 ,0
Exp/Cntr=0.3,0.1

Type RM Length L Ch R = 1 ,5311    ,1574,1574,1574
BEGIN DESCRIPTION:
UNT0204 IN SAND CR 8.0
END DESCRIPTION:
XS GIS Cut Line= 2
      3564645.41      10430284.4       3567416.3     10430622.94
#Sta/Elev= 30
  3931.4  388.06  3946.6   387.3  4028.1  384.93    4059  384.57  4114.6  383.21
  4260.5  380.51  4582.9  376.52  4653.4  376.79  4690.4  376.47  4885.1  376.34
  4965.7  375.88  5177.3  376.22  5375.8   375.7  5378.5   375.2  5381.8   375.7
    5540  375.77  5630.6  376.26  5751.5  375.72  5801.9  375.71  5841.8  376.15
  6033.6  376.01  6124.3  376.26  6335.8  377.63  6577.6  378.13  6638.1  377.86
  6663.9  378.25  6672.1  378.48  6688.4  378.01  6708.6  380.57  6722.9  381.04
#Mann= 4 ,-1 , 0
  3931.4     .05       0  5375.8     .03       0  5381.8     .05       0
  6663.9     .08       0
Bank Sta=5375.8,5381.8
XS Rating Curve= 0 ,0
Exp/Cntr=0.3,0.1

Type RM Length L Ch R = 1 ,3737    ,22,22,22
BEGIN DESCRIPTION:
UNT0204 IN SAND CR 7.0
END DESCRIPTION:
XS GIS Cut Line= 6
      3564760.31     10430442.42        3565302.      10431106.5
       3565254.8     10431200.68      3565240.69     10431280.98
      3565253.71     10431314.62      3566475.28     10431713.92
#Sta/Elev= 30
  3990.4   384.7  4552.8  375.15  4666.3  373.98  4744.5   374.3  4852.9  372.43
  4858.5  373.13  4875.3  372.41  4880.9   373.3  4897.6  372.71  4903.2  373.68
  4909.1  372.55    4920  372.42  4925.6  373.86  4942.3  372.25  4947.9  374.19
  4981.2  372.23  4983.9  371.73  4987.2  372.23  4998.3  373.03  5024.1  372.56
  5037.3  372.52  5051.5  373.75  5056.9   372.6  5066.1  373.19  5139.1  373.12
  5176.3  372.39  5266.6  374.01  5335.6  373.41  5400.2  374.01  6355.5   375.6
#Mann= 5 ,-1 , 0
  3990.4     .05       0  4981.2     .03       0  4987.2     .05       0
  5024.1     .16       0  5400.2     .05       0
Bank Sta=4981.2,4987.2
XS Rating Curve= 0 ,0
Exp/Cntr=0.3,0.1

Type RM Length L Ch R = 1 ,3715    ,47,47,47
BEGIN DESCRIPTION:
UNT0204 IN SAND CR 6.0
END DESCRIPTION:
XS GIS Cut Line= 4
      3564752.86      10430492.6      3565260.67     10431091.56
      3565211.19     10431325.93       3566323.2     10431706.15
#Sta/Elev= 30
  4048.5  385.02  4366.4  378.49  4565.2  375.14  4671.8  374.08  4770.6  374.08
  4827.8  373.36  4850.1  374.95  4855.2  374.65  4905.4  376.75  4944.5  375.72
  4949.6  376.63  4994.2  375.21  4999.4  376.42  5023.1  375.99    5044   375.6
  5057.4  374.07  5077.5  372.81  5084.8  373.61  5102.2  373.97  5155.8  372.52
  5158.6  372.02  5161.8  372.52  5179.9  373.17  5197.5  372.67  5202.7  373.22
  5228.8  372.61  5322.7  374.11  5370.2  373.45  5434.4  373.67  6248.5  375.39
#Mann= 7 ,-1 , 0
  4048.5     .05       0  5023.1     .16       0  5057.4     .05       0
  5102.2     .16       0  5155.8     .03       0  5161.8     .16       0
  5434.4     .05       0
Bank Sta=5155.8,5161.8
XS Rating Curve= 0 ,0
Exp/Cntr=0.3,0.1

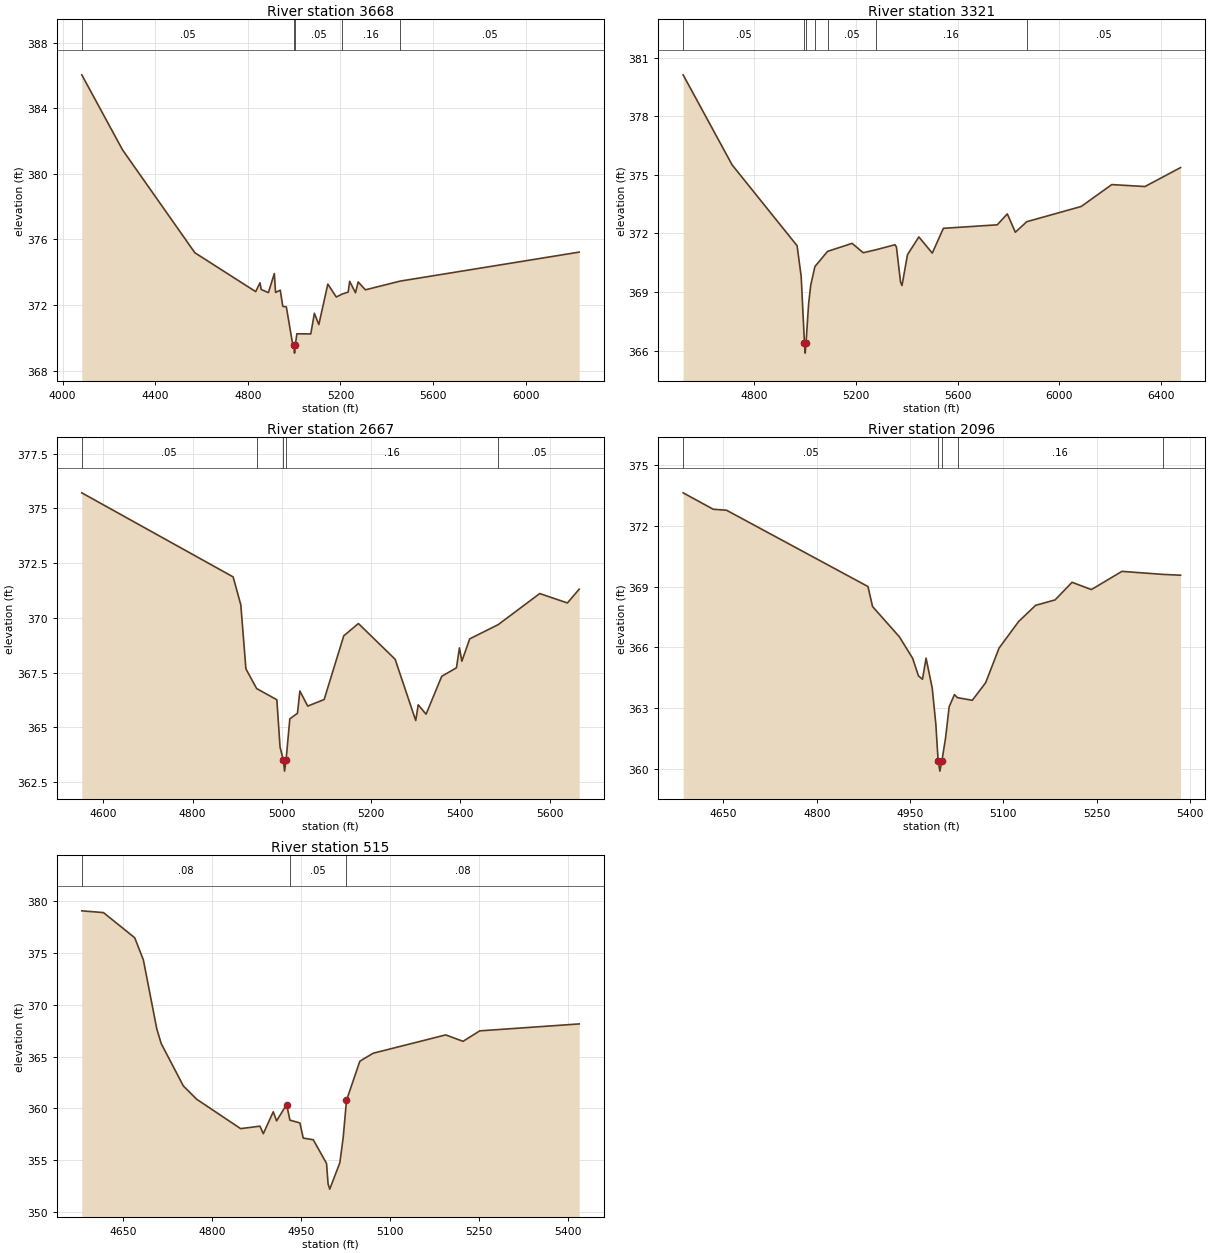
Type RM Length L Ch R = 1 ,3668    ,347,347,347
BEGIN DESCRIPTION:
UNT0204 IN SAND CR 5.0
END DESCRIPTION:
XS GIS Cut Line= 5
      3564725.92     10430539.11      3565219.07     10431125.38
        3565180.     10431236.06      3565184.34     10431357.58
      3566267.16     10431724.31
#Sta/Elev= 30
  4082.8  386.03    4259  381.45  4571.2  375.18  4833.9  372.81  4852.5  373.35
  4857.8  372.94  4888.7  372.75  4914.4  373.91  4919.7  372.76    4940   372.9
    4951  371.91  4966.3  371.88  4991.9  369.74  4998.9  369.56  5001.6  369.06
  5004.9  369.56  5011.9  370.24  5071.9  370.23  5087.4  371.49  5106.6   370.8
  5145.4  373.27  5182.1  372.48  5206.8  372.66  5233.3  372.78  5239.7  373.44
    5265  372.74  5276.4   373.4  5307.8  372.92  5457.3  373.45  6231.1  375.22
#Mann= 5 ,-1 , 0
  4082.8     .05       0  4998.9     .03       0  5004.9     .05       0
  5206.8     .16       0  5457.3     .05       0
Bank Sta=4998.9,5004.9
XS Rating Curve= 0 ,0
Exp/Cntr=0.3,0.1

Type RM Length L Ch R = 1 ,3321    ,654,654,654
BEGIN DESCRIPTION:
UNT0204 IN SAND CR 4.0
END DESCRIPTION:
XS GIS Cut Line= 3
      3564643.42     10431009.09       3565255.4     10432120.19
      3565907.31     10432342.64
#Sta/Elev= 30
  4519.7  380.12  4712.4  375.51  4968.1  371.37  4984.2   369.8  4997.2  366.37
    5000  365.87  5003.2  366.37  5013.5   368.4    5022  369.36  5038.2   370.3
    5088  371.08  5184.8  371.49  5228.4  371.01  5277.7  371.16  5353.4  371.42
  5359.1   371.3  5375.2  369.51  5380.9  369.33  5402.6  370.91  5447.3  371.82
  5500.1  370.99  5543.7  372.26  5755.8  372.44  5795.3     373    5827  372.06
  5871.9   372.6  6086.3  373.38  6206.4   374.5    6337   374.4    6477  375.37
#Mann= 7 ,-1 , 0
  4519.7     .05       0  4997.2     .03       0  5003.2     .05       0
  5038.2     .16       0    5088     .05       0  5277.7     .16       0
  5871.9     .05       0
Bank Sta=4997.2,5003.2
XS Rating Curve= 0 ,0
Exp/Cntr=0.3,0.1

Type RM Length L Ch R = 1 ,2667    ,571,571,571
BEGIN DESCRIPTION:
UNT0204 IN SAND CR 3.0
END DESCRIPTION:
XS GIS Cut Line= 2
      3564287.51     10431417.06      3564747.34     10432432.16
#Sta/Elev= 30
  4551.9  375.71    4891  371.87  4908.2  370.59  4919.6  367.67  4943.7  366.77
  4988.9  366.26  4996.1   364.1  5003.5   363.5  5006.2     363  5009.5   363.5
    5018  365.39  5035.1  365.64  5040.5  366.66  5058.1  365.97  5094.9  366.27
  5138.8  369.18  5171.7  369.74  5253.9  368.11  5300.1  365.31  5305.6  366.03
  5323.2   365.6  5358.3  367.33  5391.3  367.72    5398  368.63  5403.4  368.02
    5421  369.04  5484.8  369.69  5577.9  371.11  5639.9  370.68  5666.3  371.31
#Mann= 5 ,-1 , 0
  4551.9     .05       0  4943.7     .16       0  5003.5     .07       0
  5009.5     .16       0  5484.8     .05       0
Bank Sta=5003.5,5009.5
XS Rating Curve= 0 ,0
Exp/Cntr=0.3,0.1

Type RM Length L Ch R = 1 ,2096    ,1581,1581,1581
BEGIN DESCRIPTION:
UNT0204 IN SAND CR 2.0
END DESCRIPTION:
XS GIS Cut Line= 2
      3563892.54     10431725.21      3564296.19     10432415.33
#Sta/Elev= 30
  4585.2  373.64  4633.5  372.83    4655  372.78  4882.3  369.01  4889.7  368.02
  4932.7  366.53  4954.2  365.46  4963.4   364.6  4969.9  364.43  4975.7  365.47
  4985.6  363.99  4991.4  362.21  4995.1  360.39  4997.9  359.89  5001.1  360.39
    5007  361.52  5012.8  363.07  5021.3  363.67  5026.2  363.52    5050  363.39
  5071.5  364.26    5093  365.97  5124.4  367.28  5151.7  368.08  5183.1  368.35
  5210.3  369.22  5241.4  368.86  5290.5  369.76  5356.3  369.61  5384.7  369.57
#Mann= 5 ,-1 , 0
  4585.2     .05       0  4995.1     .04       0  5001.1     .05       0
  5026.2     .16       0  5356.3      .1       0
Bank Sta=4995.1,5001.1
XS Rating Curve= 0 ,0
Exp/Cntr=0.3,0.1

Type RM Length L Ch R = 1 ,515     ,0,0,0
BEGIN DESCRIPTION:
UNT0204 IN SAND CR 1.0
END DESCRIPTION:
XS GIS Cut Line= 2
      3563042.09     10432341.63      3563793.83     10432712.63
#Sta/Elev= 30
  4580.2  379.07  4616.7   378.9  4669.4  376.47    4684  374.33  4706.5   367.7
    4714  366.26  4751.4  362.16  4773.8  360.88  4847.9  358.04  4880.5  358.28
  4886.1  357.55  4902.9  359.67  4908.5  358.79  4925.4  360.37    4931  358.86
  4947.8  358.59  4953.4  357.13  4970.3  356.97  4992.7  354.68  4995.3   352.7
  4998.1   352.2  5015.1  354.75  5020.8   357.2  5026.3  360.76  5048.8  364.55
  5071.2  365.32  5193.5  367.09  5222.8  366.47  5250.8  367.48  5418.5  368.15
#Mann= 3 ,-1 , 0
  4580.2     .08       0    4931     .05       0  5026.3     .08       0
Bank Sta=4925.4,5026.3
XS Rating Curve= 0 ,0
Exp/Cntr=0.3,0.1

Chan Stop Cuts=-1
Use User Specified Reach Order=0
Composite Channel Slope=5