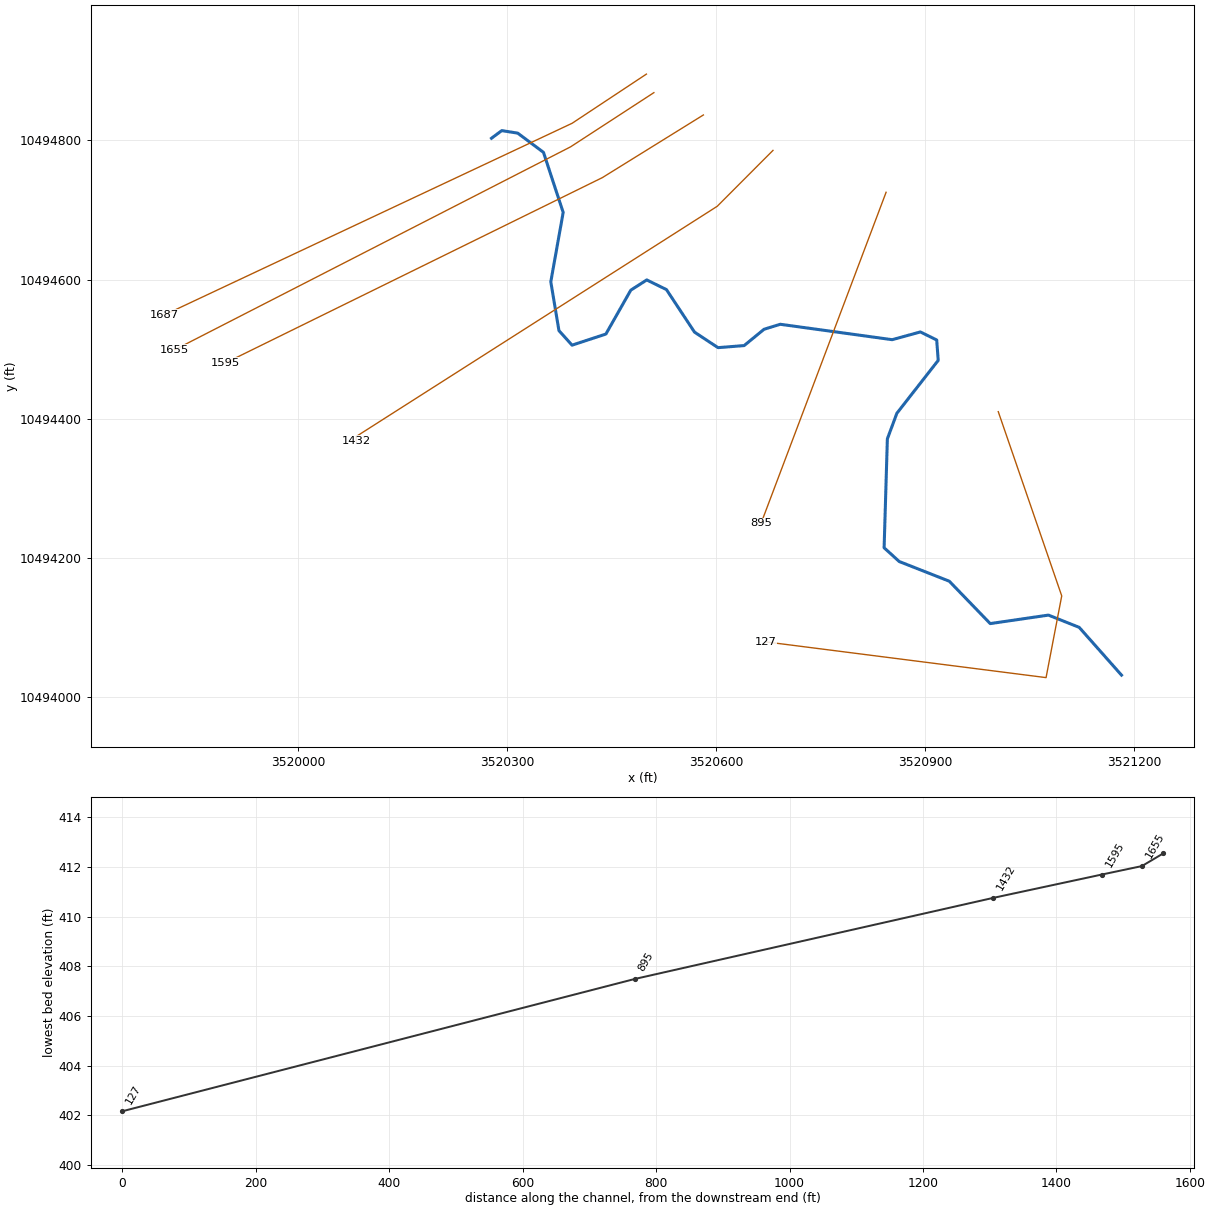
--- UNT02049 IN SAND CR.prj (project) ---

Proj Title=UNT02049 IN SAND CR Base Level Engineering
Current Plan=p01
Default Exp/Contr=0.3,0.1
English Units
Geom File=g01
Flow File=f01
Plan File=p01
Y Axis Title=Elevation
X Axis Title(PF)=Main Channel Distance
X Axis Title(XS)=Station
BEGIN DESCRIPTION:
UNT02049 IN SAND CR
END DESCRIPTION:
DSS Export Rating Curves= 0
DSS Export Rating Curve Sorted= 0
DSS Export Volume Flow Curves= 0
DXF OffsetX= 0
DXF OffsetY= 0
DXF ScaleX= 1
DXF ScaleY= 10

--- UNT02049 IN SAND CR.p01 (plan) ---

Plan Title=Multiple Run
Short Identifier=Multiple
Geom File=g01
Flow File=f01
Subcritical Flow
K Sum by GR= 0
Std Step Tol= 0.01
Critical Tol= 0.01
Num of Std Step Trials= 20
Max Error Tol= 0.3
Flow Tol Ratio= 0.001
Split Flow NTrial= 30
Split Flow Tol= 0.02
Split Flow Ratio= 0.02
Log Output Level= 0
Friction Slope Method= 1
Unsteady Friction Slope Method= 2
Unsteady Bridges Friction Slope Method= 1
Parabolic Critical Depth
Global Vel Dist=  1 , 1 , 1
Global Log Level= 0
CheckData=True
Encroach Param= -1, 0, 0, 0
BEGIN DESCRIPTION:
Multiple Run
END DESCRIPTION:

--- UNT02049 IN SAND CR.f01 (steady flow) ---

Flow Title=Multiple
Number of Profiles=7
Profile Names=10-year,25-year,50-year,1pct_min,100-year,1pct_plu,500-year
River Rch & RM= UNT02049 IN SAND,Reach-1,1687
     412     534     630     544     735     995     997
Boundary for River Rch & Prof#=UNT02049 IN SAND,Reach-1,1
Up Type=0
Dn Type=3
Dn Slope=0.005
Boundary for River Rch & Prof#=UNT02049 IN SAND,Reach-1,2
Up Type=0
Dn Type=3
Dn Slope=0.005
Boundary for River Rch & Prof#=UNT02049 IN SAND,Reach-1,3
Up Type=0
Dn Type=3
Dn Slope=0.005
Boundary for River Rch & Prof#=UNT02049 IN SAND,Reach-1,4
Up Type=0
Dn Type=3
Dn Slope=0.005
Boundary for River Rch & Prof#=UNT02049 IN SAND,Reach-1,5
Up Type=0
Dn Type=3
Dn Slope=0.005
Boundary for River Rch & Prof#=UNT02049 IN SAND,Reach-1,6
Up Type=0
Dn Type=3
Dn Slope=0.005
Boundary for River Rch & Prof#=UNT02049 IN SAND,Reach-1,7
Up Type=0
Dn Type=3
Dn Slope=0.005

--- UNT02049 IN SAND CR.g01 (geometry) ---

Geom Title=Existing Conditions
Program Version=4.10

River Reach=UNT02049 IN SAND,Reach-1
Reach XY= 30
      3520277.33     10494803.22      3520292.09     10494814.21
        3520315.     10494810.57      3520351.98     10494782.96
      3520380.29     10494696.66      3520362.51     10494596.92
      3520374.22     10494526.76      3520392.99     10494505.84
      3520441.63     10494521.83      3520477.37     10494584.88
      3520500.32     10494599.59      3520528.59     10494585.72
      3520568.91     10494524.58      3520602.63     10494502.28
      3520640.21     10494505.24      3520668.74     10494528.69
      3520692.04     10494535.87      3520852.78     10494513.72
      3520893.27     10494524.85      3520916.72     10494513.28
      3520918.88     10494483.96      3520859.52     10494407.98
      3520845.87     10494371.18       3520841.2     10494214.65
      3520862.92      10494194.9       3520934.8      10494166.6
      3520993.58     10494105.69      3521077.19     10494117.89
      3521121.36     10494100.28      3521182.11     10494031.64

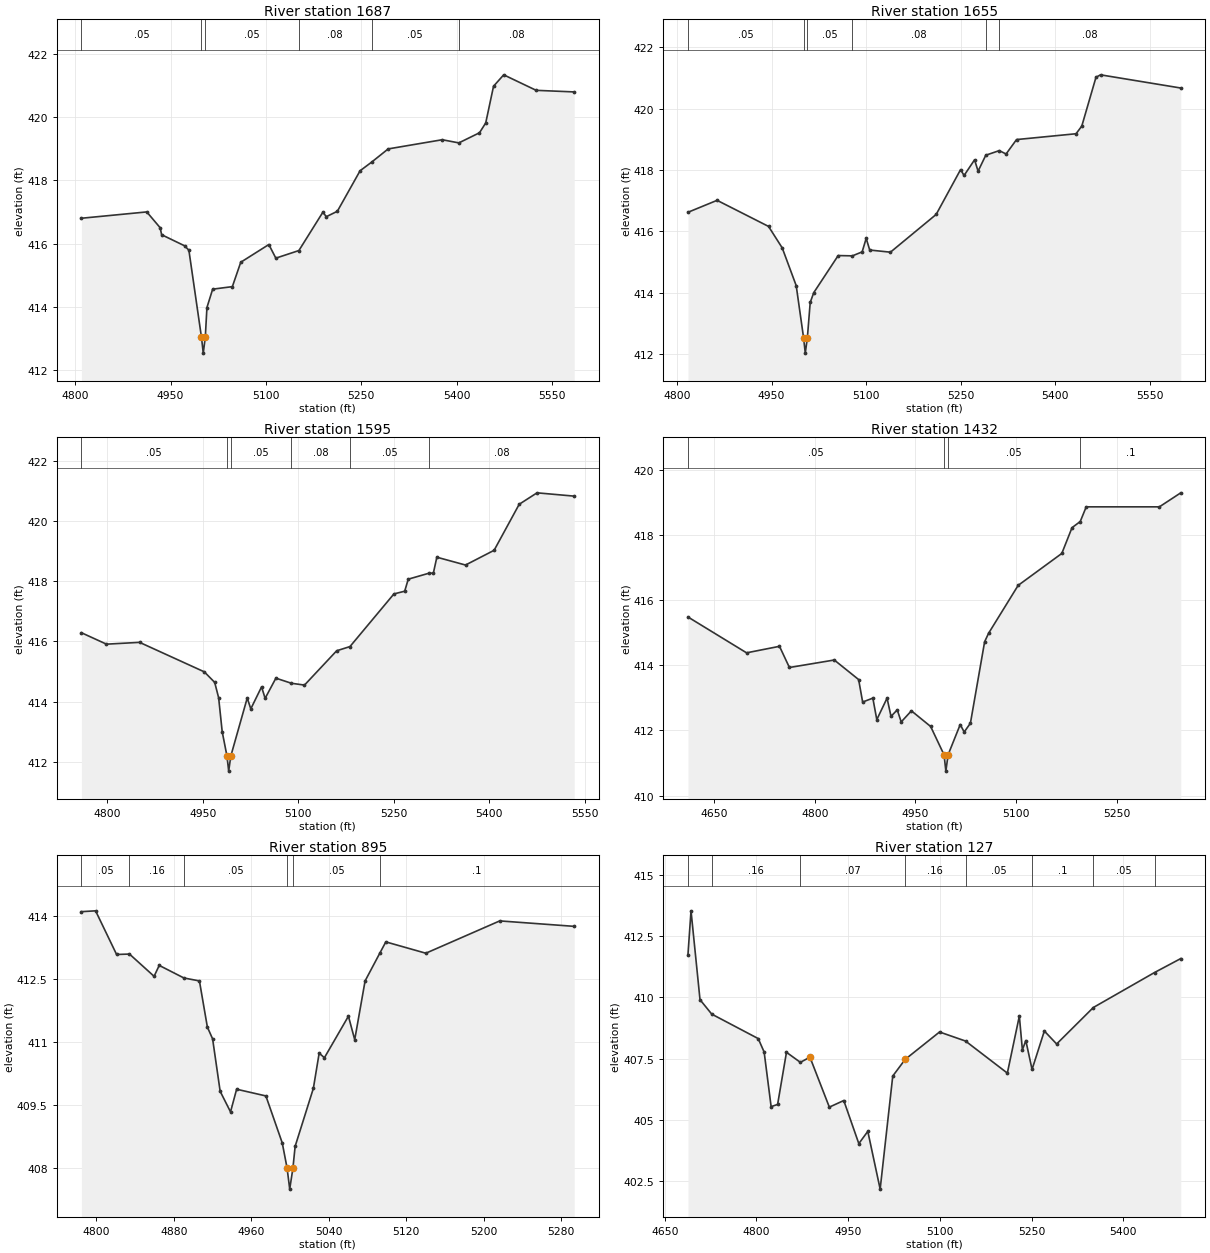
Type RM Length L Ch R = 1 ,1687    ,32,32,32
BEGIN DESCRIPTION:
UNT02049 IN SAND CK 3.0
END DESCRIPTION:
XS GIS Cut Line= 3
      3520499.81     10494895.42      3520393.15     10494824.76
      3519807.18     10494549.14
#Sta/Elev= 30
  4809.7   416.8  4912.5     417  4933.6   416.5  4935.9  416.28    4972  415.93
  4978.8  415.79  4998.6  413.04  5001.4  412.54  5004.6  413.04  5007.2  413.98
  5016.2  414.56  5047.2  414.64  5060.4  415.41  5104.6  415.97  5115.6  415.54
  5151.9  415.78  5189.6  416.99  5195.1  416.85  5212.4  417.02  5248.2   418.3
  5266.2  418.57  5292.4  418.99  5377.5  419.28  5403.6  419.18  5436.1   419.5
  5445.9  419.81  5458.2  420.97  5474.2  421.33  5525.3  420.84  5585.2  420.79
#Mann= 6 ,-1 , 0
  4809.7     .05       0  4998.6     .04       0  5004.6     .05       0
  5151.9     .08       0  5266.2     .05       0  5403.6     .08       0
Bank Sta=4998.6,5004.6
XS Rating Curve= 0 ,0
Exp/Cntr=0.3,0.1

Type RM Length L Ch R = 1 ,1655    ,60,60,60
BEGIN DESCRIPTION:
UNT02049 IN SAND CK 2.0
END DESCRIPTION:
XS GIS Cut Line= 3
      3520510.54     10494868.76      3520390.98     10494790.91
       3519822.4     10494499.24
#Sta/Elev= 30
  4817.3  416.62  4863.5  417.01  4945.1  416.16  4966.8  415.46    4989  414.23
  5000.7  412.53  5003.4  412.03  5006.7  412.53  5011.2  413.68  5016.8     414
  5055.6  415.21  5078.1   415.2  5093.6  415.33    5100  415.77  5105.6  415.39
  5138.5  415.32    5211  416.55  5249.7  418.01  5255.3  417.82  5271.9  418.33
  5277.5  417.96  5289.7  418.48  5311.1  418.63  5321.9  418.52  5338.5  418.99
  5432.9  419.18    5442  419.43  5464.5  421.02  5471.7   421.1    5599  420.67
#Mann= 6 ,-1 , 0
  4817.3     .05       0  5000.7     .04       0  5006.7     .05       0
  5078.1     .08       0  5289.7     .05       0  5311.1     .08       0
Bank Sta=5000.7,5006.7
XS Rating Curve= 0 ,0
Exp/Cntr=0.3,0.1

Type RM Length L Ch R = 1 ,1595    ,163,163,163
BEGIN DESCRIPTION:
UNT02049 IN SAND CK 1.0
END DESCRIPTION:
XS GIS Cut Line= 3
      3520581.65      10494836.7      3520436.55     10494746.64
      3519895.56     10494480.47
#Sta/Elev= 30
  4759.5  416.29  4798.8  415.91  4850.8  415.97  4952.4  414.99  4968.7  414.64
  4974.9  414.13  4980.5     413    4988  412.19  4990.7  411.69    4994  412.19
  5019.8  414.12  5025.4  413.76  5042.3  414.49  5047.9  414.11  5064.8  414.78
  5089.2  414.61  5109.7  414.55  5160.2  415.69  5181.1  415.83  5250.1  417.58
    5267  417.67  5272.6  418.07  5305.4  418.27    5312  418.27  5317.5   418.8
  5362.5  418.54  5407.4  419.03  5446.8  420.56  5474.8  420.94  5533.2  420.83
#Mann= 6 ,-1 , 0
  4759.5     .05       0    4988    .035       0    4994     .05       0
  5089.2     .08       0  5181.1     .05       0  5305.4     .08       0
Bank Sta=4988,4994
XS Rating Curve= 0 ,0
Exp/Cntr=0.3,0.1

Type RM Length L Ch R = 1 ,1432    ,537,537,537
BEGIN DESCRIPTION:
UNT02049 IN SAND CK 4.0
END DESCRIPTION:
XS GIS Cut Line= 4
       3520681.6     10494785.79      3520601.49     10494705.41
       3520083.1     10494374.62       3520083.1     10494368.15
#Sta/Elev= 30
  4610.9  415.48  4698.3  414.38  4747.4  414.58  4762.2  413.93  4829.1  414.16
  4865.4  413.56  4871.4  412.87  4886.6  412.99  4892.5  412.33  4907.8  412.99
  4913.7  412.43    4923  412.63  4928.9  412.26  4944.1   412.6  4972.8  412.12
  4992.8  411.25  4995.5  410.75  4998.8  411.25  5016.9  412.18  5022.8  411.95
  5032.1  412.22  5053.3  414.72  5059.2  414.98  5103.3  416.45  5168.4  417.43
  5183.6  418.22  5195.9  418.41  5204.8  418.86  5313.9  418.86  5345.8  419.29
#Mann= 4 ,-1 , 0
  4610.9     .05       0  4992.8    .035       0  4998.8     .05       0
  5195.9      .1       0
Bank Sta=4992.8,4998.8
XS Rating Curve= 0 ,0
Exp/Cntr=0.3,0.1

Type RM Length L Ch R = 1 ,895     ,768,768,768
BEGIN DESCRIPTION:
UNT02049 IN SAND CK 6.0
END DESCRIPTION:
XS GIS Cut Line= 2
      3520844.04     10494725.58      3520664.41     10494249.65
#Sta/Elev= 30
  4784.7   414.1  4799.3  414.12    4821  413.08  4834.3  413.09  4859.7  412.56
    4865  412.82  4890.5  412.52  4906.5  412.45  4914.7  411.35  4920.1  411.07
  4927.9  409.82  4938.6  409.33  4944.9  409.87  4975.1  409.71    4992  408.59
    4997  407.99  4999.7  407.49    5003  407.99  5005.3  408.51  5024.1  409.89
  5030.1  410.73  5035.5  410.62  5060.3  411.61  5066.8  411.05  5077.5  412.45
  5092.9  413.12  5098.9  413.38  5140.2  413.11  5216.5  413.88  5293.4  413.75
#Mann= 6 ,-1 , 0
  4784.7     .05       0  4834.3     .16       0  4890.5     .05       0
    4997    .035       0    5003     .05       0  5092.9      .1       0
Bank Sta=4997,5003
XS Rating Curve= 0 ,0
Exp/Cntr=0.3,0.1

Type RM Length L Ch R = 1 ,127     ,0,0,0
BEGIN DESCRIPTION:
UNT02049 IN SAND CK 5.0
END DESCRIPTION:
XS GIS Cut Line= 4
      3521005.13     10494410.28      3521096.28     10494145.51
      3521073.78     10494028.06      3520670.75      10494079.5
#Sta/Elev= 30
    4688  411.75    4693  413.54  4707.7  409.91  4726.9  409.32  4802.9  408.32
  4812.6  407.77    4824  405.54  4834.6  405.63  4849.1  407.76  4871.8  407.35
  4887.5  407.56  4919.2  405.52  4942.8  405.79  4967.4  404.03  4982.1  404.53
  5002.3  402.17  5022.9  406.79  5043.2  407.47  5099.4  408.59  5141.9  408.22
  5210.3  406.91  5229.9  409.24  5234.9  407.86  5240.5  408.24  5250.7  407.06
  5270.8  408.63  5290.9   408.1  5350.9  409.59    5451  411.02  5493.9  411.59
#Mann= 8 ,-1 , 0
    4688     .16       0  4726.9     .16       0  4871.8     .07       0
  5043.2     .16       0  5141.9     .05       0  5250.7      .1       0
  5350.9     .05       0    5451      .1       0
Bank Sta=4887.5,5043.2
XS Rating Curve= 0 ,0
Exp/Cntr=0.3,0.1

Chan Stop Cuts=-1
Use User Specified Reach Order=0
Composite Channel Slope=5