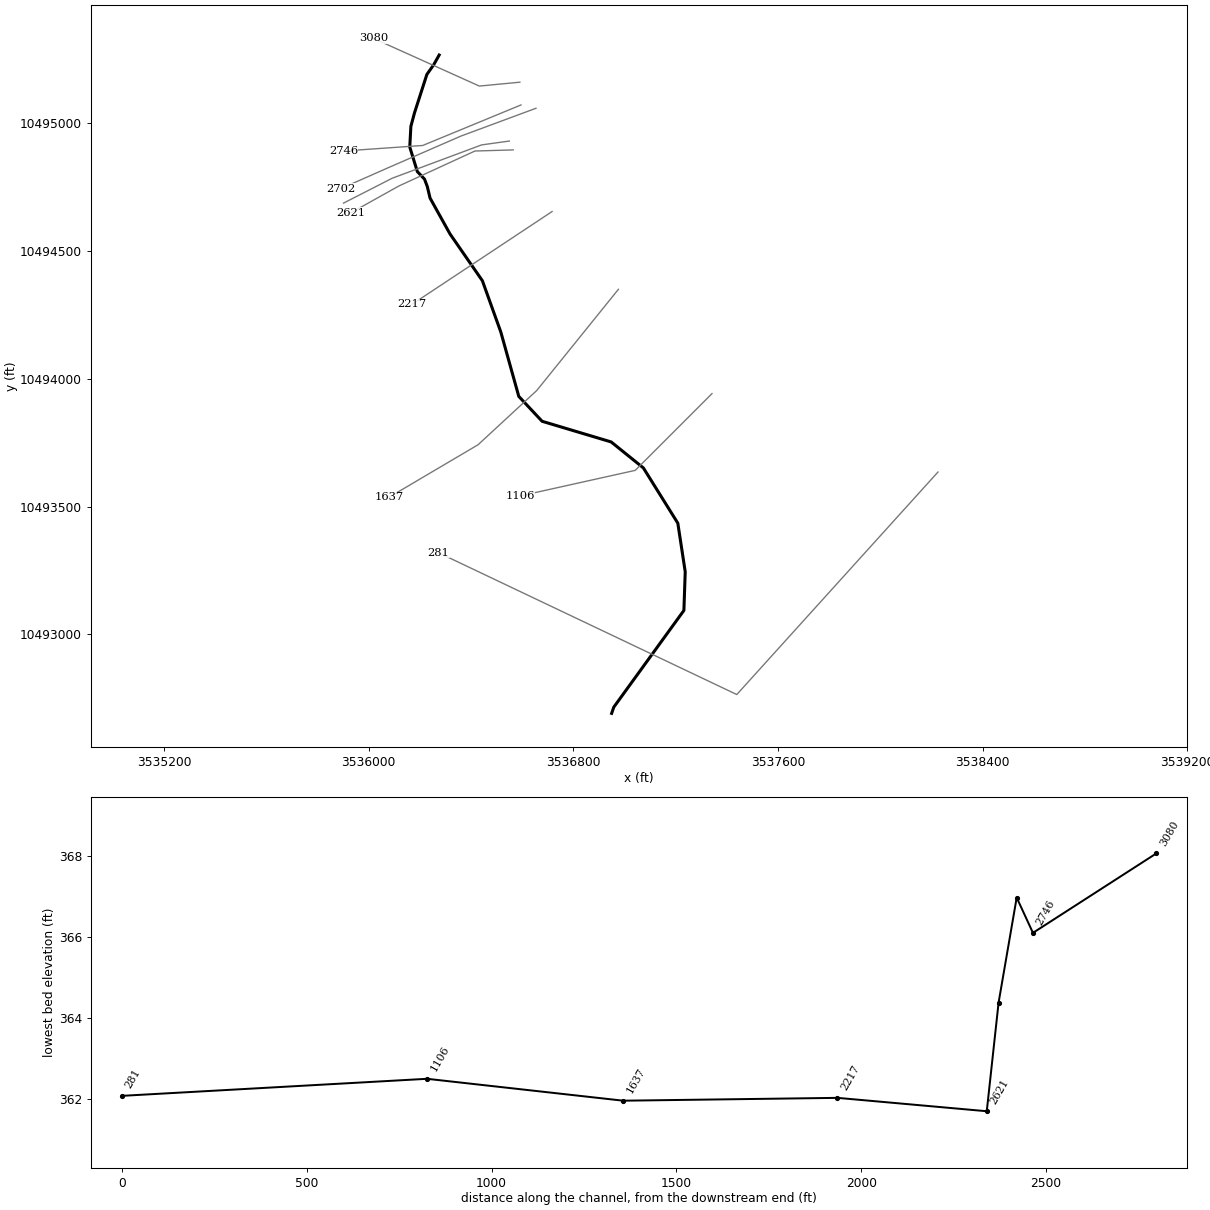
--- UNT02078 IN SAND CR.prj (project) ---

Proj Title=UNT02078 IN SAND CR Base Level Engineering
Current Plan=p01
Default Exp/Contr=0.3,0.1
English Units
Geom File=g01
Flow File=f01
Plan File=p01
BEGIN DESCRIPTION:
UNT02078 IN SAND CR
END DESCRIPTION:

--- UNT02078 IN SAND CR.p01 (plan) ---

Plan Title=Multiple Run
Short Identifier=Multiple
Geom File=g01
Flow File=f01
Subcritical Flow
K Sum by GR= 0
Std Step Tol= 0.01
Critical Tol= 0.01
Num of Std Step Trials= 20
Max Error Tol= 0.3
Flow Tol Ratio= 0.001
Split Flow NTrial= 30
Split Flow Tol= 0.02
Split Flow Ratio= 0.02
Log Output Level= 0
Friction Slope Method= 1
Unsteady Friction Slope Method= 2
Unsteady Bridges Friction Slope Method= 1
Parabolic Critical Depth
Global Vel Dist=  1 , 1 , 1
Global Log Level= 0
CheckData=True
Encroach Param= -1, 0, 0, 0
BEGIN DESCRIPTION:
Multiple Run
END DESCRIPTION:

--- UNT02078 IN SAND CR.f01 (steady flow) ---

Flow Title=Multiple
Number of Profiles=7
Profile Names=10-year,25-year,50-year,1pct_min,100-year,1pct_plu,500-year
River Rch & RM= UNT02078 IN SAND,Reach-1,3080
     338     427     494     417     564     763     734
Boundary for River Rch & Prof#=UNT02078 IN SAND,Reach-1,1
Up Type=0
Dn Type=3
Dn Slope=0.005
Boundary for River Rch & Prof#=UNT02078 IN SAND,Reach-1,2
Up Type=0
Dn Type=3
Dn Slope=0.005
Boundary for River Rch & Prof#=UNT02078 IN SAND,Reach-1,3
Up Type=0
Dn Type=3
Dn Slope=0.005
Boundary for River Rch & Prof#=UNT02078 IN SAND,Reach-1,4
Up Type=0
Dn Type=3
Dn Slope=0.005
Boundary for River Rch & Prof#=UNT02078 IN SAND,Reach-1,5
Up Type=0
Dn Type=3
Dn Slope=0.005
Boundary for River Rch & Prof#=UNT02078 IN SAND,Reach-1,6
Up Type=0
Dn Type=3
Dn Slope=0.005
Boundary for River Rch & Prof#=UNT02078 IN SAND,Reach-1,7
Up Type=0
Dn Type=3
Dn Slope=0.005

--- UNT02078 IN SAND CR.g01 (geometry) ---

Geom Title=Existing Conditions

River Reach=UNT02078 IN SAND,Reach-1
Reach XY= 22
      3536275.61     10495265.22      3536254.43     10495227.57
      3536227.53     10495189.38      3536178.91     10495038.33
      3536165.02     10494986.25      3536160.68     10494905.52
      3536190.26     10494809.62      3536218.31     10494780.14
      3536229.36     10494750.64      3536239.94     10494706.22
      3536317.80     10494566.11      3536444.54     10494382.95
      3536516.59     10494182.43      3536586.90     10493930.70
      3536678.05     10493833.47      3536948.01     10493752.74
      3537073.88     10493651.18      3537208.53     10493435.22
      3537237.51     10493245.09      3537232.30     10493094.05
      3536958.34     10492716.18      3536949.81     10492691.64

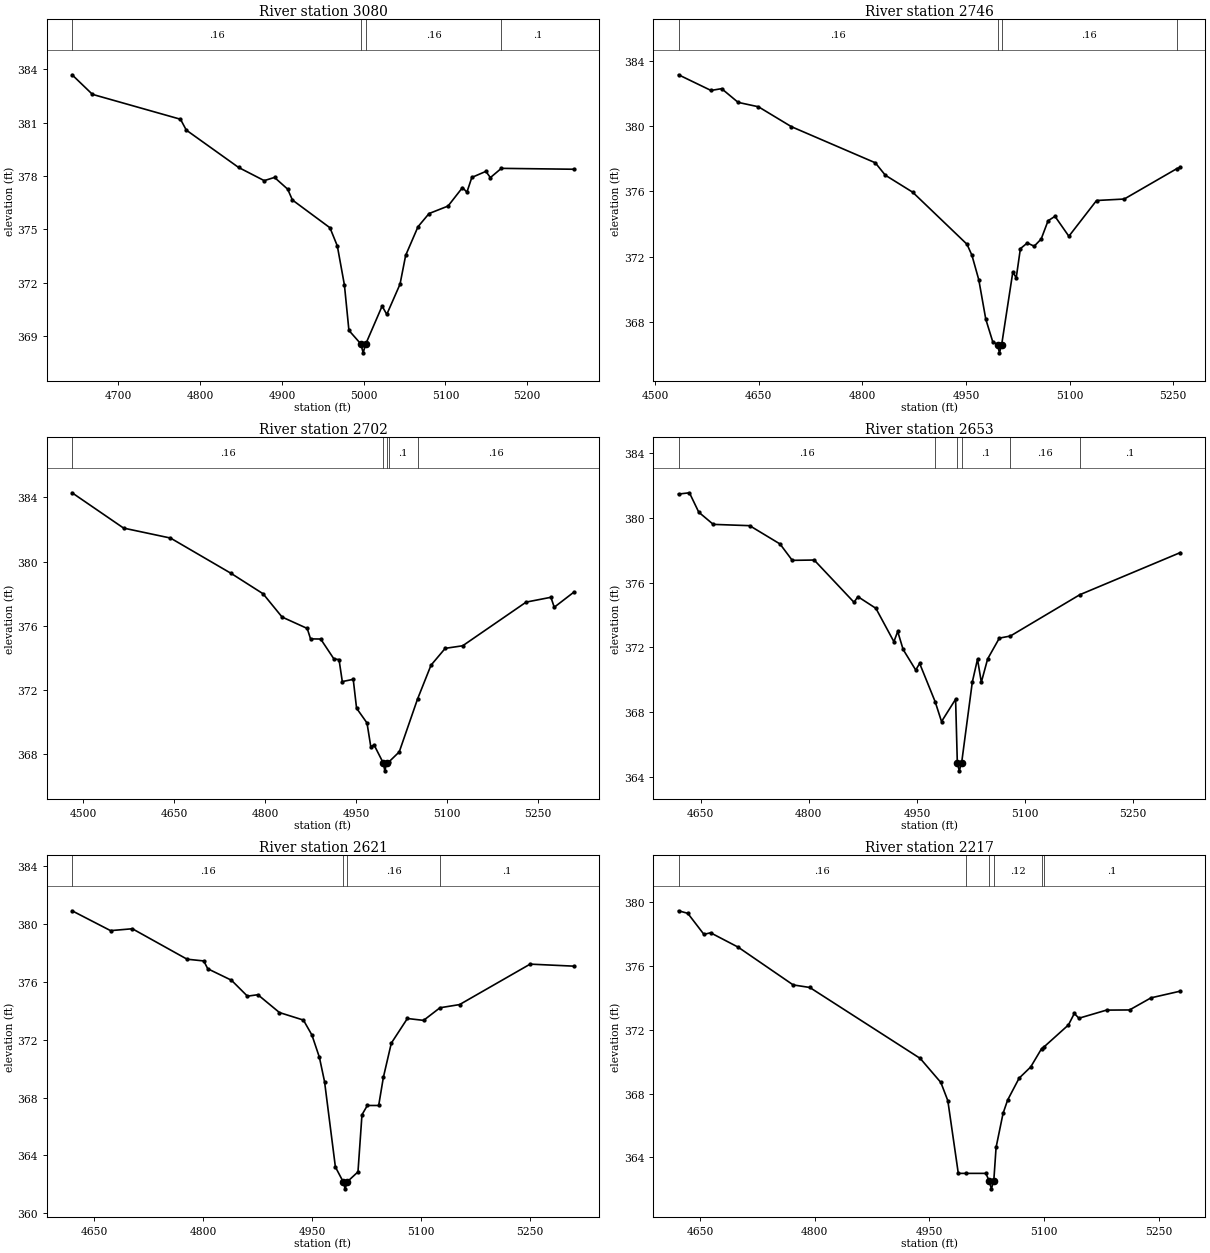
Type RM Length L Ch R = 1,3080,334,334,334
BEGIN DESCRIPTION:
UNT02078 IN SAND CR 6.2
END DESCRIPTION:
XS GIS Cut Line= 3
      3536591.18     10495159.09      3536432.74     10495143.90
      3536018.28     10495330.51
#Sta/Elev= 30
  4643.3  383.69  4668.2  382.59  4775.9  381.19  4783.0  380.58  4847.0  378.48
  4878.3  377.74  4890.9  377.92  4907.0  377.26  4912.8  376.65  4958.7  375.09
  4967.7  374.07  4976.4  371.87  4981.9  369.32  4996.5  368.56  4999.3  368.06
  5002.5  368.56  5022.5  370.69  5028.2  370.22  5044.4  371.92  5051.3  373.54
  5066.4  375.15  5079.9  375.89  5103.1  376.31  5120.8  377.35  5126.2  377.09
  5132.2  377.92  5149.4  378.26  5154.9  377.91  5168.3  378.43  5257.0  378.38
#Mann=4,-1,0
  4643.3    0.16       0  4996.5    0.07       0  5002.5    0.16       0
  5168.3     0.1       0
Bank Sta=4996.5,5002.5
Exp/Cntr=0.3,0.1

Type RM Length L Ch R = 1,2746,44,44,44
BEGIN DESCRIPTION:
UNT02078 IN SAND CR 6.1
END DESCRIPTION:
XS GIS Cut Line= 3
      3536595.52     10495070.12      3536211.38     10494911.70
      3535901.06     10494890.00
#Sta/Elev= 30
  4533.8  383.13  4580.8  382.17  4596.2  382.28  4620.1  381.44  4649.5  381.17
  4697.3  379.95  4818.7  377.74  4833.2  376.98  4872.8  375.94  4951.5  372.75
  4958.6  372.08  4968.6  370.57  4978.7  368.16  4988.7  366.79  4995.7  366.60
  4998.5  366.10  5001.7  366.60  5017.8  371.04  5022.8  370.70  5028.8  372.48
  5038.8  372.83  5048.8  372.63  5058.9  373.07  5068.9  374.19  5078.9  374.46
  5099.0  373.24  5139.1  375.43  5179.2  375.52  5255.3  377.38  5260.4  377.46
#Mann=4,-1,0
  4533.8    0.16       0  4995.7    0.07       0  5001.7    0.16       0
  5255.3    0.05       0
Bank Sta=4995.7,5001.7
Exp/Cntr=0.3,0.1

Type RM Length L Ch R = 1,2702,49,49,49
BEGIN DESCRIPTION:
UNT02078 IN SAND CR 6.0
END DESCRIPTION:
XS GIS Cut Line= 4
      3536654.08     10495057.09      3536361.12     10494948.59
      3536076.84     10494824.89      3535890.18     10494742.41
#Sta/Elev= 30
  4482.1  384.29  4567.0  382.09  4644.2  381.47  4744.0  379.27  4796.7  378.00
  4828.0  376.55  4869.4  375.84  4874.9  375.19  4891.6  375.18  4913.4  373.94
  4921.8  373.90  4927.2  372.53  4945.2  372.67  4950.7  370.87  4967.9  369.95
  4974.1  368.48  4979.6  368.58  4994.5  367.47  4997.3  366.97  5000.5  367.47
  5003.5  367.51  5021.0  368.15  5051.1  371.44  5073.3  373.55  5096.7  374.60
  5125.5  374.76  5230.0  377.48  5270.8  377.78  5276.3  377.16  5308.6  378.10
#Mann=5,-1,0
  4482.1    0.16       0  4994.5    0.07       0  5000.5    0.16       0
  5003.5     0.1       0  5051.1    0.16       0
Bank Sta=4994.5,5000.5
Exp/Cntr=0.3,0.1

Type RM Length L Ch R = 1,2653,32,32,32
BEGIN DESCRIPTION:
UNT02078 IN SAND CR 5.0
END DESCRIPTION:
XS GIS Cut Line= 4
      3536549.89     10494929.05      3536441.42     10494913.87
      3536092.03     10494783.66      3535901.66     10494686.31
#Sta/Elev= 30
  4619.3  381.46  4634.4  381.54  4647.4  380.34  4667.5  379.59  4718.0  379.51
  4760.1  378.38  4777.1  377.37  4807.5  377.39  4862.8  374.78  4868.1  375.13
  4893.1  374.41  4918.1  372.35  4923.4  372.98  4930.9  371.87  4948.4  370.60
  4953.8  371.01  4975.4  368.64  4984.2  367.42  5003.7  368.80  5006.1  364.88
  5008.8  364.38  5012.1  364.88  5026.9  369.86  5034.1  371.27  5039.4  369.85
  5048.2  371.29  5064.4  372.57  5079.7  372.70  5176.1  375.25  5315.5  377.85
#Mann=6,-1,0
  4619.3    0.16       0  4975.4     0.1       0  5006.1    0.07       0
  5012.1     0.1       0  5079.7    0.16       0  5176.1     0.1       0
Bank Sta=5006.1,5012.1
Exp/Cntr=0.3,0.1

Type RM Length L Ch R = 1,2621,404,404,404
BEGIN DESCRIPTION:
UNT02078 IN SAND CR 5.1
END DESCRIPTION:
XS GIS Cut Line= 4
      3536565.10     10494894.33      3536415.38     10494890.00
      3536118.07     10494753.28      3535931.40     10494649.09
#Sta/Elev= 30
  4619.3  380.88  4672.3  379.51  4702.3  379.64  4777.6  377.54  4800.6  377.42
  4806.1  376.88  4838.7  376.09  4860.7  374.99  4875.1  375.09  4904.8  373.86
  4937.8  373.34  4949.5  372.31  4959.8  370.77  4966.9  369.09  4981.8  363.21
  4992.4  362.20  4995.2  361.70  4998.4  362.20  5012.9  362.87  5018.4  366.81
  5025.8  367.45  5041.4  367.45  5047.9  369.40  5058.8  371.75  5080.9  373.45
  5103.2  373.32  5125.8  374.19  5152.8  374.41  5249.9  377.20  5310.1  377.06
#Mann=4,-1,0
  4619.3    0.16       0  4992.4    0.07       0  4998.4    0.16       0
  5125.8     0.1       0
Bank Sta=4992.4,4998.4
Exp/Cntr=0.3,0.1

Type RM Length L Ch R = 1,2217,580,580,580
BEGIN DESCRIPTION:
UNT02078 IN SAND CR 6.3
END DESCRIPTION:
XS GIS Cut Line= 2
      3536717.05     10494653.47      3536170.15     10494291.03
#Sta/Elev= 30
  4621.9  379.47  4634.0  379.31  4655.1  377.99  4663.8  378.09  4699.8  377.19
  4771.8  374.82  4793.5  374.66  4937.9  370.21  4964.9  368.70  4974.0  367.56
  4987.7  363.00  4997.6  363.00  5023.7  363.00  5028.1  362.53  5030.9  362.03
  5034.1  362.53  5037.1  364.63  5046.2  366.76  5052.2  367.60  5067.2  368.97
  5082.3  369.67  5096.7  370.83  5099.5  370.92  5131.7  372.31  5139.4  373.03
  5145.4  372.73  5181.5  373.24  5211.6  373.25  5239.7  374.01  5278.0  374.43
#Mann=6,-1,0
  4621.9    0.16       0  4997.6    0.12       0  5028.1    0.07       0
  5034.1    0.12       0  5096.7    0.16       0  5099.5     0.1       0
Bank Sta=5028.1,5034.1
Exp/Cntr=0.3,0.1

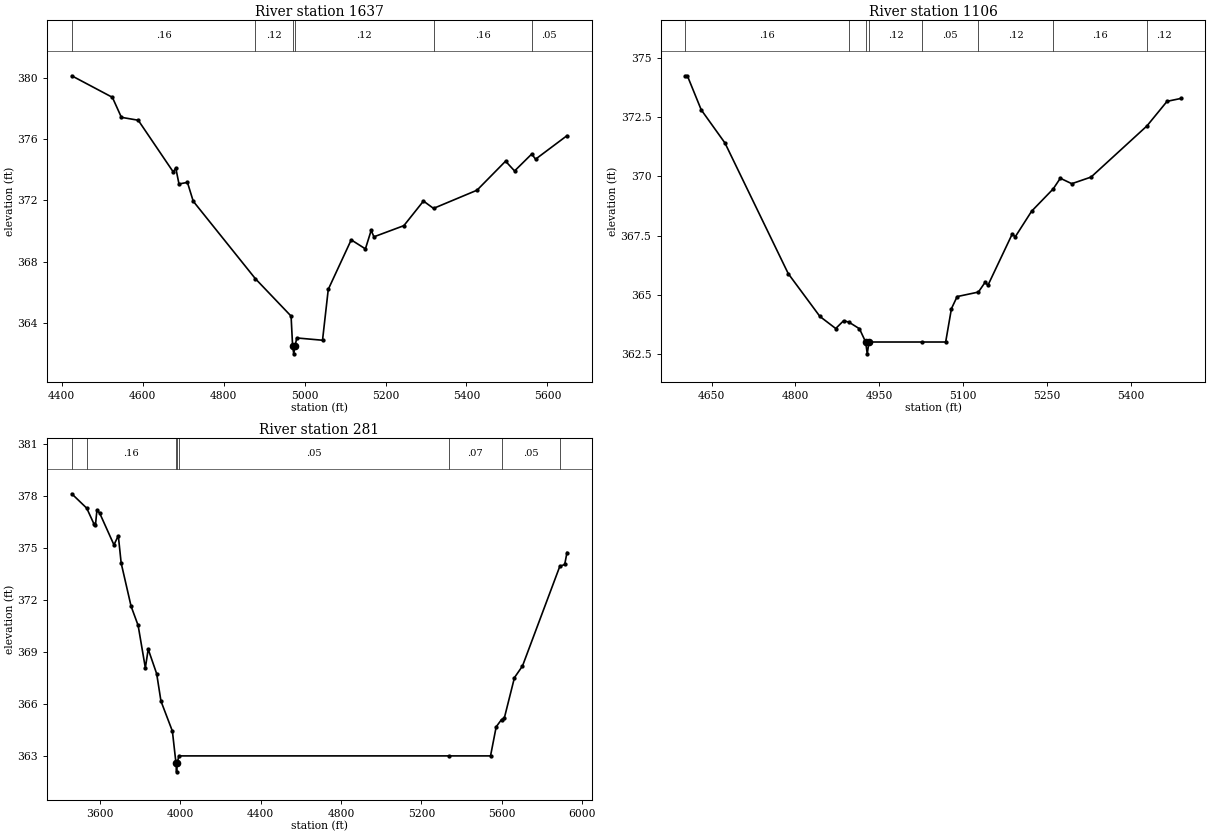
Type RM Length L Ch R = 1,1637,531,531,531
BEGIN DESCRIPTION:
UNT02078 IN SAND CR 3.0
END DESCRIPTION:
XS GIS Cut Line= 4
      3536976.36     10494349.44      3536656.93     10493953.63
      3536427.76     10493741.82      3536080.57     10493536.98
#Sta/Elev= 30
  4424.6  380.16  4525.0  378.75  4547.3  377.44  4588.9  377.25  4675.3  373.87
  4681.7  374.12  4689.6  373.08  4710.5  373.18  4724.8  371.95  4878.3  366.88
  4966.6  364.43  4970.4  362.46  4973.2  361.96  4976.4  362.46  4980.6  363.00
  5044.3  362.85  5058.5  366.18  5115.2  369.42  5150.3  368.83  5164.5  370.04
  5171.3  369.62  5245.3  370.35  5293.7  371.96  5318.6  371.48  5426.0  372.67
  5496.6  374.57  5518.9  373.93  5561.3  375.04  5570.7  374.70  5648.4  376.24
#Mann=6,-1,0
  4424.6    0.16       0  4878.3    0.12       0  4970.4    0.07       0
  4976.4    0.12       0  5318.6    0.16       0  5561.3    0.05       0
Bank Sta=4970.4,4976.4
Exp/Cntr=0.3,0.1

Type RM Length L Ch R = 1,1106,825,825,825
BEGIN DESCRIPTION:
UNT02078 IN SAND CR 2.0
END DESCRIPTION:
XS GIS Cut Line= 3
      3537342.08     10493941.62      3537042.11     10493641.64
      3536592.12     10493541.64
#Sta/Elev= 30
  4603.3  374.25  4606.8  374.25  4631.6  372.81  4674.0  371.41  4787.1  365.89
  4843.7  364.08  4872.0  363.57  4886.1  363.90  4895.5  363.84  4914.4  363.56
  4925.5  363.00  4928.3  362.50  4931.5  363.00  5026.3  363.00  5068.5  363.00
  5078.8  364.41  5089.0  364.92  5127.0  365.11  5138.9  365.52  5144.1  365.40
  5187.6  367.57  5192.7  367.44  5222.2  368.53  5260.7  369.47  5273.4  369.92
  5293.9  369.69  5328.4  369.97  5428.2  372.13  5464.2  373.17  5488.5  373.29
#Mann=8,-1,0
  4603.3    0.16       0  4895.5    0.12       0  4925.5    0.07       0
  4931.5    0.12       0  5026.3    0.05       0  5127.0    0.12       0
  5260.7    0.16       0  5428.2    0.12       0
Bank Sta=4925.5,4931.5
Exp/Cntr=0.3,0.1

Type RM Length L Ch R = 1,281,0,0,0
BEGIN DESCRIPTION:
UNT02078 IN SAND CR 1.0
END DESCRIPTION:
XS GIS Cut Line= 3
      3538225.54     10493635.09      3537439.05     10492765.26
      3536272.93     10493319.73
#Sta/Elev= 30
  3460.8  378.13  3535.3  377.30  3572.1  376.37  3578.9  376.34  3586.3  377.20
  3600.3  377.00  3670.8  375.18  3692.5  375.71  3706.7  374.13  3756.0  371.64
  3791.1  370.53  3827.0  368.08  3841.2  369.16  3883.4  367.74  3904.7  366.16
  3961.5  364.43  3979.4  362.58  3982.2  362.08  3985.4  362.58  3994.0  363.00
  5335.5  363.00  5544.3  363.00  5572.5  364.68  5599.1  365.10  5612.4  365.16
  5663.4  367.52  5703.3  368.19  5888.9  373.94  5913.3  374.05  5924.7  374.74
#Mann=8,-1,0
  3460.8    0.05       0  3535.3    0.16       0  3979.4   0.033       0
  3985.4    0.16       0  3994.0    0.05       0  5335.5    0.07       0
  5599.1    0.05       0  5888.9    0.16       0
Bank Sta=3979.4,3985.4
Exp/Cntr=0.3,0.1

Chan Stop Cuts=-1