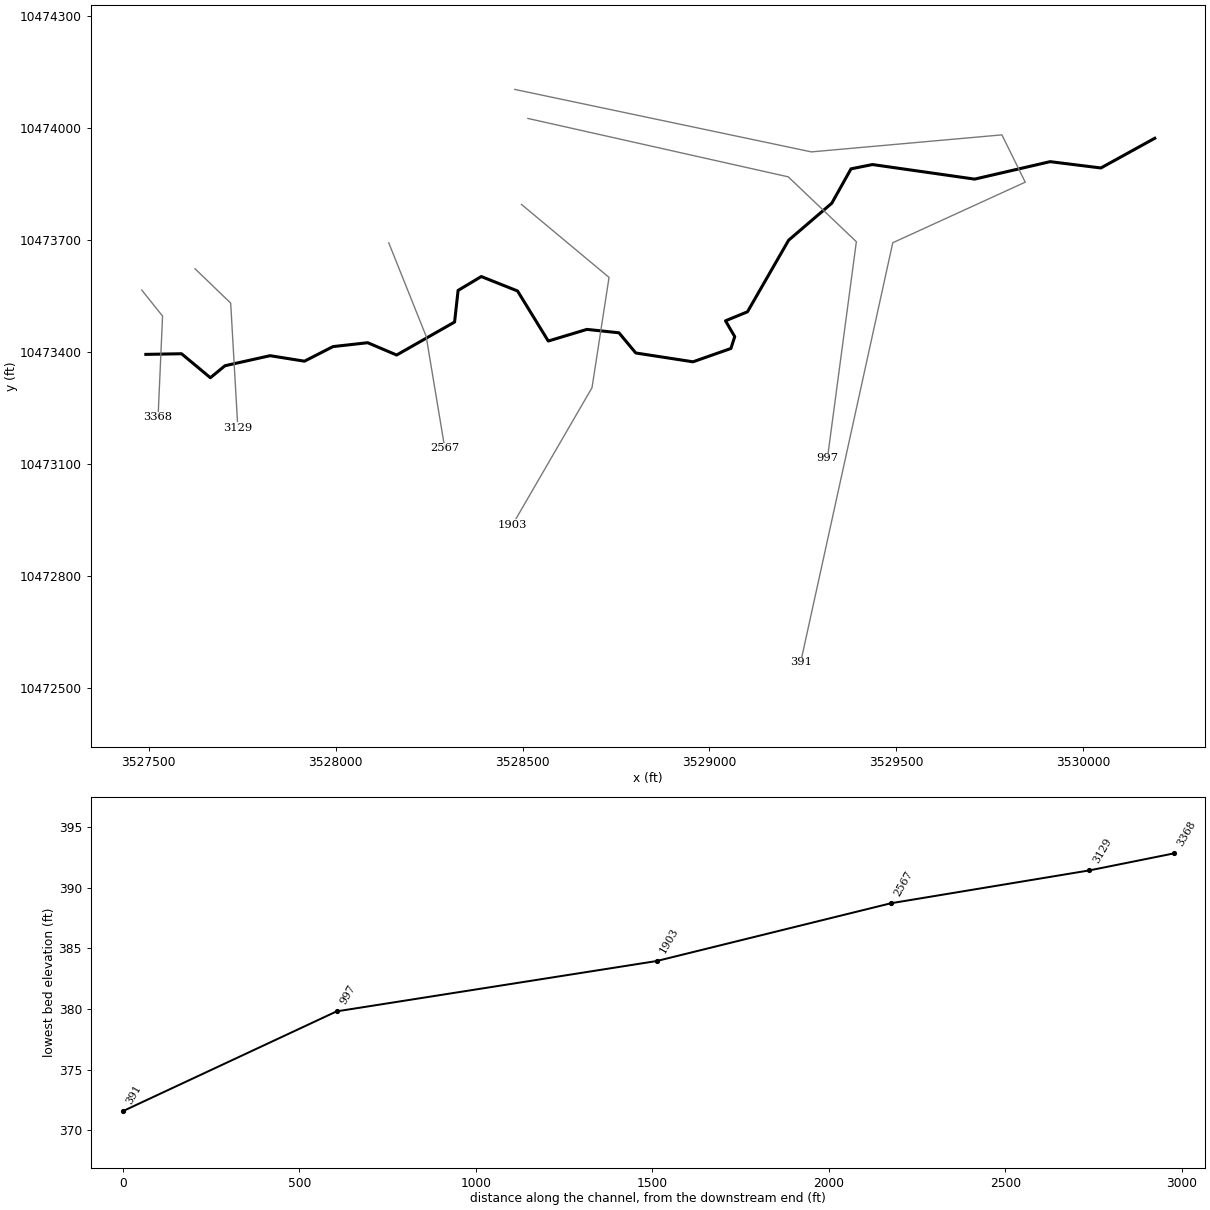
--- UNT02133 IN SAND CR.prj (project) ---

Proj Title=UNT02133 IN SAND CR Base Level Engineering
Current Plan=p01
Default Exp/Contr=0.3,0.1
English Units
Geom File=g01
Flow File=f01
Plan File=p01
BEGIN DESCRIPTION:
UNT02133 IN SAND CR
END DESCRIPTION:

--- UNT02133 IN SAND CR.p01 (plan) ---

Plan Title=Multiple Run
Short Identifier=Multiple
Geom File=g01
Flow File=f01
Subcritical Flow
K Sum by GR= 0
Std Step Tol= 0.01
Critical Tol= 0.01
Num of Std Step Trials= 20
Max Error Tol= 0.3
Flow Tol Ratio= 0.001
Split Flow NTrial= 30
Split Flow Tol= 0.02
Split Flow Ratio= 0.02
Log Output Level= 0
Friction Slope Method= 1
Unsteady Friction Slope Method= 2
Unsteady Bridges Friction Slope Method= 1
Parabolic Critical Depth
Global Vel Dist=  1 , 1 , 1
Global Log Level= 0
CheckData=True
Encroach Param= -1, 0, 0, 0
BEGIN DESCRIPTION:
Multiple Run
END DESCRIPTION:

--- UNT02133 IN SAND CR.f01 (steady flow) ---

Flow Title=Multiple
Number of Profiles=7
Profile Names=10-year,25-year,50-year,1pct_min,100-year,1pct_plu,500-year
River Rch & RM= UNT02133 IN SAND,Reach-1,3368
     414     540     638     553     748    1011    1020
River Rch & RM= UNT02133 IN SAND,Reach-1,391
     686     924    1117     987    1335    1805    1898
Boundary for River Rch & Prof#=UNT02133 IN SAND,Reach-1,1
Up Type=0
Dn Type=3
Dn Slope=0.005
Boundary for River Rch & Prof#=UNT02133 IN SAND,Reach-1,2
Up Type=0
Dn Type=3
Dn Slope=0.005
Boundary for River Rch & Prof#=UNT02133 IN SAND,Reach-1,3
Up Type=0
Dn Type=3
Dn Slope=0.005
Boundary for River Rch & Prof#=UNT02133 IN SAND,Reach-1,4
Up Type=0
Dn Type=3
Dn Slope=0.005
Boundary for River Rch & Prof#=UNT02133 IN SAND,Reach-1,5
Up Type=0
Dn Type=3
Dn Slope=0.005
Boundary for River Rch & Prof#=UNT02133 IN SAND,Reach-1,6
Up Type=0
Dn Type=3
Dn Slope=0.005
Boundary for River Rch & Prof#=UNT02133 IN SAND,Reach-1,7
Up Type=0
Dn Type=3
Dn Slope=0.005

--- UNT02133 IN SAND CR.g01 (geometry) ---

Geom Title=Existing Conditions

River Reach=UNT02133 IN SAND,Reach-1
Reach XY= 30
      3527491.92     10473393.22      3527587.40     10473394.95
      3527664.66     10473330.72      3527703.72     10473362.83
      3527824.38     10473389.74      3527916.40     10473374.99
      3527992.79     10473414.05      3528085.67     10473424.47
      3528163.11     10473391.51      3528318.21     10473479.78
      3528327.60     10473564.39      3528389.74     10473601.54
      3528486.70     10473562.94      3528568.92     10473428.95
      3528672.41     10473460.11      3528758.12     10473450.99
      3528803.14     10473396.94      3528956.31     10473373.36
      3529057.77     10473409.05      3529067.96     10473440.76
      3529043.27     10473483.09      3529102.06     10473507.18
      3529212.19     10473698.76      3529327.77     10473797.84
      3529379.21     10473889.79      3529436.61     10473901.28
      3529709.96     10473862.29      3529912.15     10473909.02
      3530047.95     10473892.11      3530192.11     10473971.64

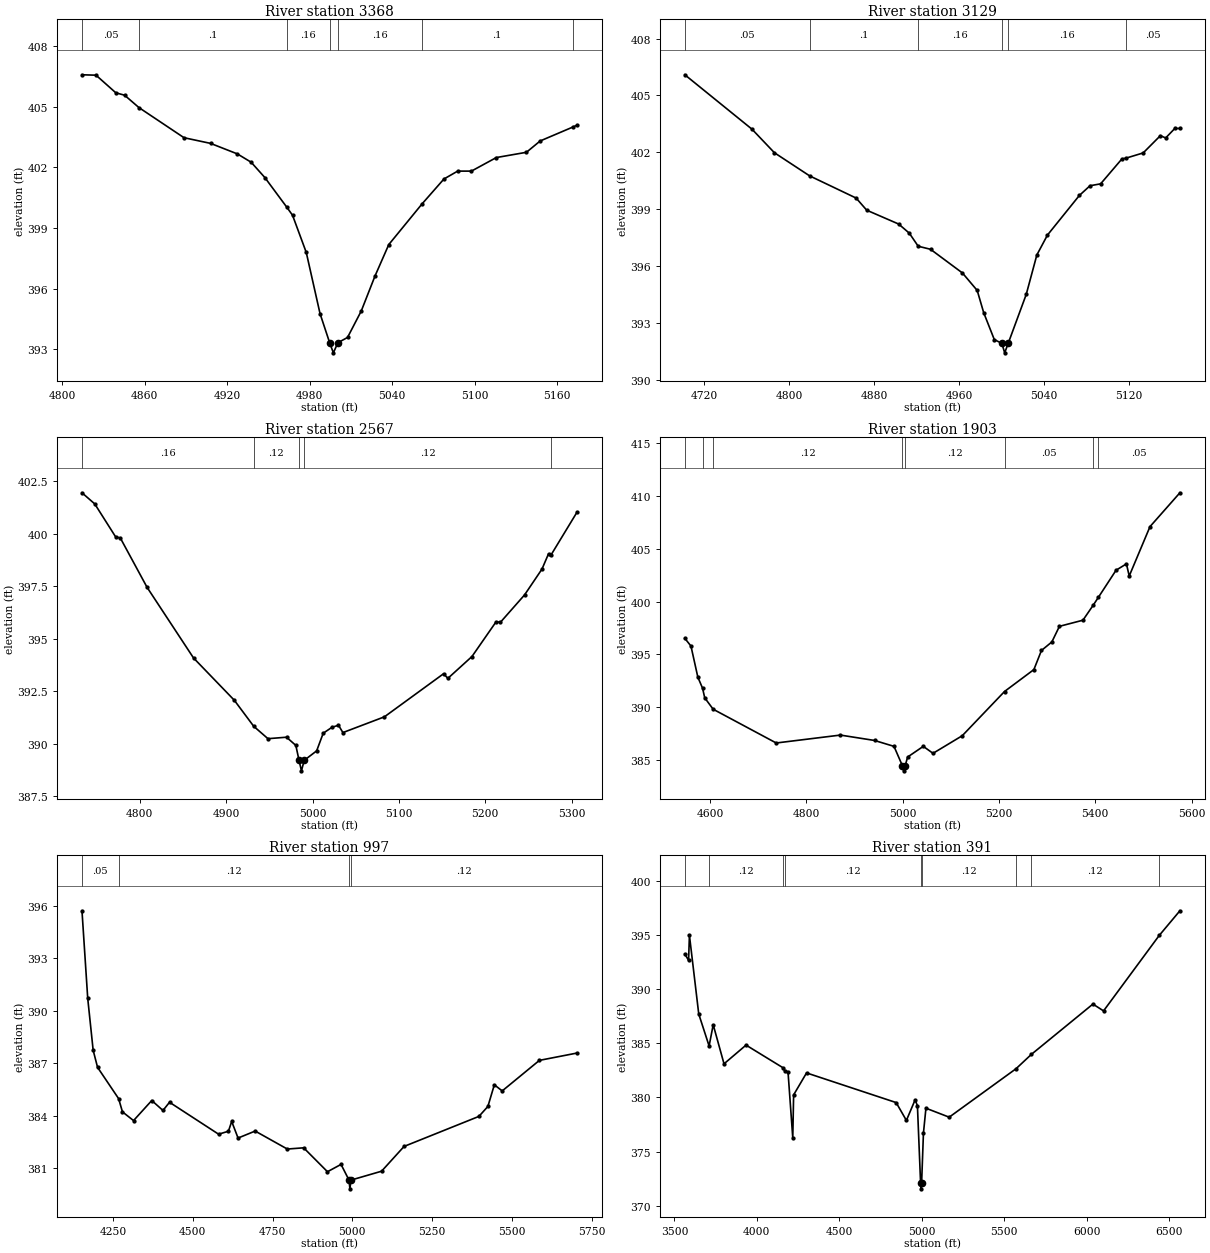
Type RM Length L Ch R = 1,3368,239,239,239
BEGIN DESCRIPTION:
UNT02133 IN SAND CR 4.0
END DESCRIPTION:
XS GIS Cut Line= 3
      3527481.15     10473565.15      3527536.70     10473495.71
      3527524.63     10473224.90
#Sta/Elev= 30
  4814.5  406.57  4824.7  406.55  4839.1  405.68  4845.5  405.56  4855.9  404.95
  4888.7  403.46  4908.0  403.18  4927.5  402.66  4937.5  402.25  4947.5  401.49
  4963.4  400.03  4967.6  399.63  4977.6  397.79  4987.6  394.77  4994.6  393.33
  4997.3  392.83  5000.6  393.33  5007.6  393.59  5017.6  394.90  5027.6  396.63
  5037.6  398.18  5061.8  400.19  5077.7  401.42  5087.7  401.81  5097.7  401.81
  5115.8  402.48  5137.7  402.74  5147.7  403.30  5171.2  403.98  5174.5  404.08
#Mann=7,-1,0
  4814.5    0.05       0  4855.9     0.1       0  4963.4    0.16       0
  4994.6    0.07       0  5000.6    0.16       0  5061.8     0.1       0
  5171.2    0.05       0
Bank Sta=4994.6,5000.6
Exp/Cntr=0.3,0.1

Type RM Length L Ch R = 1,3129,562,562,562
BEGIN DESCRIPTION:
UNT02133 IN SAND CR 4.1
END DESCRIPTION:
XS GIS Cut Line= 3
      3527623.52     10473622.44      3527718.99     10473530.44
      3527738.09     10473197.07
#Sta/Elev= 30
  4701.6  406.09  4764.9  403.22  4786.0  401.98  4819.2  400.76  4863.0  399.59
  4873.0  398.95  4903.1  398.22  4913.1  397.74  4921.5  397.05  4933.1  396.89
  4963.2  395.64  4977.1  394.72  4983.2  393.55  4993.2  392.13  5000.3  391.93
  5003.0  391.43  5006.3  391.93  5023.3  394.51  5033.3  396.59  5043.3  397.64
  5073.4  399.73  5083.4  400.24  5093.4  400.34  5113.4  401.65  5117.6  401.70
  5133.5  401.97  5149.7  402.88  5154.7  402.76  5163.3  403.26  5168.1  403.26
#Mann=6,-1,0
  4701.6    0.05       0  4819.2     0.1       0  4921.5    0.16       0
  5000.3    0.07       0  5006.3    0.16       0  5117.6    0.05       0
Bank Sta=5000.3,5006.3
Exp/Cntr=0.3,0.1

Type RM Length L Ch R = 1,2567,664,664,664
BEGIN DESCRIPTION:
UNT02133 IN SAND CR 3.0
END DESCRIPTION:
XS GIS Cut Line= 3
      3528142.11     10473691.63      3528242.11     10473441.64
      3528292.11     10473141.63
#Sta/Elev= 30
  4733.0  401.95  4747.8  401.42  4772.0  399.85  4777.4  399.80  4808.4  397.45
  4862.2  394.09  4909.4  392.08  4931.9  390.84  4948.4  390.25  4969.9  390.32
  4980.7  389.93  4984.4  389.22  4987.2  388.72  4990.4  389.22  5004.8  389.67
  5012.4  390.51  5022.5  390.79  5030.1  390.89  5035.2  390.54  5083.3  391.29
  5151.8  393.34  5156.8  393.12  5184.7  394.16  5212.6  395.81  5217.7  395.79
  5245.6  397.09  5265.8  398.32  5273.4  399.05  5276.4  399.00  5306.4  401.03
#Mann=5,-1,0
  4733.0    0.16       0  4931.9    0.12       0  4984.4    0.07       0
  4990.4    0.12       0  5276.4    0.05       0
Bank Sta=4984.4,4990.4
Exp/Cntr=0.3,0.1

Type RM Length L Ch R = 1,1903,906,906,906
BEGIN DESCRIPTION:
UNT02133 IN SAND CR 2.0
END DESCRIPTION:
XS GIS Cut Line= 4
      3528497.19     10473794.60      3528731.58     10473599.28
      3528686.01     10473304.14      3528473.33     10472937.38
#Sta/Elev= 30
  4548.0  396.51  4560.7  395.78  4575.0  392.83  4584.8  391.78  4589.3  390.87
  4606.8  389.79  4737.7  386.59  4870.9  387.34  4941.8  386.83  4982.2  386.27
  4999.5  384.45  5002.2  383.95  5005.5  384.45  5010.5  385.26  5043.0  386.27
  5063.2  385.61  5123.9  387.28  5211.6  391.47  5272.6  393.55  5288.3  395.36
  5309.9  396.17  5325.6  397.65  5374.4  398.23  5396.0  399.67  5406.5  400.40
  5443.2  402.97  5464.7  403.57  5470.5  402.42  5513.6  407.10  5575.7  410.31
#Mann=8,-1,0
  4548.0    0.05       0  4584.8    0.16       0  4606.8    0.12       0
  4999.5    0.07       0  5005.5    0.12       0  5211.6    0.05       0
  5396.0     0.1       0  5406.5    0.05       0
Bank Sta=4999.5,5005.5
Exp/Cntr=0.3,0.1

Type RM Length L Ch R = 1,997,606,606,606
BEGIN DESCRIPTION:
UNT02133 IN SAND CR 1.0
END DESCRIPTION:
XS GIS Cut Line= 4
      3528514.52     10474024.63      3529211.18     10473868.37
      3529393.47     10473694.76      3529316.02     10473114.81
#Sta/Elev= 30
  4153.0  395.73  4171.0  390.71  4188.0  387.74  4201.8  386.76  4267.7  384.97
  4279.8  384.21  4314.5  383.71  4371.6  384.86  4406.7  384.29  4427.2  384.76
  4581.0  382.93  4611.7  383.10  4622.0  383.66  4641.9  382.71  4695.5  383.11
  4796.2  382.08  4847.4  382.15  4922.0  380.78  4964.5  381.20  4989.5  380.30
  4992.3  379.80  4995.5  380.30  5091.5  380.81  5162.0  382.23  5396.4  383.95
  5424.5  384.52  5444.7  385.76  5469.4  385.41  5585.9  387.16  5703.8  387.58
#Mann=4,-1,0
  4153.0    0.05       0  4267.7    0.12       0  4989.5    0.07       0
  4995.5    0.12       0
Bank Sta=4989.5,4995.5
Exp/Cntr=0.3,0.1

Type RM Length L Ch R = 1,391,0,0,0
BEGIN DESCRIPTION:
UNT02133 IN SAND CR 1.01
END DESCRIPTION:
XS GIS Cut Line= 6
      3528479.55     10474102.29      3529273.12     10473935.14
      3529783.01     10473980.72      3529845.48     10473854.10
      3529490.92     10473692.01      3529244.41     10472569.21
#Sta/Elev= 30
  3563.0  393.25  3585.7  392.67  3590.8  394.99  3647.4  387.71  3710.2  384.76
  3735.1  386.72  3800.7  383.11  3934.3  384.84  4156.1  382.77  4169.4  382.47
  4189.0  382.36  4217.8  376.28  4223.0  380.24  4301.4  382.27  4845.0  379.53
  4907.2  377.88  4960.2  379.79  4974.1  379.23  4993.4  372.06  4996.1  371.56
  4999.4  372.06  5010.6  376.71  5025.7  379.01  5166.8  378.18  5572.6  382.66
  5665.2  383.98  6038.8  388.63  6103.3  388.00  6441.0  394.97  6566.5  397.25
#Mann=9,-1,0
  3563.0    0.05       0  3710.2    0.12       0  4156.1    0.16       0
  4169.4    0.12       0  4993.4    0.07       0  4999.4    0.12       0
  5572.6    0.16       0  5665.2    0.12       0  6441.0    0.05       0
Bank Sta=4993.4,4999.4
Exp/Cntr=0.3,0.1

Chan Stop Cuts=-1