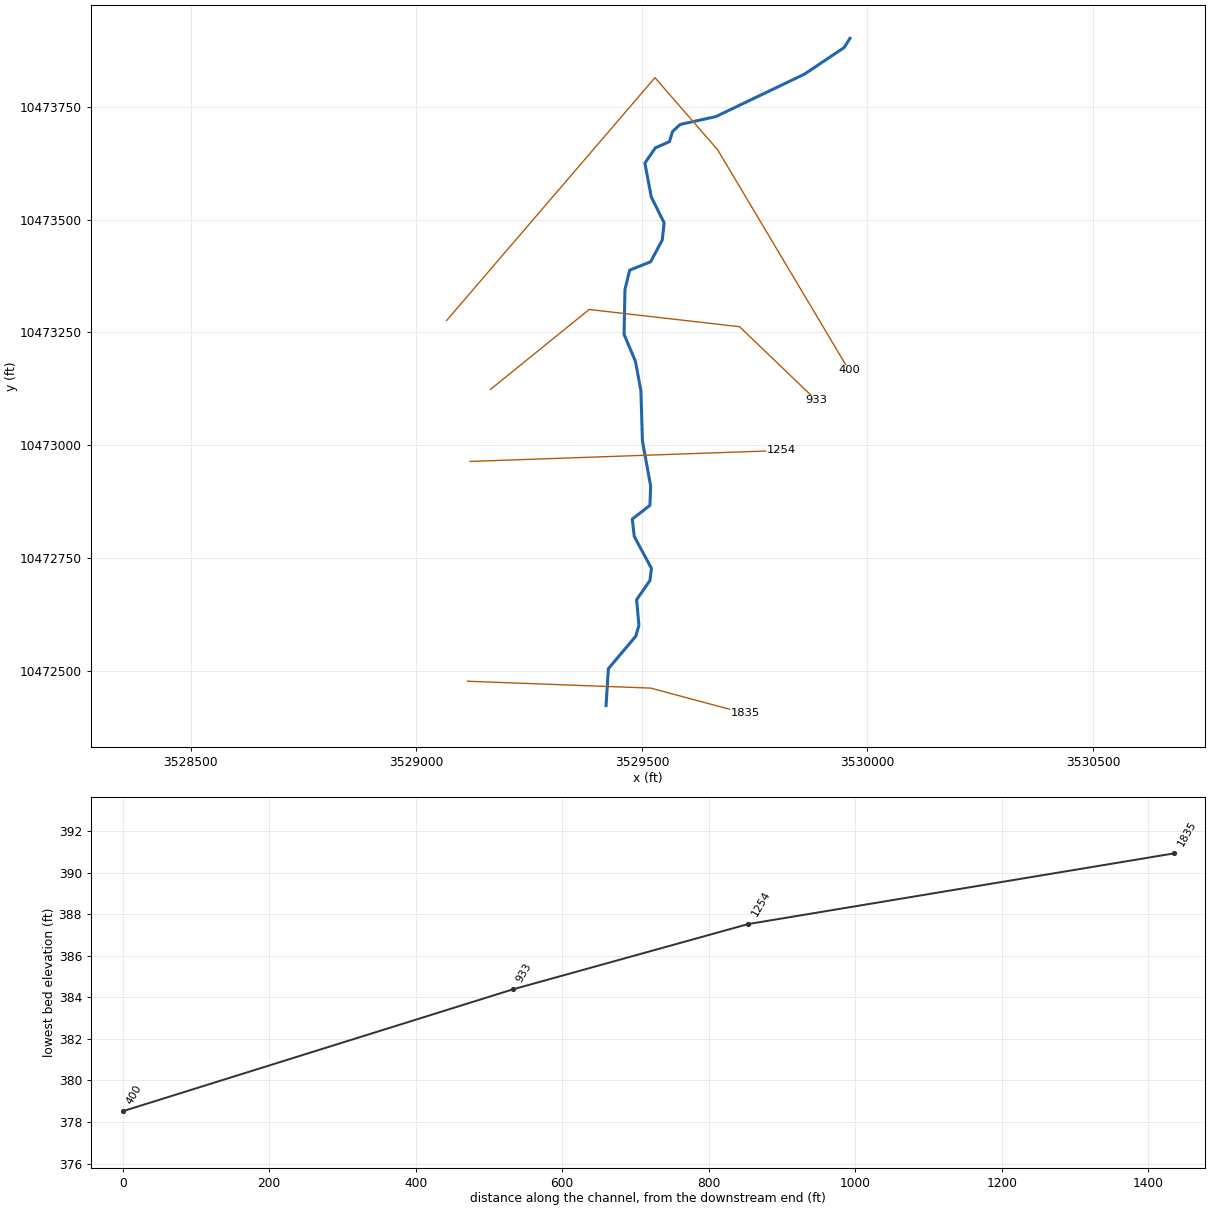
--- UNT02134 IN SAND CR.prj (project) ---

Proj Title=UNT02134 IN SAND CR Base Level Engineering
Current Plan=p01
Default Exp/Contr=0.3,0.1
English Units
Geom File=g01
Flow File=f01
Plan File=p01
BEGIN DESCRIPTION:
UNT02134 IN SAND CR
END DESCRIPTION:

--- UNT02134 IN SAND CR.p01 (plan) ---

Plan Title=Multiple Run
Short Identifier=Multiple
Geom File=g01
Flow File=f01
Subcritical Flow
K Sum by GR= 0
Std Step Tol= 0.01
Critical Tol= 0.01
Num of Std Step Trials= 20
Max Error Tol= 0.3
Flow Tol Ratio= 0.001
Split Flow NTrial= 30
Split Flow Tol= 0.02
Split Flow Ratio= 0.02
Log Output Level= 0
Friction Slope Method= 1
Unsteady Friction Slope Method= 2
Unsteady Bridges Friction Slope Method= 1
Parabolic Critical Depth
Global Vel Dist=  1 , 1 , 1
Global Log Level= 0
CheckData=True
Encroach Param= -1, 0, 0, 0
BEGIN DESCRIPTION:
Multiple Run
END DESCRIPTION:

--- UNT02134 IN SAND CR.f01 (steady flow) ---

Flow Title=Multiple
Number of Profiles=7
Profile Names=10-year,25-year,50-year,1pct_min,100-year,1pct_plu,500-year
River Rch & RM= UNT02134 IN SAND,Reach-1,1835
     375     485     570     491     665     899     897
Boundary for River Rch & Prof#=UNT02134 IN SAND,Reach-1,1
Up Type=0
Dn Type=3
Dn Slope=0.005
Boundary for River Rch & Prof#=UNT02134 IN SAND,Reach-1,2
Up Type=0
Dn Type=3
Dn Slope=0.005
Boundary for River Rch & Prof#=UNT02134 IN SAND,Reach-1,3
Up Type=0
Dn Type=3
Dn Slope=0.005
Boundary for River Rch & Prof#=UNT02134 IN SAND,Reach-1,4
Up Type=0
Dn Type=3
Dn Slope=0.005
Boundary for River Rch & Prof#=UNT02134 IN SAND,Reach-1,5
Up Type=0
Dn Type=3
Dn Slope=0.005
Boundary for River Rch & Prof#=UNT02134 IN SAND,Reach-1,6
Up Type=0
Dn Type=3
Dn Slope=0.005
Boundary for River Rch & Prof#=UNT02134 IN SAND,Reach-1,7
Up Type=0
Dn Type=3
Dn Slope=0.005

--- UNT02134 IN SAND CR.g01 (geometry) ---

Geom Title=Existing Conditions

River Reach=UNT02134 IN SAND,Reach-1
Reach XY= 30
      3529420.60     10472422.77      3529425.77     10472504.58
      3529486.54     10472576.62      3529493.48     10472600.93
      3529488.27     10472657.35      3529517.79     10472699.89
      3529521.26     10472726.80      3529483.06     10472797.98
      3529478.72     10472836.17      3529517.79     10472866.56
      3529519.52     10472909.09      3529501.29     10473008.92
      3529497.82     10473120.90      3529485.67     10473186.00
      3529460.49     10473245.90      3529462.56     10473345.38
      3529472.93     10473387.92      3529519.46     10473406.67
      3529545.16     10473454.59      3529549.32     10473492.79
      3529520.85     10473550.42      3529506.64     10473625.36
      3529529.94     10473659.09      3529561.19     10473672.98
      3529567.99     10473695.40      3529584.91     10473711.03
      3529663.91     10473728.39      3529860.52     10473822.57
      3529948.63     10473881.60      3529961.24     10473901.90

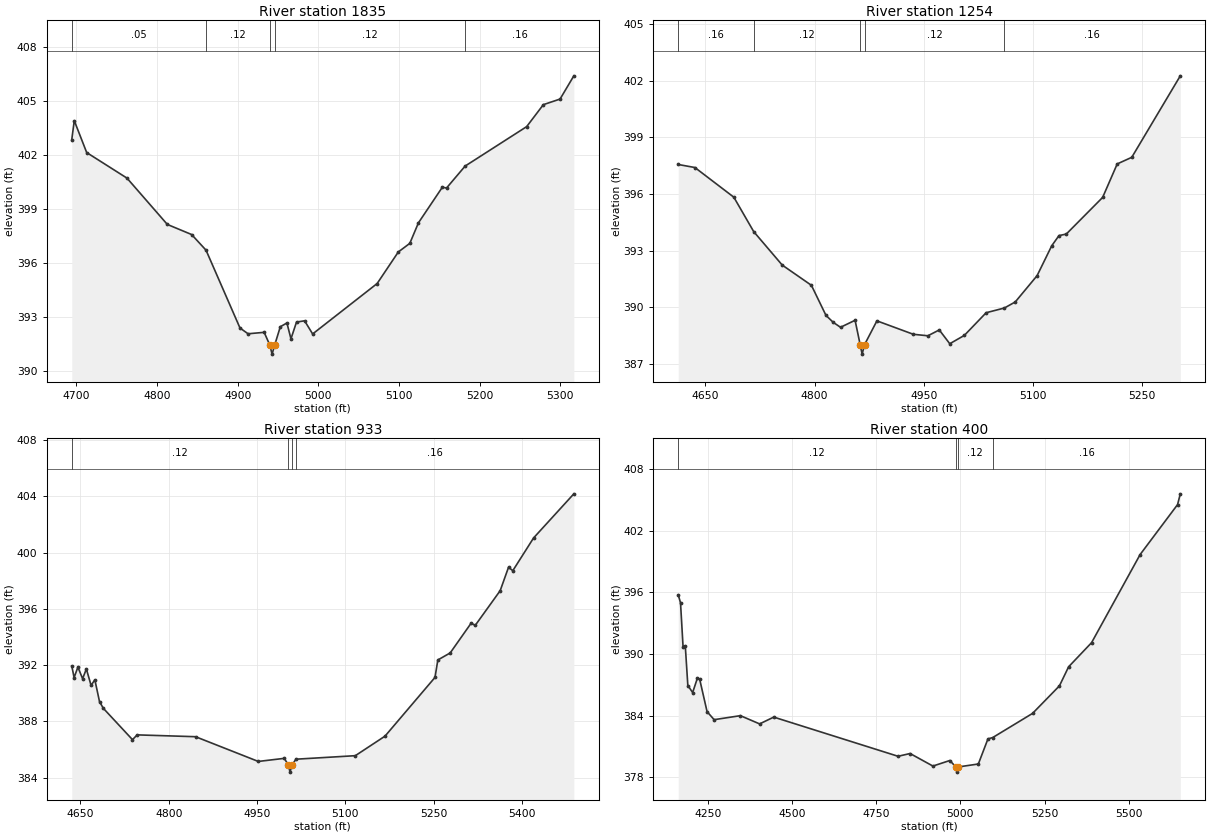
Type RM Length L Ch R = 1,1835,581,581,581
BEGIN DESCRIPTION:
UNT02134 IN SAND CR 2.0
END DESCRIPTION:
XS GIS Cut Line= 3
      3529113.65     10472476.74      3529519.49     10472461.55
      3529728.58     10472405.50
#Sta/Elev= 30
  4694.3  402.84  4697.4  403.89  4712.8  402.12  4762.8  400.70  4812.8  398.13
  4842.9  397.57  4860.8  396.70  4902.9  392.38  4912.9  392.06  4932.9  392.14
  4939.9  391.43  4942.7  390.93  4945.9  391.43  4952.9  392.45  4961.1  392.66
  4966.1  391.78  4973.0  392.71  4983.0  392.78  4993.0  392.05  5073.0  394.85
  5099.2  396.60  5113.5  397.08  5124.2  398.22  5153.9  400.20  5159.0  400.15
  5182.1  401.37  5258.4  403.56  5279.1  404.78  5299.8  405.09  5316.9  406.38
#Mann=5,-1,0
  4694.3    0.05       0  4860.8    0.12       0  4939.9    0.07       0
  4945.9    0.12       0  5182.1    0.16       0
Bank Sta=4939.9,4945.9
Exp/Cntr=0.3,0.1

Type RM Length L Ch R = 1,1254,321,321,321
BEGIN DESCRIPTION:
UNT02134 IN SAND CR 1.0
END DESCRIPTION:
XS GIS Cut Line= 2
      3529119.27     10472964.01      3529808.74     10472988.26
#Sta/Elev= 30
  4612.6  397.56  4635.5  397.40  4689.0  395.83  4716.3  394.01  4755.5  392.24
  4795.6  391.17  4815.6  389.58  4825.6  389.21  4835.6  388.95  4855.6  389.32
  4862.6  388.03  4865.3  387.53  4868.6  388.03  4885.6  389.29  4935.6  388.58
  4955.6  388.50  4971.3  388.81  4985.7  388.08  5005.7  388.52  5035.7  389.72
  5060.8  389.97  5075.7  390.29  5105.7  391.68  5125.8  393.26  5135.8  393.80
  5145.8  393.88  5195.8  395.82  5215.8  397.59  5235.8  397.94  5302.5  402.25
#Mann=5,-1,0
  4612.6    0.16       0  4716.3    0.12       0  4862.6    0.07       0
  4868.6    0.12       0  5060.8    0.16       0
Bank Sta=4862.6,4868.6
Exp/Cntr=0.3,0.1

Type RM Length L Ch R = 1,933,533,533,533
BEGIN DESCRIPTION:
UNT02134 IN SAND CR 2.2
END DESCRIPTION:
XS GIS Cut Line= 4
      3529164.46     10473123.74      3529383.20     10473300.82
      3529716.53     10473262.62      3529886.67     10473099.43
#Sta/Elev= 30
  4635.3  391.94  4639.3  391.12  4645.7  391.86  4653.7  391.04  4660.1  391.73
  4668.1  390.56  4674.5  390.96  4682.4  389.41  4688.9  388.93  4738.4  386.70
  4746.4  387.04  4845.5  386.91  4952.1  385.15  4996.2  385.37  5003.2  384.89
  5006.0  384.39  5009.2  384.89  5016.0  385.31  5116.9  385.56  5167.3  386.95
  5252.2  391.13  5257.0  392.37  5278.0  392.87  5313.6  394.99  5320.5  394.83
  5362.9  397.30  5377.1  398.97  5384.3  398.72  5419.6  401.05  5488.0  404.19
#Mann=4,-1,0
  4635.3    0.12       0  5003.2    0.07       0  5009.2    0.12       0
  5016.0    0.16       0
Bank Sta=5003.2,5009.2
Exp/Cntr=0.3,0.1

Type RM Length L Ch R = 1,400,0,0,0
BEGIN DESCRIPTION:
UNT02134 IN SAND CR 2.1
END DESCRIPTION:
XS GIS Cut Line= 4
      3529067.22     10473276.50      3529529.03     10473814.71
      3529667.92     10473654.98      3529959.22     10473166.02
#Sta/Elev= 30
  4162.6  395.76  4169.4  394.98  4176.9  390.72  4183.5  390.81  4191.1  386.94
  4205.4  386.26  4219.7  387.68  4226.3  387.54  4248.2  384.40  4269.1  383.62
  4347.0  384.01  4404.1  383.21  4446.1  383.87  4815.0  380.06  4850.7  380.33
  4918.4  379.11  4968.6  379.65  4986.6  379.02  4989.4  378.52  4992.6  379.02
  5053.2  379.31  5081.7  381.75  5095.8  381.88  5214.1  384.23  5293.9  386.91
  5321.1  388.76  5389.3  391.11  5533.4  399.68  5644.4  404.53  5652.6  405.58
#Mann=4,-1,0
  4162.6    0.12       0  4986.6    0.07       0  4992.6    0.12       0
  5095.8    0.16       0
Bank Sta=4986.6,4992.6
Exp/Cntr=0.3,0.1

Chan Stop Cuts=-1