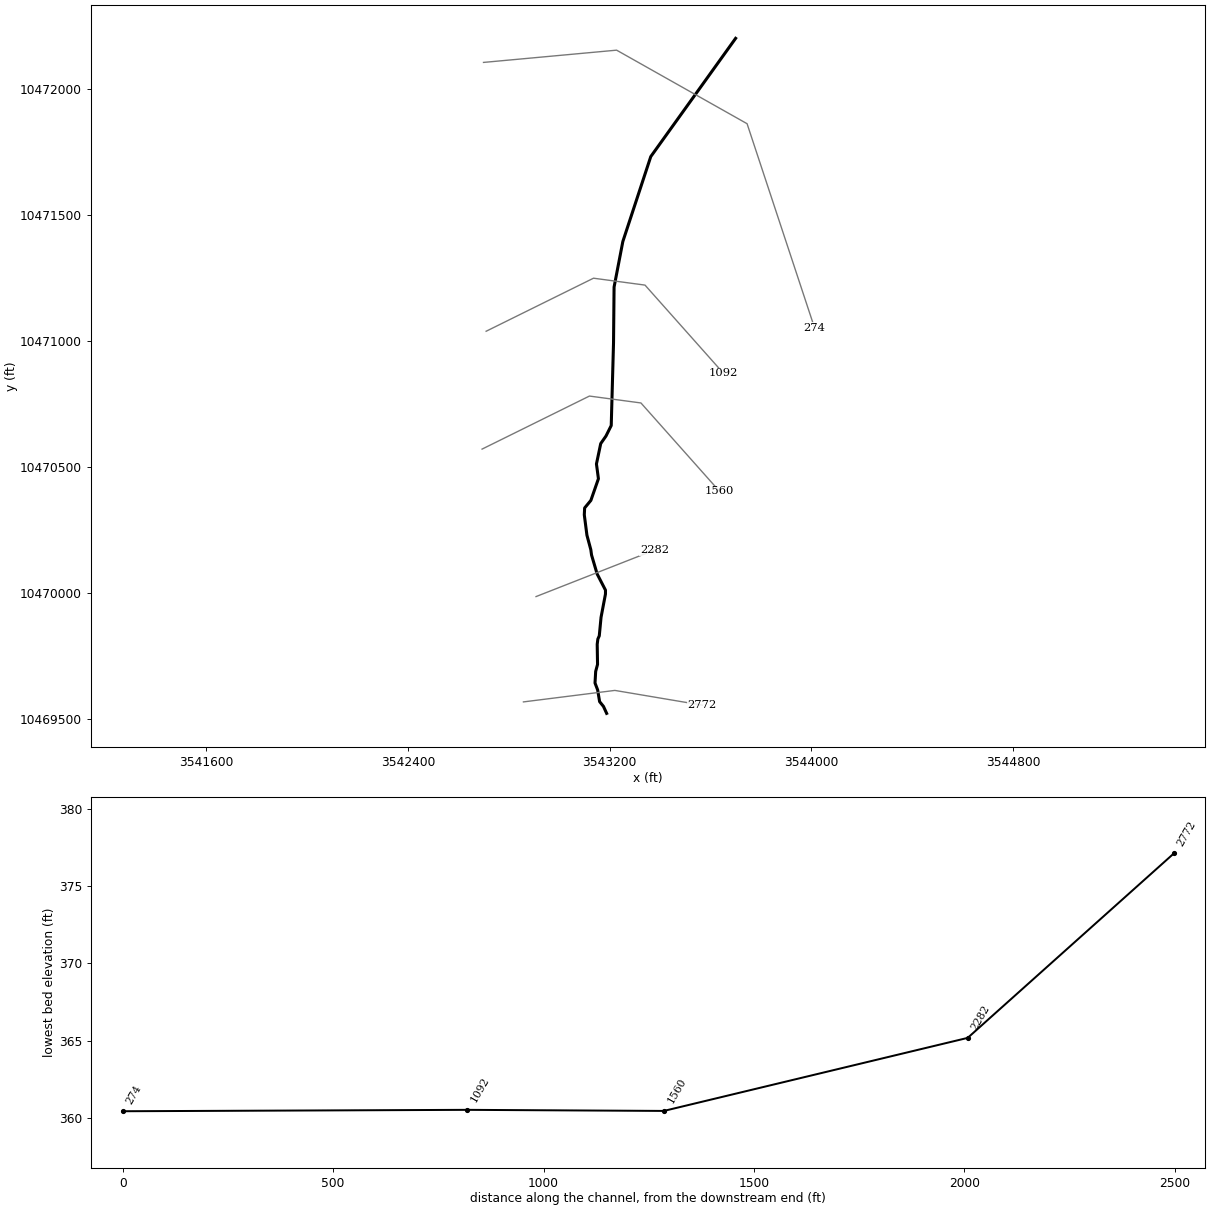
--- UNT02152 IN SAND CR.prj (project) ---

Proj Title=UNT02152 IN SAND CR Base Level Engineering
Current Plan=p01
Default Exp/Contr=0.3,0.1
English Units
Geom File=g01
Flow File=f01
Plan File=p01
BEGIN DESCRIPTION:
UNT02152 IN SAND CR
END DESCRIPTION:

--- UNT02152 IN SAND CR.p01 (plan) ---

Plan Title=Multiple Run
Short Identifier=Multiple
Geom File=g01
Flow File=f01
Subcritical Flow
K Sum by GR= 0
Std Step Tol= 0.01
Critical Tol= 0.01
Num of Std Step Trials= 20
Max Error Tol= 0.3
Flow Tol Ratio= 0.001
Split Flow NTrial= 30
Split Flow Tol= 0.02
Split Flow Ratio= 0.02
Log Output Level= 0
Friction Slope Method= 1
Unsteady Friction Slope Method= 2
Unsteady Bridges Friction Slope Method= 1
Parabolic Critical Depth
Global Vel Dist=  1 , 1 , 1
Global Log Level= 0
CheckData=True
Encroach Param= -1, 0, 0, 0
BEGIN DESCRIPTION:
Multiple Run
END DESCRIPTION:

--- UNT02152 IN SAND CR.f01 (steady flow) ---

Flow Title=Multiple
Number of Profiles=7
Profile Names=10-year,25-year,50-year,1pct_min,100-year,1pct_plu,500-year
River Rch & RM= UNT02152 IN SAND,Reach-1,2772
     226     282     324     273     369     499     476
Boundary for River Rch & Prof#=UNT02152 IN SAND,Reach-1,1
Up Type=0
Dn Type=3
Dn Slope=0.005
Boundary for River Rch & Prof#=UNT02152 IN SAND,Reach-1,2
Up Type=0
Dn Type=3
Dn Slope=0.005
Boundary for River Rch & Prof#=UNT02152 IN SAND,Reach-1,3
Up Type=0
Dn Type=3
Dn Slope=0.005
Boundary for River Rch & Prof#=UNT02152 IN SAND,Reach-1,4
Up Type=0
Dn Type=3
Dn Slope=0.005
Boundary for River Rch & Prof#=UNT02152 IN SAND,Reach-1,5
Up Type=0
Dn Type=3
Dn Slope=0.005
Boundary for River Rch & Prof#=UNT02152 IN SAND,Reach-1,6
Up Type=0
Dn Type=3
Dn Slope=0.005
Boundary for River Rch & Prof#=UNT02152 IN SAND,Reach-1,7
Up Type=0
Dn Type=3
Dn Slope=0.005

--- UNT02152 IN SAND CR.g01 (geometry) ---

Geom Title=Existing Conditions

River Reach=UNT02152 IN SAND,Reach-1
Reach XY= 30
      3543188.01     10469522.33      3543175.45     10469549.86
      3543160.13     10469568.87      3543152.32     10469615.31
      3543141.90     10469642.65      3543144.51     10469688.66
      3543151.89     10469716.44      3543150.58     10469796.30
      3543153.19     10469817.13      3543158.78     10469829.78
      3543165.82     10469903.26      3543183.33     10469995.45
      3543183.44     10470010.85      3543150.24     10470075.31
      3543128.11     10470150.39      3543125.33     10470171.11
      3543109.83     10470228.78      3543099.41     10470309.51
      3543100.72     10470336.86      3543125.46     10470366.80
      3543155.40     10470452.74      3543147.59     10470511.33
      3543164.52     10470592.06      3543185.35     10470622.01
      3543206.19     10470663.68      3543215.30     10470991.80
      3543217.47     10471212.72      3543252.19     10471393.28
      3543362.96     10471730.08      3543699.44     10472199.03

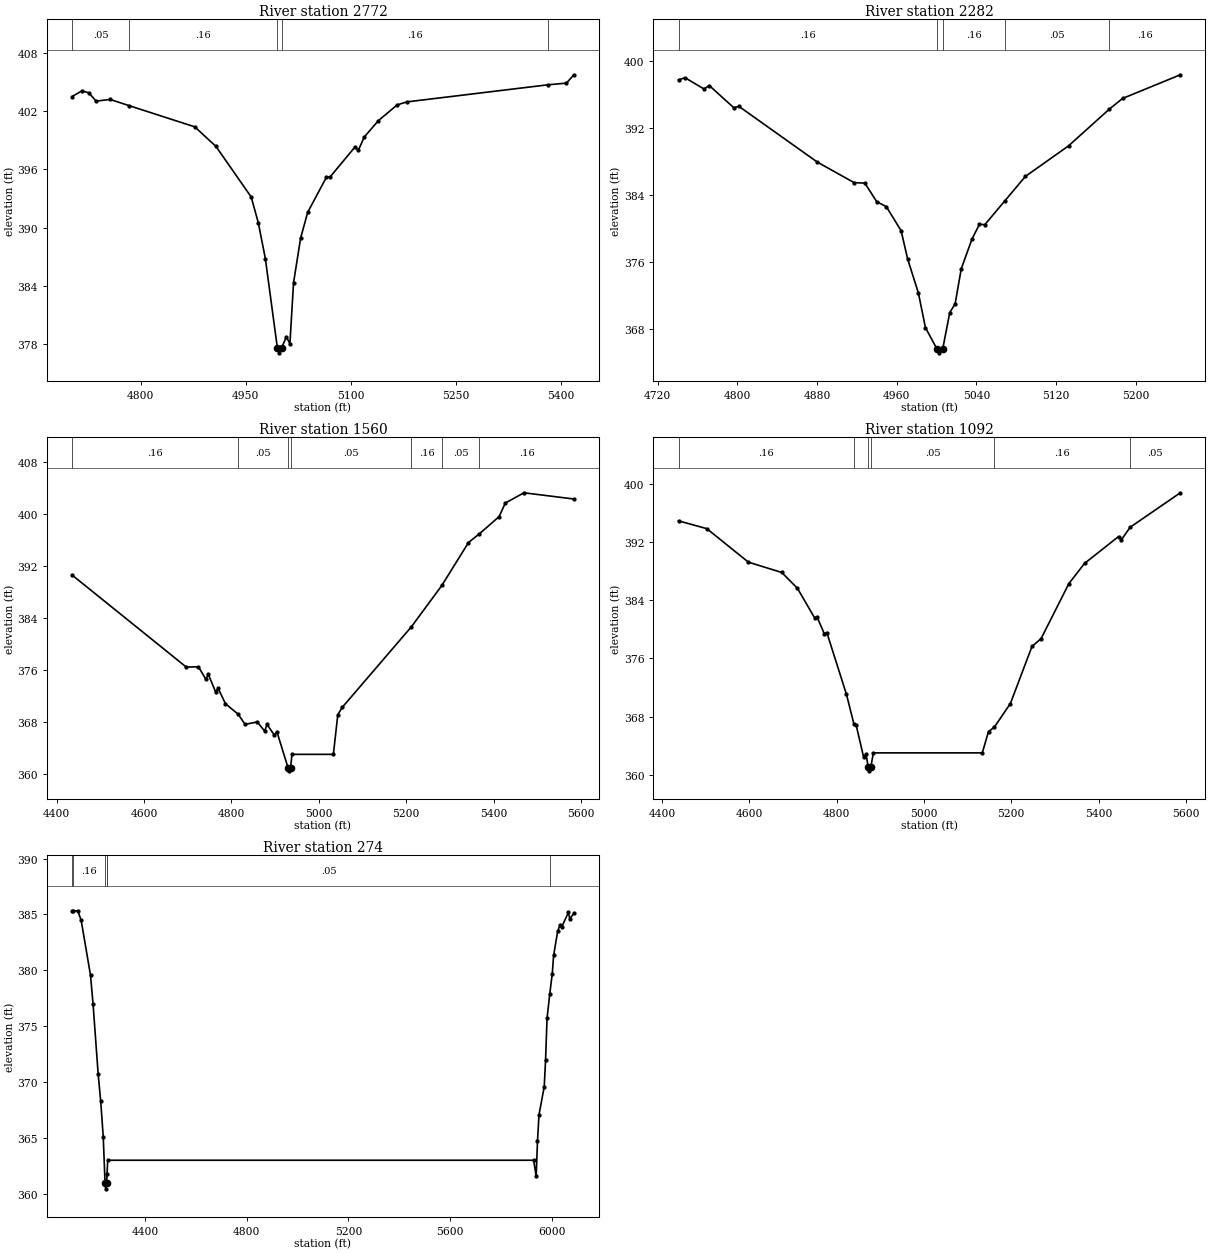
Type RM Length L Ch R = 1,2772,490,490,490
BEGIN DESCRIPTION:
UNT02152 IN SAND CR 3.1
END DESCRIPTION:
XS GIS Cut Line= 3
      3542858.06     10469567.82      3543220.51     10469613.39
      3543567.40     10469554.85
#Sta/Elev= 30
  4701.7  403.48  4715.9  404.07  4725.9  403.85  4736.0  403.01  4756.2  403.18
  4782.9  402.55  4877.1  400.36  4907.3  398.35  4957.7  393.14  4967.8  390.50
  4977.9  386.81  4995.1  377.60  4997.8  377.10  5001.1  377.60  5008.0  378.75
  5013.0  378.03  5018.2  384.31  5028.3  388.90  5038.4  391.56  5065.3  395.19
  5070.3  395.19  5105.8  398.27  5110.9  397.96  5119.3  399.32  5139.6  401.01
  5166.3  402.62  5180.2  402.93  5381.9  404.69  5408.2  404.86  5418.8  405.72
#Mann=5,-1,0
  4701.7    0.05       0  4782.9    0.16       0  4995.1    0.07       0
  5001.1    0.16       0  5381.9    0.05       0
Bank Sta=4995.1,5001.1
Exp/Cntr=0.3,0.1

Type RM Length L Ch R = 1,2282,722,722,722
BEGIN DESCRIPTION:
UNT02152 IN SAND CR 3.0
END DESCRIPTION:
XS GIS Cut Line= 2
      3542908.06     10469985.47      3543376.83     10470169.50
#Sta/Elev= 30
  4741.1  397.78  4747.6  398.04  4766.6  396.70  4772.0  397.10  4796.4  394.47
  4801.8  394.61  4880.4  387.96  4917.3  385.51  4928.1  385.45  4940.0  383.23
  4949.6  382.65  4964.5  379.76  4971.0  376.40  4981.8  372.34  4988.9  368.19
  5000.3  365.68  5003.0  365.18  5006.3  365.68  5013.3  369.99  5018.7  371.03
  5024.8  375.20  5035.5  378.74  5043.1  380.53  5048.5  380.49  5068.7  383.35
  5089.2  386.25  5132.5  389.90  5173.3  394.27  5186.7  395.56  5244.7  398.39
#Mann=5,-1,0
  4741.1    0.16       0  5000.3    0.07       0  5006.3    0.16       0
  5068.7    0.05       0  5173.3    0.16       0
Bank Sta=5000.3,5006.3
Exp/Cntr=0.3,0.1

Type RM Length L Ch R = 1,1560,468,468,468
BEGIN DESCRIPTION:
UNT02152 IN SAND CR 2.1
END DESCRIPTION:
XS GIS Cut Line= 4
      3542694.03     10470570.22      3543119.76     10470780.58
      3543324.01     10470753.19      3543635.02     10470403.53
#Sta/Elev= 30
  4435.0  390.63  4696.4  376.45  4724.4  376.49  4741.3  374.56  4746.9  375.34
  4763.7  372.61  4769.3  373.19  4786.2  370.80  4815.5  369.17  4831.0  367.62
  4859.1  367.99  4875.9  366.59  4881.5  367.60  4898.4  365.94  4903.9  366.50
  4929.4  360.96  4932.2  360.46  4935.4  360.96  4938.5  363.00  5033.3  363.00
  5043.4  369.10  5053.5  370.23  5212.1  382.67  5281.7  389.03  5342.6  395.63
  5367.8  396.99  5412.8  399.63  5427.0  401.72  5469.7  403.30  5583.9  402.34
#Mann=7,-1,0
  4435.0    0.16       0  4815.5    0.05       0  4929.4   0.033       0
  4935.4    0.05       0  5212.1    0.16       0  5281.7    0.05       0
  5367.8    0.16       0
Bank Sta=4929.4,4935.4
Exp/Cntr=0.3,0.1

Type RM Length L Ch R = 1,1092,818,818,818
BEGIN DESCRIPTION:
UNT02152 IN SAND CR 2.0
END DESCRIPTION:
XS GIS Cut Line= 4
      3542710.13     10471037.54      3543135.89     10471247.92
      3543340.14     10471220.53      3543651.12     10470870.90
#Sta/Elev= 30
  4438.2  394.90  4502.8  393.83  4598.2  389.22  4674.6  387.80  4710.4  385.63
  4749.7  381.57  4755.3  381.70  4772.1  379.36  4777.7  379.55  4822.6  371.06
  4839.9  366.93  4845.0  366.79  4861.9  362.43  4867.5  362.86  4872.4  361.03
  4875.2  360.53  4878.4  361.03  4884.3  363.00  5133.7  363.00  5147.9  365.93
  5160.9  366.51  5198.0  369.78  5247.4  377.63  5268.3  378.71  5331.9  386.27
  5367.8  389.05  5445.6  392.74  5452.3  392.31  5472.2  394.02  5587.1  398.76
#Mann=6,-1,0
  4438.2    0.16       0  4839.9    0.05       0  4872.4   0.033       0
  4878.4    0.05       0  5160.9    0.16       0  5472.2    0.05       0
Bank Sta=4872.4,4878.4
Exp/Cntr=0.3,0.1

Type RM Length L Ch R = 1,274,0,0,0
BEGIN DESCRIPTION:
UNT02152 IN SAND CR 1.0
END DESCRIPTION:
XS GIS Cut Line= 4
      3542699.77     10472103.53      3543227.52     10472152.14
      3543744.88     10471860.47      3544012.26     10471051.40
#Sta/Elev= 30
  4111.8  385.29  4117.1  385.31  4134.2  385.33  4147.5  384.49  4184.4  379.56
  4194.5  376.97  4214.6  370.70  4224.6  368.27  4234.6  365.09  4241.7  360.94
  4244.4  360.44  4247.7  360.94  4249.6  361.81  4252.2  363.00  5929.6  363.00
  5939.4  361.56  5944.6  364.72  5950.6  367.09  5971.1  369.58  5976.4  371.97
  5982.2  375.70  5992.8  377.87  6002.8  379.70  6008.1  381.33  6024.4  383.54
  6034.6  384.10  6039.8  383.87  6066.3  385.18  6071.6  384.62  6087.8  385.09
#Mann=6,-1,0
  4111.8     0.1       0  4117.1    0.16       0  4241.7   0.033       0
  4247.7    0.16       0  4249.6    0.05       0  5992.8    0.16       0
Bank Sta=4241.7,4247.7
Exp/Cntr=0.3,0.1

Chan Stop Cuts=-1