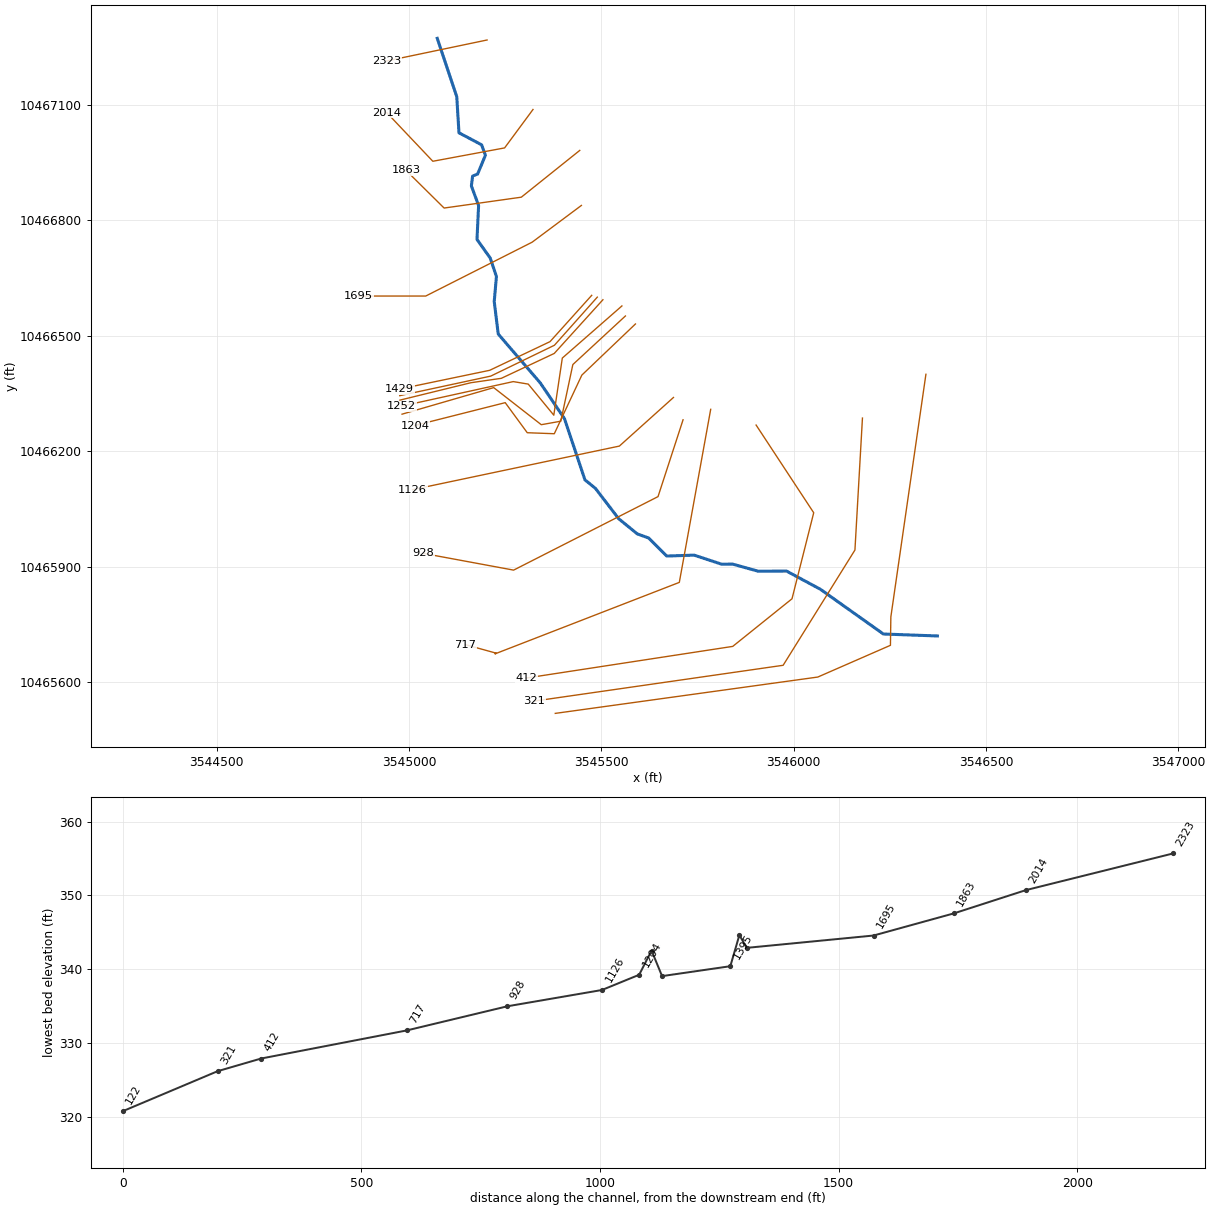
--- UNT02167 IN SAND CR.prj (project) ---

Proj Title=UNT02167 IN SAND CR Base Level Engineering
Current Plan=p01
Default Exp/Contr=0.3,0.1
English Units
Geom File=g01
Flow File=f01
Plan File=p01
Y Axis Title=Elevation
X Axis Title(PF)=Main Channel Distance
X Axis Title(XS)=Station
BEGIN DESCRIPTION:
UNT02167 IN SAND CR
END DESCRIPTION:
DSS Export Rating Curves= 0
DSS Export Rating Curve Sorted= 0
DSS Export Volume Flow Curves= 0
DXF OffsetX= 0
DXF OffsetY= 0
DXF ScaleX= 1
DXF ScaleY= 10

--- UNT02167 IN SAND CR.p01 (plan) ---

Plan Title=Multiple Run
Short Identifier=Multiple
Geom File=g01
Flow File=f01
Subcritical Flow
K Sum by GR= 0
Std Step Tol= 0.01
Critical Tol= 0.01
Num of Std Step Trials= 20
Max Error Tol= 0.3
Flow Tol Ratio= 0.001
Split Flow NTrial= 30
Split Flow Tol= 0.02
Split Flow Ratio= 0.02
Log Output Level= 0
Friction Slope Method= 1
Unsteady Friction Slope Method= 2
Unsteady Bridges Friction Slope Method= 1
Parabolic Critical Depth
Global Vel Dist=  1 , 1 , 1
Global Log Level= 0
CheckData=True
Encroach Param= -1, 0, 0, 0
BEGIN DESCRIPTION:
Multiple Run
END DESCRIPTION:

--- UNT02167 IN SAND CR.f01 (steady flow) ---

Flow Title=Multiple
Number of Profiles=7
Profile Names=10-year,25-year,50-year,1pct_min,100-year,1pct_plu,500-year
River Rch & RM= UNT02167 IN SAND,Reach-1,2323
     234     293     339     287     389     526     508
Boundary for River Rch & Prof#=UNT02167 IN SAND,Reach-1,1
Up Type=0
Dn Type=3
Dn Slope=0.005
Boundary for River Rch & Prof#=UNT02167 IN SAND,Reach-1,2
Up Type=0
Dn Type=3
Dn Slope=0.005
Boundary for River Rch & Prof#=UNT02167 IN SAND,Reach-1,3
Up Type=0
Dn Type=3
Dn Slope=0.005
Boundary for River Rch & Prof#=UNT02167 IN SAND,Reach-1,4
Up Type=0
Dn Type=3
Dn Slope=0.005
Boundary for River Rch & Prof#=UNT02167 IN SAND,Reach-1,5
Up Type=0
Dn Type=3
Dn Slope=0.005
Boundary for River Rch & Prof#=UNT02167 IN SAND,Reach-1,6
Up Type=0
Dn Type=3
Dn Slope=0.005
Boundary for River Rch & Prof#=UNT02167 IN SAND,Reach-1,7
Up Type=0
Dn Type=3
Dn Slope=0.005

--- UNT02167 IN SAND CR.g01 (geometry) ---

Geom Title=Existing Conditions
Program Version=4.10

River Reach=UNT02167 IN SAND,Reach-1
Reach XY= 30
      3545073.61     10467273.28      3545124.38     10467121.61
      3545130.09     10467027.86      3545188.94     10466996.61
      3545198.84     10466969.53      3545178.53     10466920.57
      3545165.51     10466915.36      3545162.38     10466889.84
      3545181.13      10466838.8      3545176.96     10466750.78
      3545211.34     10466702.34      3545227.48     10466654.42
      3545221.76     10466589.32      3545232.17     10466504.94
      3545341.55     10466377.86      3545404.36     10466285.09
      3545457.58     10466126.07      3545484.92     10466103.87
      3545545.46     10466024.94      3545593.79     10465985.62
      3545623.21     10465974.98      3545670.27     10465928.13
      3545741.51     10465930.48       3545813.2     10465906.88
      3545841.42     10465907.22       3545908.5     10465888.56
      3545981.46     10465889.21      3546069.72     10465841.79
      3546233.44     10465725.55      3546373.99     10465720.48

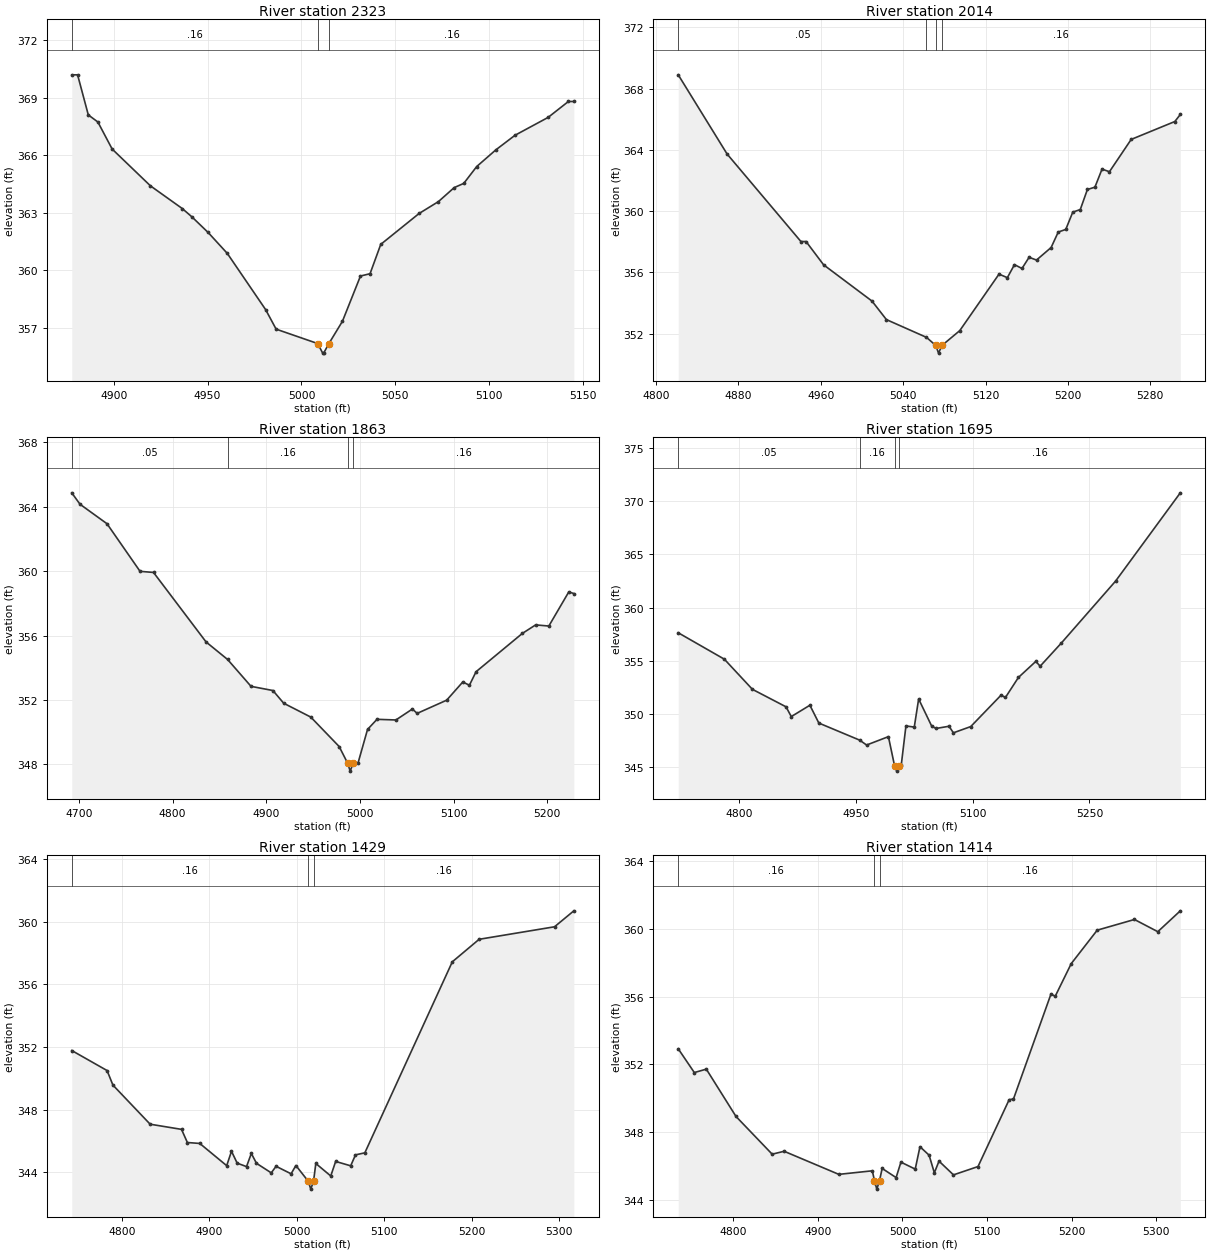
Type RM Length L Ch R = 1 ,2323    ,309,309,309
BEGIN DESCRIPTION:
UNT02167 IN SAND CR 5.0
END DESCRIPTION:
XS GIS Cut Line= 2
      3545203.14     10467268.98      3544941.49     10467214.31
#Sta/Elev= 30
  4877.7   370.2  4880.8   370.2  4886.5  368.11  4891.6  367.74  4899.2  366.33
  4919.6  364.41  4936.5  363.23  4941.6   362.8  4950.3  361.98  4960.5  360.89
  4980.9  357.96  4986.5  356.94  5008.6  356.19  5011.3  355.69  5011.8  355.69
  5014.6  356.19  5021.8  357.35  5031.4  359.71  5036.5  359.83  5042.2  361.36
  5062.6  362.97  5072.9  363.59  5081.3  364.32  5086.4  364.54  5093.3  365.42
  5103.5  366.29  5113.7  367.05  5131.3  367.98  5142.1  368.81    5145  368.81
#Mann= 3 ,-1 , 0
  4877.7     .16       0  5008.6     .07       0  5014.6     .16       0
Bank Sta=5008.6,5014.6
XS Rating Curve= 0 ,0
Exp/Cntr=0.3,0.1

Type RM Length L Ch R = 1 ,2014    ,151,151,151
BEGIN DESCRIPTION:
UNT02167 IN SAND CR 5.1
END DESCRIPTION:
XS GIS Cut Line= 4
      3545322.55     10467088.38      3545248.78     10466988.58
      3545062.15     10466953.86      3544942.79     10467079.73
#Sta/Elev= 30
  4821.7   368.9  4869.1  363.73  4940.8  358.01  4945.8  358.01  4962.8  356.49
  5009.8  354.12  5023.8  352.91  5062.7  351.75  5071.7  351.22  5074.4  350.72
  5077.7  351.22    5095  352.19  5133.1  355.88  5141.2  355.65  5148.1   356.5
  5155.4  356.25  5162.3  356.98  5169.5   356.8  5183.7  357.62  5190.6  358.63
  5197.9   358.8  5204.7  359.93    5212   360.1  5218.9  361.41  5226.2  361.56
  5233.1  362.74  5240.3  362.57  5261.4  364.68  5303.8  365.85  5309.1  366.31
#Mann= 4 ,-1 , 0
  4821.7     .05       0  5062.7     .16       0  5071.7     .03       0
  5077.7     .16       0
Bank Sta=5071.7,5077.7
XS Rating Curve= 0 ,0
Exp/Cntr=0.3,0.1

Type RM Length L Ch R = 1 ,1863    ,168,168,168
BEGIN DESCRIPTION:
UNT02167 IN SAND CR 5.2
END DESCRIPTION:
XS GIS Cut Line= 4
       3545444.1     10466982.07      3545292.19     10466860.54
      3545091.45     10466832.33      3544992.73     10466929.96
#Sta/Elev= 30
  4692.3  364.87  4701.1  364.16  4729.9  362.95  4765.2  359.99  4779.6  359.92
  4835.7   355.6  4858.7  354.51  4883.7  352.84  4907.1  352.58  4918.6  351.79
  4947.5  350.93  4977.8   349.1  4986.8  348.07  4989.6  347.57  4992.8  348.07
    4998  348.08  5008.1  350.16  5018.2  350.79  5038.4  350.75    5056  351.43
  5061.1  351.16  5092.6  351.98  5109.8  353.11  5116.9  352.91    5124  353.75
  5173.4  356.13  5187.6  356.66  5201.7  356.59    5223  358.71  5228.4  358.61
#Mann= 4 ,-1 , 0
  4692.3     .05       0  4858.7     .16       0  4986.8     .07       0
  4992.8     .16       0
Bank Sta=4986.8,4992.8
XS Rating Curve= 0 ,0
Exp/Cntr=0.3,0.1

Type RM Length L Ch R = 1 ,1695    ,266,266,266
BEGIN DESCRIPTION:
UNT02167 IN SAND CR 4.0
END DESCRIPTION:
XS GIS Cut Line= 4
      3545448.41     10466839.14      3545320.36     10466743.65
      3545043.67     10466603.68      3544868.99     10466603.68
#Sta/Elev= 30
  4722.1  357.62  4781.3  355.13  4817.3  352.29  4860.5  350.64  4867.2  349.72
  4891.1  350.79  4902.6  349.11    4955   347.5  4963.9  347.04  4991.9  347.83
  4999.8  345.08  5002.6  344.58  5005.8  345.08  5008.4  345.16  5014.4  348.84
  5025.1  348.73  5030.7  351.38  5047.4  348.83    5053   348.6  5069.7  348.81
  5075.3  348.19  5097.6  348.78  5136.5  351.74  5142.1  351.52  5158.8  353.41
  5181.1  354.92  5186.7  354.47  5213.5  356.62  5283.5  362.49  5366.6  370.81
#Mann= 4 ,-1 , 0
  4722.1     .05       0    4955     .16       0  4999.8     .07       0
  5005.8     .16       0
Bank Sta=4999.8,5005.8
XS Rating Curve= 0 ,0
Exp/Cntr=0.3,0.1

Type RM Length L Ch R = 1 ,1429    ,15,15,15
BEGIN DESCRIPTION:
UNT02167 IN SAND CR 3.7
END DESCRIPTION:
XS GIS Cut Line= 4
      3545475.17     10466605.54      3545366.85     10466485.24
      3545210.07     10466410.76      3544975.93     10466362.06
#Sta/Elev= 30
  4742.5  351.77  4782.9  350.49  4789.6  349.56  4832.2  347.06  4868.1  346.73
  4874.8  345.89    4889  345.83  4919.8  344.41  4925.3  345.33  4931.8  344.57
  4942.5  344.35    4948  345.19  4953.9  344.56  4970.8  343.95  4976.3  344.37
  4993.5  343.89    4999  344.42  5013.2  343.41    5016  342.91  5019.2  343.41
  5021.8  344.55  5038.9  343.75  5044.5  344.68  5061.7   344.4  5067.2   345.1
  5077.9  345.23    5178  357.44  5208.7  358.88    5295  359.68  5317.1   360.7
#Mann= 3 ,-1 , 0
  4742.5     .16       0  5013.2     .07       0  5019.2     .16       0
Bank Sta=5013.2,5019.2
XS Rating Curve= 0 ,0
Exp/Cntr=0.3,0.1

Type RM Length L Ch R = 1 ,1414    ,19,19,19
BEGIN DESCRIPTION:
UNT02167 IN SAND CR 3.3
END DESCRIPTION:
XS GIS Cut Line= 4
      3545489.73     10466600.83       3545378.3     10466475.86
      3545212.68     10466395.65      3544976.13     10466344.82
#Sta/Elev= 30
    4735  352.92    4754  351.52  4768.2  351.72  4803.3  348.93    4846  346.71
  4860.2  346.88  4924.8  345.52  4964.4  345.73  4966.9  345.15  4969.7  344.65
  4972.9  345.15    4976  345.87  4992.5  345.33  4998.2  346.24  5015.1  345.83
  5020.7  347.15  5031.5  346.65  5037.7  345.61  5043.2   346.3  5060.3  345.49
  5089.3  345.98  5126.1  349.92  5131.2  349.96  5175.5  356.14  5180.6  356.02
  5199.5  357.94  5230.2  359.91  5274.2  360.54  5301.8  359.82  5328.4  361.05
#Mann= 3 ,-1 , 0
    4735     .16       0  4966.9     .07       0  4972.9     .16       0
Bank Sta=4966.9,4972.9
XS Rating Curve= 0 ,0
Exp/Cntr=0.3,0.1

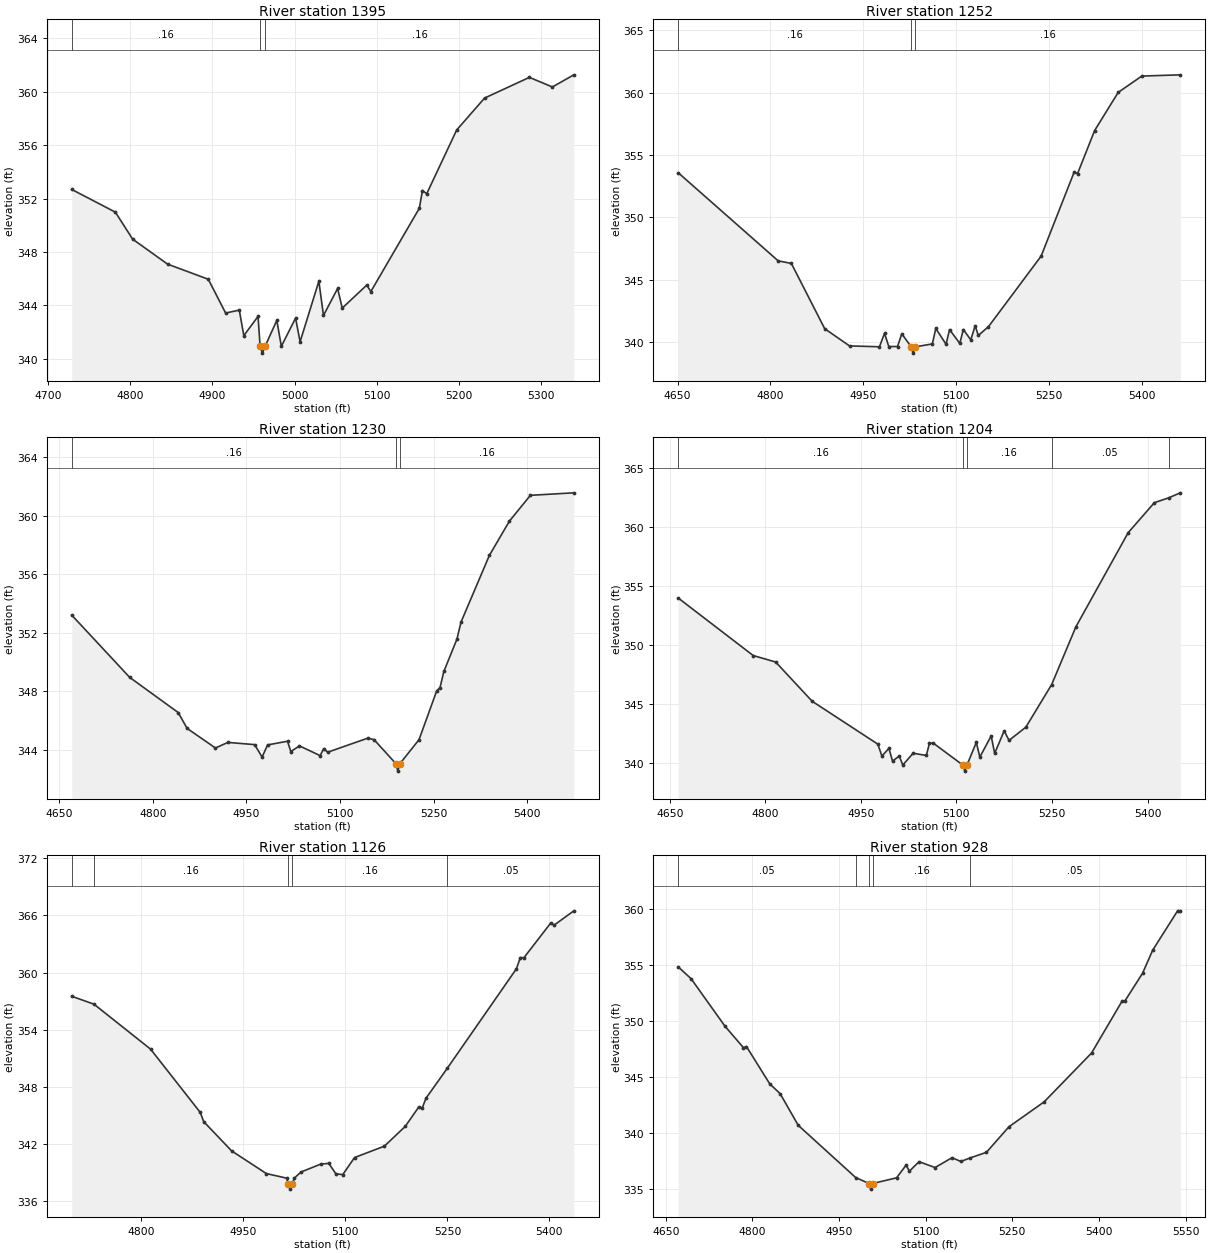
Type RM Length L Ch R = 1 ,1395    ,143,143,143
BEGIN DESCRIPTION:
UNT02167 IN SAND CR 3.5
END DESCRIPTION:
XS GIS Cut Line= 5
      3545504.35      10466594.1      3545377.78     10466454.51
      3545240.28     10466389.92      3545161.12     10466378.47
      3544976.71     10466333.27
#Sta/Elev= 30
  4729.2  352.68  4782.2  350.98  4803.2  348.96  4845.7  347.09  4895.1  345.96
  4916.2  343.43  4932.8  343.65  4938.3  341.74  4955.6  343.18  4958.1  340.93
  4960.9  340.43  4964.1  340.93  4978.4  342.88  4983.9  340.94  5001.2  343.05
  5006.7  341.28  5029.5  345.81  5035.1  343.25  5052.3  345.27  5057.9   343.8
  5087.7  345.52  5092.7  345.04  5151.6  351.27  5155.4   352.6  5160.6  352.36
    5197  357.13  5230.9  359.52  5285.4  361.07  5313.3  360.35  5339.4  361.26
#Mann= 3 ,-1 , 0
  4729.2     .16       0  4958.1     .07       0  4964.1     .16       0
Bank Sta=4958.1,4964.1
XS Rating Curve= 0 ,0
Exp/Cntr=0.3,0.1

Type RM Length L Ch R = 1 ,1252    ,22,22,22
BEGIN DESCRIPTION:
UNT02167 IN SAND CR 3.2
END DESCRIPTION:
XS GIS Cut Line= 6
      3545553.71     10466577.96      3545398.78     10466442.56
      3545376.65     10466294.13      3545310.24     10466374.86
      3545271.18     10466381.37      3544980.81     10466317.56
#Sta/Elev= 30
  4650.9  353.57  4812.4   346.5  4833.8  346.29  4887.7  341.05  4927.8  339.67
  4976.2   339.6  4984.4  340.68  4991.3  339.62  5005.4  339.62  5012.3  340.64
  5027.7  339.59  5030.5  339.09  5033.7  339.59  5061.7  339.83  5067.3  341.07
  5083.9   339.8  5089.5  340.98  5106.1  339.87  5111.8  340.98  5123.9  340.16
  5130.9  341.29    5136  340.51  5152.4  341.21  5237.6  346.88  5291.2  353.65
  5296.4  353.49  5324.1  356.96  5362.2  360.02  5400.3  361.33  5462.6  361.43
#Mann= 3 ,-1 , 0
  4650.9     .16       0  5027.7     .07       0  5033.7     .16       0
Bank Sta=5027.7,5033.7
XS Rating Curve= 0 ,0
Exp/Cntr=0.3,0.1

Type RM Length L Ch R = 1 ,1230    ,26,26,26
BEGIN DESCRIPTION:
UNT02167 IN SAND CR 3.0
END DESCRIPTION:
XS GIS Cut Line= 6
      3545562.81     10466551.91      3545426.13     10466425.64
      3545394.88      10466278.5      3545344.09     10466269.39
       3545220.4     10466365.74      3544982.15     10466296.74
#Sta/Elev= 30
  4670.1   353.2  4762.9  348.95  4840.6  346.55  4854.8  345.47  4900.2  344.13
  4920.2  344.51    4963  344.36    4975  343.51  4983.8  344.34  5015.7  344.59
    5021  343.89  5034.9  344.27    5068  343.61  5073.7  344.09    5080  343.84
  5144.2   344.8  5154.3   344.7  5189.6  343.05  5192.4  342.55  5195.6  343.05
  5226.4   344.7  5254.8  348.04    5260  348.25  5266.2  349.36  5287.1  351.56
  5293.6  352.72  5339.1  357.28  5371.2  359.62  5404.8  361.38  5474.4  361.55
#Mann= 3 ,-1 , 0
  4670.1     .16       0  5189.6     .07       0  5195.6     .16       0
Bank Sta=5189.6,5195.6
XS Rating Curve= 0 ,0
Exp/Cntr=0.3,0.1

Type RM Length L Ch R = 1 ,1204    ,78,78,78
BEGIN DESCRIPTION:
UNT02167 IN SAND CR 3.4
END DESCRIPTION:
XS GIS Cut Line= 6
      3545588.87     10466531.09      3545449.56     10466398.29
      3545377.95     10466245.95      3545307.64     10466248.55
      3545250.34     10466326.68      3545015.22     10466267.25
#Sta/Elev= 30
  4663.4  353.96  4781.1  349.08  4816.3  348.53  4873.6   345.2  4976.7  341.56
  4983.1  340.55  4994.1   341.2  4999.8  340.12  5010.3  340.55  5015.9  339.79
  5032.1  340.79  5052.8   340.6  5057.8  341.64  5063.9  341.64  5110.5  339.77
  5113.2  339.27  5116.5  339.77  5131.3  341.71  5136.8  340.46  5154.6  342.26
  5160.1  340.77    5175  342.69  5182.7  341.88    5209     343  5249.6  346.62
  5287.6  351.52  5369.7  359.51  5410.7  362.05    5433  362.46  5451.5  362.89
#Mann= 5 ,-1 , 0
  4663.4     .16       0  5110.5     .07       0  5116.5     .16       0
  5249.6     .05       0    5433     .16       0
Bank Sta=5110.5,5116.5
XS Rating Curve= 0 ,0
Exp/Cntr=0.3,0.1

Type RM Length L Ch R = 1 ,1126    ,198,198,198
BEGIN DESCRIPTION:
UNT02167 IN SAND CR 3.1
END DESCRIPTION:
XS GIS Cut Line= 3
      3545687.71     10466340.13      3545547.12     10466213.86
       3545009.4     10466100.58
#Sta/Elev= 30
  4697.5   357.5  4730.1  356.67  4813.4  351.94  4886.5  345.28  4891.6  344.31
  4932.5  341.24  4983.6  338.85  5013.8  338.36  5015.9  337.71  5018.7  337.21
  5021.9  337.71  5024.5  338.35  5034.7  339.01  5063.6  339.84  5075.6  339.92
  5085.8  338.84    5096  338.73  5113.4  340.53  5157.3  341.73    5188  343.81
  5207.9  345.85    5213  345.75  5218.6  346.78  5249.7  349.91  5351.5  360.39
  5357.3  361.57  5362.5  361.55    5402  365.21  5407.1  364.99    5436  366.49
#Mann= 5 ,-1 , 0
  4697.5     .05       0  4730.1     .16       0  5015.9     .07       0
  5021.9     .16       0  5249.7     .05       0
Bank Sta=5015.9,5021.9
XS Rating Curve= 0 ,0
Exp/Cntr=0.3,0.1

Type RM Length L Ch R = 1 ,928     ,211,211,211
BEGIN DESCRIPTION:
UNT02167 IN SAND CR 3.6
END DESCRIPTION:
XS GIS Cut Line= 4
      3545712.68     10466282.17      3545647.59     10466082.54
      3545272.15     10465891.57      3545037.83     10465934.96
#Sta/Elev= 30
  4671.5  354.86  4693.9   353.8  4752.5  349.56  4784.4  347.65  4789.6  347.75
  4829.8  344.43  4848.2  343.52  4879.3  340.71  4978.9  336.04  5002.1  335.51
  5004.8  335.01  5008.1  335.51  5049.6  336.02  5066.2  337.16  5071.8  336.61
  5088.5  337.46  5116.3  336.94  5145.7  337.82  5160.8  337.48  5177.3   337.8
  5205.3   338.3  5244.2  340.58  5305.3  342.81  5387.3  347.17  5440.2  351.81
  5445.3  351.84  5475.6  354.29  5493.1  356.35  5536.3  359.87    5541  359.87
#Mann= 5 ,-1 , 0
  4671.5     .05       0  4978.9     .16       0  5002.1     .07       0
  5008.1     .16       0  5177.3     .05       0
Bank Sta=5002.1,5008.1
XS Rating Curve= 0 ,0
Exp/Cntr=0.3,0.1

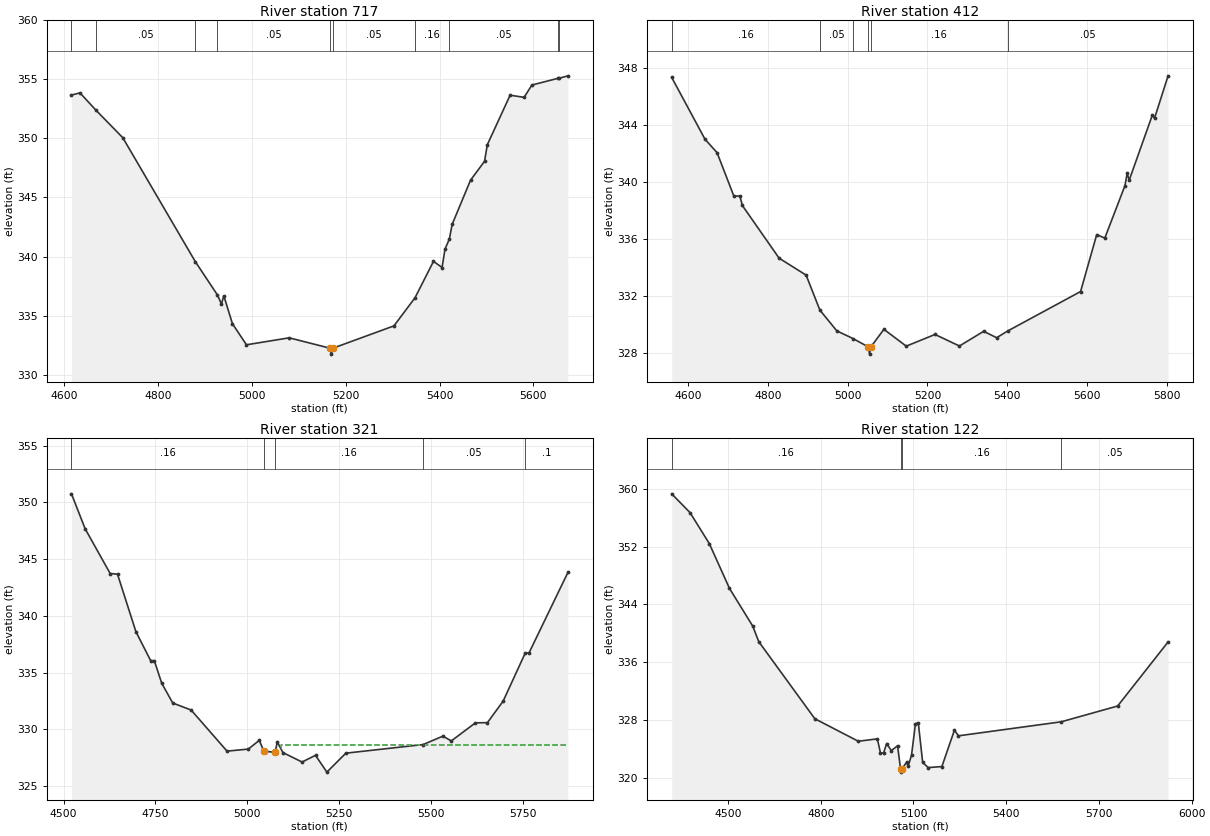
Type RM Length L Ch R = 1 ,717     ,305,305,305
BEGIN DESCRIPTION:
UNT02167 IN SAND CR 2.0
END DESCRIPTION:
XS GIS Cut Line= 5
      3545784.54     10466309.39      3545702.94     10465859.69
      3545223.77     10465673.93      3545227.24     10465675.66
      3545146.42     10465698.02
#Sta/Elev= 30
    4615  353.66    4633  353.85  4667.7  352.36  4724.5  350.05  4879.2  339.56
  4926.4  336.74  4934.8  335.98  4939.9  336.68  4958.3  334.31  4988.2  332.53
  5079.4  333.12  5166.5  332.24  5169.2  331.74  5172.5  332.24  5302.7  334.13
  5347.7  336.51  5387.1  339.59  5405.4  339.07  5411.6  340.62    5421  341.49
  5426.9  342.72  5466.1  346.46    5496  348.06  5501.9  349.46  5550.5  353.65
  5580.4  353.47  5596.9  354.51  5652.7  355.08  5654.1  355.07  5673.7  355.29
#Mann= 10 ,-1 , 0
    4615     .16       0  4667.7     .05       0  4879.2     .16       0
  4926.4     .05       0  5166.5     .03       0  5172.5     .05       0
  5347.7     .16       0    5421     .05       0  5652.7      .1       0
  5654.1     .16       0
Bank Sta=5166.5,5172.5
XS Rating Curve= 0 ,0
Exp/Cntr=0.3,0.1

Type RM Length L Ch R = 1 ,412     ,91,91,91
BEGIN DESCRIPTION:
UNT02167 IN SAND CR 2.01
END DESCRIPTION:
XS GIS Cut Line= 5
      3545902.57     10466268.49      3546052.33      10466040.6
       3545995.9     10465817.08      3545841.82     10465693.38
       3545305.4     10465611.19
#Sta/Elev= 30
  4559.4  347.35  4642.9  343.01  4673.1  342.07  4715.2  339.02  4730.3  339.03
  4736.3  338.37  4828.5  334.67  4896.2  333.48  4930.6  331.03  4973.1  329.57
  5013.9  329.03  5052.2  328.44    5055  327.94  5058.2  328.44    5091  329.68
    5147   328.5    5219  329.32  5280.2  328.51  5340.9  329.54  5373.5  329.09
  5400.9  329.56  5583.7  332.33  5624.1  336.32  5644.4  336.08  5694.9  339.76
  5700.4  340.62  5705.5  340.14  5763.8  344.73  5768.9  344.48  5802.9  347.46
#Mann= 6 ,-1 , 0
  4559.4     .16       0  4930.6     .05       0  5013.9     .16       0
  5052.2     .03       0  5058.2     .16       0  5400.9     .05       0
Bank Sta=5052.2,5058.2
XS Rating Curve= 0 ,0
Exp/Cntr=0.3,0.1

Type RM Length L Ch R = 1 ,321     ,199,199,199
BEGIN DESCRIPTION:
UNT02167 IN SAND CR 2.011
END DESCRIPTION:
XS GIS Cut Line= 4
      3546179.04     10466286.64       3546159.5     10465943.77
      3545972.87      10465644.3      3545325.53      10465551.2
#Sta/Elev= 30
  4521.5  350.75  4558.5  347.68  4626.7  343.73  4646.7  343.67  4696.8   338.6
  4736.8  336.06  4746.9  336.04  4766.9  334.07  4796.9  332.32    4847   331.7
  4944.6  328.08  5002.4  328.26  5032.4  329.03  5044.8  328.07  5075.5  327.98
  5081.4  328.89  5096.8  327.95  5148.7  327.12  5185.3  327.71  5216.2  326.23
  5267.8   327.9  5478.2  328.66  5531.8   329.4  5554.8  328.98  5620.2  330.57
    5653  330.59  5695.8  332.49  5755.8  336.72  5766.2  336.74  5871.8  343.82
#Mann= 5 ,-1 , 0
  4521.5     .16       0  5044.8     .07       0  5075.5     .16       0
  5478.2     .05       0  5755.8      .1       0
#XS Ineff= 2 , 0
       0                    5091       0  328.59
Permanent Ineff=
       F       T
Bank Sta=5044.8,5075.5
XS Rating Curve= 0 ,0
Exp/Cntr=0.3,0.1

Type RM Length L Ch R = 1 ,122     ,0,0,0
BEGIN DESCRIPTION:
UNT02167 IN SAND CR 1.0
END DESCRIPTION:
XS GIS Cut Line= 5
      3546344.03     10466400.41      3546252.88     10465769.99
      3546251.79      10465696.2      3546062.99     10465613.74
      3545380.49     10465519.34
#Sta/Elev= 30
  4317.9  359.29  4377.3  356.69  4439.6  352.41  4504.8  346.22  4580.2  340.99
  4599.6  338.85    4781  328.19  4921.6  325.08  4983.2  325.41  4993.2  323.47
  5003.2  323.44  5013.2  324.76  5028.5  323.79  5048.6  324.45  5058.1  321.31
  5060.8  320.81  5064.1  321.31  5077.5  322.18  5082.9  321.64  5093.8  323.16
  5106.4  327.49  5115.6  327.65  5129.8  322.15  5147.7  321.44    5192  321.58
  5232.5  326.61  5245.7  325.83  5578.2  327.77  5760.5  329.95  5923.7  338.81
#Mann= 4 ,-1 , 0
  4317.9     .16       0  5058.1     .07       0  5064.1     .16       0
  5578.2     .05       0
Bank Sta=5058.1,5064.1
XS Rating Curve= 0 ,0
Exp/Cntr=0.3,0.1

Chan Stop Cuts=-1
Use User Specified Reach Order=0
Composite Channel Slope=5