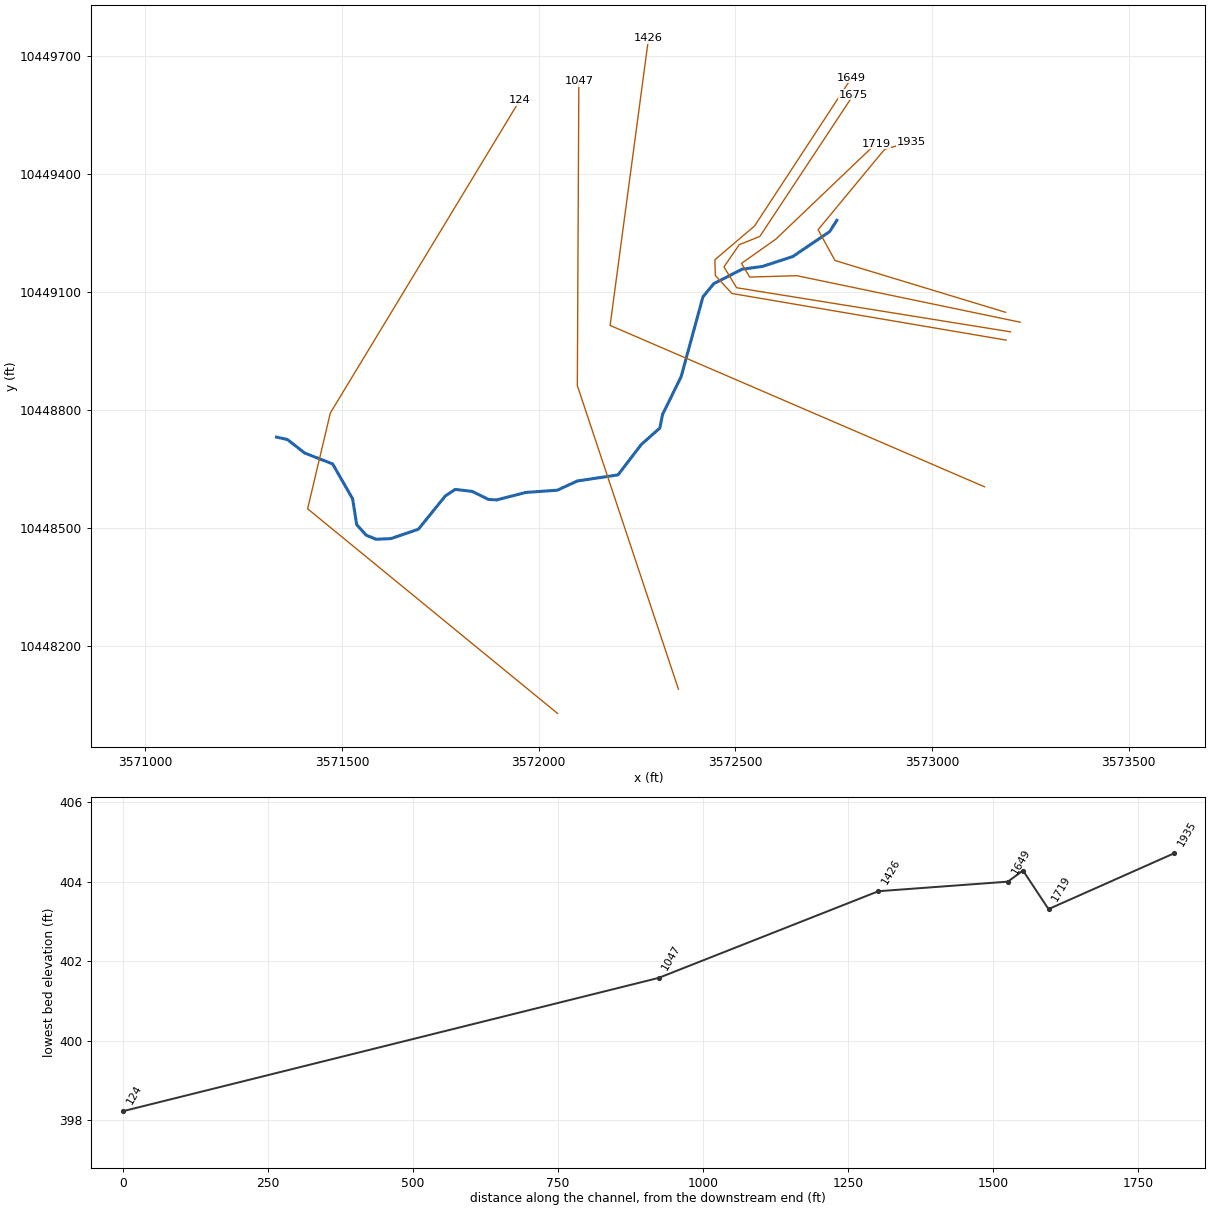
--- UNT02280 IN SAND CR.prj (project) ---

Proj Title=UNT02280 IN SAND CR Base Level Engineering
Current Plan=p01
Default Exp/Contr=0.3,0.1
English Units
Geom File=g01
Flow File=f01
Plan File=p01
BEGIN DESCRIPTION:
UNT02280 IN SAND CR
END DESCRIPTION:

--- UNT02280 IN SAND CR.p01 (plan) ---

Plan Title=Multiple Run
Short Identifier=Multiple
Geom File=g01
Flow File=f01
Subcritical Flow
K Sum by GR= 0
Std Step Tol= 0.01
Critical Tol= 0.01
Num of Std Step Trials= 20
Max Error Tol= 0.3
Flow Tol Ratio= 0.001
Split Flow NTrial= 30
Split Flow Tol= 0.02
Split Flow Ratio= 0.02
Log Output Level= 0
Friction Slope Method= 1
Unsteady Friction Slope Method= 2
Unsteady Bridges Friction Slope Method= 1
Parabolic Critical Depth
Global Vel Dist=  1 , 1 , 1
Global Log Level= 0
CheckData=True
Encroach Param= -1, 0, 0, 0
BEGIN DESCRIPTION:
Multiple Run
END DESCRIPTION:

--- UNT02280 IN SAND CR.f01 (steady flow) ---

Flow Title=Multiple
Number of Profiles=7
Profile Names=10-year,25-year,50-year,1pct_min,100-year,1pct_plu,500-year
River Rch & RM= UNT02280 IN SAND,Reach-1,1935
     329     416     482     408     551     746     719
Boundary for River Rch & Prof#=UNT02280 IN SAND,Reach-1,1
Up Type=0
Dn Type=3
Dn Slope=0.005
Boundary for River Rch & Prof#=UNT02280 IN SAND,Reach-1,2
Up Type=0
Dn Type=3
Dn Slope=0.005
Boundary for River Rch & Prof#=UNT02280 IN SAND,Reach-1,3
Up Type=0
Dn Type=3
Dn Slope=0.005
Boundary for River Rch & Prof#=UNT02280 IN SAND,Reach-1,4
Up Type=0
Dn Type=3
Dn Slope=0.005
Boundary for River Rch & Prof#=UNT02280 IN SAND,Reach-1,5
Up Type=0
Dn Type=3
Dn Slope=0.005
Boundary for River Rch & Prof#=UNT02280 IN SAND,Reach-1,6
Up Type=0
Dn Type=3
Dn Slope=0.005
Boundary for River Rch & Prof#=UNT02280 IN SAND,Reach-1,7
Up Type=0
Dn Type=3
Dn Slope=0.005

--- UNT02280 IN SAND CR.g01 (geometry) ---

Geom Title=Existing Conditions

River Reach=UNT02280 IN SAND,Reach-1
Reach XY= 30
      3572758.00     10449281.70      3572739.77     10449253.06
      3572646.02     10449189.69      3572568.76     10449164.52
      3572517.54     10449157.57      3572445.50     10449121.11
      3572417.72     10449087.26      3572362.16     10448884.13
      3572315.13     10448789.00      3572308.19     10448754.27
      3572261.14     10448712.48      3572201.76     10448635.13
      3572098.64     10448619.77      3572047.60     10448596.33
      3571967.13     10448590.60      3571893.58     10448571.59
      3571872.75     10448572.89      3571831.08     10448593.29
      3571787.82     10448598.29      3571762.84     10448581.61
      3571694.50     10448497.22      3571624.63     10448473.37
      3571587.21     10448471.69      3571561.98     10448481.80
      3571537.64     10448508.83      3571527.30     10448574.36
      3571476.48     10448663.04      3571405.39     10448690.72
      3571361.46     10448725.09      3571333.91     10448730.97

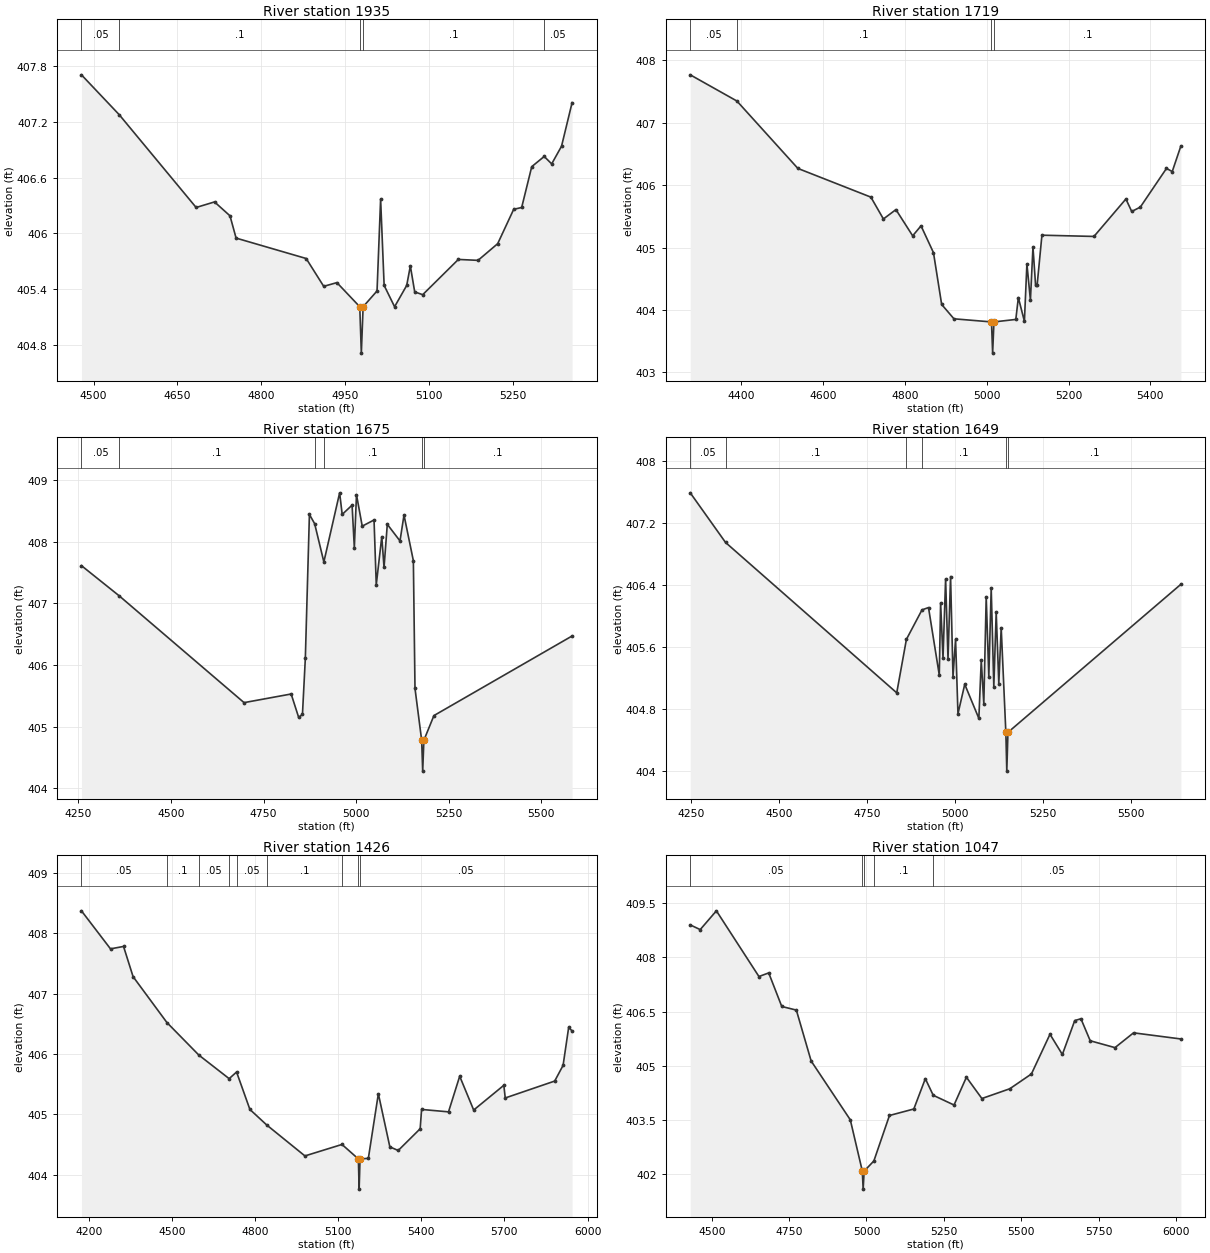
Type RM Length L Ch R = 1,1935,216,216,216
BEGIN DESCRIPTION:
UNT02280 IN SAND CR 1.1
END DESCRIPTION:
XS GIS Cut Line= 5
      3573186.91     10449048.12      3572753.33     10449179.63
      3572710.36     10449257.76      3572879.63     10449462.18
      3572947.25     10449481.22
#Sta/Elev= 30
  4478.2  407.71  4545.8  407.28  4683.4  406.28  4716.3  406.34  4744.0  406.19
  4754.9  405.95  4880.3  405.73  4911.7  405.43  4935.3  405.47  4976.2  405.21
  4979.0  404.71  4982.2  405.21  5007.1  405.38  5013.5  406.37  5019.8  405.44
  5038.5  405.21  5060.2  405.44  5066.7  405.65  5074.5  405.37  5088.8  405.34
  5152.6  405.72  5187.8  405.71  5223.0  405.89  5251.6  406.26  5265.9  406.28
  5283.9  406.72  5306.2  406.83  5319.6  406.75  5337.2  406.94  5356.1  407.41
#Mann=5,-1,0
  4478.2    0.05       0  4545.8     0.1       0  4976.2    0.07       0
  4982.2     0.1       0  5306.2    0.05       0
Bank Sta=4976.2,4982.2
Exp/Cntr=0.3,0.1

Type RM Length L Ch R = 1,1719,44,44,44
BEGIN DESCRIPTION:
UNT02280 IN SAND CR 1.0
END DESCRIPTION:
XS GIS Cut Line= 6
      3573224.02     10449023.00      3572656.35     10449141.04
      3572536.56     10449137.57      3572515.73     10449172.29
      3572603.23     10449234.10      3572857.31     10449476.45
#Sta/Elev= 30
  4276.0  407.77  4390.0  407.35  4538.9  406.27  4717.2  405.81  4747.8  405.46
  4778.4  405.61  4819.3  405.19  4839.7  405.35  4870.1  404.92  4890.1  404.09
  4920.1  403.86  5011.8  403.81  5014.6  403.31  5017.8  403.81  5071.2  403.85
  5077.4  404.20  5092.2  403.82  5098.3  404.74  5106.9  404.16  5113.1  405.01
  5119.5  404.40  5123.3  404.40  5135.0  405.20  5262.1  405.18  5340.1  405.78
  5354.3  405.58  5375.3  405.65  5439.2  406.27  5453.3  406.22  5474.4  406.63
#Mann=4,-1,0
  4276.0    0.05       0  4390.0     0.1       0  5011.8    0.07       0
  5017.8     0.1       0
Bank Sta=5011.8,5017.8
Exp/Cntr=0.3,0.1

Type RM Length L Ch R = 1,1675,26,26,26
BEGIN DESCRIPTION:
UNT02280 IN SAND CR 3.0
END DESCRIPTION:
XS GIS Cut Line= 6
      3573199.37     10448998.52      3572503.23     10449110.49
      3572471.11     10449163.44      3572510.17     10449219.86
      3572562.25     10449240.70      3572800.69     10449601.17
#Sta/Elev= 30
  4258.3  407.61  4360.4  407.12  4697.4  405.39  4824.6  405.53  4844.9  405.15
  4855.1  405.20  4862.9  406.11  4873.9  408.44  4888.0  408.29  4912.9  407.67
  4955.5  408.79  4962.4  408.44  4989.1  408.59  4995.2  407.90  5001.0  408.76
  5016.5  408.25  5048.4  408.35  5054.4  407.30  5069.3  408.08  5075.4  407.58
  5084.2  408.28  5118.5  408.01  5129.3  408.43  5154.6  407.69  5159.0  405.62
  5177.0  404.78  5179.8  404.28  5183.0  404.78  5210.1  405.18  5583.2  406.47
#Mann=6,-1,0
  4258.3    0.05       0  4360.4     0.1       0  4888.0    0.05       0
  4912.9     0.1       0  5177.0    0.07       0  5183.0     0.1       0
Bank Sta=5177,5183
Exp/Cntr=0.3,0.1

Type RM Length L Ch R = 1,1649,223,223,223
BEGIN DESCRIPTION:
UNT02280 IN SAND CR 2.0
END DESCRIPTION:
XS GIS Cut Line= 6
      3573188.17     10448977.52      3572491.51     10449095.81
      3572449.19     10449141.38      3572448.11     10449181.53
      3572549.02     10449267.46      3572795.53     10449643.66
#Sta/Elev= 30
  4247.1  407.59  4347.4  406.95  4834.0  405.01  4861.5  405.70  4905.8  406.08
  4924.3  406.11  4954.9  405.24  4958.7  406.17  4965.5  405.46  4972.9  406.48
  4979.7  405.45  4987.0  406.51  4993.9  405.22  5001.2  405.70  5008.0  404.74
  5027.3  405.12  5067.4  404.68  5074.2  405.43  5081.5  404.87  5088.3  406.25
  5095.7  405.22  5102.5  406.36  5109.9  405.09  5116.7  406.05  5124.1  405.13
  5130.9  405.85  5144.1  404.50  5146.8  404.00  5150.1  404.50  5641.6  406.41
#Mann=6,-1,0
  4247.1    0.05       0  4347.4     0.1       0  4861.5    0.05       0
  4905.8     0.1       0  5144.1    0.07       0  5150.1     0.1       0
Bank Sta=5144.1,5150.1
Exp/Cntr=0.3,0.1

Type RM Length L Ch R = 1,1426,379,379,379
BEGIN DESCRIPTION:
UNT02280 IN SAND CR 5.0
END DESCRIPTION:
XS GIS Cut Line= 3
      3573133.20     10448605.01      3572181.79     10449014.74
      3572279.40     10449743.85
#Sta/Elev= 30
  4172.8  408.37  4277.7  407.74  4324.8  407.78  4359.2  407.28  4481.3  406.52
  4596.8  405.98  4706.1  405.59  4732.9  405.70  4781.0  405.08  4842.4  404.82
  4979.7  404.31  5113.5  404.50  5172.7  404.26  5175.4  403.76  5178.7  404.26
  5208.7  404.27  5244.8  405.34  5286.3  404.46  5316.5  404.40  5395.8  404.76
  5400.9  405.08  5498.1  405.04  5538.5  405.63  5589.0  405.07  5697.9  405.48
  5702.9  405.27  5881.5  405.55  5911.8  405.81  5932.0  406.44  5944.3  406.38
#Mann=9,-1,0
  4172.8    0.05       0  4481.3     0.1       0  4596.8    0.05       0
  4706.1     0.1       0  4732.9    0.05       0  4842.4     0.1       0
  5113.5    0.05       0  5172.7    0.07       0  5178.7    0.05       0
Bank Sta=5172.7,5178.7
Exp/Cntr=0.3,0.1

Type RM Length L Ch R = 1,1047,923,923,923
BEGIN DESCRIPTION:
UNT02280 IN SAND CR 6.0
END DESCRIPTION:
XS GIS Cut Line= 3
      3572355.40     10448091.12      3572098.45     10448861.96
      3572102.32     10449634.51
#Sta/Elev= 30
  4430.7  408.90  4462.9  408.77  4515.2  409.29  4652.6  407.47  4684.2  407.57
  4726.4  406.64  4773.5  406.54  4821.3  405.13  4947.8  403.50  4986.6  402.08
  4989.3  401.58  4992.6  402.08  5023.9  402.36  5074.3  403.62  5153.0  403.80
  5190.2  404.64  5215.7  404.18  5282.9  403.91  5322.9  404.68  5372.9  404.09
  5462.9  404.36  5532.9  404.77  5592.9  405.87  5632.9  405.31  5672.9  406.25
  5692.9  406.30  5722.9  405.69  5802.9  405.50  5862.9  405.91  6015.8  405.74
#Mann=5,-1,0
  4430.7    0.05       0  4986.6    0.03       0  4992.6    0.05       0
  5023.9     0.1       0  5215.7    0.05       0
Bank Sta=4986.6,4992.6
Exp/Cntr=0.3,0.1

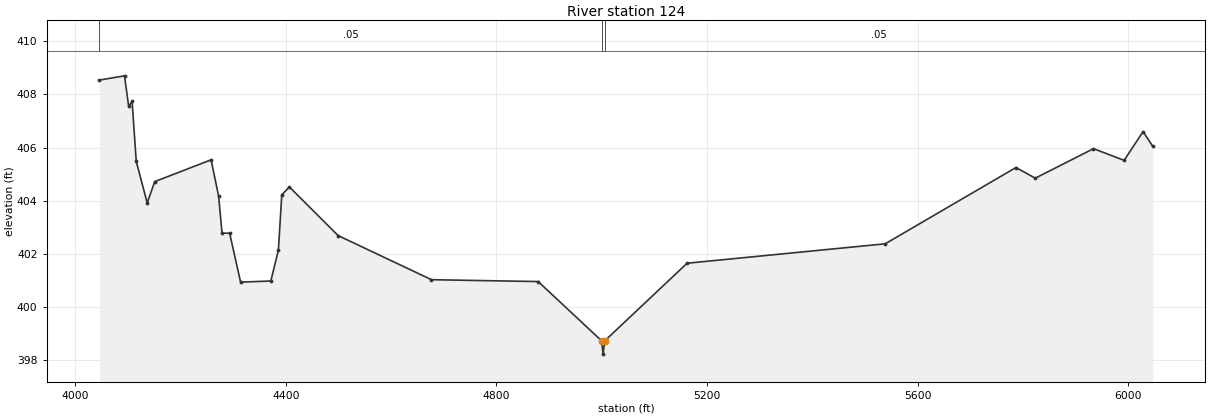
Type RM Length L Ch R = 1,124,0,0,0
BEGIN DESCRIPTION:
UNT02280 IN SAND CR 4.0
END DESCRIPTION:
XS GIS Cut Line= 4
      3572047.95     10448029.52      3571412.95     10448549.06
      3571470.68     10448792.33      3571952.64     10449587.37
#Sta/Elev= 30
  4046.1  408.54  4093.9  408.70  4101.8  407.55  4108.3  407.74  4116.2  405.48
  4137.0  403.92  4151.3  404.72  4258.3  405.54  4272.6  404.17  4279.1  402.78
  4293.5  402.78  4314.3  400.94  4371.7  400.98  4386.1  402.14  4392.5  404.22
  4406.9  404.52  4499.5  402.69  4676.8  401.03  4879.4  400.96  4999.8  398.73
  5002.6  398.23  5005.8  398.73  5162.1  401.65  5538.3  402.38  5786.5  405.25
  5823.3  404.85  5933.8  405.96  5992.0  405.52  6027.9  406.60  6046.3  406.05
#Mann=3,-1,0
  4046.1    0.05       0  4999.8   0.035       0  5005.8    0.05       0
Bank Sta=4999.8,5005.8
Exp/Cntr=0.3,0.1

Chan Stop Cuts=-1