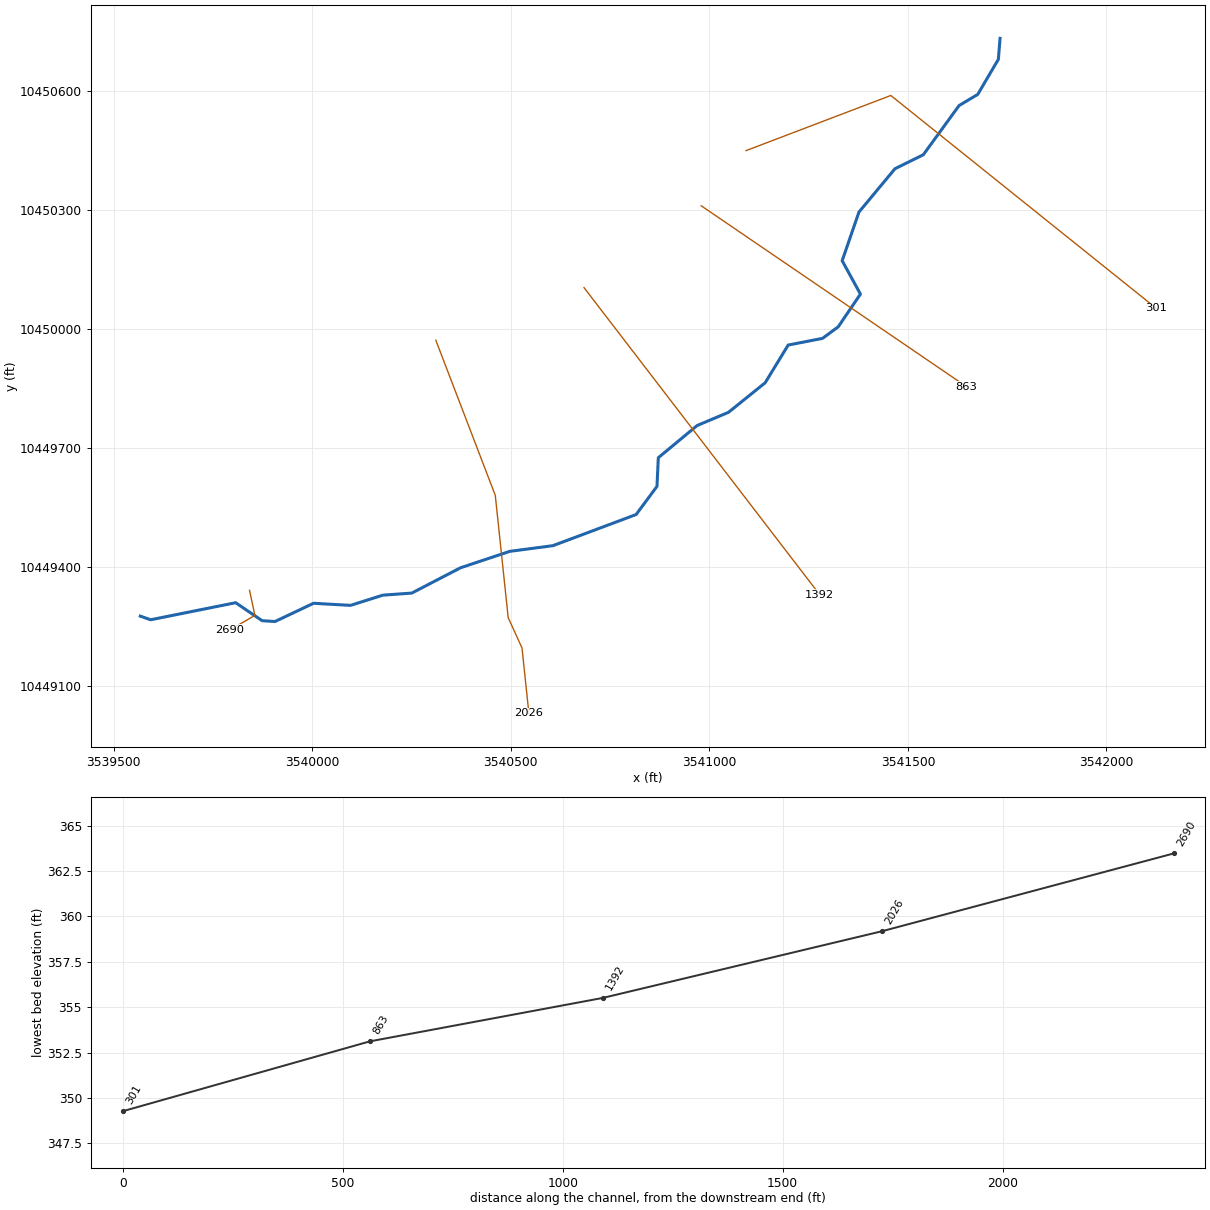
--- UNT02311 IN SAND CR.prj (project) ---

Proj Title=UNT02311 IN SAND CR Base Level Engineering
Current Plan=p01
Default Exp/Contr=0.3,0.1
English Units
Geom File=g01
Flow File=f01
Plan File=p01
BEGIN DESCRIPTION:
UNT02311 IN SAND CR
END DESCRIPTION:

--- UNT02311 IN SAND CR.p01 (plan) ---

Plan Title=Multiple Run
Short Identifier=Multiple
Geom File=g01
Flow File=f01
Subcritical Flow
K Sum by GR= 0
Std Step Tol= 0.01
Critical Tol= 0.01
Num of Std Step Trials= 20
Max Error Tol= 0.3
Flow Tol Ratio= 0.001
Split Flow NTrial= 30
Split Flow Tol= 0.02
Split Flow Ratio= 0.02
Log Output Level= 0
Friction Slope Method= 1
Unsteady Friction Slope Method= 2
Unsteady Bridges Friction Slope Method= 1
Parabolic Critical Depth
Global Vel Dist=  1 , 1 , 1
Global Log Level= 0
CheckData=True
Encroach Param= -1, 0, 0, 0
BEGIN DESCRIPTION:
Multiple Run
END DESCRIPTION:

--- UNT02311 IN SAND CR.f01 (steady flow) ---

Flow Title=Multiple
Number of Profiles=7
Profile Names=10-year,25-year,50-year,1pct_min,100-year,1pct_plu,500-year
River Rch & RM= UNT02311 IN SAND,Reach-1,2690
     306     390     455     390     527     713     701
Boundary for River Rch & Prof#=UNT02311 IN SAND,Reach-1,1
Up Type=0
Dn Type=3
Dn Slope=0.005
Boundary for River Rch & Prof#=UNT02311 IN SAND,Reach-1,2
Up Type=0
Dn Type=3
Dn Slope=0.005
Boundary for River Rch & Prof#=UNT02311 IN SAND,Reach-1,3
Up Type=0
Dn Type=3
Dn Slope=0.005
Boundary for River Rch & Prof#=UNT02311 IN SAND,Reach-1,4
Up Type=0
Dn Type=3
Dn Slope=0.005
Boundary for River Rch & Prof#=UNT02311 IN SAND,Reach-1,5
Up Type=0
Dn Type=3
Dn Slope=0.005
Boundary for River Rch & Prof#=UNT02311 IN SAND,Reach-1,6
Up Type=0
Dn Type=3
Dn Slope=0.005
Boundary for River Rch & Prof#=UNT02311 IN SAND,Reach-1,7
Up Type=0
Dn Type=3
Dn Slope=0.005

--- UNT02311 IN SAND CR.g01 (geometry) ---

Geom Title=Existing Conditions

River Reach=UNT02311 IN SAND,Reach-1
Reach XY= 30
      3539567.11     10449276.64      3539593.11     10449267.46
      3539807.17     10449310.43      3539873.79     10449265.15
      3539906.16     10449263.06      3540003.31     10449308.97
      3540096.42     10449303.71      3540177.73     10449329.39
      3540250.83     10449334.73      3540373.46     10449398.38
      3540497.35     10449439.72      3540606.10     10449454.07
      3540815.65     10449532.50      3540868.12     10449603.41
      3540871.53     10449675.55      3540969.25     10449756.62
      3541048.16     10449789.79      3541140.60     10449864.30
      3541198.53     10449959.24      3541285.08     10449976.10
      3541324.52     10450005.15      3541380.46     10450087.56
      3541334.47     10450171.62      3541376.75     10450294.15
      3541467.50     10450403.29      3541538.77     10450438.43
      3541628.83     10450562.29      3541675.87     10450590.39
      3541727.77     10450678.77      3541732.11     10450731.64

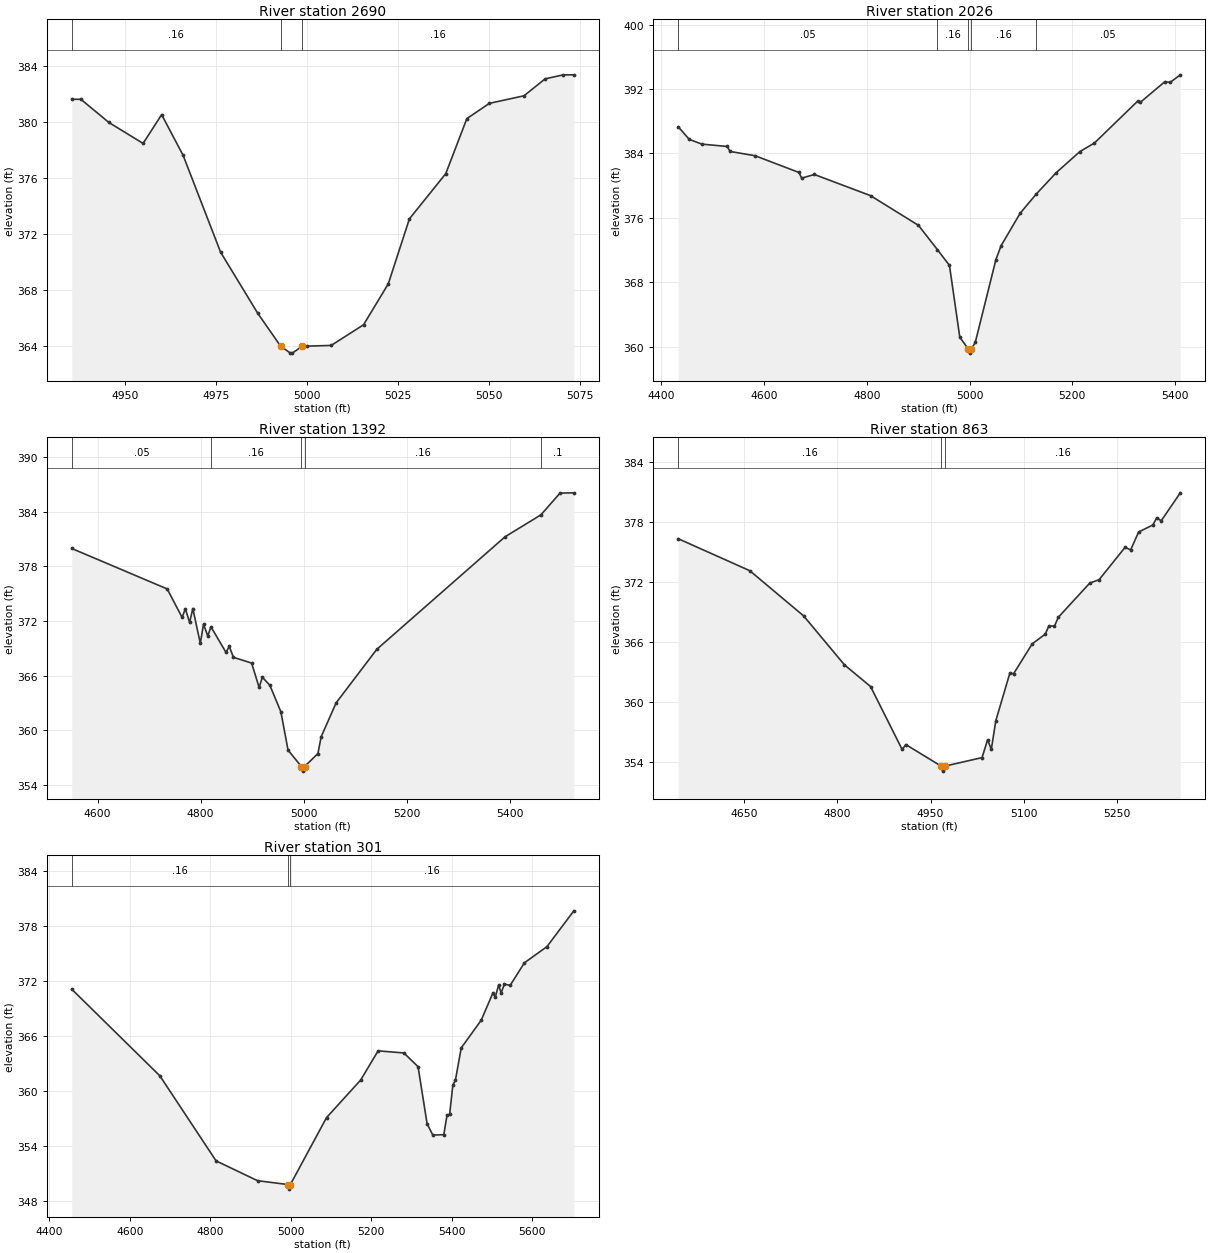
Type RM Length L Ch R = 1,2690,664,664,664
BEGIN DESCRIPTION:
UNT02311 IN SAND CR 6.0
END DESCRIPTION:
XS GIS Cut Line= 3
      3539842.12     10449341.60      3539855.58     10449278.42
      3539792.07     10449241.62
#Sta/Elev= 24
  4935.4  381.64  4937.9  381.64  4945.6  379.98  4955.0  378.48  4960.1  380.54
  4966.0  377.63  4976.3  370.70  4986.5  366.33  4992.8  363.97  4995.5  363.47
  4996.0  363.47  4998.8  363.97  5000.0  363.97  5006.7  364.02  5015.6  365.50
  5022.4  368.43  5028.2  373.08  5038.2  376.32  5044.0  380.26  5050.2  381.35
  5059.7  381.89  5065.5  383.10  5070.5  383.39  5073.4  383.39
#Mann=3,-1,0
  4935.4    0.16       0  4992.8    0.07       0  4998.8    0.16       0
Bank Sta=4992.8,4998.8
Exp/Cntr=0.3,0.1

Type RM Length L Ch R = 1,2026,634,634,634
BEGIN DESCRIPTION:
UNT02311 IN SAND CR 4.0
END DESCRIPTION:
XS GIS Cut Line= 5
      3540311.19     10449971.43      3540460.94     10449580.80
      3540493.49     10449272.64      3540528.21     10449196.68
      3540545.57     10449031.74
#Sta/Elev= 30
  4432.7  387.30  4454.2  385.73  4478.9  385.14  4528.3  384.85  4533.6  384.23
  4582.4  383.70  4667.7  381.62  4673.1  380.92  4697.8  381.37  4807.2  378.74
  4900.5  375.05  4937.5  372.02  4960.8  370.08  4980.9  361.17  4997.5  359.68
  5000.2  359.18  5003.5  359.68  5011.1  360.52  5051.3  370.81  5061.4  372.53
  5098.4  376.55  5129.8  378.94  5168.6  381.59  5214.6  384.21  5243.1  385.28
  5327.2  390.48  5332.2  390.32  5380.2  392.90  5390.3  392.80  5410.3  393.75
#Mann=5,-1,0
  4432.7    0.05       0  4937.5    0.16       0  4997.5    0.07       0
  5003.5    0.16       0  5129.8    0.05       0
Bank Sta=4997.5,5003.5
Exp/Cntr=0.3,0.1

Type RM Length L Ch R = 1,1392,529,529,529
BEGIN DESCRIPTION:
UNT02311 IN SAND CR 3.0
END DESCRIPTION:
XS GIS Cut Line= 2
      3540684.46     10450103.80      3541278.09     10449330.35
#Sta/Elev= 30
  4549.7  379.95  4735.0  375.51  4764.0  372.38  4770.3  373.34  4778.5  371.83
  4784.8  373.36  4799.3  369.54  4805.6  371.65  4813.8  370.34  4820.0  371.35
  4849.2  368.54  4855.5  369.21  4863.7  368.00  4899.0  367.37  4913.5  364.70
  4919.8  365.82  4934.4  364.93  4955.8  362.02  4969.7  357.82  4995.7  356.01
  4998.5  355.51  5001.7  356.01  5027.7  357.44  5034.0  359.28  5063.1  363.01
  5142.0  368.88  5391.2  381.24  5460.7  383.64  5497.9  386.03  5524.7  386.06
#Mann=5,-1,0
  4549.7    0.05       0  4820.0    0.16       0  4995.7    0.07       0
  5001.7    0.16       0  5460.7     0.1       0
Bank Sta=4995.7,5001.7
Exp/Cntr=0.3,0.1

Type RM Length L Ch R = 1,863,562,562,562
BEGIN DESCRIPTION:
UNT02311 IN SAND CR 2.0
END DESCRIPTION:
XS GIS Cut Line= 2
      3540979.61     10450309.96      3541647.53     10449854.56
#Sta/Elev= 30
  4543.8  376.31  4659.0  373.12  4745.7  368.61  4811.5  363.72  4853.5  361.56
  4904.3  355.28  4910.3  355.77  4967.1  353.62  4969.8  353.12  4973.1  353.62
  5033.0  354.47  5041.9  356.25  5047.9  355.30  5055.2  358.17  5077.8  362.91
  5083.8  362.84  5113.7  365.82  5134.7  366.79  5140.7  367.62  5149.6  367.58
  5155.6  368.46  5206.5  371.89  5221.4  372.22  5263.4  375.46  5272.2  375.19
  5285.1  376.98  5308.1  377.69  5314.2  378.40  5321.4  378.10  5352.2  380.89
#Mann=3,-1,0
  4543.8    0.16       0  4967.1    0.07       0  4973.1    0.16       0
Bank Sta=4967.1,4973.1
Exp/Cntr=0.3,0.1

Type RM Length L Ch R = 1,301,0,0,0
BEGIN DESCRIPTION:
UNT02311 IN SAND CR 1.0
END DESCRIPTION:
XS GIS Cut Line= 3
      3541092.44     10450448.85      3541457.03     10450587.74
      3542125.41     10450051.74
#Sta/Elev= 30
  4456.0  371.10  4674.8  361.64  4814.5  352.35  4917.5  350.19  4992.9  349.77
  4995.7  349.27  4998.9  349.77  5088.7  357.08  5173.6  361.19  5216.8  364.37
  5280.8  364.14  5316.0  362.64  5338.4  356.42  5352.6  355.17  5380.0  355.22
  5388.0  357.37  5394.4  357.42  5402.4  360.63  5408.8  361.17  5423.2  364.69
  5472.8  367.71  5501.6  370.66  5508.0  370.25  5516.0  371.56  5522.4  370.70
  5530.4  371.66  5544.8  371.52  5580.0  373.98  5636.1  375.75  5702.9  379.66
#Mann=3,-1,0
  4456.0    0.16       0  4992.9    0.07       0  4998.9    0.16       0
Bank Sta=4992.9,4998.9
Exp/Cntr=0.3,0.1

Chan Stop Cuts=-1