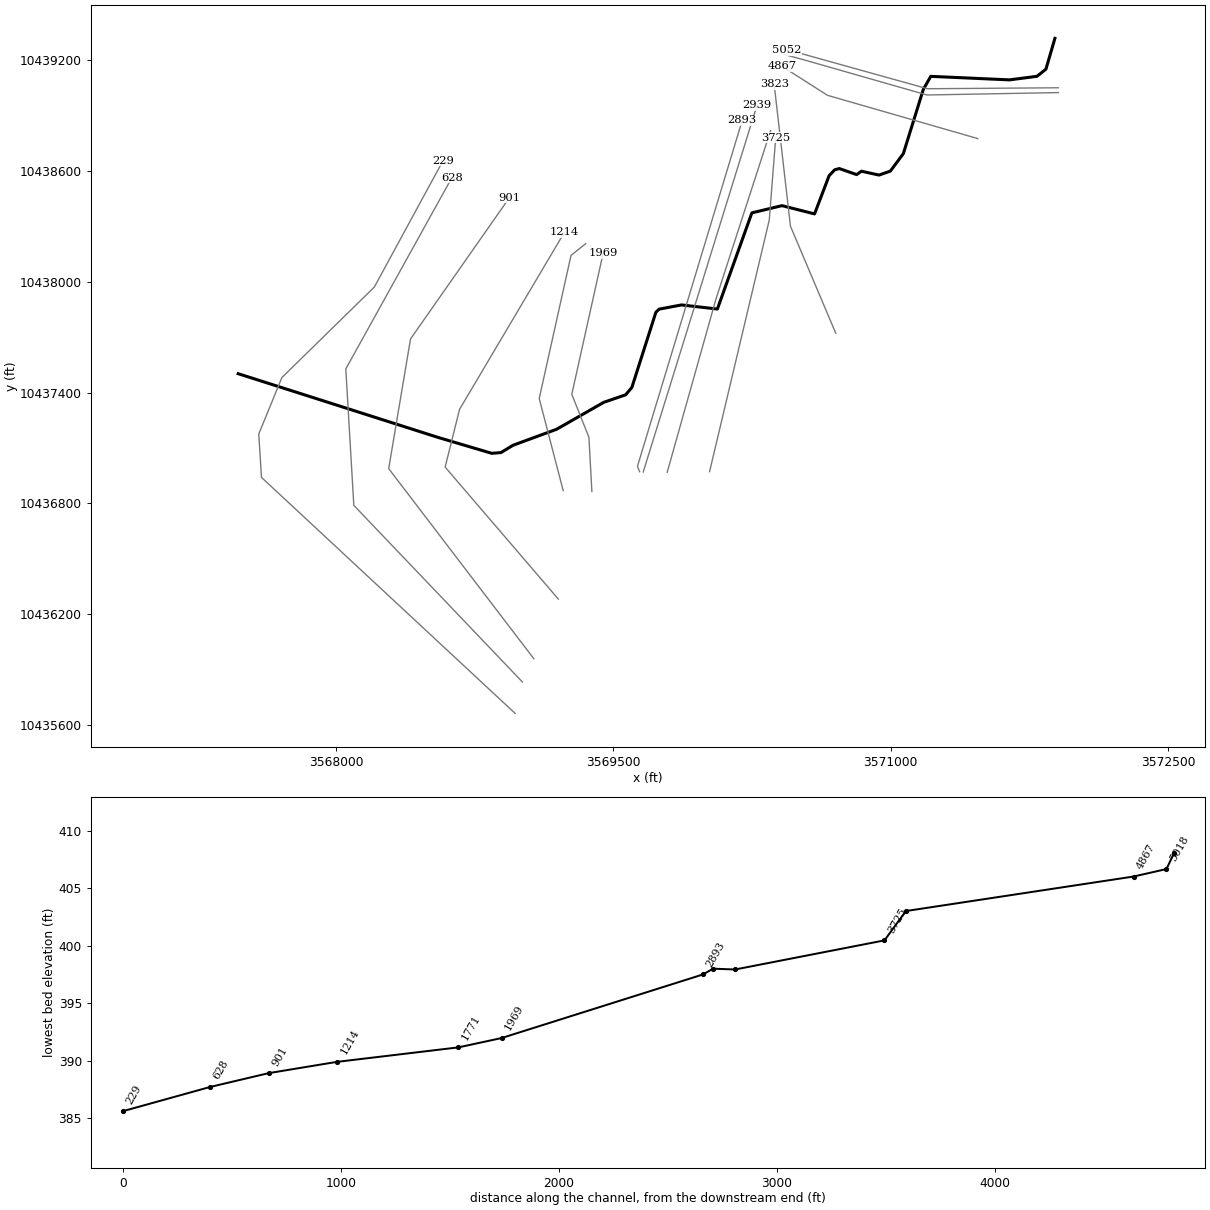
--- UNT02339 IN SAND CR.prj (project) ---

Proj Title=UNT02339 IN SAND CR Base Level Engineering
Current Plan=p01
Default Exp/Contr=0.3,0.1
English Units
Geom File=g01
Flow File=f01
Plan File=p01
Y Axis Title=Elevation
X Axis Title(PF)=Main Channel Distance
X Axis Title(XS)=Station
BEGIN DESCRIPTION:
UNT02339 IN SAND CR
END DESCRIPTION:
DSS Export Rating Curves= 0
DSS Export Rating Curve Sorted= 0
DSS Export Volume Flow Curves= 0
DXF OffsetX= 0
DXF OffsetY= 0
DXF ScaleX= 1
DXF ScaleY= 10

--- UNT02339 IN SAND CR.p01 (plan) ---

Plan Title=Multiple Run
Short Identifier=Multiple
Geom File=g01
Flow File=f01
Subcritical Flow
K Sum by GR= 0
Std Step Tol= 0.01
Critical Tol= 0.01
Num of Std Step Trials= 20
Max Error Tol= 0.3
Flow Tol Ratio= 0.001
Split Flow NTrial= 30
Split Flow Tol= 0.02
Split Flow Ratio= 0.02
Log Output Level= 0
Friction Slope Method= 1
Unsteady Friction Slope Method= 2
Unsteady Bridges Friction Slope Method= 1
Parabolic Critical Depth
Global Vel Dist=  1 , 1 , 1
Global Log Level= 0
CheckData=True
Encroach Param= -1, 0, 0, 0
BEGIN DESCRIPTION:
Multiple Run
END DESCRIPTION:

--- UNT02339 IN SAND CR.f01 (steady flow) ---

Flow Title=Multiple
Program Version=4.10
Number of Profiles= 7
Profile Names=10-year,25-year,50-year,1pct_min,100-year,1pct_plu,500-year
River Rch & RM=UNT02339 IN SAND,Reach-1         ,5052
     346     443     517     442     597     808     794
Boundary for River Rch & Prof#=UNT02339 IN SAND,Reach-1         , 1
Up Type= 0
Dn Type= 3
Dn Slope=0.005
Boundary for River Rch & Prof#=UNT02339 IN SAND,Reach-1         , 2
Up Type= 0
Dn Type= 3
Dn Slope=0.005
Boundary for River Rch & Prof#=UNT02339 IN SAND,Reach-1         , 3
Up Type= 0
Dn Type= 3
Dn Slope=0.005
Boundary for River Rch & Prof#=UNT02339 IN SAND,Reach-1         , 4
Up Type= 0
Dn Type= 3
Dn Slope=0.005
Boundary for River Rch & Prof#=UNT02339 IN SAND,Reach-1         , 5
Up Type= 0
Dn Type= 3
Dn Slope=0.005
Boundary for River Rch & Prof#=UNT02339 IN SAND,Reach-1         , 6
Up Type= 0
Dn Type= 3
Dn Slope=0.005
Boundary for River Rch & Prof#=UNT02339 IN SAND,Reach-1         , 7
Up Type= 0
Dn Type= 3
Dn Slope=0.005
DSS Import GetInterval= 0
DSS Import GetPeak= 0
DSS Import FillOption= 0

--- UNT02339 IN SAND CR.g01 (geometry) ---

Geom Title=Existing Conditions
Program Version=4.10

River Reach=UNT02339 IN SAND,Reach-1
Reach XY= 30
      3571887.74     10439315.28      3571839.13     10439148.44
      3571790.69      10439109.9      3571641.73     10439090.63
      3571216.52     10439109.71      3571176.16      10439039.4
      3571068.08     10438691.74      3570997.79     10438597.24
      3570936.57     10438575.86      3570841.52     10438596.69
      3570815.48     10438578.46      3570721.73     10438611.01
      3570696.99      10438604.5      3570666.58     10438572.36
      3570587.93      10438365.8      3570411.66     10438410.49
       3570248.9     10438371.43      3570062.44     10437851.38
      3569868.68     10437873.58      3569747.15      10437850.8
      3569729.79      10437833.8      3569600.02     10437427.39
      3569566.04     10437387.31      3569448.31     10437347.08
       3569193.1     10437201.24      3568957.69     10437114.78
      3568892.06      10437075.2      3568842.58     10437071.03
      3568554.04     10437156.45       3567470.9     10437501.75

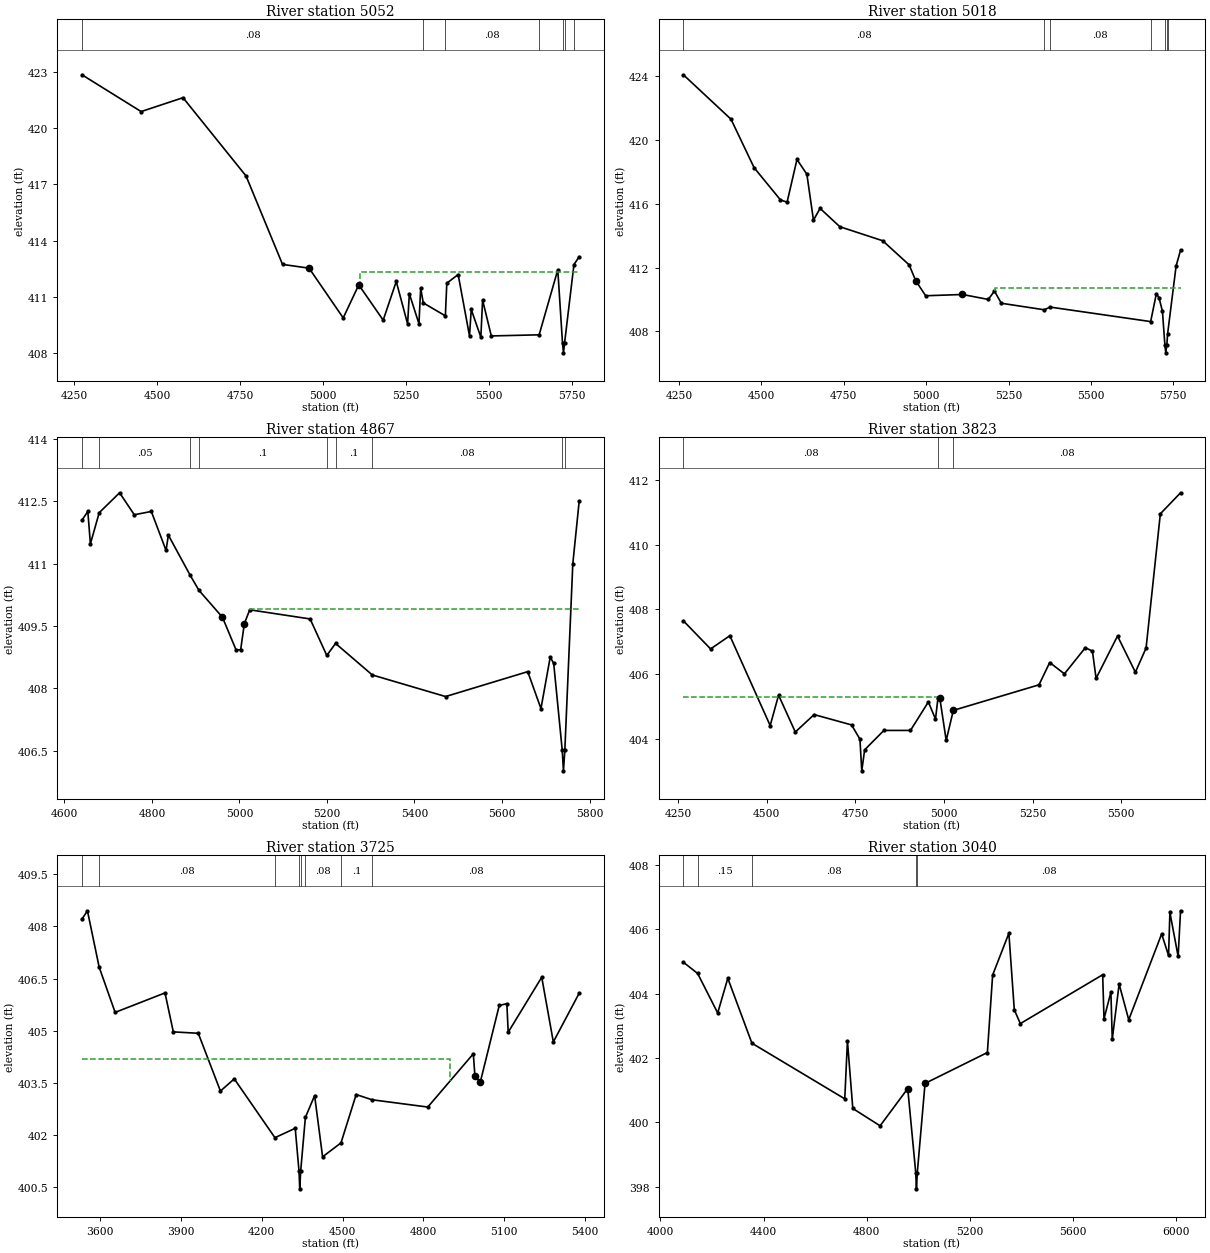
Type RM Length L Ch R = 1 ,5052    ,34,34,34
BEGIN DESCRIPTION:
UNT02339 IN SAND CR 7.6
END DESCRIPTION:
XS GIS Cut Line= 4
      3571906.69     10439047.95      3571198.36     10439042.74
      3570516.07     10439232.84      3570436.38     10439252.51
#Sta/Elev= 30
  4273.5  422.83  4451.9  420.87  4578.1  421.61  4768.1  417.44  4878.1  412.73
  4958.1  412.53    5061  409.88  5107.9  411.64  5181.5  409.76  5220.9  411.82
  5255.1  409.56  5260.3  411.17  5289.3  409.57  5294.5  411.47  5302.3  410.68
  5368.9  409.99  5373.3  411.73  5407.5  412.19  5441.7  408.92  5446.9  410.33
  5475.9  408.85  5481.1  410.83  5507.4  408.92  5651.6  408.98  5707.8  412.44
  5722.1  408.52  5724.9  408.02  5728.1  408.52  5756.5  412.72  5772.2  413.14
#Mann= 7 ,-1 , 0
  4273.5     .08       0  5302.3      .1       0  5368.9     .08       0
  5651.6      .1       0  5722.1     .07       0  5728.1      .1       0
  5756.5     .08       0
#XS Ineff= 2 , 0
                         5113.03          412.32
Permanent Ineff=
       F       F
Bank Sta=4958.1,5107.9
XS Rating Curve= 0 ,0
Exp/Cntr=0.3,0.1

Type RM Length L Ch R = 1 ,5018    ,151,151,151
BEGIN DESCRIPTION:
UNT02339 IN SAND CR 7.5
END DESCRIPTION:
XS GIS Cut Line= 4
      3571906.65      10439021.9      3571195.75     10439008.88
      3570521.27     10439201.59      3570429.11     10439226.65
#Sta/Elev= 30
  4263.8   424.1  4408.4  421.31  4478.4  418.27  4558.4  416.25  4578.4  416.11
  4608.4  418.79  4638.4  417.86  4658.4  414.98  4678.4  415.72  4738.4  414.57
  4868.4  413.69  4948.5  412.18  4968.5  411.19  4998.6  410.24  5110.4  410.32
  5188.4  410.01  5207.4  410.53  5228.2  409.77  5358.5  409.36  5376.1  409.53
  5681.1  408.62  5698.4  410.37  5706.5  410.12  5716.9  409.26  5724.2  407.16
    5727  406.66  5730.2  407.16  5732.4  407.83  5758.3  412.11  5771.8   413.1
#Mann= 7 ,-1 , 0
  4263.8     .08       0  5358.5      .1       0  5376.1     .08       0
  5681.1      .1       0  5724.2     .07       0  5730.2      .1       0
  5732.4     .08       0
#XS Ineff= 2 , 0
                         5207.65          410.71
Permanent Ineff=
       F       F
Bank Sta=4968.5,5110.4
XS Rating Curve= 0 ,0
Exp/Cntr=0.3,0.1

Type RM Length L Ch R = 1 ,4867    ,1044,1044,1044
BEGIN DESCRIPTION:
UNT02339 IN SAND CR 7.0
END DESCRIPTION:
XS GIS Cut Line= 3
      3571470.66     10438773.14      3570657.84     10439007.08
      3570413.07     10439163.31
#Sta/Elev= 30
  4640.1  412.05  4653.5  412.26  4659.4  411.48  4679.5  412.23  4726.1  412.71
  4759.7  412.18  4798.6  412.26  4832.3  411.32  4837.5  411.69  4887.5  410.72
  4907.4  410.36  4961.2  409.71  4992.4  408.92  5002.8  408.93  5011.2  409.56
  5023.6  409.89  5161.5  409.67  5199.6  408.79  5219.6  409.08  5303.6  408.32
  5471.1   407.8  5658.8   408.4    5689  407.51  5710.2  408.75  5718.1   408.6
  5737.6  406.51  5740.4  406.01  5743.6  406.51  5761.8     411  5776.3   412.5
#Mann= 9 ,-1 , 0
  4640.1     .08       0  4679.5     .05       0  4887.5     .08       0
  4907.4      .1       0  5199.6     .08       0  5219.6      .1       0
  5303.6     .08       0  5737.6     .07       0  5743.6     .08       0
#XS Ineff= 2 , 0
                         5023.66           409.9
Permanent Ineff=
       F       F
Bank Sta=4961.2,5011.2
XS Rating Curve= 0 ,0
Exp/Cntr=0.3,0.1

Type RM Length L Ch R = 1 ,3823    ,98,98,98
BEGIN DESCRIPTION:
UNT02339 IN SAND CR 5.1
END DESCRIPTION:
XS GIS Cut Line= 3
      3570702.44     10437720.89      3570457.65       10438299.
      3570369.29     10439068.24
#Sta/Elev= 30
  4265.4  407.65  4342.2  406.78  4396.5  407.19  4510.2  404.41  4533.9  405.35
  4581.1  404.21  4634.1  404.75  4739.7  404.43  4763.3  403.99  4768.5  403.01
  4776.6  403.66  4830.9  404.26  4905.9  404.26  4956.3  405.14  4976.4  404.61
  4983.5  405.27  4988.6  405.26  5006.6  403.95  5026.7  404.88  5268.3  405.67
  5298.5  406.36    5340  406.01  5399.1  406.82    5419  406.71  5429.3  405.87
  5489.7  407.18  5540.1  406.06  5570.3  406.81  5610.5  410.96  5667.5  411.61
#Mann= 3 ,-1 , 0
  4265.4     .08       0  4983.5     .07       0  5026.7     .08       0
#XS Ineff= 2 , 0
         4983.52  405.29
Permanent Ineff=
       F       F
Bank Sta=4988.6,5026.7
XS Rating Curve= 0 ,0
Exp/Cntr=0.3,0.1

Type RM Length L Ch R = 1 ,3725    ,685,685,685
BEGIN DESCRIPTION:
UNT02339 IN SAND CR 4.1
END DESCRIPTION:
XS GIS Cut Line= 3
      3570020.16     10436971.94      3570343.07     10438333.03
      3570377.76     10438777.11
#Sta/Elev= 30
  3533.2  408.21  3553.5  408.45    3597  406.83  3656.2  405.53  3841.2  406.09
  3872.1  404.97  3964.6  404.93  4046.8  403.27  4098.2  403.62    4249  401.93
  4324.3   402.2  4338.4  400.96  4341.1  400.46  4344.4  400.96  4361.9  402.51
  4396.2  403.14  4425.8  401.38    4494  401.78  4550.4  403.17  4608.9  403.02
    4816  402.81  4984.9  404.34  4990.9   403.7  5010.9  403.53  5081.1  405.73
  5109.3  405.78  5114.3  404.96  5238.7  406.54  5281.7  404.68  5377.5  406.08
#Mann= 8 ,-1 , 0
  3533.2      .1       0    3597     .08       0    4249      .1       0
  4338.4     .07       0  4344.4      .1       0  4361.9     .08       0
    4494      .1       0  4608.9     .08       0
#XS Ineff= 2 , 0
         4900.21  404.19
Permanent Ineff=
       F       F
Bank Sta=4990.9,5010.9
XS Rating Curve= 0 ,0
Exp/Cntr=0.3,0.1

Type RM Length L Ch R = 1 ,3040    ,101,101,101
BEGIN DESCRIPTION:
UNT02339 IN SAND CR 4.0
END DESCRIPTION:
XS GIS Cut Line= 3
      3569790.98     10436968.44      3570054.87     10437905.95
        3570350.     10438815.63
#Sta/Elev= 30
  4088.8  404.98  4144.2  404.63  4222.1   403.4  4261.3  404.48    4355  402.46
  4715.4  400.73  4725.8  402.53  4746.6  400.43  4852.6  399.89  4959.9  401.05
    4991  398.43  4993.7  397.93    4997  398.43  5027.1  401.21  5269.1  402.17
  5289.5  404.58  5352.6  405.88  5373.6   403.5    5397  403.07  5716.7  404.59
  5721.9  403.22  5748.7  404.05  5753.9  402.58  5780.6   404.3  5817.9  403.19
  5945.7  405.86  5972.5  405.19  5977.7  406.53  6009.7  405.16  6019.1  406.58
#Mann= 5 ,-1 , 0
  4088.8      .1       0  4144.2     .15       0    4355     .08       0
    4991     .07       0    4997     .08       0
Bank Sta=4959.9,5027.1
XS Rating Curve= 0 ,0
Exp/Cntr=0.3,0.1

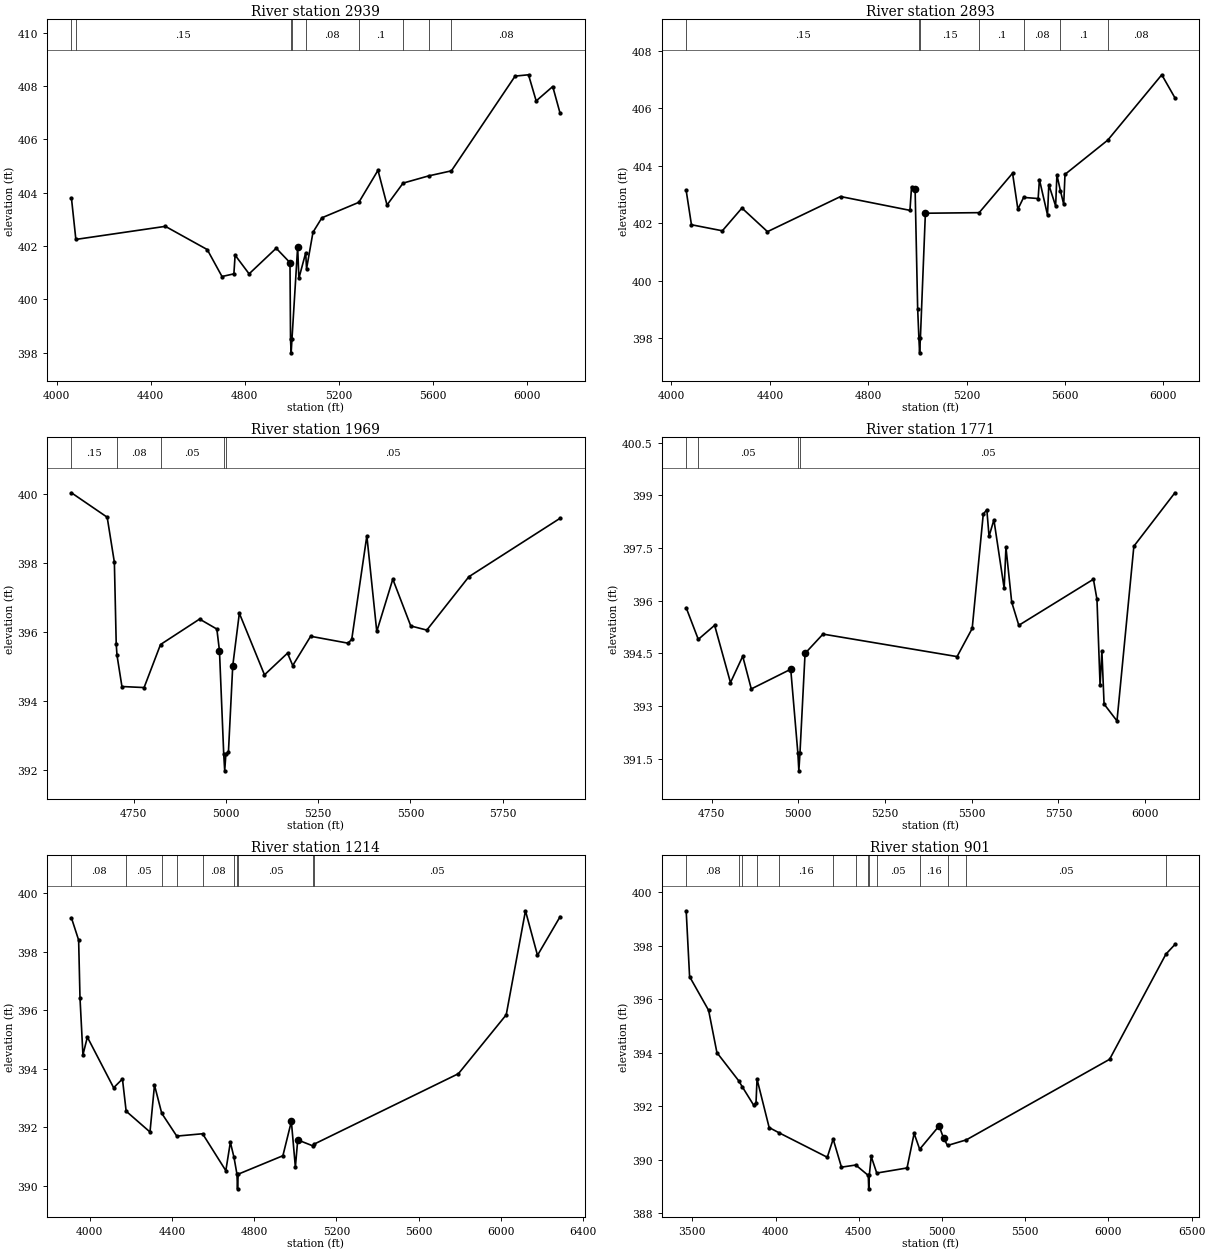
Type RM Length L Ch R = 1 ,2939    ,46,46,46
BEGIN DESCRIPTION:
UNT02339 IN SAND CR 3.1
END DESCRIPTION:
XS GIS Cut Line= 2
      3569661.44     10436970.18       3570277.1     10438954.57
#Sta/Elev= 30
    4063  403.81  4081.9  402.25  4462.4  402.74  4640.4  401.87  4703.2  400.86
  4753.7  400.96  4758.9  401.66  4818.4  400.96  4933.6  401.92  4992.2  401.38
  4994.5   398.5  4997.2     398  5000.5   398.5  5024.8  401.97    5030  400.79
    5059  401.75  5062.6  401.15    5090  402.52  5127.8  403.06  5284.9  403.64
  5366.3  404.84  5404.7  403.54    5473  404.36  5581.3  404.63  5678.4  404.82
  5949.2  408.37  6006.2  408.42  6038.8  407.44  6109.2  407.98  6140.7  406.97
#Mann= 9 ,-1 , 0
    4063      .1       0  4081.9     .15       0  4994.5     .07       0
  5000.5     .15       0    5059     .08       0  5284.9      .1       0
    5473     .08       0  5581.3      .1       0  5678.4     .08       0
Bank Sta=4992.2,5024.8
XS Rating Curve= 0 ,0
Exp/Cntr=0.3,0.1

Type RM Length L Ch R = 1 ,2893    ,924,924,924
BEGIN DESCRIPTION:
UNT02339 IN SAND CR 3.0
END DESCRIPTION:
XS GIS Cut Line= 3
      3569641.69     10436971.79      3569630.04     10437000.53
      3570197.16     10438872.71
#Sta/Elev= 30
  4059.9  403.14  4081.3  401.95    4207  401.74  4286.6  402.53  4390.5  401.71
  4687.6  402.93  4969.8  402.45  4976.3  403.27  4990.7   403.2  5001.1  399.04
  5006.2     398    5009   397.5  5012.2     398  5032.5  402.35  5251.2  402.37
    5387  403.74  5408.6  402.49    5432   402.9    5491  402.86  5496.2  403.52
  5529.1  402.29  5534.4  403.34  5562.1   402.6  5567.3  403.68  5581.6  403.13
    5595  402.66  5600.2   403.7  5774.1  404.89  5993.7  407.16  6047.1  406.36
#Mann= 7 ,-1 , 0
  4059.9     .15       0  5006.2     .07       0  5012.2     .15       0
  5251.2      .1       0    5432     .08       0  5581.6      .1       0
  5774.1     .08       0
Bank Sta=4990.7,5032.5
XS Rating Curve= 0 ,0
Exp/Cntr=0.3,0.1

Type RM Length L Ch R = 1 ,1969    ,198,198,198
BEGIN DESCRIPTION:
UNT02339 IN SAND CR 2.1
END DESCRIPTION:
XS GIS Cut Line= 4
      3569383.67     10436864.81      3569367.75     10437157.88
      3569275.11     10437390.16      3569444.71     10438153.37
#Sta/Elev= 30
  4580.7  400.05  4677.7  399.34  4697.2  398.03  4702.2  395.66  4704.3  395.33
  4717.7  394.42  4777.8  394.39  4822.3  395.64  4928.3  396.38  4975.1  396.09
  4982.2  395.46  4993.7  392.47  4996.4  391.97  4999.7  392.47  5006.5  392.51
  5018.2  395.02  5036.1  396.55  5104.3  394.76  5166.8  395.39  5180.9  395.03
  5229.5  395.88  5330.7  395.68  5340.9  395.79  5381.9   398.8  5408.8  396.02
  5452.3  397.54    5501  396.18  5544.5  396.06  5658.5  397.61  5906.1  399.31
#Mann= 5 ,-1 , 0
  4580.7     .15       0  4704.3     .08       0  4822.3     .05       0
  4993.7     .04       0  4999.7     .05       0
Bank Sta=4982.2,5018.2
XS Rating Curve= 0 ,0
Exp/Cntr=0.3,0.1

Type RM Length L Ch R = 1 ,1771    ,557,557,557
BEGIN DESCRIPTION:
UNT02339 IN SAND CR 2.0
END DESCRIPTION:
XS GIS Cut Line= 4
      3569228.47     10436869.98      3569098.92     10437367.39
      3569270.97     10438141.66      3569350.57     10438205.02
#Sta/Elev= 30
  4676.8   395.8  4711.7   394.9  4758.8   395.3  4804.5  393.67  4839.8  394.42
  4864.5  393.49  4978.2  394.05  4998.8  391.66  5001.6  391.16  5004.8  391.66
  5019.5   394.5  5071.2  395.05  5457.7  394.41  5501.3  395.21  5533.2  398.46
  5543.5  398.59  5549.9  397.83  5563.9   398.3  5593.5  396.35  5598.6  397.52
  5615.2  395.96  5635.7   395.3  5850.8  396.61    5861  396.04    5870  393.59
  5875.2  394.57  5881.5  393.06  5918.7  392.58  5967.4  397.55  6085.7  399.07
#Mann= 4 ,-1 , 0
  4676.8     .08       0  4711.7     .05       0  4998.8     .03       0
  5004.8     .05       0
Bank Sta=4978.2,5019.5
XS Rating Curve= 0 ,0
Exp/Cntr=0.3,0.1

Type RM Length L Ch R = 1 ,1214    ,313,313,313
BEGIN DESCRIPTION:
UNT02339 IN SAND CR 1.0
END DESCRIPTION:
XS GIS Cut Line= 4
      3569202.42     10436282.82      3568590.13     10436996.66
      3568668.25     10437309.16      3569235.73     10438267.11
#Sta/Elev= 30
  3911.4  399.15  3946.5  398.39  3953.1  396.42  3967.4  394.47  3988.9  395.08
  4116.7  393.35  4159.5  393.65  4177.5  392.55  4293.4  391.84  4315.3  393.44
  4350.4  392.48  4423.5   391.7  4549.1  391.78  4662.1  390.52  4684.1  391.49
  4701.9  390.97  4716.2   390.4  4718.9   389.9  4722.2   390.4  4939.5  391.03
  4980.7   392.2  5000.2  390.64  5011.6  391.57  5083.9  391.37  5089.7  391.42
  5792.9  393.83  6025.3  395.84  6118.8  399.39  6177.3  397.87  6287.4  399.19
#Mann= 10 ,-1 , 0
  3911.4     .08       0  4177.5     .05       0  4350.4     .16       0
  4423.5     .05       0  4549.1     .08       0  4701.9     .05       0
  4716.2     .03       0  4722.2     .05       0  5083.9      .1       0
  5089.7     .05       0
Bank Sta=4980.7,5011.6
XS Rating Curve= 0 ,0
Exp/Cntr=0.3,0.1

Type RM Length L Ch R = 1 ,901     ,268,268,268
BEGIN DESCRIPTION:
UNT02339 IN SAND CR 1.09
END DESCRIPTION:
XS GIS Cut Line= 4
      3569069.69     10435960.48      3568284.94      10436988.3
        3568403.     10437689.68      3568937.41     10438453.13
#Sta/Elev= 30
  3463.1  399.31  3483.6  396.85  3597.9  395.59  3647.8  394.01  3778.4  392.96
  3800.5  392.73  3868.2  392.05  3882.7  392.13  3888.8  393.02  3961.6  391.21
  4019.3  391.02  4310.8   390.1  4346.2  390.78    4396  389.73    4482  389.81
  4557.2  389.42  4559.9  388.92  4563.2  389.42  4574.7  390.13  4608.1  389.51
  4790.1   389.7  4832.6  390.99    4866   390.4  4982.7  391.27  5009.2  390.82
  5033.2  390.54  5146.3  390.75    6007  393.76  6345.4  397.69  6399.4  398.05
#Mann= 14 ,-1 , 0
  3463.1     .08       0  3778.4     .05       0  3800.5     .16       0
  3888.8     .05       0  4019.3     .16       0  4346.2     .05       0
    4482     .08       0  4557.2     .07       0  4563.2     .08       0
  4608.1     .05       0    4866     .16       0  5033.2      .1       0
  5146.3     .05       0  6345.4     .08       0
Bank Sta=4982.7,5009.2
XS Rating Curve= 0 ,0
Exp/Cntr=0.3,0.1

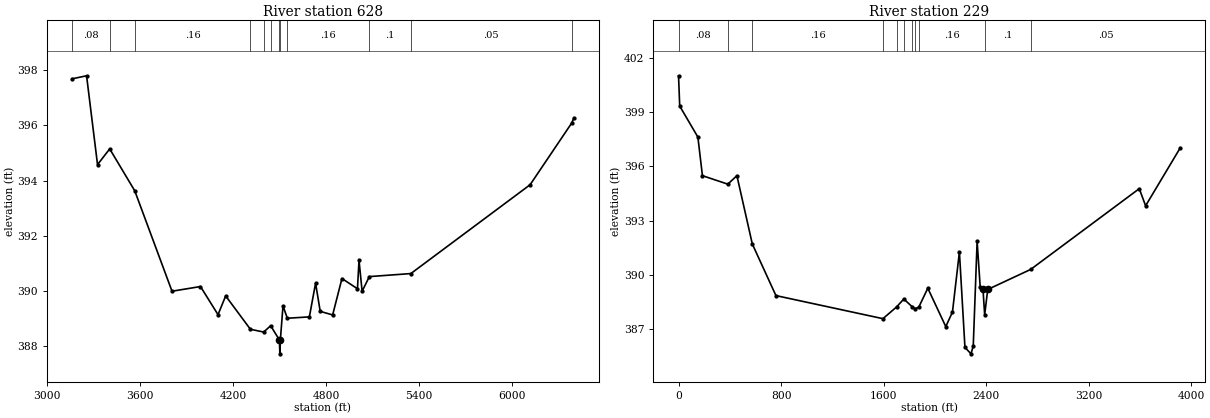
Type RM Length L Ch R = 1 ,628     ,401,401,401
BEGIN DESCRIPTION:
UNT02339 IN SAND CR 1.1
END DESCRIPTION:
XS GIS Cut Line= 4
      3569007.83     10435834.76      3568096.37     10436789.62
      3568052.97     10437527.47      3568625.89     10438560.46
#Sta/Elev= 30
  3160.2  397.69  3253.9   397.8  3324.6  394.58  3403.2  395.15    3565  393.63
  3805.6  389.99  3989.5  390.16  4102.7  389.14  4152.1  389.82  4311.9  388.61
  4397.7  388.51  4442.7  388.74  4499.3  388.22    4502  387.72  4505.3  388.22
  4522.3  389.46  4550.2  389.01  4692.6  389.06  4732.7  390.28  4762.7  389.26
  4842.9  389.13    4903  390.45  5003.2  390.08  5013.2  391.11  5033.2  389.99
  5080.1  390.52    5348  390.63  6118.1  393.85  6387.1  396.09  6400.6  396.27
#Mann= 12 ,-1 , 0
  3160.2     .08       0  3403.2     .05       0    3565     .16       0
  4311.9      .1       0  4397.7     .05       0  4442.7     .08       0
  4499.3     .07       0  4505.3     .08       0  4550.2     .16       0
  5080.1      .1       0    5348     .05       0  6387.1     .08       0
Bank Sta=4499.3,4505.3
XS Rating Curve= 0 ,0
Exp/Cntr=0.3,0.1

Type RM Length L Ch R = 1 ,229     ,0,0,0
XS GIS Cut Line= 6
      3568968.58     10435664.78      3567597.05     10436940.82
      3567582.29     10437175.19      3567707.29     10437480.75
      3568207.29     10437970.33      3568578.39     10438653.27
#Sta/Elev= 30
       0  401.03     9.2  399.35   150.9  397.63   186.4  395.49   384.4  395.02
   455.3  395.49   575.5   391.7   759.7  388.84  1594.2  387.56  1700.7  388.21
  1757.2  388.65  1820.9  388.23  1841.9  388.11  1873.3  388.19  1944.3  389.25
  2084.6  387.12  2136.7  387.93  2190.8  391.26    2234  385.97    2281  385.61
  2298.8  386.04    2329  391.85  2352.8  389.34  2374.4  389.23  2387.8  387.78
  2411.8  389.18  2746.4  390.29  3593.8  394.77  3643.2  393.82    3914  397.04
#Mann= 11 ,-1 , 0
       0     .08       0   384.4     .05       0   575.5     .16       0
  1594.2      .1       0  1700.7     .05       0  1757.2     .08       0
  1820.9     .07       0  1841.9     .08       0  1873.3     .16       0
  2387.8      .1       0  2746.4     .05       0
Bank Sta=2374.4,2411.8
XS Rating Curve= 0 ,0
Exp/Cntr=0.3,0.1

Chan Stop Cuts=-1
Use User Specified Reach Order=0
Composite Channel Slope=5