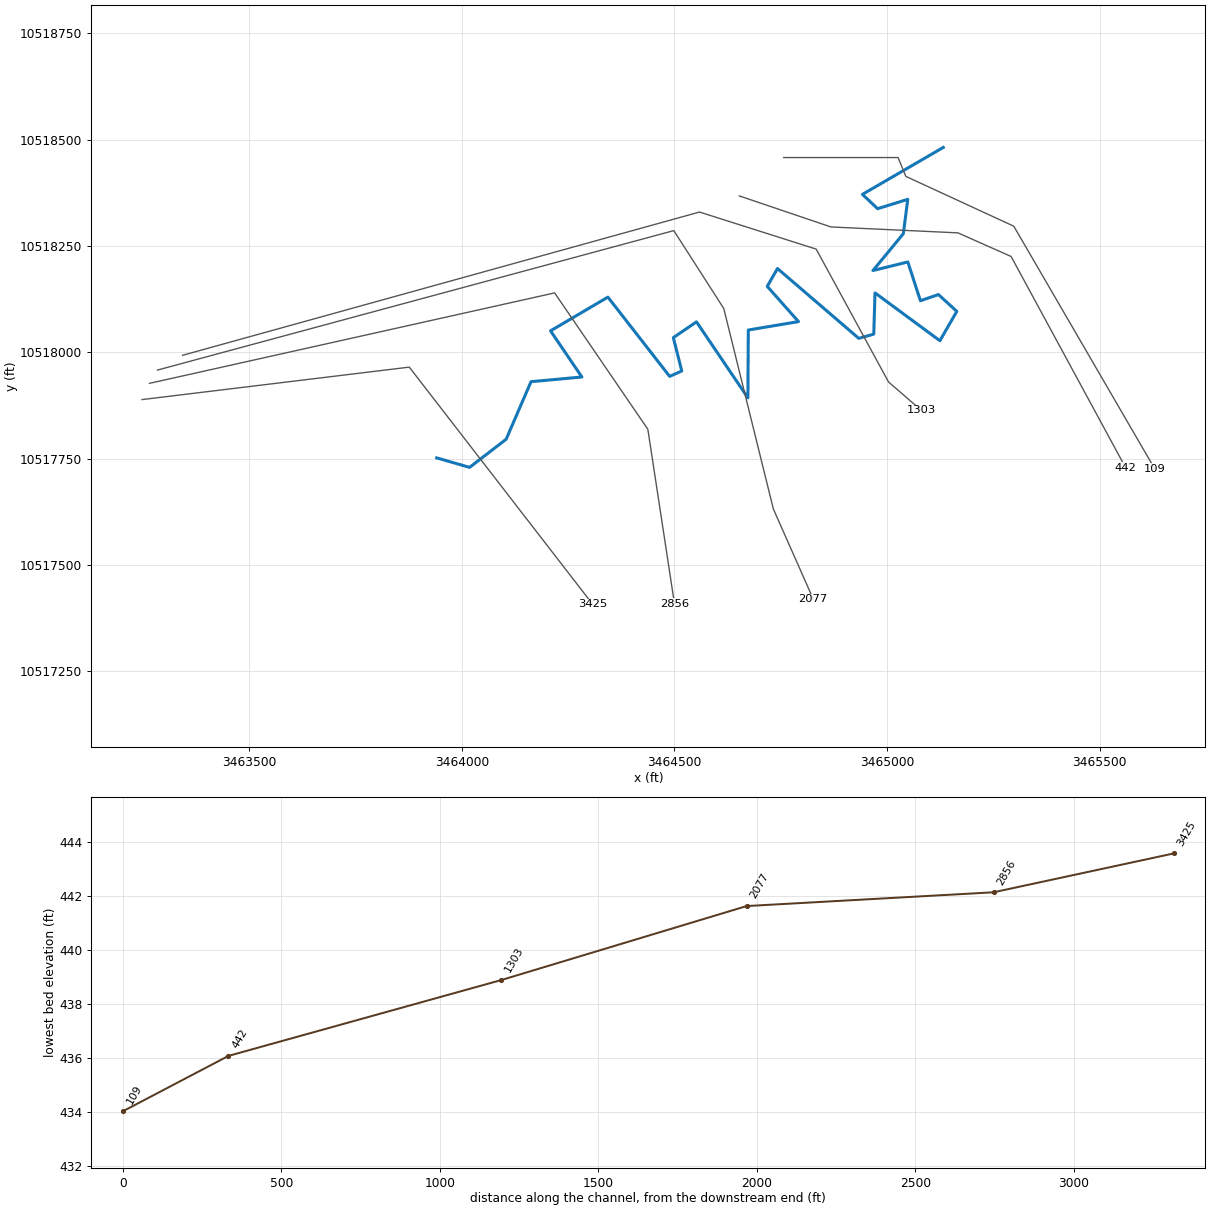
--- UNT0494 IN SAND CR.prj (project) ---

Proj Title=UNT0494 IN SAND CR Base Level Engineering
Current Plan=p01
Default Exp/Contr=0.3,0.1
English Units
Geom File=g01
Flow File=f01
Plan File=p01
BEGIN DESCRIPTION:
UNT0494 IN SAND CR
END DESCRIPTION:

--- UNT0494 IN SAND CR.p01 (plan) ---

Plan Title=Multiple Run
Short Identifier=Multiple
Geom File=g01
Flow File=f01
Subcritical Flow
K Sum by GR= 0
Std Step Tol= 0.01
Critical Tol= 0.01
Num of Std Step Trials= 20
Max Error Tol= 0.3
Flow Tol Ratio= 0.001
Split Flow NTrial= 30
Split Flow Tol= 0.02
Split Flow Ratio= 0.02
Log Output Level= 0
Friction Slope Method= 1
Unsteady Friction Slope Method= 2
Unsteady Bridges Friction Slope Method= 1
Parabolic Critical Depth
Global Vel Dist=  1 , 1 , 1
Global Log Level= 0
CheckData=True
Encroach Param= -1, 0, 0, 0
BEGIN DESCRIPTION:
Multiple Run
END DESCRIPTION:

--- UNT0494 IN SAND CR.f01 (steady flow) ---

Flow Title=Multiple
Number of Profiles=7
Profile Names=10-year,25-year,50-year,1pct_min,100-year,1pct_plu,500-year
River Rch & RM= UNT0494 IN SAND ,Reach-1,3425
     866    1177    1432    1270    1718    2324    2467
Boundary for River Rch & Prof#=UNT0494 IN SAND ,Reach-1,1
Up Type=0
Dn Type=3
Dn Slope=0.005
Boundary for River Rch & Prof#=UNT0494 IN SAND ,Reach-1,2
Up Type=0
Dn Type=3
Dn Slope=0.005
Boundary for River Rch & Prof#=UNT0494 IN SAND ,Reach-1,3
Up Type=0
Dn Type=3
Dn Slope=0.005
Boundary for River Rch & Prof#=UNT0494 IN SAND ,Reach-1,4
Up Type=0
Dn Type=3
Dn Slope=0.005
Boundary for River Rch & Prof#=UNT0494 IN SAND ,Reach-1,5
Up Type=0
Dn Type=3
Dn Slope=0.005
Boundary for River Rch & Prof#=UNT0494 IN SAND ,Reach-1,6
Up Type=0
Dn Type=3
Dn Slope=0.005
Boundary for River Rch & Prof#=UNT0494 IN SAND ,Reach-1,7
Up Type=0
Dn Type=3
Dn Slope=0.005

--- UNT0494 IN SAND CR.g01 (geometry) ---

Geom Title=Existing Conditions

River Reach=UNT0494 IN SAND ,Reach-1
Reach XY= 30
      3463940.98     10517751.60      3464018.21     10517729.32
      3464104.13     10517795.35      3464162.72     10517930.78
      3464282.32     10517941.85      3464208.57     10518050.37
      3464343.48     10518129.63      3464488.66     10517943.25
      3464517.08     10517956.03      3464497.33     10518034.40
      3464551.76     10518071.50      3464672.66     10517892.76
      3464673.57     10518052.28      3464791.64     10518072.09
      3464718.11     10518154.97      3464742.24     10518196.84
      3464933.29     10518032.72      3464968.62     10518042.60
      3464971.49     10518139.64      3465124.07     10518027.12
      3465163.84     10518096.11      3465120.64     10518135.67
      3465078.29     10518121.15      3465048.73     10518212.29
      3464966.69     10518192.19      3465038.11     10518278.69
      3465048.56     10518359.57      3464977.72     10518337.58
      3464941.91     10518371.24      3465132.11     10518481.64

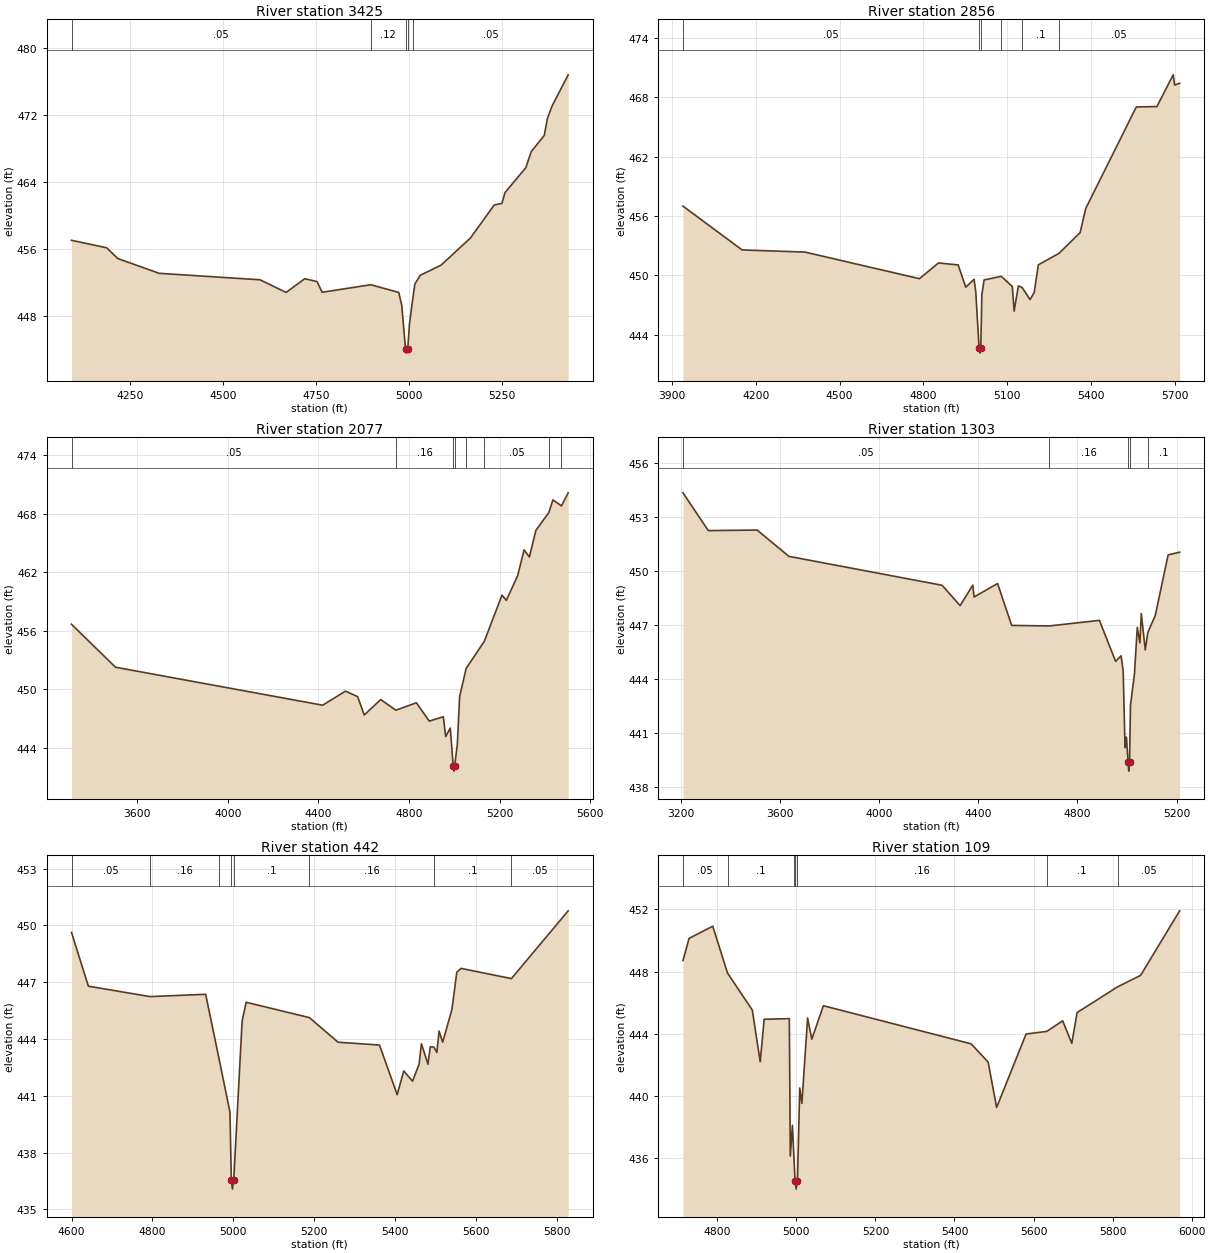
Type RM Length L Ch R = 1,3425,569,569,569
BEGIN DESCRIPTION:
ROCKY CREEK 33.1
END DESCRIPTION:
XS GIS Cut Line= 3
      3463248.08     10517888.72      3463876.44     10517965.03
      3464307.65     10517407.38
#Sta/Elev= 30
  4091.4  457.03  4186.1  456.14  4216.3  454.85  4327.6  453.09  4599.1  452.32
  4669.6  450.81  4719.7  452.45  4752.9  452.10  4766.6  450.83  4897.6  451.73
  4972.9  450.81  4981.1  449.26  4991.1  444.07  4993.9  443.57  4997.1  444.07
  5001.9  447.10  5010.9  450.10  5016.4  451.82  5030.9  452.86  5087.0  454.07
  5165.8  457.29  5230.1  461.24  5250.9  461.44  5259.1  462.72  5315.2  465.69
  5329.7  467.60  5365.0  469.55  5373.2  471.54  5386.0  473.06  5429.3  476.77
#Mann=5,-1,0
  4091.4    0.05       0  4897.6    0.12       0  4991.1    0.07       0
  4997.1    0.12       0  5010.9    0.05       0
Bank Sta=4991.1,4997.1
Exp/Cntr=0.3,0.1

Type RM Length L Ch R = 1,2856,779,779,779
BEGIN DESCRIPTION:
ROCKY CREEK 39.4
END DESCRIPTION:
XS GIS Cut Line= 4
      3463265.48     10517926.92      3464218.19     10518139.56
      3464437.39     10517818.94      3464499.89     10517409.22
#Sta/Elev= 30
  3939.3  457.00  4151.0  452.57  4376.4  452.35  4786.3  449.66  4854.5  451.25
  4925.0  451.05  4952.2  448.80  4982.0  449.60  4988.0  448.36  5000.0  442.63
  5002.7  442.13  5006.0  442.63  5009.8  448.03  5017.9  449.53  5079.4  449.90
  5118.9  448.87  5125.5  446.38  5140.5  448.93  5154.3  448.76  5182.4  447.55
  5197.3  448.26  5212.2  451.06  5286.0  452.22  5361.8  454.32  5382.0  456.77
  5563.1  467.03  5636.8  467.07  5695.2  470.28  5700.3  469.25  5718.3  469.42
#Mann=6,-1,0
  3939.3    0.05       0  5000.0    0.04       0  5006.0    0.05       0
  5079.4    0.12       0  5154.3     0.1       0  5286.0    0.05       0
Bank Sta=5000,5006
Exp/Cntr=0.3,0.1

Type RM Length L Ch R = 1,2077,774,774,774
BEGIN DESCRIPTION:
ROCKY CREEK 39.3
END DESCRIPTION:
XS GIS Cut Line= 5
      3463284.52     10517958.16      3464498.45     10518286.04
      3464615.92     10518102.87      3464732.53     10517631.44
      3464826.28     10517419.64
#Sta/Elev= 30
  3310.5  456.66  3504.8  452.26  4419.2  448.37  4519.9  449.81  4573.5  449.25
  4602.7  447.37  4675.4  448.95  4742.3  447.86  4832.6  448.62  4889.8  446.74
  4951.6  447.19  4962.1  445.16  4982.5  446.03  4995.4  442.12  4998.1  441.62
  5001.4  442.12  5013.4  444.33  5023.7  449.25  5052.5  452.14  5132.6  454.91
  5210.6  459.64  5229.8  459.11  5279.5  461.61  5308.2  464.28  5331.5  463.55
  5360.3  466.28  5417.2  468.09  5435.6  469.40  5473.1  468.78  5502.8  470.12
#Mann=8,-1,0
  3310.5    0.05       0  4742.3    0.16       0  4995.4    0.07       0
  5001.4    0.16       0  5052.5     0.1       0  5132.6    0.05       0
  5417.2     0.1       0  5473.1    0.05       0
Bank Sta=4995.4,5001.4
Exp/Cntr=0.3,0.1

Type RM Length L Ch R = 1,1303,861,861,861
BEGIN DESCRIPTION:
ROCKY CREEK 39.1
END DESCRIPTION:
XS GIS Cut Line= 5
      3463343.52     10517992.87      3464558.83     10518329.69
      3464833.22     10518242.55      3465003.36     10517930.05
      3465079.78     10517864.05
#Sta/Elev= 30
  3206.8  454.35  3309.1  452.25  3506.3  452.28  3634.4  450.82  4253.4  449.21
  4326.0  448.08  4377.2  449.22  4382.4  448.56  4477.3  449.31  4534.3  446.98
  4686.1  446.95  4888.6  447.26  4954.1  444.98  4976.0  445.29  4984.6  444.44
  4992.1  440.18  4997.8  440.77  5004.3  439.38  5007.1  438.88  5010.3  439.38
  5014.0  442.54  5030.1  444.28  5041.5  446.87  5052.0  446.01  5057.7  447.64
  5073.8  445.62  5084.1  446.59  5114.1  447.53  5166.1  450.90  5212.6  451.05
#Mann=5,-1,0
  3206.8    0.05       0  4686.1    0.16       0  5004.3    0.07       0
  5010.3    0.16       0  5084.1     0.1       0
Bank Sta=5004.3,5010.3
Exp/Cntr=0.3,0.1

Type RM Length L Ch R = 1,442,333,333,333
BEGIN DESCRIPTION:
ROCKY CREEK 38.1
END DESCRIPTION:
XS GIS Cut Line= 5
      3464652.66     10518367.55      3464867.94     10518294.63
      3465166.55     10518280.75      3465291.55     10518225.19
      3465560.59     10517728.95
#Sta/Elev= 30
  4599.9  449.63  4641.6  446.79  4793.8  446.24  4931.5  446.36  4964.0  443.01
  4991.5  440.14  4994.9  436.57  4997.6  436.07  5000.9  436.57  5021.6  444.95
  5031.6  445.94  5187.8  445.13  5258.7  443.83  5361.1  443.68  5404.8  441.06
  5421.0  442.31  5442.8  441.77  5459.0  442.67  5464.7  443.75  5480.9  442.67
  5486.6  443.59  5495.5  443.57  5502.8  443.29  5508.4  444.42  5517.2  443.83
  5540.0  445.55  5552.2  447.53  5562.7  447.73  5687.1  447.19  5827.4  450.77
#Mann=8,-1,0
  4599.9    0.05       0  4793.8    0.16       0  4964.0     0.1       0
  4994.9    0.07       0  5000.9     0.1       0  5187.8    0.16       0
  5495.5     0.1       0  5687.1    0.05       0
Bank Sta=4994.9,5000.9
Exp/Cntr=0.3,0.1

Type RM Length L Ch R = 1,109,0,0,0
BEGIN DESCRIPTION:
ROCKY CREEK 38.11
END DESCRIPTION:
XS GIS Cut Line= 5
      3464756.71     10518457.82      3465025.77     10518457.82
      3465044.00     10518413.55      3465297.91     10518296.36
      3465629.37     10517725.74
#Sta/Elev= 30
  4713.2  448.71  4728.6  450.14  4788.6  450.92  4825.9  447.91  4888.6  445.53
  4908.6  442.21  4918.6  444.94  4982.3  444.98  4984.7  436.15  4990.1  438.12
  4994.7  435.65  4996.8  434.52  4999.5  434.02  5002.8  434.52  5008.6  440.52
  5014.0  439.53  5028.5  445.02  5039.1  443.66  5068.5  445.81  5442.1  443.36
  5485.2  442.19  5506.7  439.27  5581.2  443.99  5633.5  444.16  5673.8  444.84
  5696.9  443.39  5710.3  445.37  5812.5  447.02  5870.9  447.76  5969.7  451.91
#Mann=7,-1,0
  4713.2    0.05       0  4825.9     0.1       0  4994.7    0.16       0
  4996.8    0.07       0  5002.8    0.16       0  5633.5     0.1       0
  5812.5    0.05       0
Bank Sta=4996.8,5002.8
Exp/Cntr=0.3,0.1

Chan Stop Cuts=-1