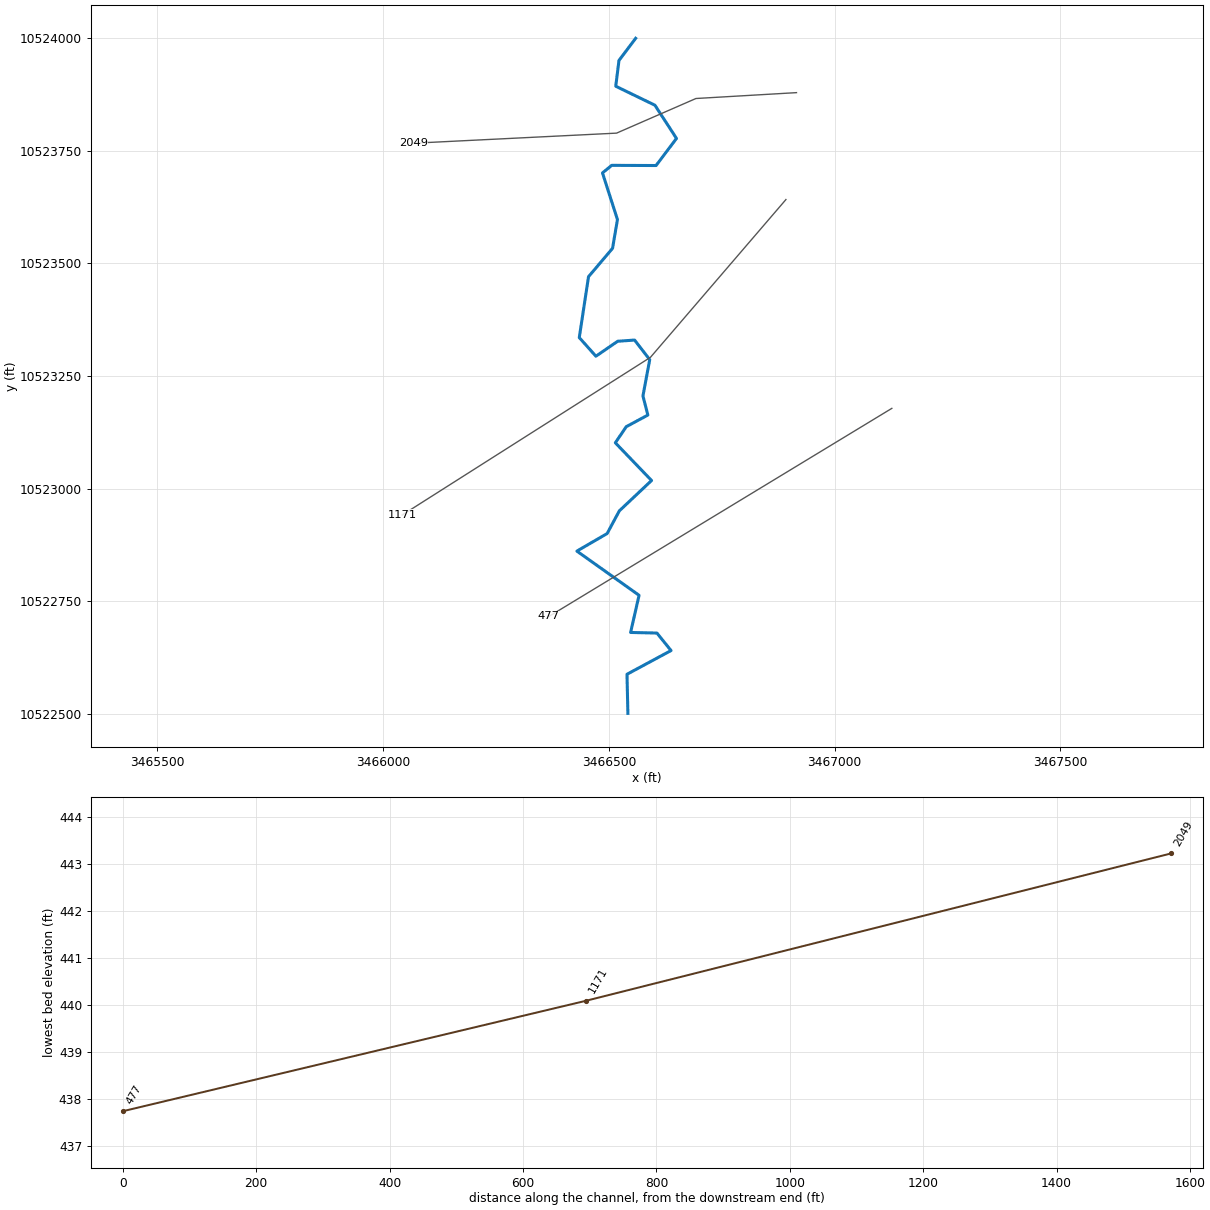
--- UNT0501 IN SAND CR.prj (project) ---

Proj Title=UNT0501 IN SAND CR Base Level Engineering
Current Plan=p01
Default Exp/Contr=0.3,0.1
English Units
Geom File=g01
Flow File=f01
Plan File=p01
BEGIN DESCRIPTION:
UNT0501 IN SAND CR
END DESCRIPTION:

--- UNT0501 IN SAND CR.p01 (plan) ---

Plan Title=Multiple Run
Short Identifier=Multiple
Geom File=g01
Flow File=f01
Subcritical Flow
K Sum by GR= 0
Std Step Tol= 0.01
Critical Tol= 0.01
Num of Std Step Trials= 20
Max Error Tol= 0.3
Flow Tol Ratio= 0.001
Split Flow NTrial= 30
Split Flow Tol= 0.02
Split Flow Ratio= 0.02
Log Output Level= 0
Friction Slope Method= 1
Unsteady Friction Slope Method= 2
Unsteady Bridges Friction Slope Method= 1
Parabolic Critical Depth
Global Vel Dist=  1 , 1 , 1
Global Log Level= 0
CheckData=True
Encroach Param= -1, 0, 0, 0
BEGIN DESCRIPTION:
Multiple Run
END DESCRIPTION:

--- UNT0501 IN SAND CR.f01 (steady flow) ---

Flow Title=Multiple
Number of Profiles=7
Profile Names=10-year,25-year,50-year,1pct_min,100-year,1pct_plu,500-year
River Rch & RM= UNT0501 IN SAND ,Reach-1,2049
     663     884    1060     930    1257    1700    1759
Boundary for River Rch & Prof#=UNT0501 IN SAND ,Reach-1,1
Up Type=0
Dn Type=3
Dn Slope=0.005
Boundary for River Rch & Prof#=UNT0501 IN SAND ,Reach-1,2
Up Type=0
Dn Type=3
Dn Slope=0.005
Boundary for River Rch & Prof#=UNT0501 IN SAND ,Reach-1,3
Up Type=0
Dn Type=3
Dn Slope=0.005
Boundary for River Rch & Prof#=UNT0501 IN SAND ,Reach-1,4
Up Type=0
Dn Type=3
Dn Slope=0.005
Boundary for River Rch & Prof#=UNT0501 IN SAND ,Reach-1,5
Up Type=0
Dn Type=3
Dn Slope=0.005
Boundary for River Rch & Prof#=UNT0501 IN SAND ,Reach-1,6
Up Type=0
Dn Type=3
Dn Slope=0.005
Boundary for River Rch & Prof#=UNT0501 IN SAND ,Reach-1,7
Up Type=0
Dn Type=3
Dn Slope=0.005

--- UNT0501 IN SAND CR.g01 (geometry) ---

Geom Title=Existing Conditions

River Reach=UNT0501 IN SAND ,Reach-1
Reach XY= 30
      3466559.30     10523999.35      3466522.37     10523950.37
      3466515.25     10523893.09      3466602.05     10523850.90
      3466649.74     10523777.31      3466604.53     10523717.14
      3466506.40     10523717.54      3466485.82     10523700.75
      3466519.00     10523597.31      3466508.12     10523533.41
      3466454.94     10523470.56      3466434.43     10523335.43
      3466471.26     10523294.07      3466519.59     10523327.30
      3466556.96     10523329.87      3466590.46     10523286.42
      3466575.44     10523205.90      3466586.36     10523163.51
      3466538.52     10523137.71      3466514.29     10523101.95
      3466594.53     10523018.32      3466523.18     10522951.00
      3466496.14     10522900.61      3466429.15     10522861.65
      3466566.87     10522763.64      3466548.12     10522681.17
      3466606.46     10522679.81      3466637.67     10522641.02
      3466540.12     10522588.41      3466542.11     10522501.64

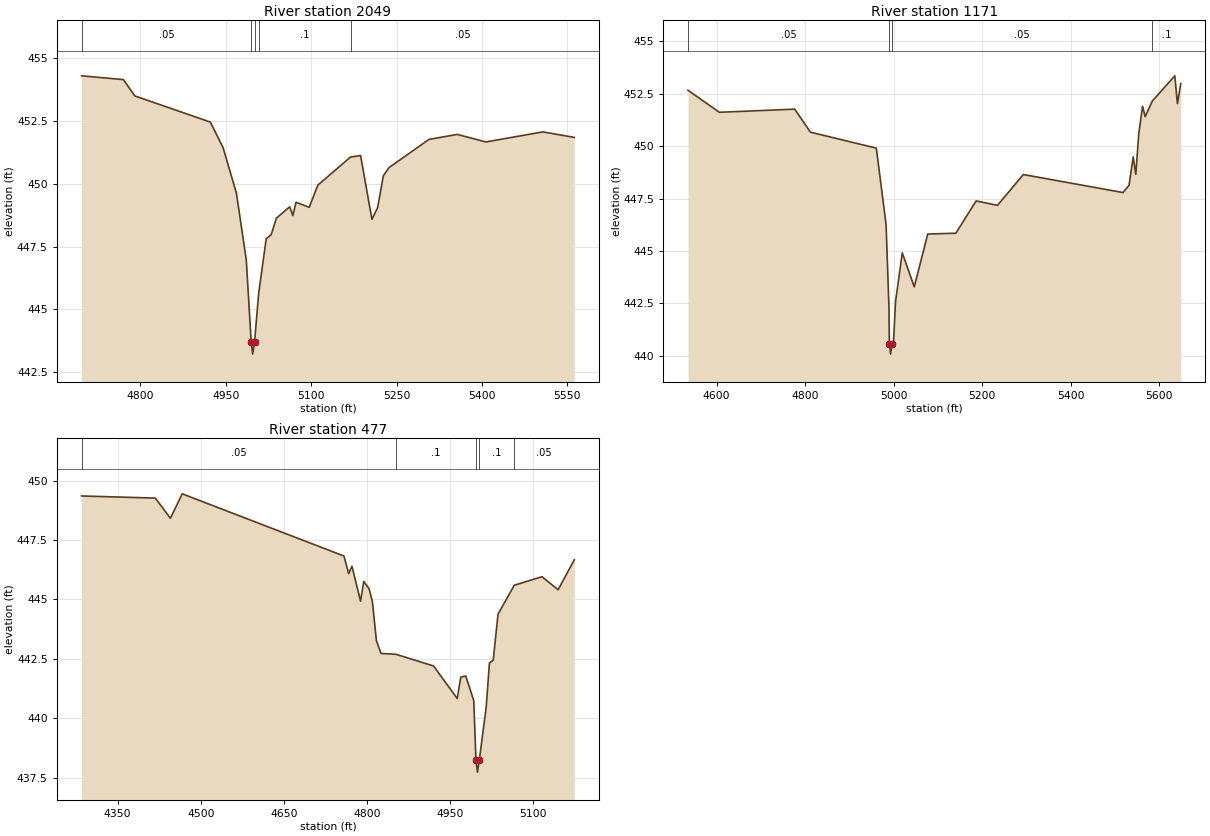
Type RM Length L Ch R = 1,2049,878,878,878
BEGIN DESCRIPTION:
UNT0501 IN SAND CR 1.0
END DESCRIPTION:
XS GIS Cut Line= 4
      3466915.53     10523878.87      3466692.82     10523865.85
      3466517.04     10523789.03      3466067.12     10523766.64
#Sta/Elev= 30
  4696.8  454.29  4770.3  454.14  4790.4  453.49  4923.0  452.45  4945.4  451.43
  4968.8  449.62  4986.1  446.97  4994.7  443.72  4997.4  443.22  5000.7  443.72
  5007.8  445.62  5021.1  447.81  5029.8  447.97  5039.0  448.63  5062.4  449.08
  5067.9  448.73  5073.5  449.26  5096.7  449.06  5111.7  449.94  5169.2  451.06
  5186.8  451.12  5206.8  448.58  5216.8  449.05  5226.8  450.31  5236.8  450.64
  5306.9  451.76  5356.5  451.96  5407.0  451.66  5507.1  452.06  5562.2  451.84
#Mann=5,-1,0
  4696.8    0.05       0  4994.7   0.035       0  5000.7    0.05       0
  5007.8     0.1       0  5169.2    0.05       0
Bank Sta=4994.7,5000.7
Exp/Cntr=0.3,0.1

Type RM Length L Ch R = 1,1171,694,694,694
BEGIN DESCRIPTION:
UNT0501 IN SAND CR 2.0
END DESCRIPTION:
XS GIS Cut Line= 3
      3466892.13     10523641.67      3466592.11     10523291.64
      3466042.13     10522941.66
#Sta/Elev= 30
  4535.3  452.67  4606.1  451.62  4776.2  451.77  4811.9  450.67  4960.6  449.91
  4982.6  446.27  4989.2  442.29  4990.0  440.58  4992.8  440.08  4996.0  440.58
  4999.3  440.58  5003.9  442.57  5019.2  444.91  5046.3  443.29  5076.7  445.81
  5140.2  445.85  5186.0  447.39  5234.2  447.18  5292.6  448.65  5517.8  447.79
  5531.4  448.14  5540.7  449.49  5546.6  448.66  5553.4  450.61  5561.9  451.91
  5567.8  451.41  5584.0  452.16  5634.7  453.36  5640.6  452.03  5648.2  452.99
#Mann=4,-1,0
  4535.3    0.05       0  4990.0   0.035       0  4996.0    0.05       0
  5584.0     0.1       0
Bank Sta=4990,4996
Exp/Cntr=0.3,0.1

Type RM Length L Ch R = 1,477,0,0,0
BEGIN DESCRIPTION:
UNT0501 IN SAND CR 3.0
END DESCRIPTION:
XS GIS Cut Line= 2
      3467126.66     10523178.36      3466367.09     10522716.63
#Sta/Elev= 30
  4285.0  449.36  4418.1  449.27  4445.3  448.42  4466.6  449.45  4758.4  446.83
  4766.9  446.09  4772.8  446.40  4788.3  444.93  4794.1  445.76  4803.7  445.45
  4809.6  444.92  4816.9  443.27  4825.1  442.73  4852.6  442.69  4920.0  442.20
  4962.7  440.83  4969.1  441.73  4978.1  441.78  4992.5  440.74  4996.5  438.23
  4999.2  437.73  5002.5  438.23  5015.0  440.48  5020.8  442.33  5027.6  442.44
  5036.3  444.38  5065.6  445.60  5115.7  445.96  5144.6  445.41  5173.9  446.67
#Mann=5,-1,0
  4285.0    0.05       0  4852.6     0.1       0  4996.5    0.07       0
  5002.5     0.1       0  5065.6    0.05       0
Bank Sta=4996.5,5002.5
Exp/Cntr=0.3,0.1

Chan Stop Cuts=-1