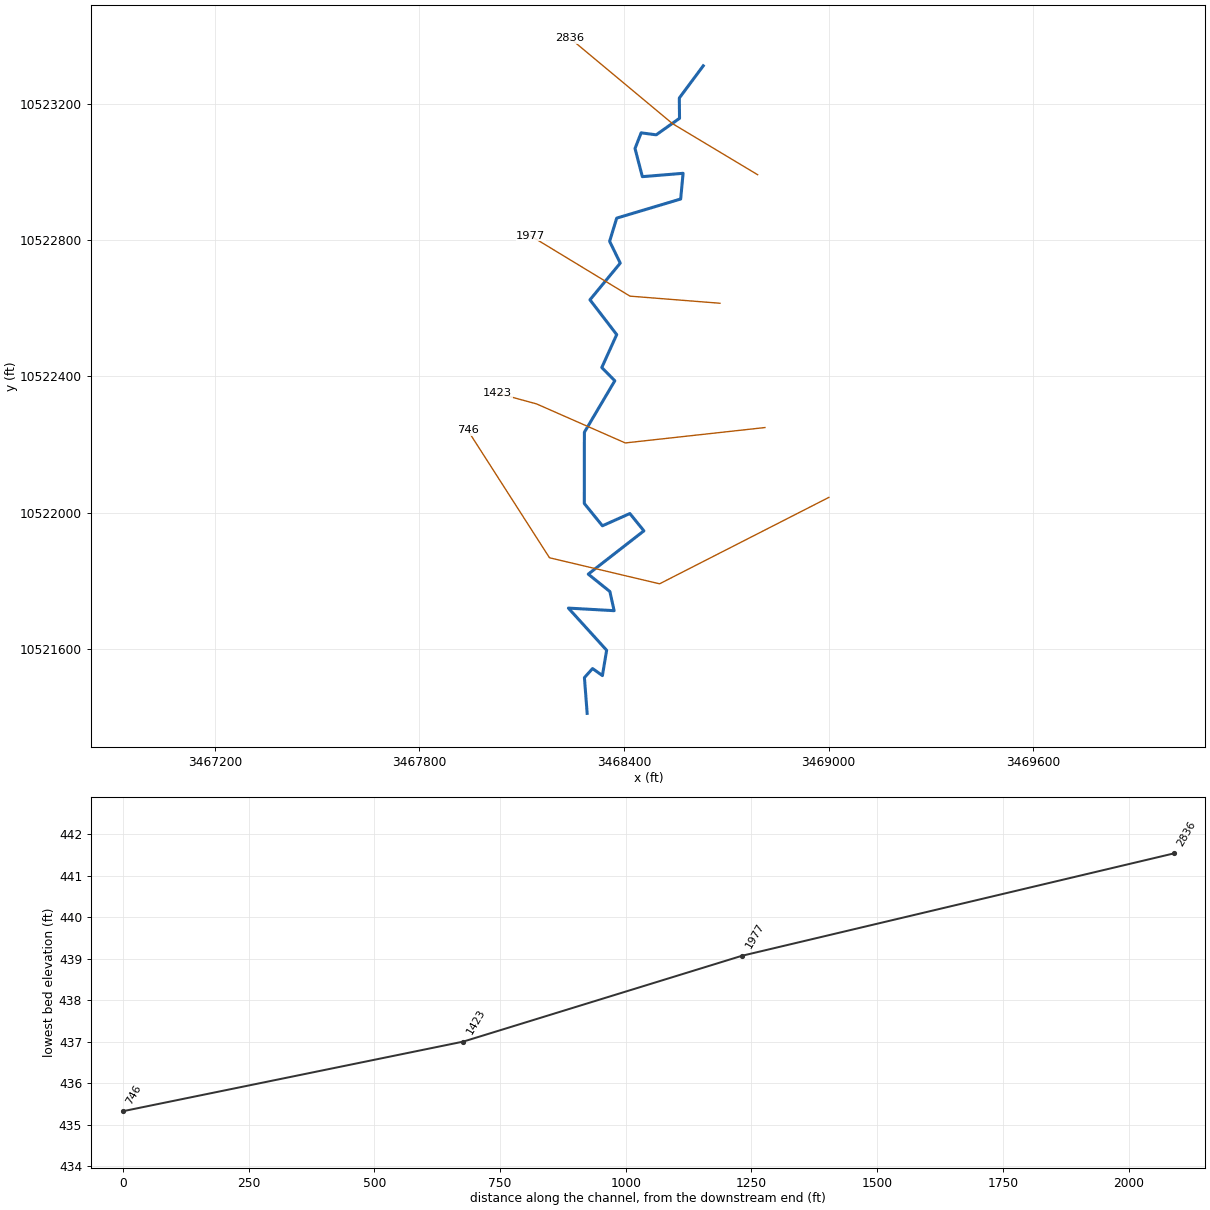
--- UNT0502 IN SAND CR.prj (project) ---

Proj Title=UNT0502 IN SAND CR Base Level Engineering
Current Plan=p01
Default Exp/Contr=0.3,0.1
English Units
Geom File=g01
Flow File=f01
Plan File=p01
BEGIN DESCRIPTION:
UNT0502 IN SAND CR
END DESCRIPTION:

--- UNT0502 IN SAND CR.p01 (plan) ---

Plan Title=Multiple Run
Short Identifier=Multiple
Geom File=g01
Flow File=f01
Subcritical Flow
K Sum by GR= 0
Std Step Tol= 0.01
Critical Tol= 0.01
Num of Std Step Trials= 20
Max Error Tol= 0.3
Flow Tol Ratio= 0.001
Split Flow NTrial= 30
Split Flow Tol= 0.02
Split Flow Ratio= 0.02
Log Output Level= 0
Friction Slope Method= 1
Unsteady Friction Slope Method= 2
Unsteady Bridges Friction Slope Method= 1
Parabolic Critical Depth
Global Vel Dist=  1 , 1 , 1
Global Log Level= 0
CheckData=True
Encroach Param= -1, 0, 0, 0
BEGIN DESCRIPTION:
Multiple Run
END DESCRIPTION:

--- UNT0502 IN SAND CR.f01 (steady flow) ---

Flow Title=Multiple
Number of Profiles=7
Profile Names=10-year,25-year,50-year,1pct_min,100-year,1pct_plu,500-year
River Rch & RM= UNT0502 IN SAND ,Reach-1,2836
     665     886    1063     931    1259    1703    1760
Boundary for River Rch & Prof#=UNT0502 IN SAND ,Reach-1,1
Up Type=0
Dn Type=3
Dn Slope=0.005
Boundary for River Rch & Prof#=UNT0502 IN SAND ,Reach-1,2
Up Type=0
Dn Type=3
Dn Slope=0.005
Boundary for River Rch & Prof#=UNT0502 IN SAND ,Reach-1,3
Up Type=0
Dn Type=3
Dn Slope=0.005
Boundary for River Rch & Prof#=UNT0502 IN SAND ,Reach-1,4
Up Type=0
Dn Type=3
Dn Slope=0.005
Boundary for River Rch & Prof#=UNT0502 IN SAND ,Reach-1,5
Up Type=0
Dn Type=3
Dn Slope=0.005
Boundary for River Rch & Prof#=UNT0502 IN SAND ,Reach-1,6
Up Type=0
Dn Type=3
Dn Slope=0.005
Boundary for River Rch & Prof#=UNT0502 IN SAND ,Reach-1,7
Up Type=0
Dn Type=3
Dn Slope=0.005

--- UNT0502 IN SAND CR.g01 (geometry) ---

Geom Title=Existing Conditions

River Reach=UNT0502 IN SAND ,Reach-1
Reach XY= 30
      3468632.59     10523310.96      3468562.40     10523216.61
      3468563.02     10523156.98      3468494.60     10523108.60
      3468450.44     10523114.42      3468432.49     10523068.41
      3468454.00     10522985.89      3468573.47     10522995.70
      3468566.37     10522920.34      3468378.78     10522864.27
      3468357.94     10522796.22      3468389.19     10522732.33
      3468300.30     10522624.69      3468378.78     10522522.61
      3468335.03     10522426.08      3468373.22     10522387.19
      3468283.95     10522236.09      3468283.72     10522027.20
      3468336.81     10521961.84      3468417.38     10521997.78
      3468458.47     10521946.99      3468295.36     10521820.04
      3468358.68     10521769.02      3468371.18     10521712.87
      3468237.09     10521720.40      3468349.21     10521596.73
      3468336.80     10521522.44      3468307.94     10521543.11
      3468284.06     10521516.59      3468292.11     10521411.64

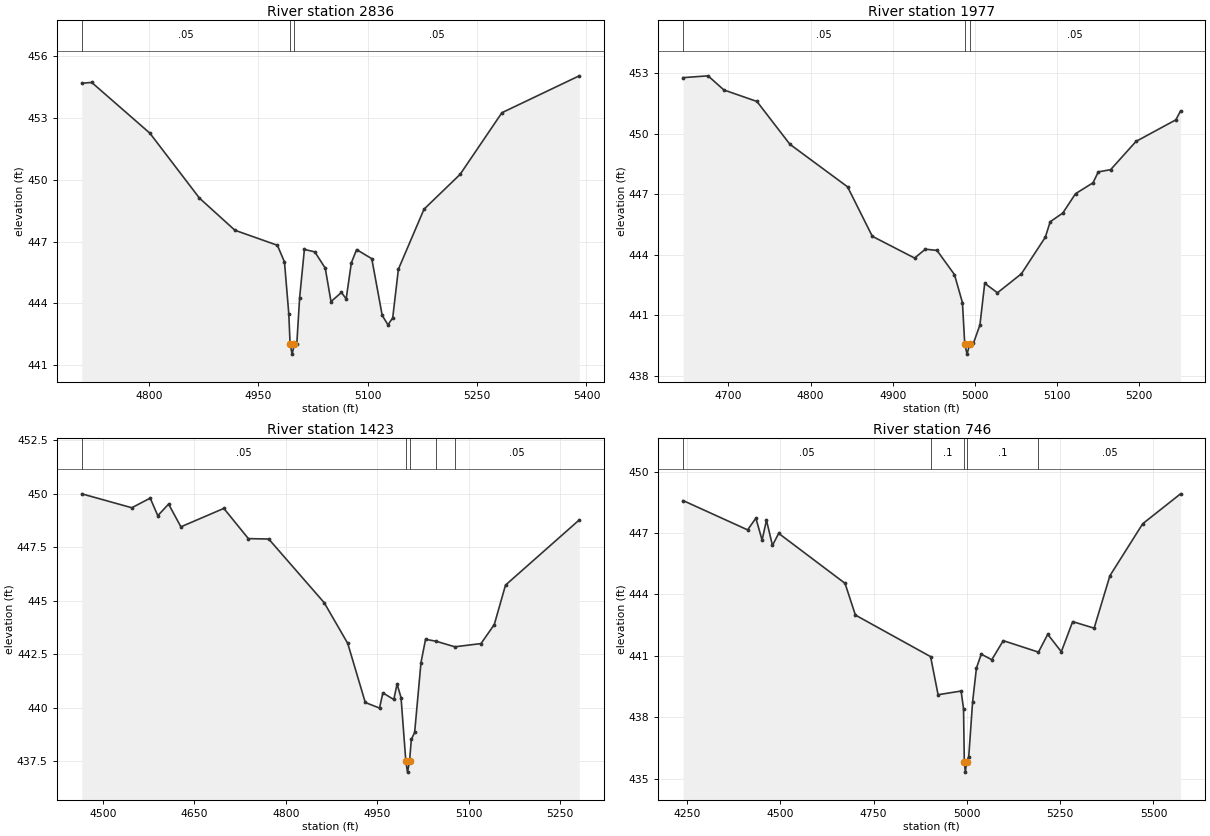
Type RM Length L Ch R = 1,2836,859,859,859
BEGIN DESCRIPTION:
UNT0502 IN SAND CR 4.0
END DESCRIPTION:
XS GIS Cut Line= 3
      3468792.09     10522991.65      3468542.11     10523141.64
      3468242.14     10523391.61
#Sta/Elev= 30
  4708.0  454.68  4721.6  454.72  4801.3  452.26  4869.3  449.11  4917.9  447.55
  4976.2  446.82  4985.9  446.01  4991.8  443.51  4993.6  442.04  4996.4  441.54
  4999.6  442.04  5002.8  442.04  5006.7  444.28  5013.2  446.62  5027.5  446.50
  5041.8  445.71  5049.7  444.09  5064.0  444.53  5070.5  444.22  5077.6  445.97
  5084.8  446.61  5105.6  446.17  5119.9  443.42  5127.8  442.96  5134.3  443.30
  5142.1  445.66  5177.2  448.57  5226.7  450.26  5284.0  453.25  5390.0  455.04
#Mann=3,-1,0
  4708.0    0.05       0  4993.6   0.035       0  4999.6    0.05       0
Bank Sta=4993.6,4999.6
Exp/Cntr=0.3,0.1

Type RM Length L Ch R = 1,1977,554,554,554
BEGIN DESCRIPTION:
UNT0502 IN SAND CR 3.0
END DESCRIPTION:
XS GIS Cut Line= 3
      3468681.59     10522614.59      3468417.73     10522635.42
      3468126.57     10522812.19
#Sta/Elev= 30
  4644.8  452.77  4675.1  452.86  4694.4  452.16  4734.6  451.59  4774.7  449.47
  4844.9  447.36  4875.0  444.91  4926.5  443.83  4939.5  444.27  4953.7  444.21
  4975.0  443.01  4984.7  441.62  4987.5  439.57  4990.3  439.07  4993.5  439.57
  4998.0  439.60  5006.0  440.52  5011.8  442.58  5027.3  442.11  5056.4  443.05
  5085.5  444.86  5091.5  445.63  5106.8  446.06  5122.3  447.02  5143.6  447.56
  5150.0  448.10  5165.0  448.21  5195.9  449.61  5244.4  450.68  5250.1  451.12
#Mann=3,-1,0
  4644.8    0.05       0  4987.5   0.035       0  4993.5    0.05       0
Bank Sta=4987.5,4993.5
Exp/Cntr=0.3,0.1

Type RM Length L Ch R = 1,1423,677,677,677
BEGIN DESCRIPTION:
UNT0502 IN SAND CR 2.0
END DESCRIPTION:
XS GIS Cut Line= 4
      3468813.59     10522250.01      3468403.84     10522204.86
      3468143.42     10522319.45      3468028.84     10522350.70
#Sta/Elev= 30
  4465.4  449.99  4547.4  449.34  4577.6  449.79  4590.0  448.97  4607.7  449.51
  4627.9  448.45  4698.3  449.31  4738.5  447.90  4771.9  447.88  4862.8  444.91
  4901.4  443.01  4930.2  440.25  4953.5  439.99  4959.0  440.70  4976.9  440.39
  4982.3  441.11  4988.8  440.48  4996.7  437.50  4999.4  437.00  5002.7  437.50
  5005.7  438.53  5011.1  438.85  5021.5  442.11  5029.0  443.20  5046.2  443.11
  5077.0  442.85  5119.9  443.00  5141.7  443.89  5160.1  445.73  5280.9  448.77
#Mann=5,-1,0
  4465.4    0.05       0  4996.7   0.035       0  5002.7    0.05       0
  5046.2     0.1       0  5077.0    0.05       0
Bank Sta=4996.7,5002.7
Exp/Cntr=0.3,0.1

Type RM Length L Ch R = 1,746,0,0,0
BEGIN DESCRIPTION:
UNT0502 IN SAND CR 1.0
END DESCRIPTION:
XS GIS Cut Line= 4
      3469001.08     10522045.15      3468504.53     10521791.67
      3468181.61     10521868.06      3467942.10     10522241.64
#Sta/Elev= 30
  4239.5  448.58  4412.3  447.15  4434.5  447.72  4451.1  446.65  4462.9  447.62
  4478.9  446.39  4495.6  446.98  4673.4  444.54  4701.2  442.99  4902.7  440.96
  4922.8  439.10  4984.5  439.28  4991.0  438.42  4993.1  435.82  4995.9  435.32
  4999.1  435.82  5005.0  436.08  5015.3  438.75  5025.6  440.40  5038.4  441.08
  5066.7  440.81  5097.5  441.74  5191.8  441.18  5216.7  442.05  5253.1  441.20
  5283.5  442.67  5341.0  442.35  5383.3  444.91  5471.2  447.45  5572.6  448.91
#Mann=5,-1,0
  4239.5    0.05       0  4902.7     0.1       0  4993.1    0.07       0
  4999.1     0.1       0  5191.8    0.05       0
Bank Sta=4993.1,4999.1
Exp/Cntr=0.3,0.1

Chan Stop Cuts=-1