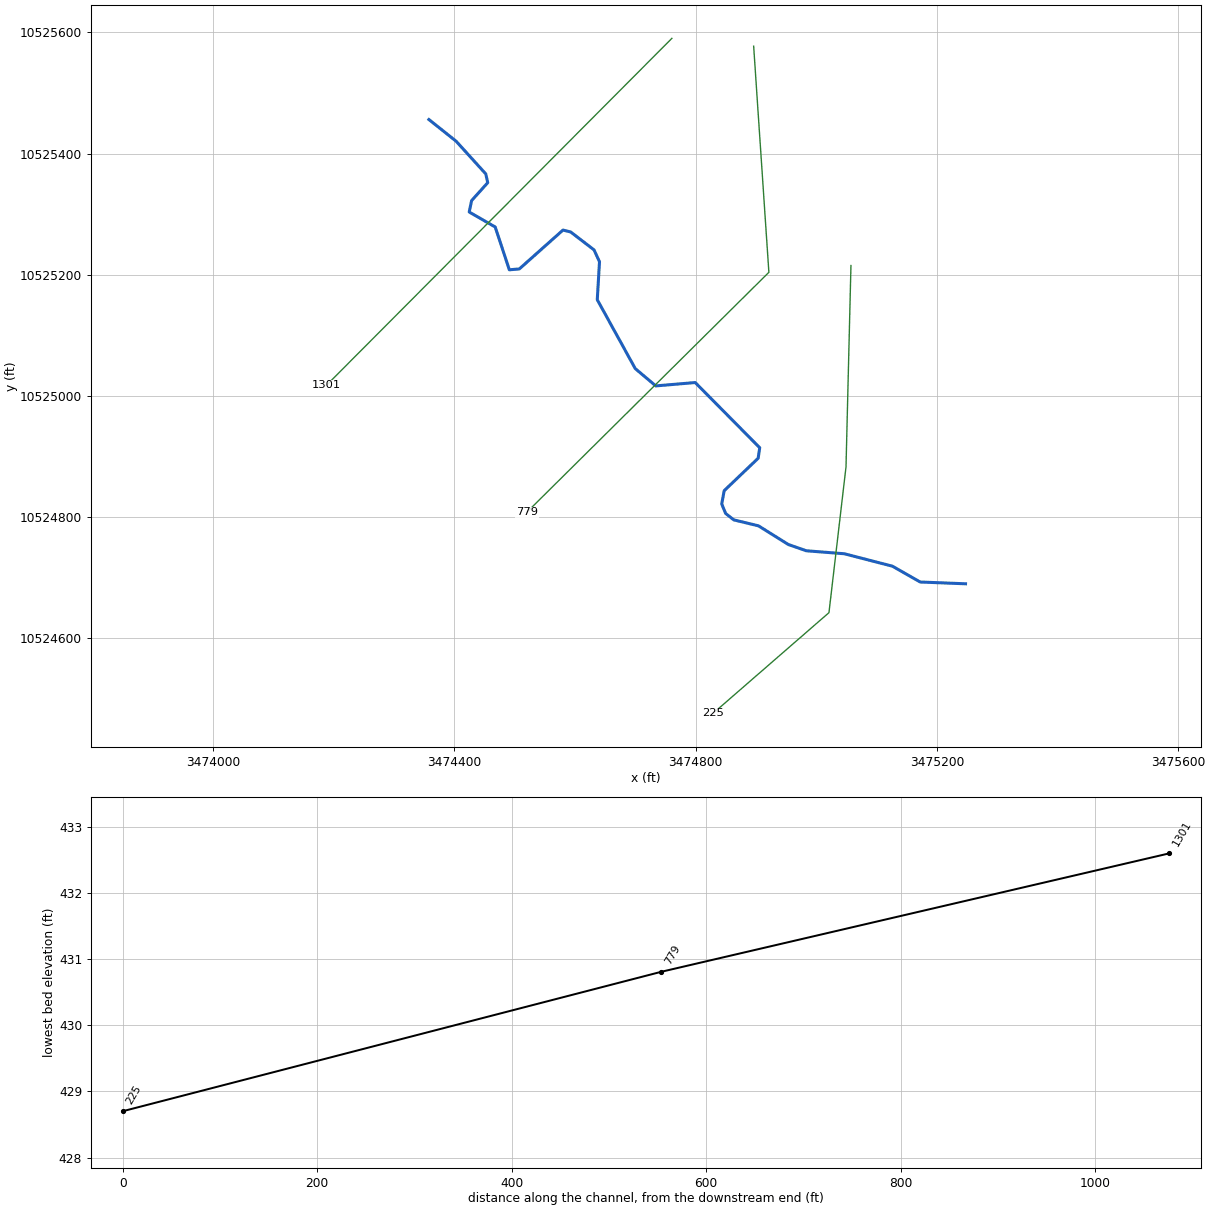
--- UNT0507 IN SAND CR.prj (project) ---

Proj Title=UNT0507 IN SAND CR Base Level Engineering
Current Plan=p01
Default Exp/Contr=0.3,0.1
English Units
Geom File=g01
Flow File=f01
Plan File=p01
BEGIN DESCRIPTION:
UNT0507 IN SAND CR
END DESCRIPTION:

--- UNT0507 IN SAND CR.p01 (plan) ---

Plan Title=Multiple Run
Short Identifier=Multiple
Geom File=g01
Flow File=f01
Subcritical Flow
K Sum by GR= 0
Std Step Tol= 0.01
Critical Tol= 0.01
Num of Std Step Trials= 20
Max Error Tol= 0.3
Flow Tol Ratio= 0.001
Split Flow NTrial= 30
Split Flow Tol= 0.02
Split Flow Ratio= 0.02
Log Output Level= 0
Friction Slope Method= 1
Unsteady Friction Slope Method= 2
Unsteady Bridges Friction Slope Method= 1
Parabolic Critical Depth
Global Vel Dist=  1 , 1 , 1
Global Log Level= 0
CheckData=True
Encroach Param= -1, 0, 0, 0
BEGIN DESCRIPTION:
Multiple Run
END DESCRIPTION:

--- UNT0507 IN SAND CR.f01 (steady flow) ---

Flow Title=Multiple
Number of Profiles=7
Profile Names=10-year,25-year,50-year,1pct_min,100-year,1pct_plu,500-year
River Rch & RM= UNT0507 IN SAND ,Reach-1,1301
     539     710     844     735     994    1344    1369
Boundary for River Rch & Prof#=UNT0507 IN SAND ,Reach-1,1
Up Type=0
Dn Type=3
Dn Slope=0.005
Boundary for River Rch & Prof#=UNT0507 IN SAND ,Reach-1,2
Up Type=0
Dn Type=3
Dn Slope=0.005
Boundary for River Rch & Prof#=UNT0507 IN SAND ,Reach-1,3
Up Type=0
Dn Type=3
Dn Slope=0.005
Boundary for River Rch & Prof#=UNT0507 IN SAND ,Reach-1,4
Up Type=0
Dn Type=3
Dn Slope=0.005
Boundary for River Rch & Prof#=UNT0507 IN SAND ,Reach-1,5
Up Type=0
Dn Type=3
Dn Slope=0.005
Boundary for River Rch & Prof#=UNT0507 IN SAND ,Reach-1,6
Up Type=0
Dn Type=3
Dn Slope=0.005
Boundary for River Rch & Prof#=UNT0507 IN SAND ,Reach-1,7
Up Type=0
Dn Type=3
Dn Slope=0.005

--- UNT0507 IN SAND CR.g01 (geometry) ---

Geom Title=Existing Conditions

River Reach=UNT0507 IN SAND ,Reach-1
Reach XY= 30
      3474357.57     10525456.32      3474402.72     10525420.48
      3474451.80     10525366.60      3474455.12     10525352.05
      3474428.37     10525322.47      3474424.39     10525303.65
      3474467.49     10525278.94      3474490.94     10525208.25
      3474507.53     10525209.73      3474579.85     10525273.83
      3474592.59     10525270.73      3474631.32     10525241.16
      3474640.41     10525221.57      3474636.70     10525158.89
      3474699.67     10525045.23      3474733.70     10525016.64
      3474799.11     10525022.18      3474906.04     10524914.58
      3474903.40     10524897.20      3474847.13     10524843.70
      3474843.02     10524821.78      3474849.57     10524806.00
      3474862.98     10524795.54      3474904.06     10524785.63
      3474953.43     10524754.88      3474983.29     10524744.51
      3475046.26     10524739.60      3475126.04     10524719.06
      3475172.06     10524692.96      3475247.21     10524690.02

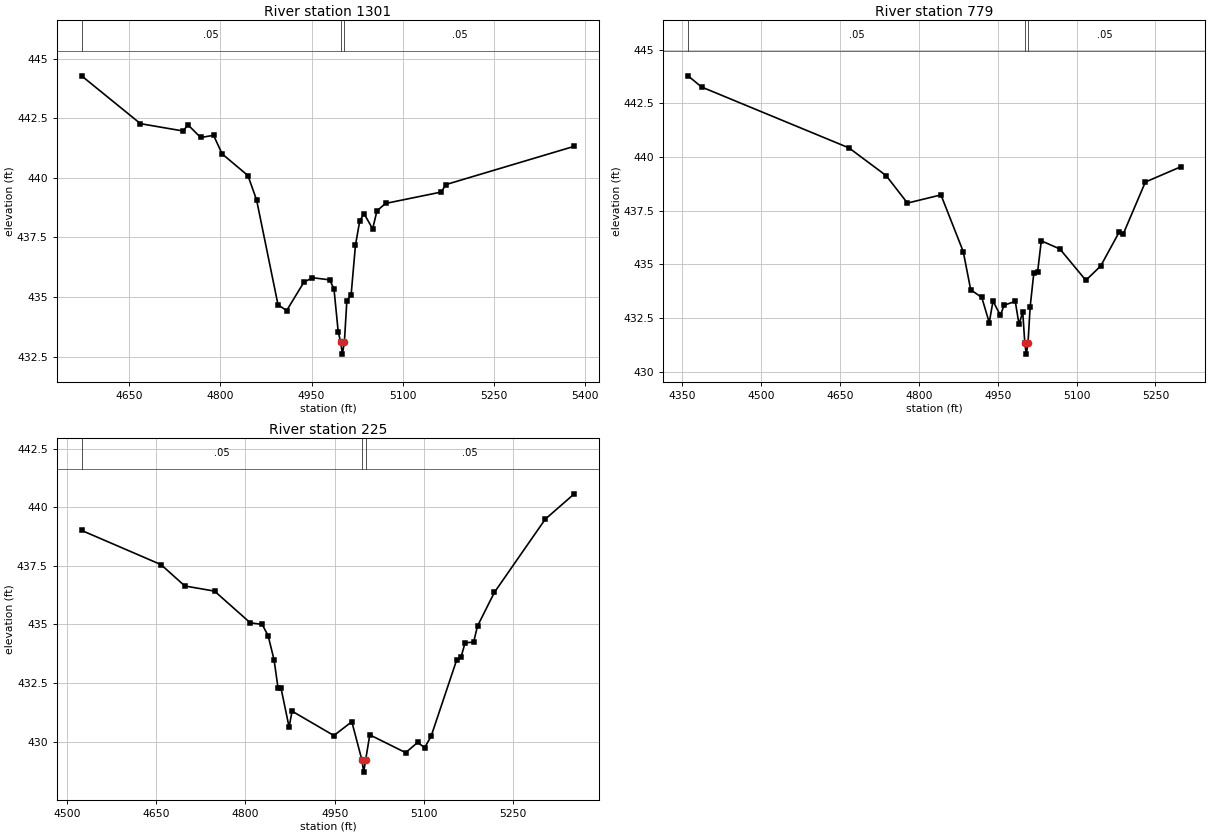
Type RM Length L Ch R = 1,1301,522,522,522
BEGIN DESCRIPTION:
UNT0507 IN SAND CR 1.0
END DESCRIPTION:
XS GIS Cut Line= 2
      3474760.42     10525590.31      3474187.45     10525017.34
#Sta/Elev= 30
  4571.8  444.29  4668.7  442.28  4739.4  441.97  4746.4  442.24  4767.7  441.70
  4788.9  441.79  4803.0  441.01  4845.4  440.10  4859.6  439.08  4894.9  434.67
  4909.1  434.43  4937.4  435.62  4951.5  435.81  4979.8  435.72  4986.9  435.34
  4993.9  433.53  4998.0  433.10  5000.7  432.60  5004.0  433.10  5008.1  434.85
  5015.1  435.09  5022.2  437.17  5029.3  438.20  5036.4  438.50  5050.5  437.86
  5057.6  438.62  5071.7  438.93  5163.6  439.41  5170.7  439.72  5382.1  441.33
#Mann=3,-1,0
  4571.8    0.05       0  4998.0   0.035       0  5004.0    0.05       0
Bank Sta=4998,5004
Exp/Cntr=0.3,0.1

Type RM Length L Ch R = 1,779,554,554,554
BEGIN DESCRIPTION:
UNT0092 IN SAND CR 7.0
END DESCRIPTION:
XS GIS Cut Line= 3
      3474895.97     10525577.27      3474921.20     10525204.14
      3474520.13     10524808.29
#Sta/Elev= 30
  4360.7  443.78  4386.4  443.26  4667.0  440.42  4737.6  439.13  4778.2  437.85
  4841.9  438.23  4884.3  435.59  4898.5  433.81  4919.6  433.45  4933.8  432.28
  4940.9  433.28  4955.0  432.62  4962.1  433.09  4983.3  433.27  4990.4  432.20
  4997.5  432.77  5001.5  431.31  5004.2  430.81  5007.5  431.31  5011.6  433.01
  5018.6  434.59  5025.8  434.64  5032.8  436.09  5068.2  435.71  5117.6  434.25
  5145.9  434.92  5181.3  436.51  5188.4  436.39  5230.8  438.83  5298.2  439.54
#Mann=3,-1,0
  4360.7    0.05       0  5001.5   0.035       0  5007.5    0.05       0
Bank Sta=5001.5,5007.5
Exp/Cntr=0.3,0.1

Type RM Length L Ch R = 1,225,0,0,0
BEGIN DESCRIPTION:
UNT0092 IN SAND CR 10.0
END DESCRIPTION:
XS GIS Cut Line= 4
      3475057.27     10525215.30      3475049.07     10524882.99
      3475020.81     10524642.36      3474828.61     10524476.14
#Sta/Elev= 30
  4524.3  439.01  4658.0  437.55  4698.0  436.64  4748.0  436.42  4808.0  435.07
  4828.1  435.00  4838.1  434.52  4848.1  433.49  4854.9  432.27  4859.9  432.27
  4873.4  430.62  4878.4  431.30  4948.7  430.26  4978.9  430.85  4996.0  429.20
  4998.8  428.70  5002.0  429.20  5009.1  430.29  5069.5  429.53  5089.7  429.97
  5101.4  429.74  5112.4  430.24  5155.2  433.48  5162.8  433.62  5169.4  434.22
  5183.7  434.24  5190.3  434.93  5218.8  436.37  5304.3  439.49  5353.1  440.57
#Mann=3,-1,0
  4524.3    0.05       0  4996.0   0.035       0  5002.0    0.05       0
Bank Sta=4996,5002
Exp/Cntr=0.3,0.1

Chan Stop Cuts=-1