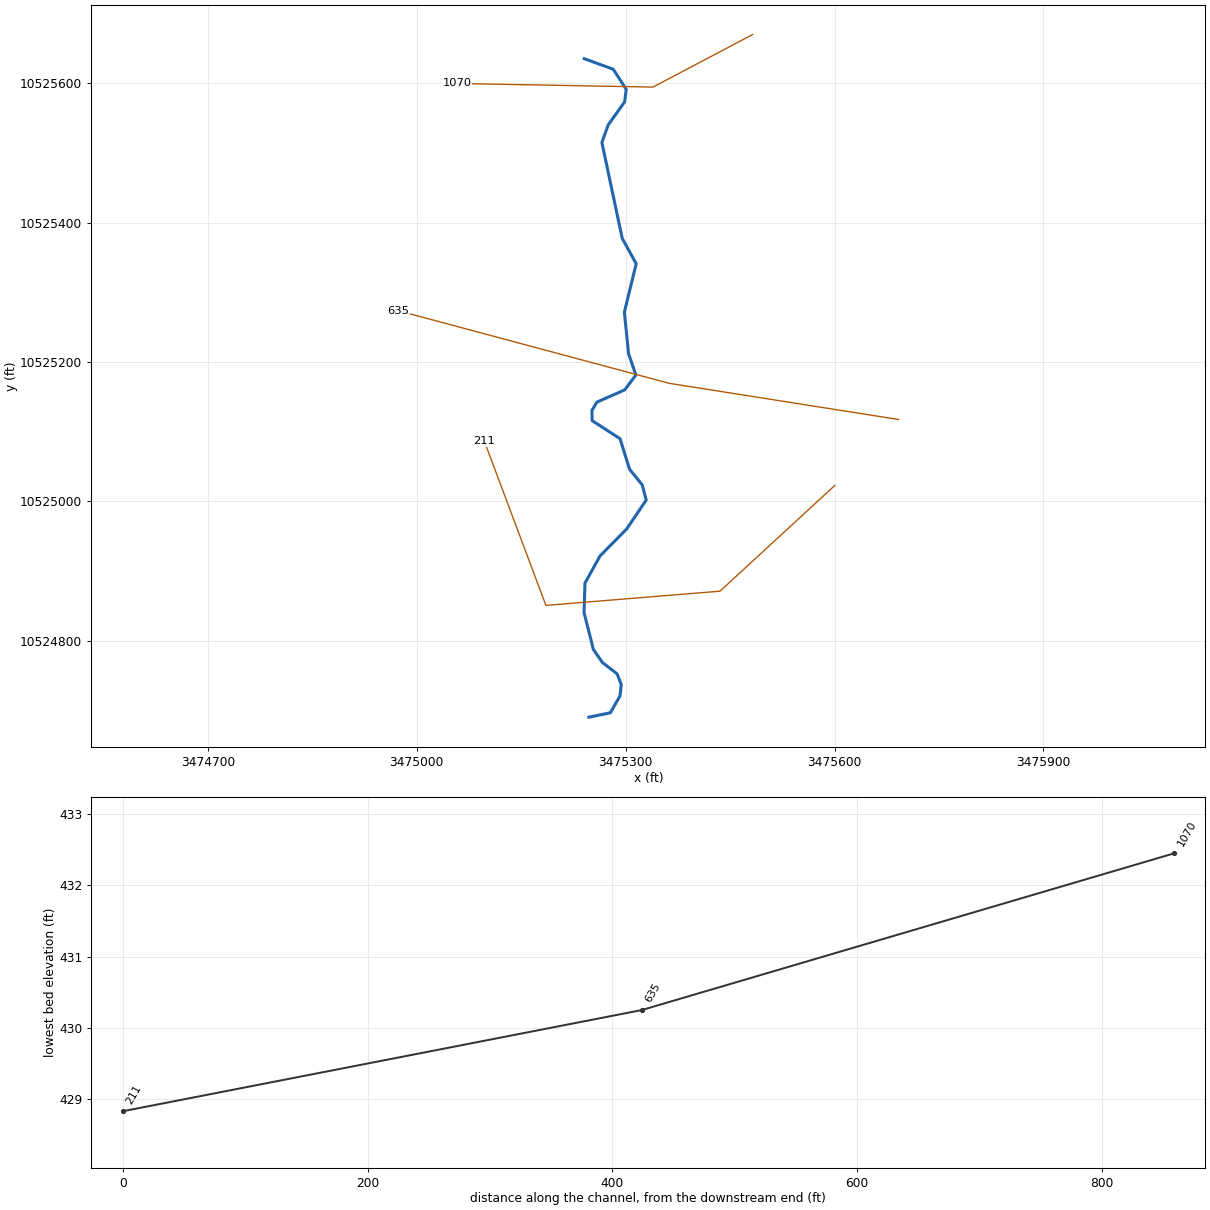
--- UNT0508 IN SAND CR.prj (project) ---

Proj Title=UNT0508 IN SAND CR Base Level Engineering
Current Plan=p01
Default Exp/Contr=0.3,0.1
English Units
Geom File=g01
Flow File=f01
Plan File=p01
BEGIN DESCRIPTION:
UNT0508 IN SAND CR
END DESCRIPTION:

--- UNT0508 IN SAND CR.p01 (plan) ---

Plan Title=Multiple Run
Short Identifier=Multiple
Geom File=g01
Flow File=f01
Subcritical Flow
K Sum by GR= 0
Std Step Tol= 0.01
Critical Tol= 0.01
Num of Std Step Trials= 20
Max Error Tol= 0.3
Flow Tol Ratio= 0.001
Split Flow NTrial= 30
Split Flow Tol= 0.02
Split Flow Ratio= 0.02
Log Output Level= 0
Friction Slope Method= 1
Unsteady Friction Slope Method= 2
Unsteady Bridges Friction Slope Method= 1
Parabolic Critical Depth
Global Vel Dist=  1 , 1 , 1
Global Log Level= 0
CheckData=True
Encroach Param= -1, 0, 0, 0
BEGIN DESCRIPTION:
Multiple Run
END DESCRIPTION:

--- UNT0508 IN SAND CR.f01 (steady flow) ---

Flow Title=Multiple
Number of Profiles=7
Profile Names=10-year,25-year,50-year,1pct_min,100-year,1pct_plu,500-year
River Rch & RM= UNT0508 IN SAND ,Reach-1,1070
     451     585     690     595     805    1088    1090
Boundary for River Rch & Prof#=UNT0508 IN SAND ,Reach-1,1
Up Type=0
Dn Type=3
Dn Slope=0.005
Boundary for River Rch & Prof#=UNT0508 IN SAND ,Reach-1,2
Up Type=0
Dn Type=3
Dn Slope=0.005
Boundary for River Rch & Prof#=UNT0508 IN SAND ,Reach-1,3
Up Type=0
Dn Type=3
Dn Slope=0.005
Boundary for River Rch & Prof#=UNT0508 IN SAND ,Reach-1,4
Up Type=0
Dn Type=3
Dn Slope=0.005
Boundary for River Rch & Prof#=UNT0508 IN SAND ,Reach-1,5
Up Type=0
Dn Type=3
Dn Slope=0.005
Boundary for River Rch & Prof#=UNT0508 IN SAND ,Reach-1,6
Up Type=0
Dn Type=3
Dn Slope=0.005
Boundary for River Rch & Prof#=UNT0508 IN SAND ,Reach-1,7
Up Type=0
Dn Type=3
Dn Slope=0.005

--- UNT0508 IN SAND CR.g01 (geometry) ---

Geom Title=Existing Conditions

River Reach=UNT0508 IN SAND ,Reach-1
Reach XY= 30
      3475240.50     10525635.62      3475282.19     10525620.46
      3475300.80     10525591.60      3475298.55     10525573.60
      3475274.96     10525540.61      3475265.88     10525515.27
      3475295.04     10525377.68      3475315.14     10525341.18
      3475298.15     10525271.66      3475304.17     10525212.09
      3475314.68     10525181.29      3475298.49     10525159.92
      3475258.58     10525142.40      3475251.57     10525130.40
      3475251.89     10525115.88      3475292.00     10525089.84
      3475305.54     10525046.09      3475323.77     10525023.70
      3475329.50     10525001.82      3475301.47     10524960.28
      3475263.27     10524921.66      3475241.57     10524882.59
      3475240.27     10524840.06      3475253.72     10524787.11
      3475266.75     10524768.44      3475287.58     10524752.39
      3475293.66     10524737.19      3475291.92     10524720.70
      3475278.03     10524696.40      3475247.21     10524690.02

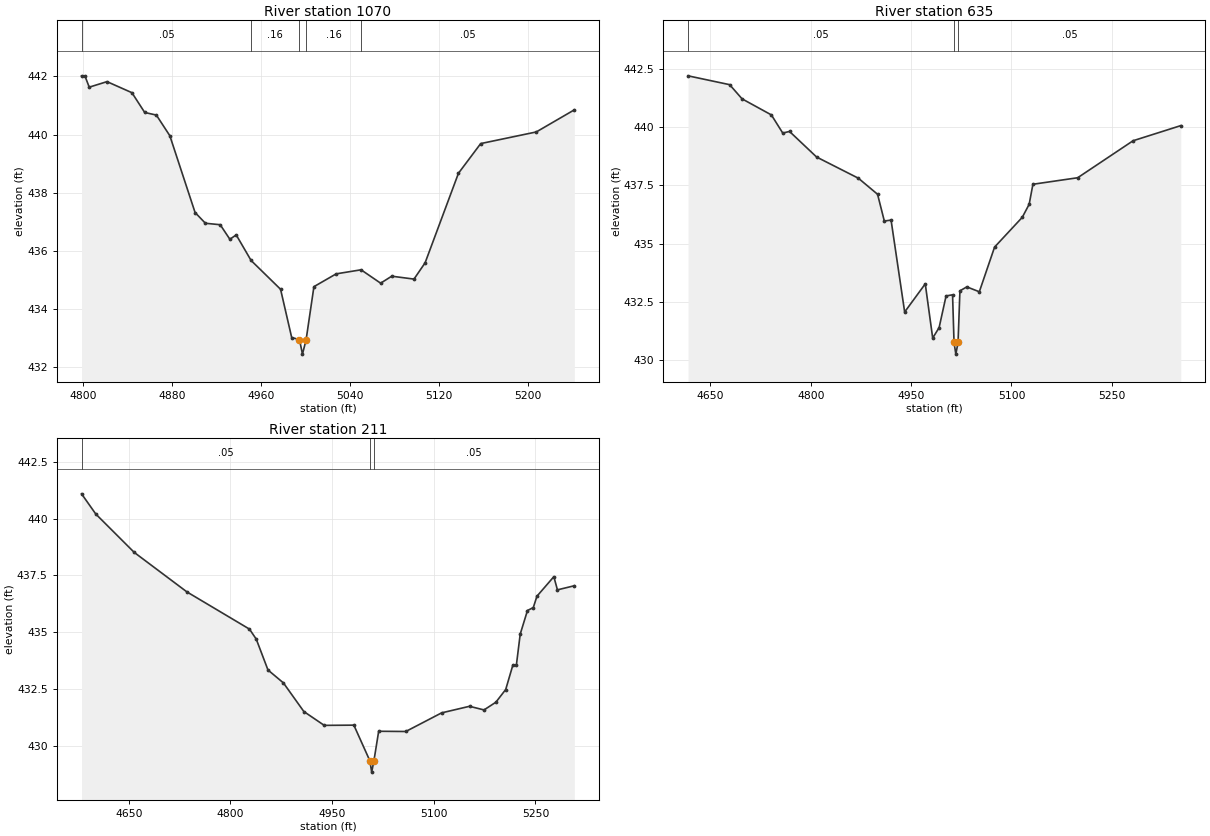
Type RM Length L Ch R = 1,1070,435,435,435
BEGIN DESCRIPTION:
UNT0508 IN SAND CR 2.0
END DESCRIPTION:
XS GIS Cut Line= 3
      3475482.38     10525670.32      3475339.19     10525594.82
      3475057.92     10525600.03
#Sta/Elev= 30
  4798.5  442.02  4801.5  442.02  4805.4  441.63  4821.4  441.82  4843.8  441.44
  4855.3  440.76  4865.8  440.67  4877.9  439.96  4900.6  437.32  4909.9  436.95
  4923.2  436.90  4931.9  436.40  4937.6  436.55  4951.0  435.67  4977.5  434.68
  4987.5  433.02  4994.5  432.95  4997.2  432.45  5000.5  432.95  5007.5  434.77
  5027.5  435.21  5049.9  435.35  5067.5  434.89  5077.5  435.13  5097.5  435.03
  5107.5  435.59  5137.5  438.67  5157.5  439.69  5207.5  440.09  5241.7  440.85
#Mann=5,-1,0
  4798.5    0.05       0  4951.0    0.16       0  4994.5    0.07       0
  5000.5    0.16       0  5049.9    0.05       0
Bank Sta=4994.5,5000.5
Exp/Cntr=0.3,0.1

Type RM Length L Ch R = 1,635,424,424,424
BEGIN DESCRIPTION:
UNT0508 IN SAND CR 1.0
END DESCRIPTION:
XS GIS Cut Line= 3
      3475691.94     10525117.50      3475362.47     10525169.46
      3474973.24     10525273.76
#Sta/Elev= 30
  4616.6  442.21  4678.8  441.83  4697.4  441.22  4741.2  440.53  4758.2  439.75
  4768.3  439.82  4808.8  438.72  4871.2  437.81  4899.9  437.12  4910.0  435.97
  4920.1  436.01  4940.4  432.06  4971.2  433.27  4982.3  430.94  4991.9  431.39
  5002.3  432.75  5012.0  432.80  5014.2  430.75  5016.9  430.25  5020.2  430.75
  5023.0  432.97  5033.3  433.14  5052.0  432.93  5074.8  434.85  5116.2  436.13
  5126.5  436.69  5132.1  437.55  5199.0  437.83  5281.8  439.42  5353.1  440.07
#Mann=3,-1,0
  4616.6    0.05       0  5014.2   0.035       0  5020.2    0.05       0
Bank Sta=5014.2,5020.2
Exp/Cntr=0.3,0.1

Type RM Length L Ch R = 1,211,0,0,0
BEGIN DESCRIPTION:
UNT0508 IN SAND CR 2.1
END DESCRIPTION:
XS GIS Cut Line= 4
      3475600.39     10525022.86      3475435.47     10524870.96
      3475185.47     10524850.56      3475097.03     10525086.37
#Sta/Elev= 30
  4580.4  441.09  4601.4  440.20  4658.1  438.51  4735.8  436.77  4828.1  435.13
  4838.1  434.69  4855.4  433.33  4878.2  432.76  4908.3  431.50  4938.4  430.89
  4982.1  430.90  5005.7  429.33  5008.4  428.83  5011.7  429.33  5018.7  430.63
  5058.7  430.62  5111.5  431.44  5152.7  431.73  5174.1  431.57  5191.6  431.91
  5206.1  432.47  5216.6  433.54  5221.9  433.56  5227.5  434.91  5238.2  435.95
  5246.8  436.08  5252.2  436.58  5277.1  437.44  5282.4  436.86  5307.3  437.04
#Mann=3,-1,0
  4580.4    0.05       0  5005.7   0.035       0  5011.7    0.05       0
Bank Sta=5005.7,5011.7
Exp/Cntr=0.3,0.1

Chan Stop Cuts=-1