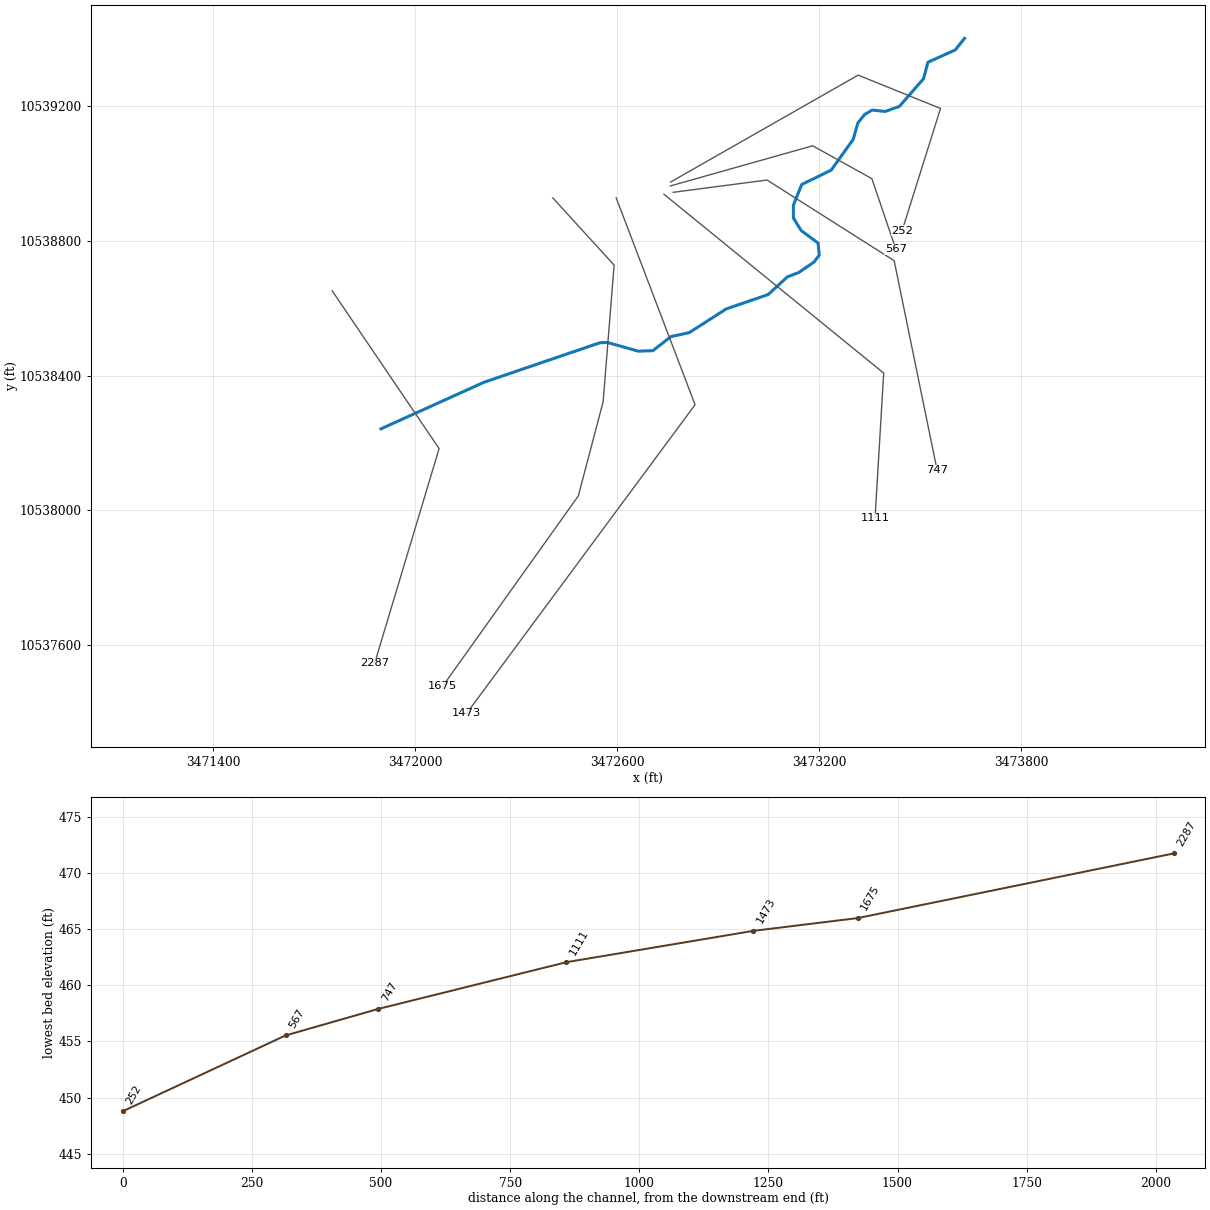
--- UNT0516 IN SAND CR.prj (project) ---

Proj Title=UNT0516 IN SAND CR Base Level Engineering
Current Plan=p01
Default Exp/Contr=0.3,0.1
English Units
Geom File=g01
Flow File=f01
Plan File=p01
BEGIN DESCRIPTION:
UNT0516 IN SAND CR
END DESCRIPTION:

--- UNT0516 IN SAND CR.p01 (plan) ---

Plan Title=Multiple Run
Short Identifier=Multiple
Geom File=g01
Flow File=f01
Subcritical Flow
K Sum by GR= 0
Std Step Tol= 0.01
Critical Tol= 0.01
Num of Std Step Trials= 20
Max Error Tol= 0.3
Flow Tol Ratio= 0.001
Split Flow NTrial= 30
Split Flow Tol= 0.02
Split Flow Ratio= 0.02
Log Output Level= 0
Friction Slope Method= 1
Unsteady Friction Slope Method= 2
Unsteady Bridges Friction Slope Method= 1
Parabolic Critical Depth
Global Vel Dist=  1 , 1 , 1
Global Log Level= 0
CheckData=True
Encroach Param= -1, 0, 0, 0
BEGIN DESCRIPTION:
Multiple Run
END DESCRIPTION:

--- UNT0516 IN SAND CR.f01 (steady flow) ---

Flow Title=Multiple
Number of Profiles=7
Profile Names=10-year,25-year,50-year,1pct_min,100-year,1pct_plu,500-year
River Rch & RM= UNT0516 IN SAND ,Reach-1,2287
     572     757     904     789    1067    1443    1482
Boundary for River Rch & Prof#=UNT0516 IN SAND ,Reach-1,1
Up Type=0
Dn Type=3
Dn Slope=0.005
Boundary for River Rch & Prof#=UNT0516 IN SAND ,Reach-1,2
Up Type=0
Dn Type=3
Dn Slope=0.005
Boundary for River Rch & Prof#=UNT0516 IN SAND ,Reach-1,3
Up Type=0
Dn Type=3
Dn Slope=0.005
Boundary for River Rch & Prof#=UNT0516 IN SAND ,Reach-1,4
Up Type=0
Dn Type=3
Dn Slope=0.005
Boundary for River Rch & Prof#=UNT0516 IN SAND ,Reach-1,5
Up Type=0
Dn Type=3
Dn Slope=0.005
Boundary for River Rch & Prof#=UNT0516 IN SAND ,Reach-1,6
Up Type=0
Dn Type=3
Dn Slope=0.005
Boundary for River Rch & Prof#=UNT0516 IN SAND ,Reach-1,7
Up Type=0
Dn Type=3
Dn Slope=0.005

--- UNT0516 IN SAND CR.g01 (geometry) ---

Geom Title=Existing Conditions

River Reach=UNT0516 IN SAND ,Reach-1
Reach XY= 30
      3471898.61     10538241.64      3472204.71     10538379.98
      3472549.12     10538497.38      3472570.87     10538498.18
      3472662.74     10538472.39      3472706.11     10538473.72
      3472759.90     10538515.57      3472814.43     10538527.41
      3472923.80     10538597.58      3473048.70     10538640.52
      3473105.86     10538693.00      3473139.83     10538705.99
      3473185.04     10538737.28      3473200.55     10538757.70
      3473196.97     10538793.57      3473147.35     10538830.08
      3473123.83     10538867.53      3473123.59     10538905.85
      3473148.32     10538967.34      3473236.05     10539010.23
      3473301.16     10539101.28      3473315.44     10539150.61
      3473335.14     10539175.24      3473357.49     10539188.57
      3473396.58     10539184.44      3473438.76     10539199.64
      3473510.37     10539281.73      3473523.22     10539330.56
      3473604.56     10539367.18      3473632.11     10539401.64

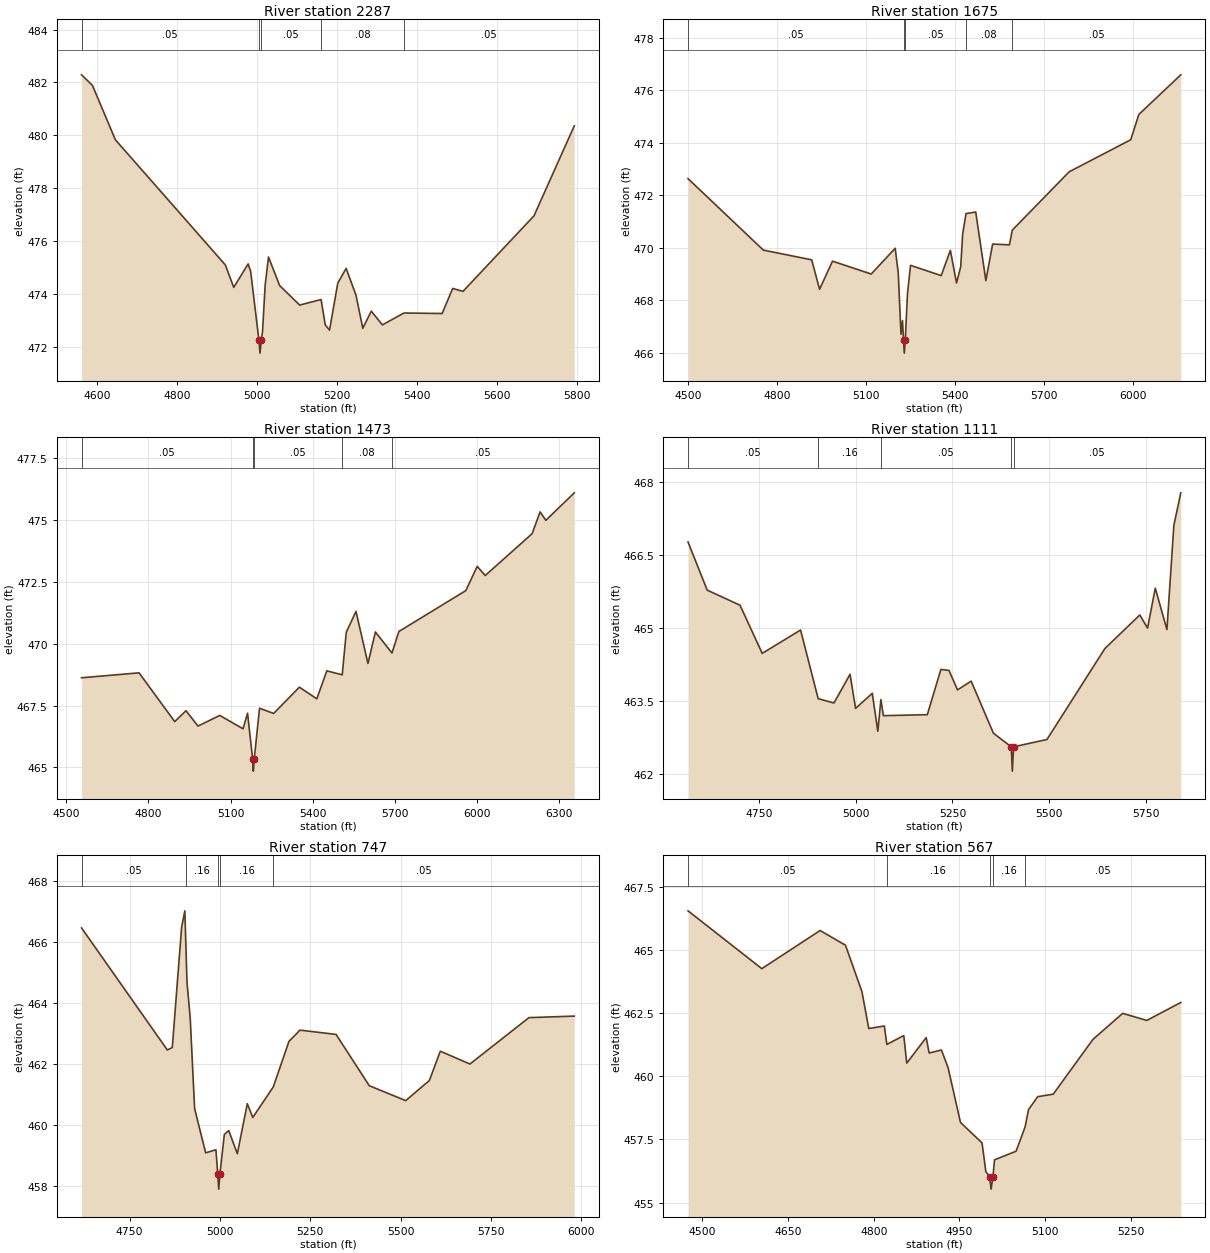
Type RM Length L Ch R = 1,2287,612,612,612
BEGIN DESCRIPTION:
UNT0516 IN SAND CR 1.0
END DESCRIPTION:
XS GIS Cut Line= 3
      3471753.51     10538651.67      3472071.19     10538182.96
      3471879.73     10537545.10
#Sta/Elev= 30
  4561.8  482.29  4589.0  481.89  4646.4  479.83  4921.4  475.09  4942.4  474.24
  4978.4  475.13  4984.7  474.84  5005.3  472.25  5008.0  471.75  5011.3  472.25
  5014.3  472.56  5020.9  474.32  5029.3  475.39  5057.1  474.31  5107.2  473.57
  5160.8  473.78  5171.2  472.82  5181.9  472.62  5202.5  474.40  5223.4  474.96
  5248.0  473.95  5265.1  472.69  5286.3  473.34  5314.1  472.82  5368.1  473.27
  5463.5  473.25  5489.8  474.20  5515.7  474.09  5693.2  476.95  5794.0  480.36
#Mann=5,-1,0
  4561.8    0.05       0  5005.3    0.03       0  5011.3    0.05       0
  5160.8    0.08       0  5368.1    0.05       0
Bank Sta=5005.3,5011.3
Exp/Cntr=0.3,0.1

Type RM Length L Ch R = 1,1675,202,202,202
BEGIN DESCRIPTION:
UNT0516 IN SAND CR 2.2
END DESCRIPTION:
XS GIS Cut Line= 5
      3472408.78     10538927.69      3472591.07     10538728.04
      3472558.52     10538322.22      3472484.73     10538042.28
      3472081.38     10537476.28
#Sta/Elev= 30
  4498.5  472.63  4752.7  469.91  4915.7  469.54  4942.2  468.42  4985.9  469.49
  5116.4  469.00  5197.3  469.98  5207.6  469.04  5216.8  466.71  5221.9  467.23
  5225.3  466.49  5228.0  465.99  5231.3  466.49  5238.6  468.24  5249.0  469.33
  5352.4  468.94  5383.4  469.90  5404.1  468.66  5418.3  469.28  5424.8  470.52
  5436.2  471.30  5468.9  471.36  5503.1  468.75  5525.9  470.14  5582.5  470.11
  5592.2  470.67  5784.1  472.89  5991.8  474.11  6018.9  475.07  6160.5  476.58
#Mann=5,-1,0
  4498.5    0.05       0  5225.3    0.03       0  5231.3    0.05       0
  5436.2    0.08       0  5592.2    0.05       0
Bank Sta=5225.3,5231.3
Exp/Cntr=0.3,0.1

Type RM Length L Ch R = 1,1473,362,362,362
BEGIN DESCRIPTION:
UNT0516 IN SAND CR 2.0
END DESCRIPTION:
XS GIS Cut Line= 3
      3472597.23     10538927.76      3472831.61     10538313.17
      3472152.94     10537396.28
#Sta/Elev= 30
  4555.8  468.62  4765.7  468.82  4895.9  466.85  4936.9  467.29  4980.8  466.67
  5060.3  467.10  5145.2  466.56  5161.7  467.19  5180.1  465.35  5182.8  464.85
  5186.1  465.35  5205.4  467.39  5256.9  467.18  5350.9  468.24  5414.5  467.77
  5451.0  468.90  5507.2  468.74  5522.0  470.46  5557.5  471.30  5601.1  469.20
  5628.4  470.47  5688.8  469.62  5714.0  470.49  5958.2  472.14  5999.9  473.12
  6029.2  472.75  6200.3  474.44  6229.5  475.32  6250.4  474.98  6354.3  476.09
#Mann=5,-1,0
  4555.8    0.05       0  5180.1    0.03       0  5186.1    0.05       0
  5507.2    0.08       0  5688.8    0.05       0
Bank Sta=5180.1,5186.1
Exp/Cntr=0.3,0.1

Type RM Length L Ch R = 1,1111,364,364,364
BEGIN DESCRIPTION:
UNT0516 IN SAND CR 2.1
END DESCRIPTION:
XS GIS Cut Line= 3
      3472739.15     10538938.42      3473391.95     10538407.15
      3473366.21     10537975.89
#Sta/Elev= 30
  4566.5  466.77  4616.1  465.78  4700.9  465.47  4758.3  464.48  4857.4  464.96
  4902.9  463.55  4943.7  463.46  4985.3  464.05  4999.7  463.35  5042.8  463.66
  5057.1  462.88  5065.1  463.53  5071.5  463.20  5185.0  463.22  5220.1  464.15
  5241.0  464.13  5263.2  463.73  5298.4  463.91  5355.9  462.84  5402.0  462.56
  5404.8  462.06  5408.0  462.56  5494.2  462.71  5644.1  464.58  5734.3  465.27
  5754.3  465.00  5774.3  465.82  5804.4  464.97  5822.3  467.11  5840.2  467.78
#Mann=5,-1,0
  4566.5    0.05       0  4902.9    0.16       0  5065.1    0.05       0
  5402.0    0.07       0  5408.0    0.05       0
Bank Sta=5402,5408
Exp/Cntr=0.3,0.1

Type RM Length L Ch R = 1,747,180,180,180
BEGIN DESCRIPTION:
UNT0516 IN SAND CR 2.11
END DESCRIPTION:
XS GIS Cut Line= 4
      3472766.75     10538944.25      3473045.41     10538980.71
      3473423.02     10538741.13      3473550.63     10538118.71
#Sta/Elev= 30
  4616.9  466.46  4854.3  462.46  4868.0  462.54  4893.8  466.48  4902.7  467.02
  4905.4  465.97  4908.7  464.69  4917.7  463.48  4929.8  460.54  4960.3  459.09
  4988.8  459.19  4993.8  458.40  4996.5  457.90  4999.8  458.40  5012.0  459.69
  5024.3  459.82  5048.0  459.06  5075.6  460.70  5090.8  460.25  5147.5  461.25
  5190.8  462.74  5221.3  463.11  5321.2  462.97  5413.1  461.29  5514.0  460.80
  5579.4  461.46  5609.7  462.42  5691.7  462.00  5855.0  463.52  5980.5  463.57
#Mann=5,-1,0
  4616.9    0.05       0  4905.4    0.16       0  4993.8    0.07       0
  4999.8    0.16       0  5147.5    0.05       0
Bank Sta=4993.8,4999.8
Exp/Cntr=0.3,0.1

Type RM Length L Ch R = 1,567,315,315,315
BEGIN DESCRIPTION:
UNT0516 IN SAND CR 2.111
END DESCRIPTION:
XS GIS Cut Line= 4
      3472757.82     10538963.06      3473181.00     10539082.42
      3473356.78     10538984.76      3473428.00     10538775.42
#Sta/Elev= 30
  4475.2  466.55  4604.3  464.26  4706.2  465.77  4750.6  465.19  4779.4  463.35
  4791.4  461.89  4818.6  461.99  4823.0  461.26  4852.6  461.61  4857.8  460.52
  4891.8  461.53  4897.0  460.92  4918.4  461.04  4930.1  460.34  4951.8  458.17
  4989.5  457.36  4996.2  456.22  5002.6  456.03  5005.3  455.53  5008.6  456.03
  5011.3  456.69  5049.0  457.03  5064.8  457.99  5070.8  458.68  5086.8  459.19
  5114.0  459.29  5183.5  461.46  5235.5  462.49  5277.7  462.21  5337.1  462.92
#Mann=5,-1,0
  4475.2    0.05       0  4823.0    0.16       0  5002.6    0.07       0
  5008.6    0.16       0  5064.8    0.05       0
Bank Sta=5002.6,5008.6
Exp/Cntr=0.3,0.1

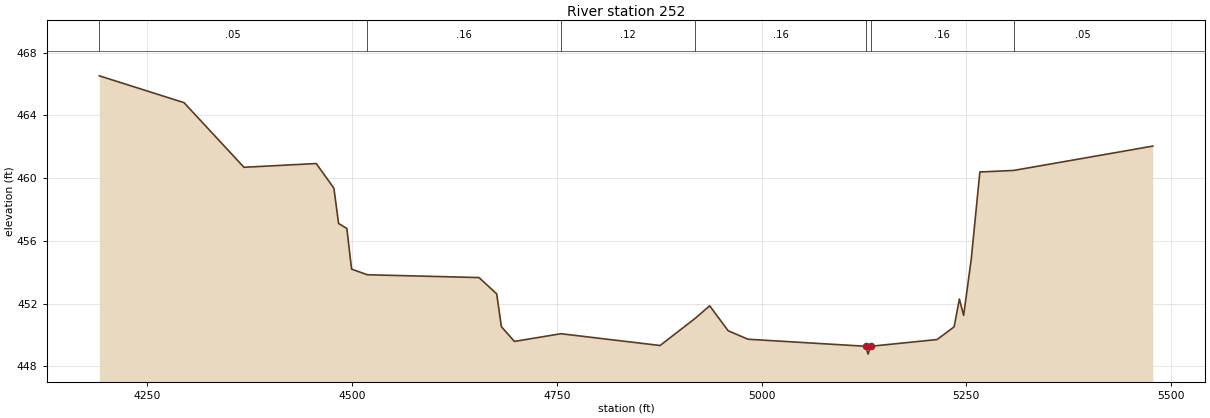
Type RM Length L Ch R = 1,252,0,0,0
BEGIN DESCRIPTION:
UNT0516 IN SAND CR 3.0
END DESCRIPTION:
XS GIS Cut Line= 4
      3472758.65     10538974.61      3473315.98     10539292.34
      3473560.77     10539193.38      3473446.65     10538830.27
#Sta/Elev= 30
  4191.5  466.52  4294.9  464.81  4368.1  460.69  4456.3  460.93  4477.9  459.36
  4483.6  457.11  4493.7  456.79  4499.5  454.20  4518.6  453.84  4655.1  453.66
  4676.7  452.62  4682.4  450.53  4698.3  449.59  4755.1  450.08  4876.2  449.33
  4919.0  451.06  4936.7  451.86  4959.3  450.27  4983.5  449.73  5127.3  449.28
  5130.1  448.78  5133.3  449.28  5214.4  449.71  5235.2  450.52  5241.6  452.29
  5246.8  451.25  5256.1  454.84  5266.6  460.39  5308.0  460.49  5477.7  462.04
#Mann=7,-1,0
  4191.5    0.05       0  4518.6    0.16       0  4755.1    0.12       0
  4919.0    0.16       0  5127.3    0.07       0  5133.3    0.16       0
  5308.0    0.05       0
Bank Sta=5127.3,5133.3
Exp/Cntr=0.3,0.1

Chan Stop Cuts=-1