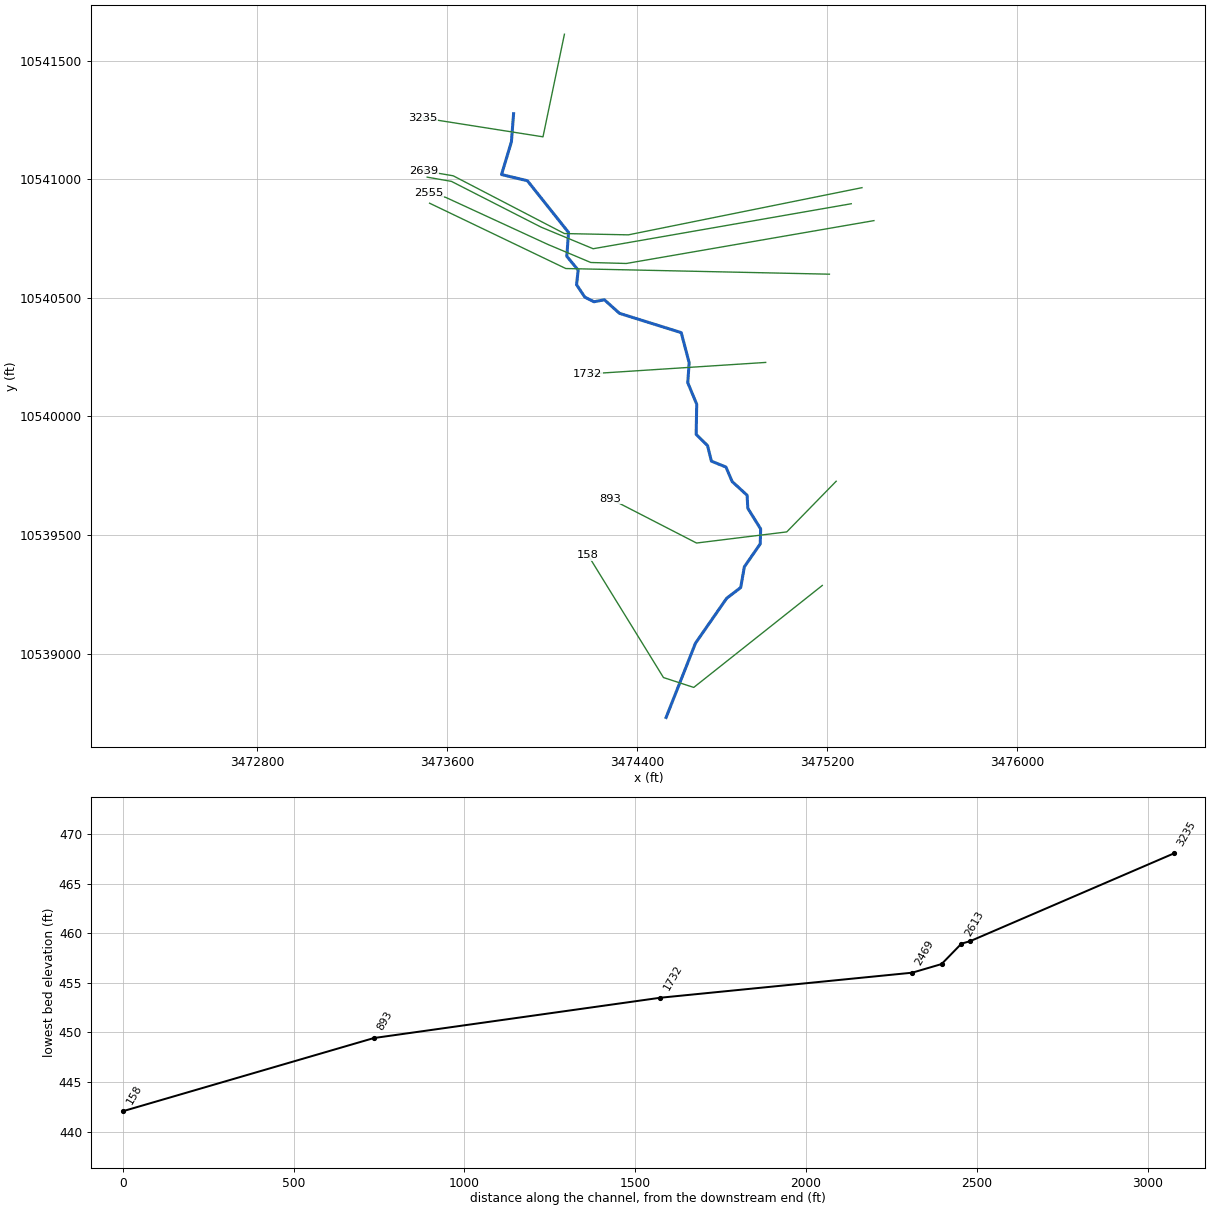
--- UNT0517 IN SAND CR.prj (project) ---

Proj Title=UNT0517 IN SAND CR Base Level Engineering
Current Plan=p01
Default Exp/Contr=0.3,0.1
English Units
Geom File=g01
Flow File=f01
Plan File=p01
Y Axis Title=Elevation
X Axis Title(PF)=Main Channel Distance
X Axis Title(XS)=Station
BEGIN DESCRIPTION:
UNT0517 IN SAND CR
END DESCRIPTION:
DSS Export Rating Curves= 0
DSS Export Rating Curve Sorted= 0
DSS Export Volume Flow Curves= 0
DXF OffsetX= 0
DXF OffsetY= 0
DXF ScaleX= 1
DXF ScaleY= 10

--- UNT0517 IN SAND CR.p01 (plan) ---

Plan Title=Multiple Run
Short Identifier=Multiple
Geom File=g01
Flow File=f01
Subcritical Flow
K Sum by GR= 0
Std Step Tol= 0.01
Critical Tol= 0.01
Num of Std Step Trials= 20
Max Error Tol= 0.3
Flow Tol Ratio= 0.001
Split Flow NTrial= 30
Split Flow Tol= 0.02
Split Flow Ratio= 0.02
Log Output Level= 0
Friction Slope Method= 1
Unsteady Friction Slope Method= 2
Unsteady Bridges Friction Slope Method= 1
Parabolic Critical Depth
Global Vel Dist=  1 , 1 , 1
Global Log Level= 0
CheckData=True
Encroach Param= -1, 0, 0, 0
BEGIN DESCRIPTION:
Multiple Run
END DESCRIPTION:

--- UNT0517 IN SAND CR.f01 (steady flow) ---

Flow Title=Multiple
Number of Profiles=7
Profile Names=10-year,25-year,50-year,1pct_min,100-year,1pct_plu,500-year
River Rch & RM= UNT0517 IN SAND ,Reach-1,3235
     711     950    1141    1001    1354    1831    1898
Boundary for River Rch & Prof#=UNT0517 IN SAND ,Reach-1,1
Up Type=0
Dn Type=3
Dn Slope=0.005
Boundary for River Rch & Prof#=UNT0517 IN SAND ,Reach-1,2
Up Type=0
Dn Type=3
Dn Slope=0.005
Boundary for River Rch & Prof#=UNT0517 IN SAND ,Reach-1,3
Up Type=0
Dn Type=3
Dn Slope=0.005
Boundary for River Rch & Prof#=UNT0517 IN SAND ,Reach-1,4
Up Type=0
Dn Type=3
Dn Slope=0.005
Boundary for River Rch & Prof#=UNT0517 IN SAND ,Reach-1,5
Up Type=0
Dn Type=3
Dn Slope=0.005
Boundary for River Rch & Prof#=UNT0517 IN SAND ,Reach-1,6
Up Type=0
Dn Type=3
Dn Slope=0.005
Boundary for River Rch & Prof#=UNT0517 IN SAND ,Reach-1,7
Up Type=0
Dn Type=3
Dn Slope=0.005

--- UNT0517 IN SAND CR.g01 (geometry) ---

Geom Title=Existing Conditions
Program Version=4.10

River Reach=UNT0517 IN SAND ,Reach-1
Reach XY= 30
      3473879.37     10541275.93      3473870.19     10541157.46
       3473828.6      10541019.6      3473937.66      10540993.4
      3474110.93     10540775.65      3474103.64     10540675.13
      3474151.56      10540616.8      3474144.79     10540555.34
      3474179.68     10540502.74      3474218.23     10540483.47
      3474261.98      10540491.8      3474325.91     10540434.59
      3474585.79     10540353.45      3474619.21      10540226.8
      3474613.43     10540142.34      3474651.07     10540051.62
       3474648.8     10539924.46      3474696.82     10539877.18
      3474712.92     10539811.84      3474774.39     10539786.89
      3474800.44     10539725.79       3474863.5     10539667.98
      3474866.32     10539613.36      3474920.54     10539526.12
       3474918.8     10539463.16      3474851.89     10539366.72
      3474836.48     10539279.15      3474777.35     10539233.97
      3474645.91     10539044.77      3474522.11     10538731.64

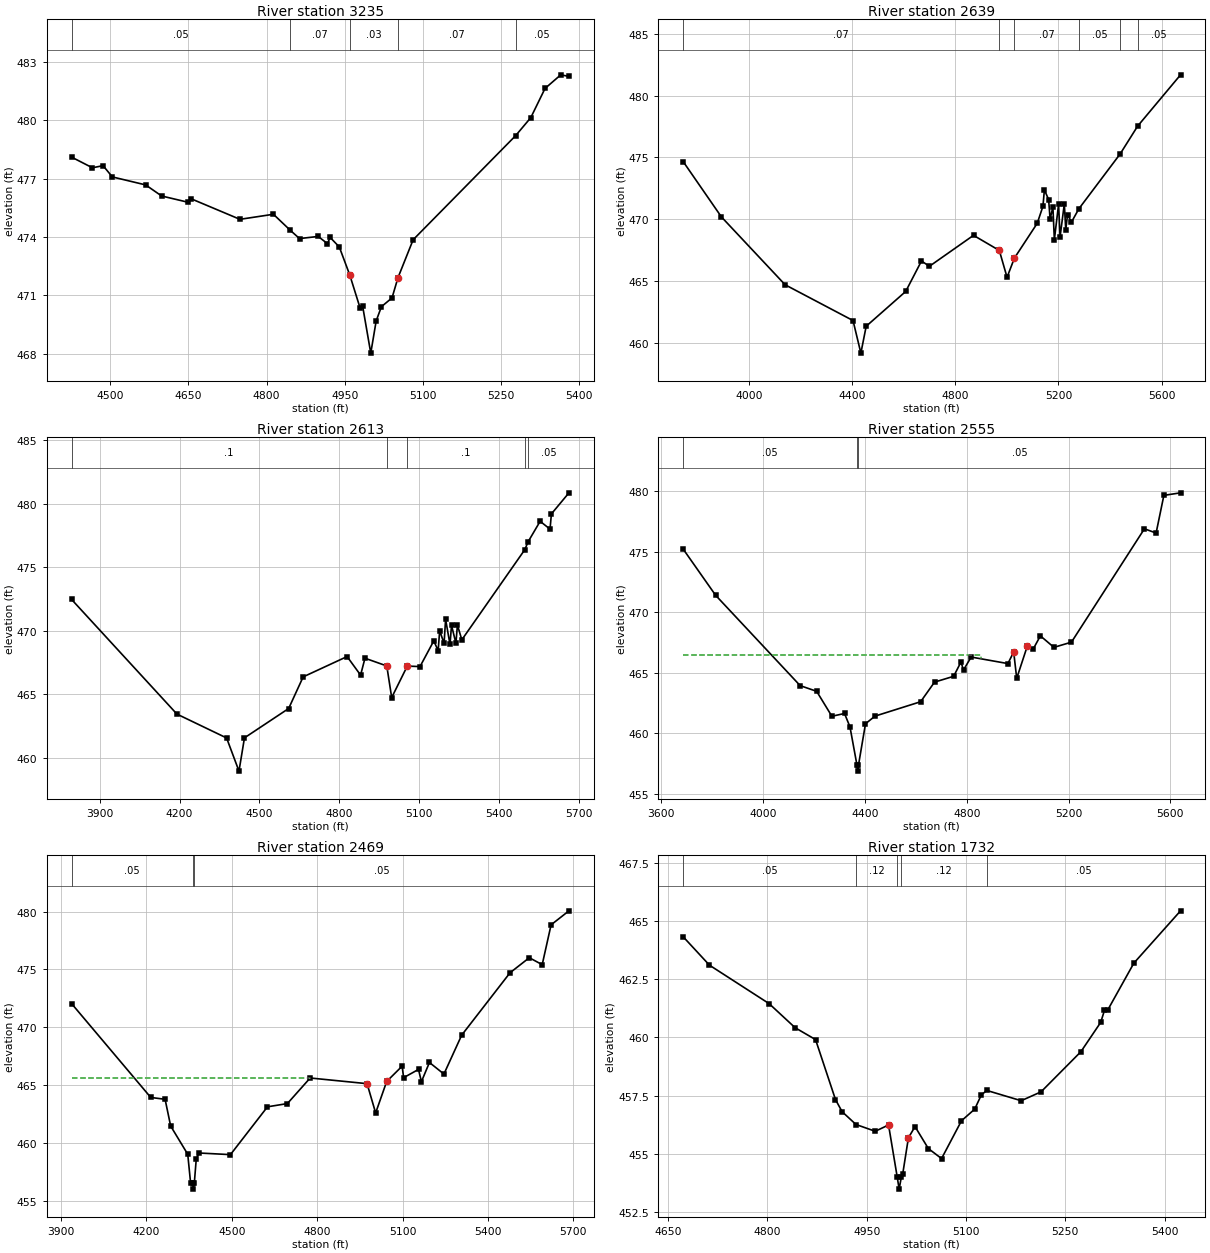
Type RM Length L Ch R = 1 ,3235    ,596,596,596
BEGIN DESCRIPTION:
UNT0517 IN SAND CR 4.0
END DESCRIPTION:
XS GIS Cut Line= 3
      3474093.61     10541610.86      3474003.32     10541178.53
      3473496.73     10541258.33
#Sta/Elev= 30
  4425.8  478.11  4465.9  477.56  4486.3  477.67  4504.1  477.09    4568  476.68
  4598.7  476.11    4649  475.79  4654.1  475.98    4749  474.91  4813.2  475.17
  4845.8  474.34  4863.3  473.92  4899.1  474.03  4916.9  473.66    4922  473.98
  4939.6  473.49  4959.8  472.04  4979.4  470.36  4984.5  470.43    5000  468.03
  5010.4  469.69  5020.5  470.42  5040.8  470.87  5052.1   471.9  5081.3  473.86
  5277.9  479.21  5307.1  480.14  5334.4  481.64  5364.6  482.34  5380.3  482.26
#Mann= 5 ,-1 , 0
  4425.8     .05       0  4845.8     .07       0  4959.8     .03       0
  5052.1     .07       0  5277.9     .05       0
Bank Sta=4959.8,5052.1
XS Rating Curve= 0 ,0
Exp/Cntr=0.3,0.1

Type RM Length L Ch R = 1 ,2639    ,26,26,26
BEGIN DESCRIPTION:
UNT0517 IN SAND CR 4.4
END DESCRIPTION:
XS GIS Cut Line= 5
      3475347.51     10540964.28      3474363.06     10540765.47
      3474093.54     10540770.91      3473624.79      10541014.4
      3473501.05     10541035.24
#Sta/Elev= 30
  3745.7  474.67    3894   470.2  4140.9  464.72  4404.1  461.83  4434.5   459.2
  4455.1  461.37  4608.2  464.18  4669.4  466.64    4700  466.21    4871  468.71
    4971  467.49    5001  465.32  5029.4  466.87  5117.9  469.68    5140  471.05
  5145.7  472.38  5162.1   471.6  5167.8  470.02  5178.6     471  5184.3  468.36
  5200.7  471.22  5206.4  468.58  5222.9  471.25  5228.5  469.14  5235.3  470.39
  5250.6  469.78  5279.5  470.86  5439.5  475.29  5507.1  477.53  5673.3  481.67
#Mann= 6 ,-1 , 0
  3745.7     .07       0    4971     .03       0  5029.4     .07       0
  5279.5     .05       0  5439.5     .16       0  5507.1     .05       0
#XS Ineff= 2 , 0
       0 4906.92  467.69  5145.7       0  472.38
Permanent Ineff=
       T       F
Bank Sta=4971,5029.4
XS Rating Curve= 0 ,0
Exp/Cntr=0.3,0.1

Type RM Length L Ch R = 1 ,2613    ,58,58,58
BEGIN DESCRIPTION:
UNT0517 IN SAND CR 4.1
END DESCRIPTION:
XS GIS Cut Line= 5
      3475302.31     10540896.56      3474214.66     10540706.95
      3473995.24     10540797.99      3473617.63      10540990.7
      3473515.33      10541008.6
#Sta/Elev= 30
  3793.8  472.46  4189.9  463.43  4376.6  461.55  4423.1  458.94  4443.7  461.56
  4609.8  463.87  4664.3  466.36  4829.4  467.96  4880.1   466.5  4896.6  467.83
  4978.6  467.22    4997  464.73  5055.6  467.21  5103.4  467.17  5155.1  469.19
  5171.7  468.43  5177.3     470  5193.9  468.99  5199.6  470.89  5216.2  468.91
  5221.8  470.42  5238.4  469.01    5244  470.44  5260.6  469.28  5497.4  476.38
  5509.5  476.99  5554.9  478.61  5592.1  477.99  5597.2  479.19  5663.2  480.85
#Mann= 5 ,-1 , 0
  3793.8      .1       0  4978.6     .05       0  5055.6      .1       0
  5497.4     .16       0  5509.5     .05       0
#XS Ineff= 2 , 0
       0  4826.1  466.51               0
Permanent Ineff=
       T       F
Bank Sta=4978.6,5055.6
XS Rating Curve= 0 ,0
Exp/Cntr=0.3,0.1

Type RM Length L Ch R = 1 ,2555    ,86,86,86
BEGIN DESCRIPTION:
UNT0517 IN SAND CR 4.2
END DESCRIPTION:
XS GIS Cut Line= 6
      3475397.88      10540825.4      3474354.43     10540644.83
      3474204.67     10540648.95      3474023.88     10540725.07
      3473594.19     10540922.99      3473521.32     10540943.81
#Sta/Elev= 30
    3686  475.23  3813.6  471.41  4145.7  463.95  4210.5  463.48  4270.3  461.42
  4319.9  461.65  4341.4  460.54  4368.8  457.39  4371.6  456.89  4374.8  457.39
  4402.3   460.8  4439.4  461.43  4618.8  462.62  4673.5  464.24  4748.6  464.72
  4777.3   465.9  4787.3  465.24  4817.3  466.31  4961.7  465.77  4984.4  466.73
  4996.3  464.55  5038.3  467.24  5060.3  466.94  5089.2  468.06  5142.5  467.11
  5211.3  467.54  5497.9   476.9  5543.8  476.55  5574.3  479.66  5639.8  479.87
#Mann= 3 ,-1 , 0
    3686     .05       0  4368.8     .04       0  4374.8     .05       0
#XS Ineff= 2 , 0
       0  4856.4  466.45               0
Permanent Ineff=
       T       F
Bank Sta=4984.4,5038.3
XS Rating Curve= 0 ,0
Exp/Cntr=0.3,0.1

Type RM Length L Ch R = 1 ,2469    ,737,737,737
BEGIN DESCRIPTION:
UNT0517 IN SAND CR 4.3
END DESCRIPTION:
XS GIS Cut Line= 3
      3475210.31      10540599.7       3474099.4     10540623.51
      3473525.47     10540898.79
#Sta/Elev= 30
  3937.1  472.05  4215.4  463.94  4265.8  463.78  4285.4  461.47  4345.4  459.03
  4355.4  456.56  4362.4  456.52  4365.2  456.02  4368.4  456.52  4375.4  458.65
  4385.4  459.14  4495.4     459  4625.5  463.13  4695.5  463.41  4775.5  465.62
  4975.5  465.13  5005.6   462.6  5044.4  465.32  5098.5  466.64    5104  465.65
  5156.2  466.36  5166.4   465.3  5194.6  466.96  5245.5  465.96  5307.9  469.32
  5477.8  474.71  5545.5  476.01  5590.8  475.41    5622  478.85  5684.8  480.06
#Mann= 3 ,-1 , 0
  3937.1     .05       0  4362.4    .035       0  4368.4     .05       0
#XS Ineff= 2 , 0
       0 4773.67  465.62               0
Permanent Ineff=
       T       F
Bank Sta=4975.5,5044.4
XS Rating Curve= 0 ,0
Exp/Cntr=0.3,0.1

Type RM Length L Ch R = 1 ,1732    ,839,839,839
BEGIN DESCRIPTION:
UNT0517 IN SAND CR 2.0
END DESCRIPTION:
XS GIS Cut Line= 2
      3474941.81     10540227.85      3474191.79     10540179.24
#Sta/Elev= 30
  4672.6  464.32  4712.4   463.1  4802.6  461.45  4841.8  460.42  4872.7  459.91
  4902.8  457.34  4912.8  456.82  4933.8  456.27  4962.9  455.98    4983  456.25
  4996.2     454    4999   453.5  5002.2     454  5004.3  454.13    5013   455.7
    5023  456.18  5043.1  455.24  5063.1  454.81  5093.2  456.43  5113.2  456.93
  5123.2  457.54  5131.5  457.73  5183.4  457.29  5213.4  457.67  5273.6  459.39
  5303.6  460.65  5309.2  461.16  5314.2  461.18  5353.7  463.19  5424.2  465.43
#Mann= 5 ,-1 , 0
  4672.6     .05       0  4933.8     .12       0  4996.2     .07       0
  5002.2     .12       0  5131.5     .05       0
Bank Sta=4983,5013
XS Rating Curve= 0 ,0
Exp/Cntr=0.3,0.1

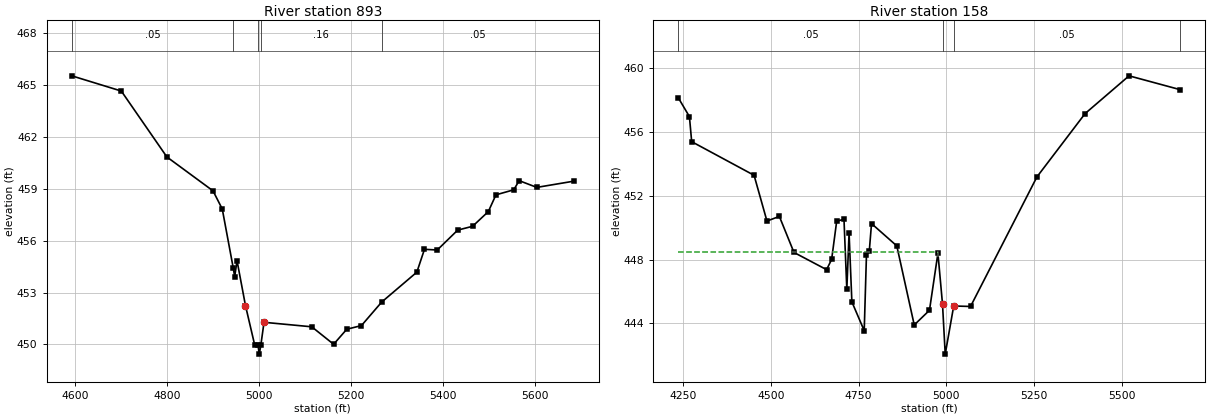
Type RM Length L Ch R = 1 ,893     ,735,735,735
BEGIN DESCRIPTION:
UNT0517 IN SAND CR 1.0
END DESCRIPTION:
XS GIS Cut Line= 4
      3475238.84     10539727.19      3475030.52     10539513.67
      3474650.32     10539466.79      3474286.42     10539653.94
#Sta/Elev= 30
  4593.1  465.53  4700.7  464.65  4799.7  460.84  4899.9  458.88    4920  457.83
    4944   454.4    4947  453.92  4952.1  454.84  4970.4  452.25  4990.6  449.95
  4997.7  449.94  5000.4  449.44  5003.7  449.94  5010.7  451.28  5114.4  451.02
  5161.9  450.01  5190.5  450.88  5222.3  451.09  5266.3  452.45  5342.7  454.18
  5359.2   455.5    5387  455.46  5431.4  456.61  5463.7  456.83  5497.9  457.68
  5514.5  458.65  5553.2  458.94  5564.9  459.47  5603.2  459.08  5683.7  459.44
#Mann= 5 ,-1 , 0
  4593.1     .05       0    4944     .16       0  4997.7     .07       0
  5003.7     .16       0  5266.3     .05       0
Bank Sta=4970.4,5010.7
XS Rating Curve= 0 ,0
Exp/Cntr=0.3,0.1

Type RM Length L Ch R = 1 ,158     ,0,0,0
BEGIN DESCRIPTION:
UNT0517 IN SAND CR 1.1
END DESCRIPTION:
XS GIS Cut Line= 4
      3475180.26     10539287.95      3474638.58     10538858.25
      3474510.98     10538899.92      3474193.27     10539415.54
#Sta/Elev= 30
  4235.6  458.16  4267.5  456.97  4273.9   455.4  4451.8  453.29  4488.5  450.42
  4523.9  450.71  4565.5  448.45  4658.5  447.37  4672.9  448.01  4687.3  450.41
  4708.1  450.53  4716.2  446.13  4722.6  449.67  4730.6  445.35  4765.8  443.54
  4772.2   448.3  4780.3  448.55  4786.6  450.26  4858.7  448.86  4908.4   443.9
  4951.8  444.82  4975.9   448.4    4989   445.2  4996.7  442.07  5020.9  445.09
  5068.9  445.06  5258.2  453.19  5395.4  457.16  5520.8  459.53  5666.9  458.66
#Mann= 4 ,-1 , 0
  4235.6     .05       0    4989     .03       0  5020.9     .05       0
  5666.9     .05       0
#XS Ineff= 2 , 0
         4976.74  448.45
Permanent Ineff=
       F       F
Bank Sta=4989,5020.9
XS Rating Curve= 0 ,0
Exp/Cntr=0.3,0.1

Chan Stop Cuts=-1
Use User Specified Reach Order=0
Composite Channel Slope=5