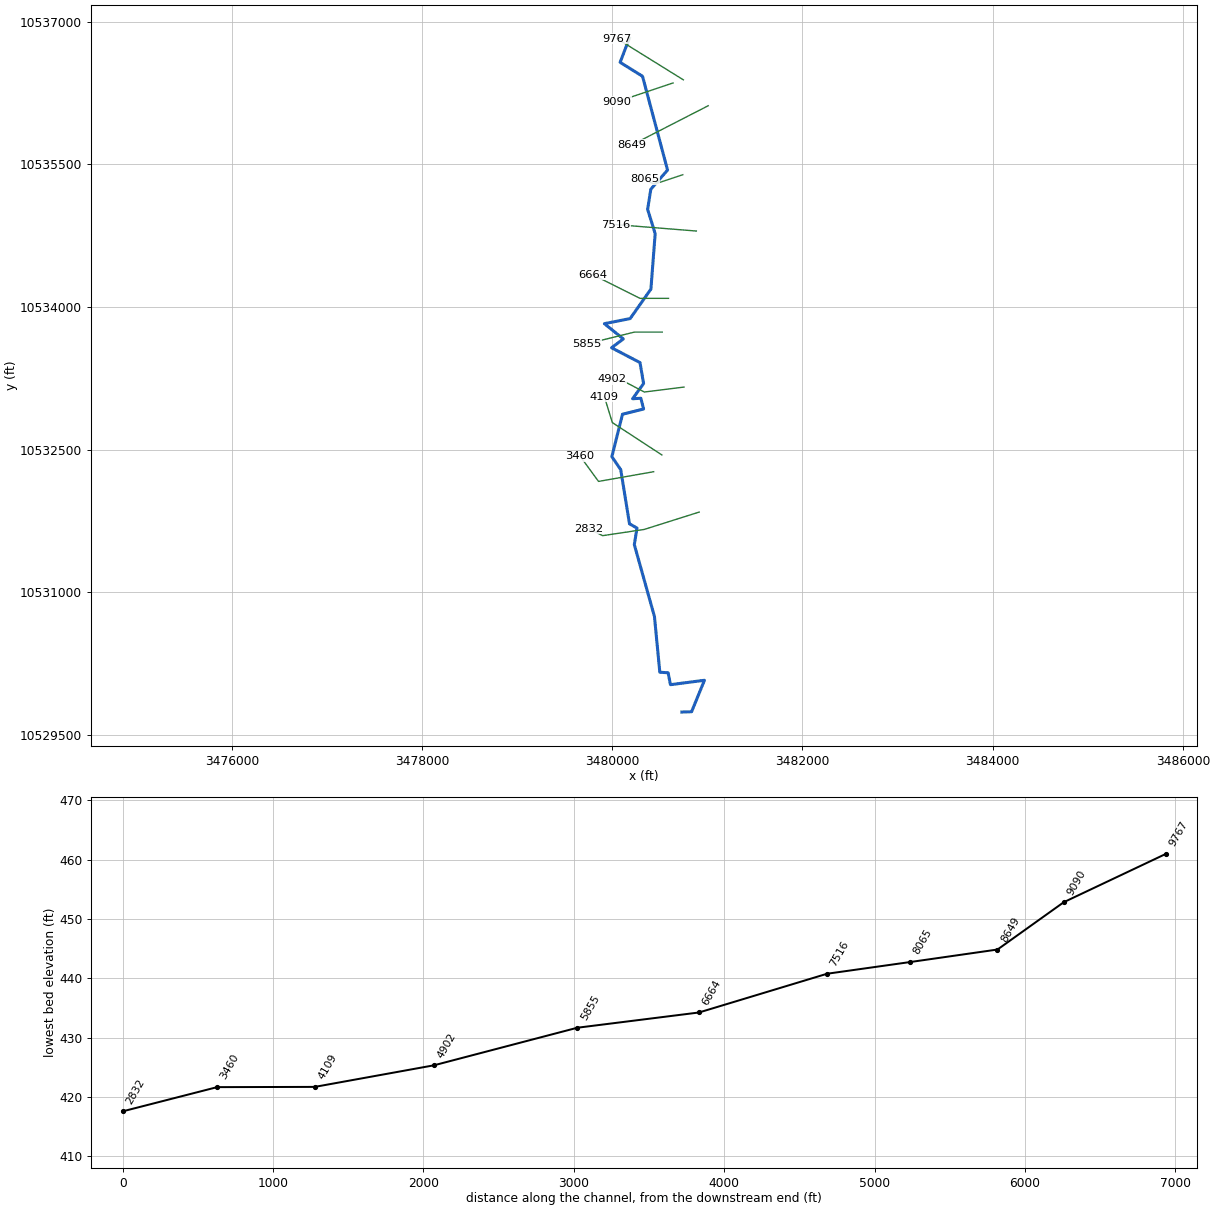
--- UNT0520 IN SAND CR.prj (project) ---

Proj Title=UNT0520 IN SAND CR Base Level Engineering
Current Plan=p01
Default Exp/Contr=0.3,0.1
English Units
Geom File=g01
Flow File=f01
Plan File=p01
Y Axis Title=Elevation
X Axis Title(PF)=Main Channel Distance
X Axis Title(XS)=Station
BEGIN DESCRIPTION:
UNT0520 IN SAND CR
END DESCRIPTION:
DSS Export Rating Curves= 0
DSS Export Rating Curve Sorted= 0
DSS Export Volume Flow Curves= 0
DXF OffsetX= 0
DXF OffsetY= 0
DXF ScaleX= 1
DXF ScaleY= 10

--- UNT0520 IN SAND CR.p01 (plan) ---

Plan Title=Multiple Run
Short Identifier=Multiple
Geom File=g01
Flow File=f01
Subcritical Flow
K Sum by GR= 0
Std Step Tol= 0.01
Critical Tol= 0.01
Num of Std Step Trials= 20
Max Error Tol= 0.3
Flow Tol Ratio= 0.001
Split Flow NTrial= 30
Split Flow Tol= 0.02
Split Flow Ratio= 0.02
Log Output Level= 0
Friction Slope Method= 1
Unsteady Friction Slope Method= 2
Unsteady Bridges Friction Slope Method= 1
Parabolic Critical Depth
Global Vel Dist=  1 , 1 , 1
Global Log Level= 0
CheckData=True
Encroach Param= -1, 0, 0, 0
BEGIN DESCRIPTION:
Multiple Run
END DESCRIPTION:

--- UNT0520 IN SAND CR.f01 (steady flow) ---

Flow Title=Multiple
Number of Profiles=7
Profile Names=10-year,25-year,50-year,1pct_min,100-year,1pct_plu,500-year
River Rch & RM= UNT0520 IN SAND ,Reach-1,9767
     547     718     852     739    1000    1352    1372
Boundary for River Rch & Prof#=UNT0520 IN SAND ,Reach-1,1
Up Type=0
Dn Type=3
Dn Slope=0.005
Boundary for River Rch & Prof#=UNT0520 IN SAND ,Reach-1,2
Up Type=0
Dn Type=3
Dn Slope=0.005
Boundary for River Rch & Prof#=UNT0520 IN SAND ,Reach-1,3
Up Type=0
Dn Type=3
Dn Slope=0.005
Boundary for River Rch & Prof#=UNT0520 IN SAND ,Reach-1,4
Up Type=0
Dn Type=3
Dn Slope=0.005
Boundary for River Rch & Prof#=UNT0520 IN SAND ,Reach-1,5
Up Type=0
Dn Type=3
Dn Slope=0.005
Boundary for River Rch & Prof#=UNT0520 IN SAND ,Reach-1,6
Up Type=0
Dn Type=3
Dn Slope=0.005
Boundary for River Rch & Prof#=UNT0520 IN SAND ,Reach-1,7
Up Type=0
Dn Type=3
Dn Slope=0.005

--- UNT0520 IN SAND CR.g01 (geometry) ---

Geom Title=Existing Conditions
Program Version=4.10

River Reach=UNT0520 IN SAND ,Reach-1
Reach XY= 30
      3480180.18     10536826.35      3480083.33     10536573.36
      3480318.83      10536426.6      3480582.07     10535440.85
      3480406.01     10535239.16      3480372.58     10535027.38
      3480451.84     10534771.42      3480407.05     10534189.04
      3480188.89     10533879.15      3479917.83      10533825.4
      3480117.37     10533664.64      3479993.27      10533572.2
      3480292.38     10533416.22      3480330.01     10533196.05
      3480214.42     10533035.95      3480301.37     10533041.28
        3480330.     10532927.95      3480108.36     10532873.26
      3479996.39     10532426.71      3480089.63     10532290.45
      3480181.83      10531721.1      3480260.47     10531676.23
      3480232.62     10531502.19      3480444.35     10530745.71
       3480500.6     10530160.29      3480587.94     10530154.53
      3480612.51     10530029.41      3480969.98     10530075.72
      3480834.71     10529744.99      3480732.11     10529741.64

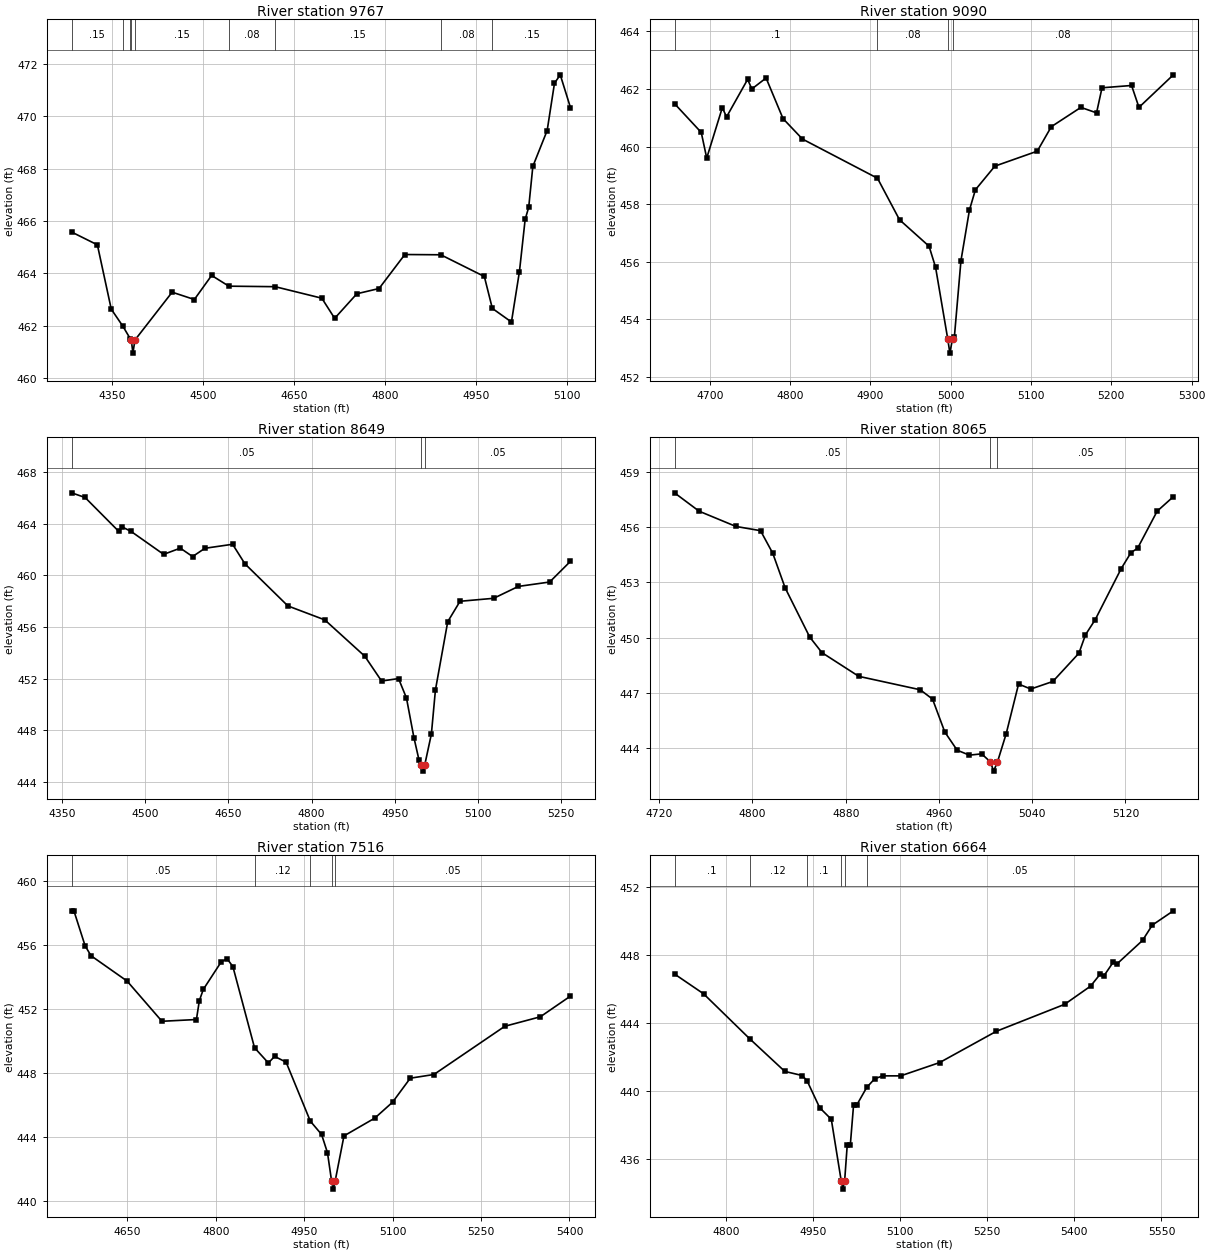
Type RM Length L Ch R = 1 ,9767    ,677,677,677
BEGIN DESCRIPTION:
UNT0520 IN SAND CR 12.1
END DESCRIPTION:
XS GIS Cut Line= 2
      3480748.23     10536389.37      3480049.45      10536823.4
#Sta/Elev= 30
  4283.5  465.58    4326  465.09  4348.9  462.63    4368  461.98  4380.5  461.49
  4381.9  461.45  4384.6  460.95  4387.9  461.45  4449.3  463.28  4485.9     463
  4514.4  463.92  4542.8  463.51  4619.2  463.49  4696.1  463.05  4717.3  462.28
  4753.9  463.22  4790.5  463.42    4833  464.72  4892.3  464.71  4964.1  463.88
  4977.3  462.66  5008.8  462.14    5022  464.07  5031.4  466.06  5037.3  466.53
  5044.1  468.09  5067.7  469.46  5079.8  471.27  5089.3  471.59  5106.1  470.34
#Mann= 9 ,-1 , 0
  4283.5     .15       0    4368      .1       0  4380.5     .15       0
  4381.9     .07       0  4387.9     .15       0  4542.8     .08       0
  4619.2     .15       0  4892.3     .08       0  4977.3     .15       0
Bank Sta=4381.9,4387.9
XS Rating Curve= 0 ,0
Exp/Cntr=0.3,0.1

Type RM Length L Ch R = 1 ,9090    ,441,441,441
BEGIN DESCRIPTION:
UNT0520 IN SAND CR 12.0
END DESCRIPTION:
XS GIS Cut Line= 2
      3480640.12     10536356.74      3480051.51      10536158.8
#Sta/Elev= 30
  4656.2  461.49  4689.5  460.49  4696.3   459.6  4715.7  461.35    4721  461.03
  4747.2  462.33  4752.5     462  4770.2  462.38  4791.3  460.97  4815.5  460.26
  4908.9   458.9  4936.3  457.46  4973.1  456.54  4981.2  455.81  4996.3  453.33
    4999  452.83  5002.3  453.33  5004.6  453.39  5012.8  456.04  5023.4   457.8
  5030.8   458.5    5055  459.32  5107.8  459.84  5125.3  460.69  5162.1  461.36
  5181.6  461.17  5188.4  462.04  5225.2  462.12  5234.4  461.36  5277.2  462.49
#Mann= 4 ,-1 , 0
  4656.2      .1       0  4908.9     .08       0  4996.3     .07       0
  5002.3     .08       0
Bank Sta=4996.3,5002.3
XS Rating Curve= 0 ,0
Exp/Cntr=0.3,0.1

Type RM Length L Ch R = 1 ,8649    ,584,584,584
BEGIN DESCRIPTION:
UNT0520 IN SAND CR 11.0
END DESCRIPTION:
XS GIS Cut Line= 2
       3481009.9     10536117.15      3480208.76     10535706.18
#Sta/Elev= 30
  4366.9  466.38  4391.2  466.02  4452.2  463.39  4457.8  463.75  4474.4  463.39
    4533  461.62  4563.1   462.1  4585.3  461.45  4607.5  462.09  4657.5   462.4
  4679.7  460.89  4757.3  457.63  4823.9  456.55  4896.1  453.74  4926.4  451.82
    4957  452.01  4971.3  450.51  4984.8  447.44  4993.8  445.74  4998.4  445.35
  5001.1  444.85  5004.4  445.35  5016.3  447.72  5023.6  451.13  5045.8  456.41
    5068  457.99  5128.7  458.22  5173.3  459.14  5229.8  459.48  5267.3  461.08
#Mann= 3 ,-1 , 0
  4366.9     .05       0  4998.4    .035       0  5004.4     .05       0
Bank Sta=4998.4,5004.4
XS Rating Curve= 0 ,0
Exp/Cntr=0.3,0.1

Type RM Length L Ch R = 1 ,8065    ,549,549,549
BEGIN DESCRIPTION:
UNT0520 IN SAND CR 9.0
END DESCRIPTION:
XS GIS Cut Line= 3
      3480742.12     10535391.65      3480442.11     10535291.64
      3480342.15     10535341.62
#Sta/Elev= 30
  4733.1  457.88  4754.2  456.88  4785.8  456.05  4806.9  455.82  4817.4  454.59
    4828  452.71  4849.1  450.03  4859.6  449.18  4891.2  447.89  4943.9  447.16
  4954.5  446.65    4965  444.86  4975.6  443.87  4986.1   443.6  4996.6  443.67
  5004.2  443.23  5006.9  442.73  5010.2  443.23  5017.7  444.77  5028.3  447.47
  5038.8   447.2  5057.7  447.61  5080.1  449.15  5085.7  450.15  5094.1  450.98
  5116.4  453.76  5124.8  454.63  5130.4  454.86  5147.2  456.88  5161.1  457.67
#Mann= 3 ,-1 , 0
  4733.1     .05       0  5004.2     .03       0  5010.2     .05       0
Bank Sta=5004.2,5010.2
XS Rating Curve= 0 ,0
Exp/Cntr=0.3,0.1

Type RM Length L Ch R = 1 ,7516    ,852,852,852
BEGIN DESCRIPTION:
UNT0520 IN SAND CR 8.0
END DESCRIPTION:
XS GIS Cut Line= 2
      3480884.93     10534799.43      3480041.14     10534867.15
#Sta/Elev= 30
  4555.2  458.13  4559.1  458.13  4578.1  455.95  4588.1  455.33  4649.3  453.75
  4708.5  451.24    4767  451.35    4772  452.53  4778.7  453.23  4808.8  454.93
  4818.9  455.15  4828.9  454.65  4865.6  449.59  4889.1  448.64  4899.7  449.05
  4919.2  448.69  4960.3  445.01  4979.4  444.18  4989.4  443.04  4996.4  441.27
  4999.2  440.77  5002.4  441.27  5017.4  444.09  5069.7   445.2  5099.8  446.19
  5129.9  447.69    5170  447.92  5290.4  450.93  5350.6  451.52  5401.7  452.81
#Mann= 5 ,-1 , 0
  4555.2     .05       0  4865.6     .12       0  4960.3     .05       0
  4996.4    .035       0  5002.4     .05       0
Bank Sta=4996.4,5002.4
XS Rating Curve= 0 ,0
Exp/Cntr=0.3,0.1

Type RM Length L Ch R = 1 ,6664    ,809,809,809
BEGIN DESCRIPTION:
UNT0520 IN SAND CR 6.0
END DESCRIPTION:
XS GIS Cut Line= 3
      3480592.11     10534091.64      3480292.11     10534091.64
      3479792.12     10534341.63
#Sta/Elev= 30
  4711.5  446.87  4761.5  445.71  4840.9  443.07  4901.5  441.15  4931.5  440.91
  4939.8   440.6  4961.5  439.02  4981.5  438.34  4998.5  434.74  5001.3  434.24
  5004.5  434.74    5009  436.86  5014.3  436.86  5019.9   439.2  5025.5  439.19
  5042.5  440.21  5056.2  440.72  5070.2  440.89  5100.9  440.89    5168  441.67
  5265.9  443.51  5383.3  445.09    5428  446.16  5444.7  446.87  5450.3  446.73
  5467.1  447.57  5472.7  447.44  5517.4  448.84  5534.2  449.74  5570.5  450.58
#Mann= 6 ,-1 , 0
  4711.5      .1       0  4840.9     .12       0  4939.8      .1       0
  4998.5     .07       0  5004.5      .1       0  5042.5     .05       0
Bank Sta=4998.5,5004.5
XS Rating Curve= 0 ,0
Exp/Cntr=0.3,0.1

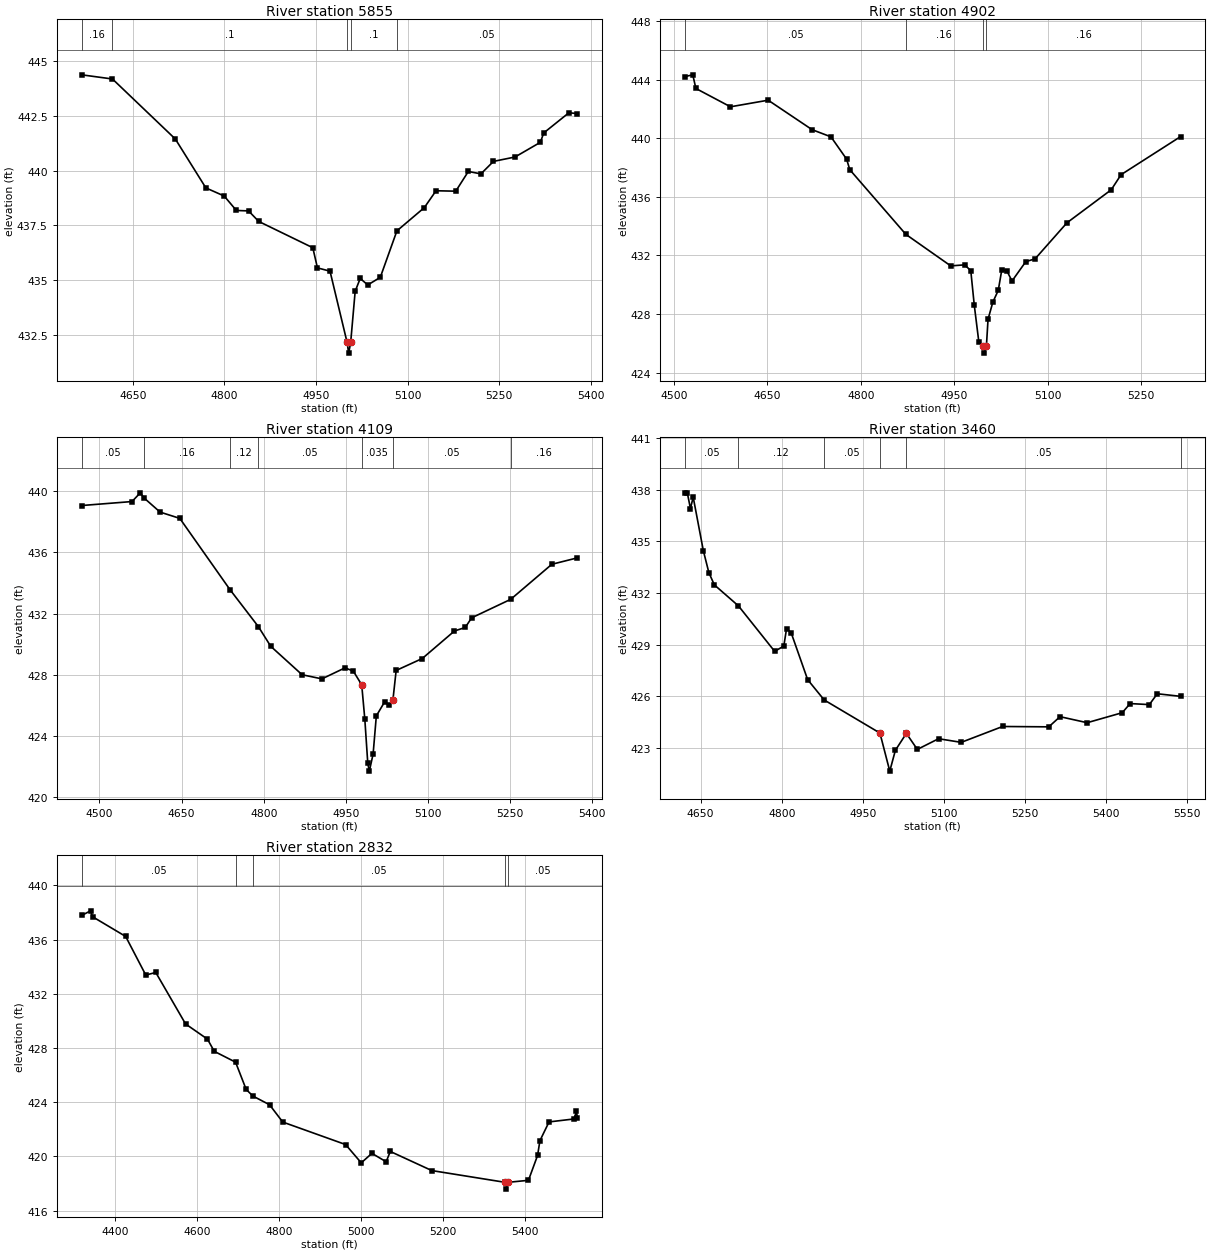
Type RM Length L Ch R = 1 ,5855    ,953,953,953
BEGIN DESCRIPTION:
UNT0520 IN SAND CR 4.0
END DESCRIPTION:
XS GIS Cut Line= 3
       3480525.5     10533736.94      3480233.85     10533736.94
      3479728.63     10533611.94
#Sta/Elev= 30
  4566.2  444.37  4616.6  444.18  4719.6  441.44  4769.6  439.21  4799.6  438.84
  4819.6  438.18  4839.6  438.16  4856.2  437.68  4944.8  436.48  4952.4  435.56
    4973  435.41  5000.9  432.17  5003.6  431.67  5006.9  432.17  5014.2  434.49
  5022.5  435.08  5034.8  434.78  5055.4  435.13  5082.6  437.25  5127.5  438.31
  5146.7  439.08    5179  439.06  5199.6  439.96  5220.2  439.85  5240.8  440.42
  5276.1  440.62  5317.6  441.29  5323.2  441.72  5364.4  442.64  5378.3   442.6
#Mann= 5 ,-1 , 0
  4566.2     .16       0  4616.6      .1       0  5000.9     .07       0
  5006.9      .1       0  5082.6     .05       0
Bank Sta=5000.9,5006.9
XS Rating Curve= 0 ,0
Exp/Cntr=0.3,0.1

Type RM Length L Ch R = 1 ,4902    ,793,793,793
BEGIN DESCRIPTION:
UNT0520 IN SAND CR 2.0
END DESCRIPTION:
XS GIS Cut Line= 4
      3480754.67     10533158.81      3480338.01     10533106.73
      3480119.26     10533221.31      3479992.12     10533241.64
#Sta/Elev= 30
  4517.9   444.2  4530.5  444.32  4535.5  443.39    4591  442.14  4651.5  442.59
    4722  440.58  4752.3  440.09  4777.4  438.57  4782.5  437.85  4872.5  433.44
  4944.5  431.29    4967  431.36  4976.7  430.96  4982.3  428.61  4989.6  426.11
  4995.8  425.84  4998.5  425.34  5001.8  425.84  5004.4  427.65  5012.2  428.83
  5020.8  429.62  5026.5  431.03  5034.8  430.93  5042.9  430.26    5065  431.58
  5079.9  431.77  5131.1  434.23  5202.1  436.48  5217.9  437.51  5313.5  440.11
#Mann= 4 ,-1 , 0
  4517.9     .05       0  4872.5     .16       0  4995.8     .07       0
  5001.8     .16       0
Bank Sta=4995.8,5001.8
XS Rating Curve= 0 ,0
Exp/Cntr=0.3,0.1

Type RM Length L Ch R = 1 ,4109    ,649,649,649
BEGIN DESCRIPTION:
UNT0520 IN SAND CR 1.0
END DESCRIPTION:
XS GIS Cut Line= 3
      3480522.14     10532445.15      3480001.32     10532785.42
      3479917.98     10533056.27
#Sta/Elev= 30
  4467.5  439.06  4559.4  439.32  4574.5  439.89  4581.2  439.56  4610.7  438.63
  4646.7  438.22  4738.2  433.57  4790.1  431.15  4812.8  429.86  4870.1     428
  4906.3  427.73  4948.5  428.45  4963.6  428.24    4979  427.34  4984.7  425.08
  4990.1   422.2  4992.9   421.7  4999.8  422.81  5005.7  425.31  5020.9  426.23
    5029     426    5036  426.35  5041.9  428.28  5089.6  429.06  5148.4  430.86
  5168.1  431.09  5179.8  431.72  5251.2  432.93  5326.3  435.22    5373  435.64
#Mann= 7 ,-1 , 0
  4467.5     .05       0  4581.2     .16       0  4738.2     .12       0
  4790.1     .05       0    4979    .035       0    5036     .05       0
  5251.2     .16       0
Bank Sta=4979,5036
XS Rating Curve= 0 ,0
Exp/Cntr=0.3,0.1

Type RM Length L Ch R = 1 ,3460    ,628,628,628
BEGIN DESCRIPTION:
UNT0520 IN SAND CR 1.011
END DESCRIPTION:
XS GIS Cut Line= 3
      3480435.73     10532268.66      3479856.28     10532166.66
      3479662.27     10532432.43
#Sta/Elev= 30
  4620.9  437.81  4625.3  437.81  4631.1   436.9  4636.2  437.56    4655  434.45
  4665.2  433.18  4675.3  432.47  4719.9  431.25    4787  428.61  4803.9  428.92
    4809  429.93  4817.5  429.69    4848  426.97  4878.6  425.79  4981.8  423.87
    5000  421.66  5010.4  422.87  5030.7  423.85    5051  422.92  5090.3  423.54
  5132.3  423.33  5208.8  424.25  5294.3  424.23  5315.1  424.82  5365.3  424.47
  5430.2  425.05  5444.9  425.58  5480.4  425.52  5495.1  426.15  5538.3     426
#Mann= 6 ,-1 , 0
  4620.9     .05       0  4719.9     .12       0  4878.6     .05       0
  4981.8     .03       0  5030.7     .05       0  5538.3     .05       0
Bank Sta=4981.8,5030.7
XS Rating Curve= 0 ,0
Exp/Cntr=0.3,0.1

Type RM Length L Ch R = 1 ,2832    ,0,0,0
BEGIN DESCRIPTION:
FROST CREEK 11.0
END DESCRIPTION:
XS GIS Cut Line= 4
      3480914.25     10531844.18      3480336.56     10531661.75
      3479899.18     10531596.26      3479756.78     10531668.64
#Sta/Elev= 30
  4319.6  437.78  4341.1  438.12  4346.3  437.68  4426.7  436.23  4475.7  433.38
  4500.1  433.57  4572.7  429.77    4626  428.65  4642.6  427.75  4694.5  426.95
  4720.3  424.94  4736.7  424.45  4777.2  423.81  4809.5  422.53  4962.6  420.87
  5000.7  419.52  5026.7  420.22  5061.4   419.6  5071.5  420.36  5172.6  418.95
  5351.6  418.08  5354.3  417.58  5357.6  418.08  5408.1  418.23  5430.4  420.07
    5436  421.15  5458.3  422.54  5519.4  422.76    5525  423.32  5527.4  422.85
#Mann= 5 ,-1 , 0
  4319.6     .05       0  4694.5     .16       0  4736.7     .05       0
  5351.6    .035       0  5357.6     .05       0
Bank Sta=5351.6,5357.6
XS Rating Curve= 0 ,0
Exp/Cntr=0.3,0.1

Chan Stop Cuts=-1
Use User Specified Reach Order=0
Composite Channel Slope=5