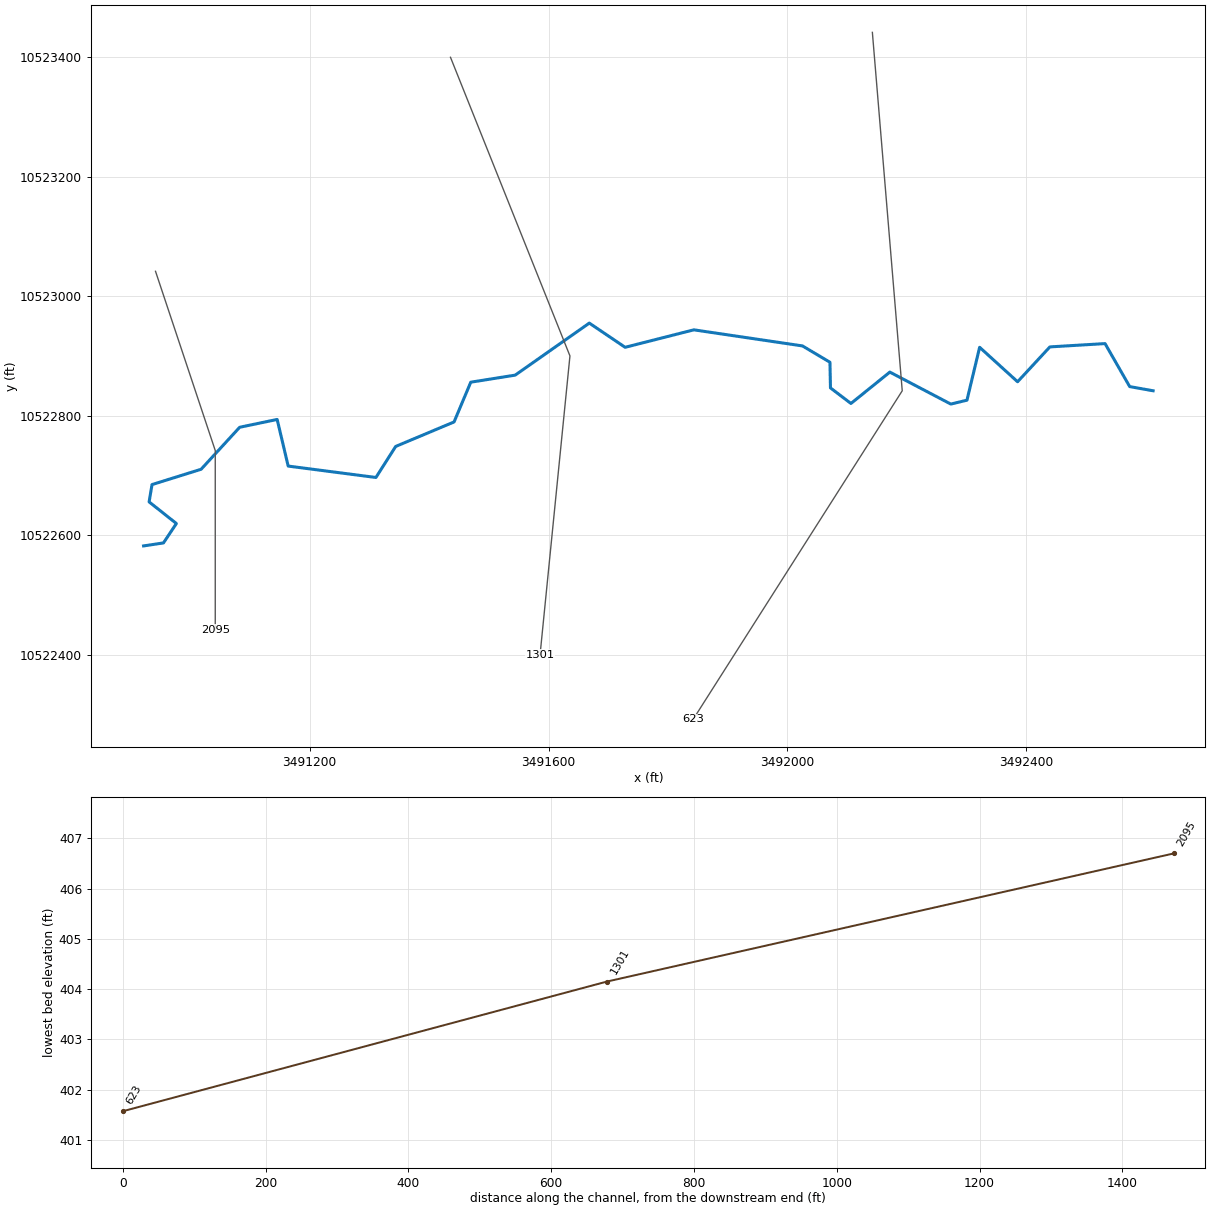
--- UNT0533 IN SAND CR.prj (project) ---

Proj Title=UNT0533 IN SAND CR Base Level Engineering
Current Plan=p01
Default Exp/Contr=0.3,0.1
English Units
Geom File=g01
Flow File=f01
Plan File=p01
BEGIN DESCRIPTION:
UNT0533 IN SAND CR
END DESCRIPTION:

--- UNT0533 IN SAND CR.p01 (plan) ---

Plan Title=Multiple Run
Short Identifier=Multiple
Geom File=g01
Flow File=f01
Subcritical Flow
K Sum by GR= 0
Std Step Tol= 0.01
Critical Tol= 0.01
Num of Std Step Trials= 20
Max Error Tol= 0.3
Flow Tol Ratio= 0.001
Split Flow NTrial= 30
Split Flow Tol= 0.02
Split Flow Ratio= 0.02
Log Output Level= 0
Friction Slope Method= 1
Unsteady Friction Slope Method= 2
Unsteady Bridges Friction Slope Method= 1
Parabolic Critical Depth
Global Vel Dist=  1 , 1 , 1
Global Log Level= 0
CheckData=True
Encroach Param= -1, 0, 0, 0
BEGIN DESCRIPTION:
Multiple Run
END DESCRIPTION:

--- UNT0533 IN SAND CR.f01 (steady flow) ---

Flow Title=Multiple
Number of Profiles=7
Profile Names=10-year,25-year,50-year,1pct_min,100-year,1pct_plu,500-year
River Rch & RM= UNT0533 IN SAND ,Reach-1,2095
     589     780     933     815    1102    1491    1534
Boundary for River Rch & Prof#=UNT0533 IN SAND ,Reach-1,1
Up Type=0
Dn Type=3
Dn Slope=0.005
Boundary for River Rch & Prof#=UNT0533 IN SAND ,Reach-1,2
Up Type=0
Dn Type=3
Dn Slope=0.005
Boundary for River Rch & Prof#=UNT0533 IN SAND ,Reach-1,3
Up Type=0
Dn Type=3
Dn Slope=0.005
Boundary for River Rch & Prof#=UNT0533 IN SAND ,Reach-1,4
Up Type=0
Dn Type=3
Dn Slope=0.005
Boundary for River Rch & Prof#=UNT0533 IN SAND ,Reach-1,5
Up Type=0
Dn Type=3
Dn Slope=0.005
Boundary for River Rch & Prof#=UNT0533 IN SAND ,Reach-1,6
Up Type=0
Dn Type=3
Dn Slope=0.005
Boundary for River Rch & Prof#=UNT0533 IN SAND ,Reach-1,7
Up Type=0
Dn Type=3
Dn Slope=0.005

--- UNT0533 IN SAND CR.g01 (geometry) ---

Geom Title=Existing Conditions

River Reach=UNT0533 IN SAND ,Reach-1
Reach XY= 30
      3490922.11     10522581.96      3490955.37     10522586.94
      3490977.02     10522619.45      3490931.39     10522655.65
      3490936.26     10522684.62      3491018.43     10522710.27
      3491082.99     10522780.55      3491145.73     10522793.67
      3491164.20     10522715.59      3491311.09     10522696.51
      3491344.15     10522748.47      3491441.86     10522789.45
      3491469.83     10522856.03      3491544.20     10522867.84
      3491668.27     10522954.94      3491728.25     10522914.43
      3491843.24     10522943.66      3492025.09     10522916.75
      3492071.10     10522889.40      3492071.97     10522846.43
      3492106.26     10522820.39      3492171.36     10522872.91
      3492273.41     10522819.38      3492300.45     10522825.90
      3492321.67     10522914.44      3492385.20     10522856.73
      3492439.26     10522915.11      3492531.63     10522920.62
      3492572.87     10522848.65      3492612.11     10522841.64

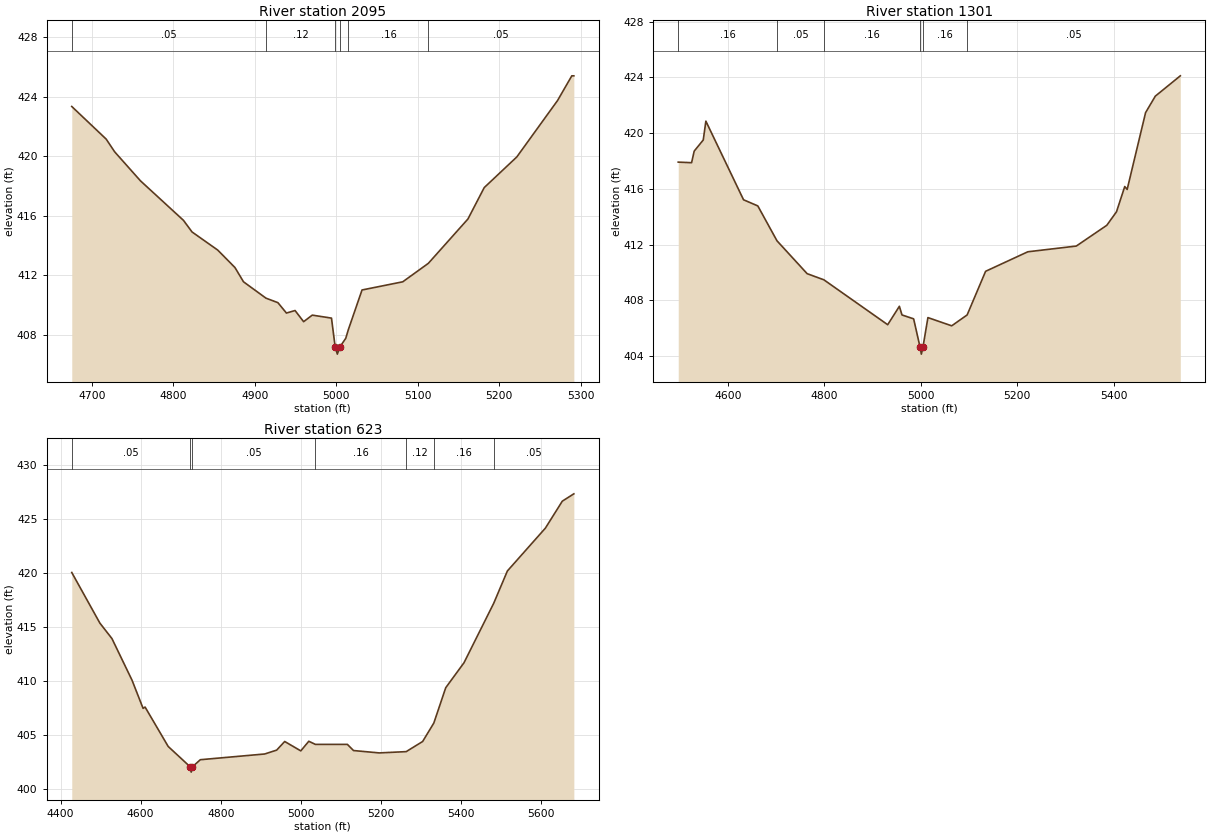
Type RM Length L Ch R = 1,2095,794,794,794
BEGIN DESCRIPTION:
UNT0533 IN SAND CR 4.0
END DESCRIPTION:
XS GIS Cut Line= 3
      3490942.10     10523041.66      3491042.11     10522741.64
      3491042.11     10522441.59
#Sta/Elev= 30
  4675.3  423.34  4717.5  421.15  4728.0  420.29  4759.7  418.34  4812.4  415.69
  4822.9  414.91  4854.5  413.69  4875.6  412.52  4886.1  411.56  4913.7  410.46
  4928.3  410.16  4938.8  409.46  4949.4  409.63  4959.9  408.88  4970.5  409.32
  4994.1  409.12  4998.6  407.20  5001.3  406.70  5004.6  407.20  5011.6  407.76
  5014.9  408.36  5031.6  411.01  5081.6  411.56  5113.0  412.80  5161.6  415.78
  5181.6  417.89  5221.6  419.95  5271.6  423.74  5289.1  425.40  5291.6  425.40
#Mann=6,-1,0
  4675.3    0.05       0  4913.7    0.12       0  4998.6    0.07       0
  5004.6    0.12       0  5014.9    0.16       0  5113.0    0.05       0
Bank Sta=4998.6,5004.6
Exp/Cntr=0.3,0.1

Type RM Length L Ch R = 1,1301,678,678,678
BEGIN DESCRIPTION:
UNT0533 IN SAND CR 2.0
END DESCRIPTION:
XS GIS Cut Line= 3
      3491435.87     10523399.94      3491635.86     10522899.98
      3491585.85     10522399.95
#Sta/Elev= 30
  4497.2  417.92  4524.9  417.88  4530.3  418.71  4549.1  419.51  4554.5  420.86
  4632.6  415.22  4662.2  414.78  4701.9  412.28  4764.5  409.92  4799.2  409.48
  4931.5  406.26  4955.7  407.58  4961.1  406.96  4985.3  406.68  4998.6  404.65
  5001.3  404.15  5004.6  404.65  5014.9  406.77  5064.2  406.18  5096.2  406.96
  5134.5  410.09  5222.0  411.49  5322.5  411.90  5385.8  413.39  5405.9  414.36
  5423.0  416.17  5428.0  415.96  5466.2  421.47  5486.3  422.65  5538.2  424.11
#Mann=6,-1,0
  4497.2    0.16       0  4701.9    0.05       0  4799.2    0.16       0
  4998.6    0.07       0  5004.6    0.16       0  5096.2    0.05       0
Bank Sta=4998.6,5004.6
Exp/Cntr=0.3,0.1

Type RM Length L Ch R = 1,623,0,0,0
BEGIN DESCRIPTION:
UNT0533 IN SAND CR 1.0
END DESCRIPTION:
XS GIS Cut Line= 3
      3492142.11     10523441.63      3492192.11     10522841.64
      3491842.10     10522291.63
#Sta/Elev= 30
  4427.9  420.07  4498.1  415.38  4528.2  413.95  4578.4  410.09  4606.0  407.48
  4611.0  407.60  4668.7  403.95  4723.4  402.07  4726.2  401.57  4729.4  402.07
  4749.0  402.72  4909.6  403.25  4939.7  403.61  4959.7  404.41  4999.9  403.54
  5019.9  404.43  5036.4  404.14  5116.3  404.14  5131.6  403.57  5195.9  403.35
  5263.2  403.47  5304.3  404.41  5332.2  406.12  5361.9  409.39  5407.6  411.71
  5481.7  417.21  5515.9  420.21  5610.8  424.18  5653.1  426.68  5681.9  427.36
#Mann=7,-1,0
  4427.9    0.05       0  4723.4   0.035       0  4729.4    0.05       0
  5036.4    0.16       0  5263.2    0.12       0  5332.2    0.16       0
  5481.7    0.05       0
Bank Sta=4723.4,4729.4
Exp/Cntr=0.3,0.1

Chan Stop Cuts=-1