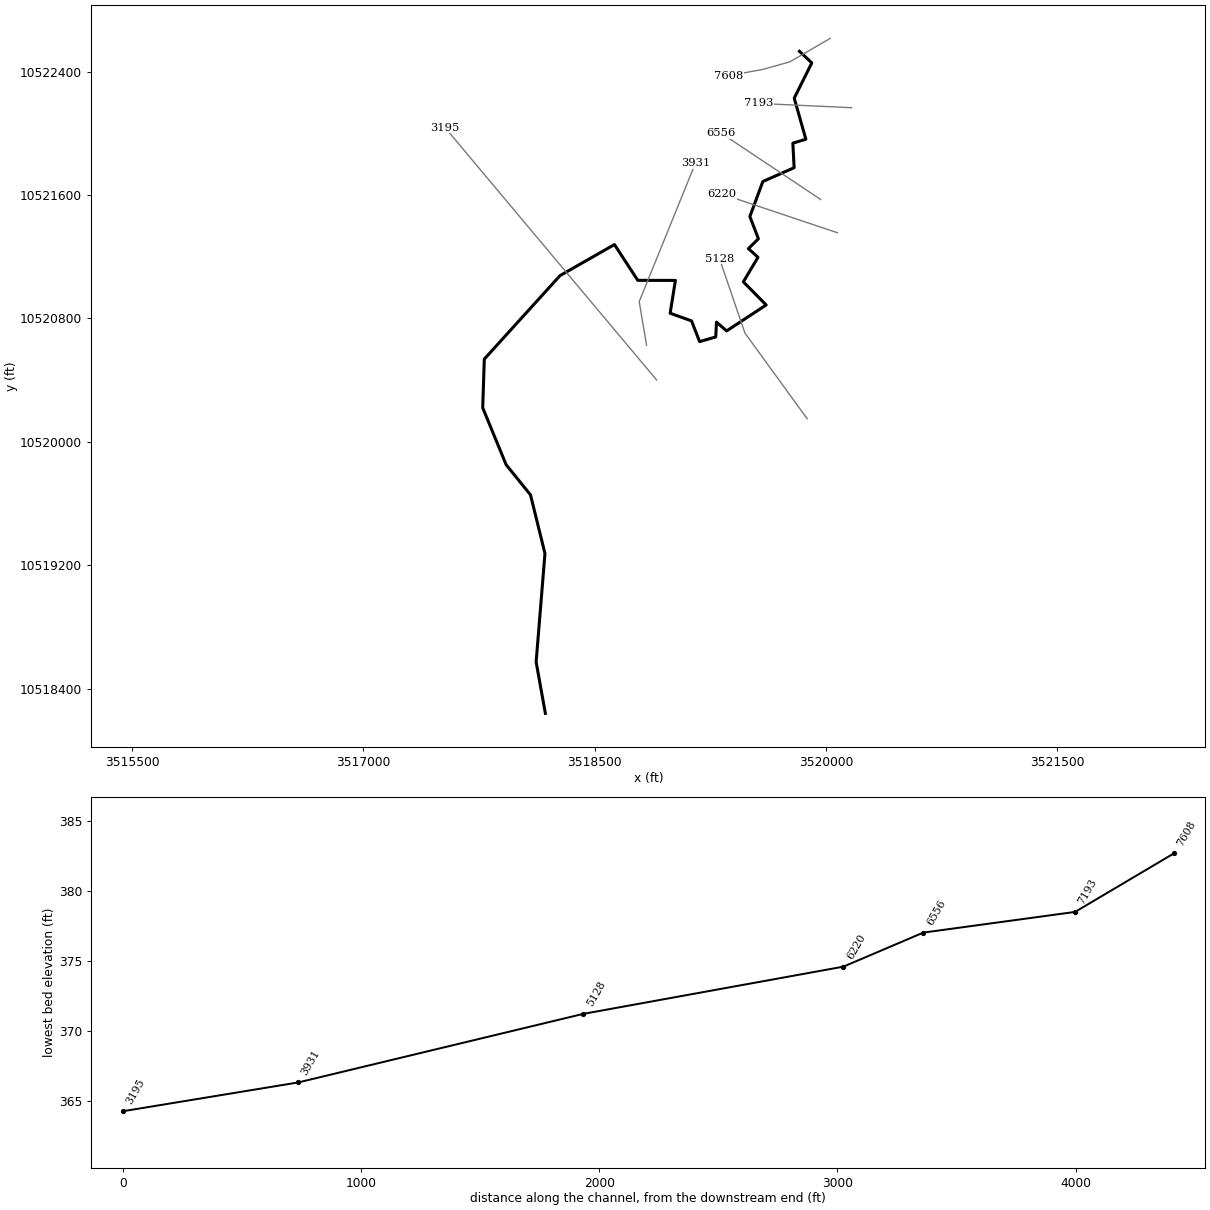
--- UNT0554 IN SAND CR.prj (project) ---

Proj Title=UNT0554 IN SAND CR Base Level Engineering
Current Plan=p01
Default Exp/Contr=0.3,0.1
English Units
Geom File=g01
Flow File=f01
Plan File=p01
BEGIN DESCRIPTION:
UNT0554 IN SAND CR
END DESCRIPTION:

--- UNT0554 IN SAND CR.p01 (plan) ---

Plan Title=Multiple Run
Short Identifier=Multiple
Geom File=g01
Flow File=f01
Subcritical Flow
K Sum by GR= 0
Std Step Tol= 0.01
Critical Tol= 0.01
Num of Std Step Trials= 20
Max Error Tol= 0.3
Flow Tol Ratio= 0.001
Split Flow NTrial= 30
Split Flow Tol= 0.02
Split Flow Ratio= 0.02
Log Output Level= 0
Friction Slope Method= 1
Unsteady Friction Slope Method= 2
Unsteady Bridges Friction Slope Method= 1
Parabolic Critical Depth
Global Vel Dist=  1 , 1 , 1
Global Log Level= 0
CheckData=True
Encroach Param= -1, 0, 0, 0
BEGIN DESCRIPTION:
Multiple Run
END DESCRIPTION:

--- UNT0554 IN SAND CR.f01 (steady flow) ---

Flow Title=Multiple
Number of Profiles=7
Profile Names=10-year,25-year,50-year,1pct_min,100-year,1pct_plu,500-year
River Rch & RM= UNT0554 IN SAND ,Reach-1,7608
     914    1245    1515    1345    1819    2460    2614
Boundary for River Rch & Prof#=UNT0554 IN SAND ,Reach-1,1
Up Type=0
Dn Type=3
Dn Slope=0.005
Boundary for River Rch & Prof#=UNT0554 IN SAND ,Reach-1,2
Up Type=0
Dn Type=3
Dn Slope=0.005
Boundary for River Rch & Prof#=UNT0554 IN SAND ,Reach-1,3
Up Type=0
Dn Type=3
Dn Slope=0.005
Boundary for River Rch & Prof#=UNT0554 IN SAND ,Reach-1,4
Up Type=0
Dn Type=3
Dn Slope=0.005
Boundary for River Rch & Prof#=UNT0554 IN SAND ,Reach-1,5
Up Type=0
Dn Type=3
Dn Slope=0.005
Boundary for River Rch & Prof#=UNT0554 IN SAND ,Reach-1,6
Up Type=0
Dn Type=3
Dn Slope=0.005
Boundary for River Rch & Prof#=UNT0554 IN SAND ,Reach-1,7
Up Type=0
Dn Type=3
Dn Slope=0.005

--- UNT0554 IN SAND CR.g01 (geometry) ---

Geom Title=Existing Conditions

River Reach=UNT0554 IN SAND ,Reach-1
Reach XY= 30
      3519827.70     10522532.14      3519907.81     10522457.09
      3519793.83     10522228.44      3519869.25     10521962.27
      3519784.88     10521936.50      3519793.24     10521777.50
      3519590.33     10521687.91      3519506.18     10521461.05
      3519561.63     10521316.79      3519496.86     10521252.88
      3519558.88     10521196.60      3519464.05     10521037.58
      3519611.94     10520887.43      3519355.41     10520719.32
      3519289.70     10520776.38      3519285.07     10520680.28
      3519180.42     10520649.79      3519128.04     10520784.23
      3518989.35     10520834.01      3519023.40     10521046.67
      3518779.47     10521047.23      3518628.30     10521279.20
      3518275.43     10521078.08      3517784.34     10520536.50
      3517774.05     10520220.83      3517925.96     10519851.91
      3518083.95     10519656.16      3518177.70     10519275.96
      3518120.41     10518572.83      3518180.31     10518239.56

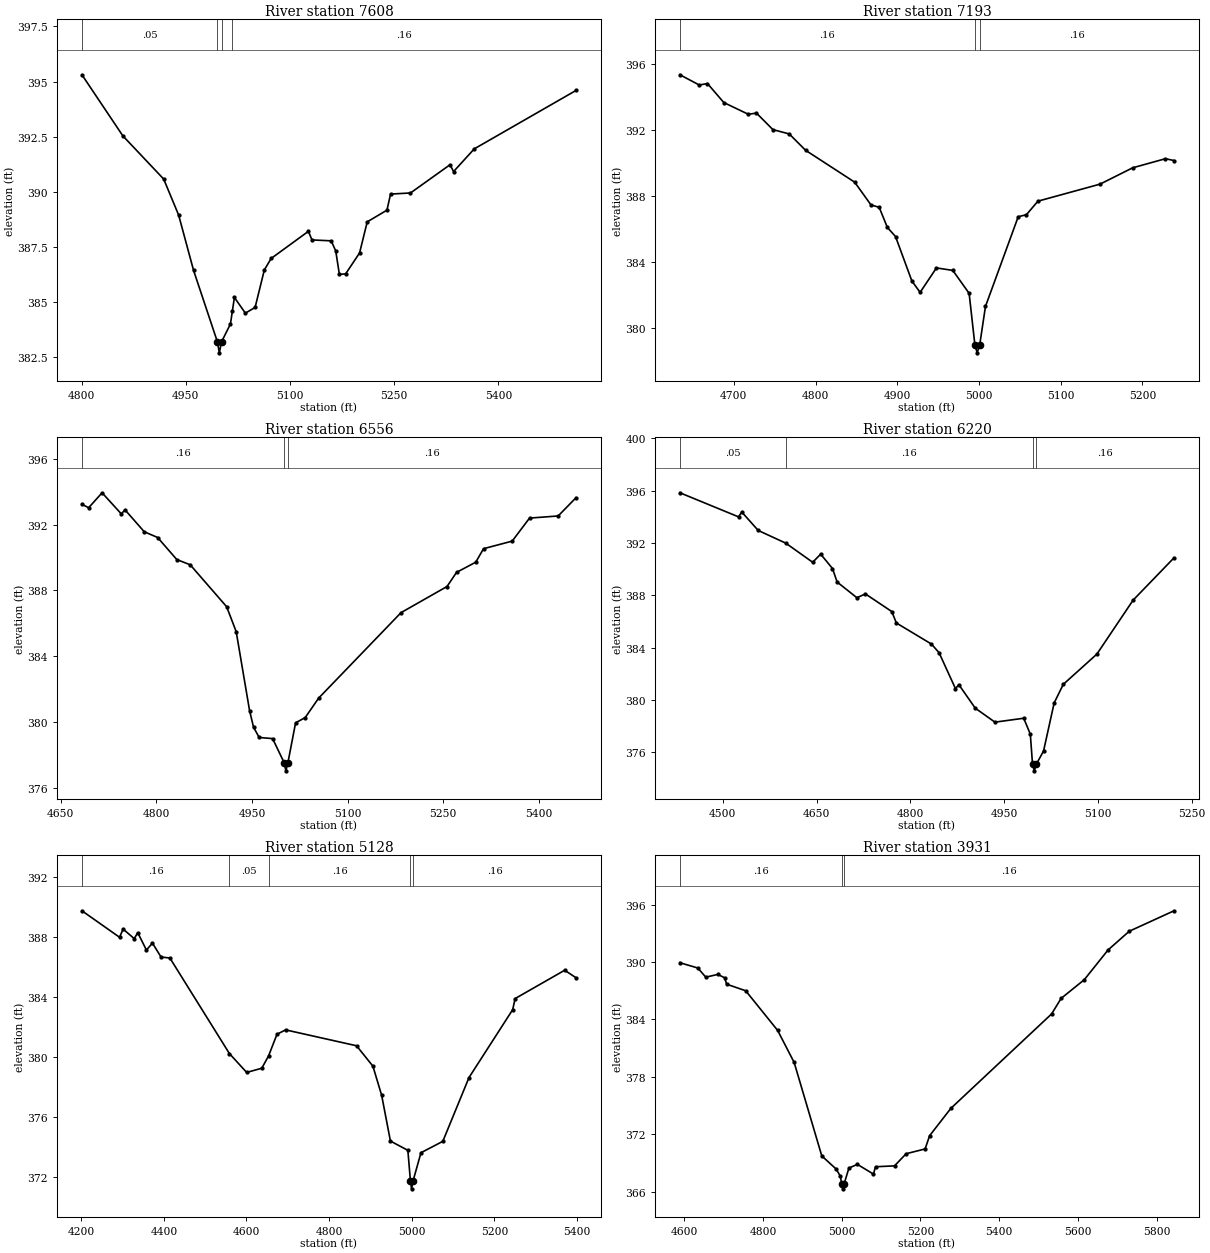
Type RM Length L Ch R = 1,7608,415,415,415
BEGIN DESCRIPTION:
UNT0554 IN SAND CR 11.0
END DESCRIPTION:
XS GIS Cut Line= 4
      3520027.81     10522616.29      3519763.50     10522463.08
      3519590.33     10522414.91      3519368.07     10522373.65
#Sta/Elev= 30
  4800.5  395.31  4859.4  392.54  4918.2  390.58  4939.7  388.95  4961.2  386.44
  4995.5  383.20  4998.3  382.70  5001.5  383.20  5014.3  384.01  5017.2  384.62
  5020.0  385.21  5035.8  384.50  5049.8  384.76  5063.1  386.46  5072.9  386.98
  5126.5  388.21  5131.7  387.82  5159.3  387.78  5165.9  387.32  5171.1  386.26
  5180.1  386.28  5200.2  387.23  5211.2  388.64  5239.6  389.17  5244.8  389.90
  5273.5  389.95  5330.4  391.23  5335.5  390.92  5365.3  391.95  5511.8  394.60
#Mann=4,-1,0
  4800.5    0.05       0  4995.5   0.035       0  5001.5    0.05       0
  5017.2    0.16       0
Bank Sta=4995.5,5001.5
Exp/Cntr=0.3,0.1

Type RM Length L Ch R = 1,7193,637,637,637
BEGIN DESCRIPTION:
UNT0554 IN SAND CR 11.1
END DESCRIPTION:
XS GIS Cut Line= 2
      3520165.75     10522166.56      3519561.59     10522194.33
#Sta/Elev= 30
  4634.0  395.34  4657.7  394.72  4667.7  394.81  4687.7  393.66  4717.7  392.95
  4727.7  393.02  4747.8  392.02  4767.8  391.76  4787.8  390.77  4847.9  388.84
  4867.9  387.46  4877.9  387.32  4887.9  386.10  4897.9  385.55  4917.9  382.86
  4928.0  382.17  4948.0  383.65  4968.0  383.50  4988.0  382.11  4995.0  379.01
  4997.8  378.51  5001.0  379.01  5008.0  381.32  5048.1  386.75  5058.1  386.87
  5072.2  387.69  5148.2  388.72  5188.2  389.71  5228.3  390.26  5238.8  390.15
#Mann=3,-1,0
  4634.0    0.16       0  4995.0    0.07       0  5001.0    0.16       0
Bank Sta=4995,5001
Exp/Cntr=0.3,0.1

Type RM Length L Ch R = 1,6556,336,336,336
BEGIN DESCRIPTION:
UNT0554 IN SAND CR 10.0
END DESCRIPTION:
XS GIS Cut Line= 2
      3519966.05     10521570.92      3519321.46     10522000.64
#Sta/Elev= 30
  4683.4  393.24  4693.9  393.03  4715.0  393.94  4745.0  392.66  4751.0  392.90
  4781.1  391.57  4802.1  391.22  4832.1  389.88  4853.2  389.56  4910.3  387.01
  4925.3  385.49  4946.3  380.68  4952.5  379.68  4961.3  379.06  4982.4  378.99
  5000.4  377.53  5003.2  377.03  5006.4  377.53  5018.4  379.95  5033.5  380.27
  5054.5  381.45  5183.7  386.65  5255.8  388.24  5270.8  389.10  5300.9  389.72
  5313.1  390.54  5358.0  391.00  5385.2  392.40  5430.1  392.53  5458.1  393.64
#Mann=3,-1,0
  4683.4    0.16       0  5000.4    0.07       0  5006.4    0.16       0
Bank Sta=5000.4,5006.4
Exp/Cntr=0.3,0.1

Type RM Length L Ch R = 1,6220,1092,1092,1092
BEGIN DESCRIPTION:
UNT0554 IN SAND CR 8.0
END DESCRIPTION:
XS GIS Cut Line= 2
      3520073.42     10521356.03      3519324.21     10521607.21
#Sta/Elev= 30
  4431.5  395.84  4525.2  394.00  4530.4  394.37  4556.7  392.96  4600.8  391.99
  4643.8  390.53  4656.6  391.15  4675.5  390.05  4682.9  389.02  4714.5  387.82
  4728.2  388.11  4770.4  386.76  4777.6  385.89  4833.7  384.28  4845.9  383.62
  4872.2  380.87  4877.5  381.18  4903.8  379.38  4935.3  378.31  4981.3  378.61
  4991.9  377.39  4995.4  375.09  4998.2  374.59  5001.4  375.09  5013.0  376.10
  5030.0  379.78  5044.6  381.20  5098.3  383.51  5156.2  387.63  5221.7  390.87
#Mann=4,-1,0
  4431.5    0.05       0  4600.8    0.16       0  4995.4    0.07       0
  5001.4    0.16       0
Bank Sta=4995.4,5001.4
Exp/Cntr=0.3,0.1

Type RM Length L Ch R = 1,5128,1197,1197,1197
BEGIN DESCRIPTION:
UNT0554 IN SAND CR 7.0
END DESCRIPTION:
XS GIS Cut Line= 3
      3519878.08     10520149.46      3519474.46     10520704.99
      3519309.56     10521186.67
#Sta/Elev= 30
  4201.8  389.77  4292.9  388.00  4301.4  388.55  4328.4  387.91  4336.9  388.31
  4357.8  387.15  4372.5  387.61  4393.3  386.68  4414.6  386.62  4558.7  380.24
  4600.5  378.98  4637.1  379.26  4653.6  380.09  4673.9  381.53  4694.8  381.82
  4866.4  380.76  4906.0  379.40  4927.2  377.45  4948.4  374.40  4990.6  373.78
  4996.9  371.71  4999.6  371.21  5002.9  371.71  5022.3  373.62  5075.2  374.38
  5138.6  378.64  5244.3  383.17  5250.2  383.91  5370.1  385.80  5397.6  385.30
#Mann=5,-1,0
  4201.8    0.16       0  4558.7    0.05       0  4653.6    0.16       0
  4996.9    0.07       0  5002.9    0.16       0
Bank Sta=4996.9,5002.9
Exp/Cntr=0.3,0.1

Type RM Length L Ch R = 1,3931,736,736,736
BEGIN DESCRIPTION:
UNT0554 IN SAND CR 5.0
END DESCRIPTION:
XS GIS Cut Line= 3
      3518836.43     10520626.90      3518788.69     10520908.99
      3519153.13     10521807.06
#Sta/Elev= 30
  4588.9  389.93  4634.3  389.38  4654.6  388.42  4685.0  388.71  4702.5  388.36
  4707.5  387.69  4756.0  387.00  4837.1  382.86  4879.1  379.51  4949.3  369.74
  4985.8  368.37  4996.6  367.61  4999.9  366.80  5002.6  366.30  5005.9  366.80
  5018.2  368.47  5039.7  368.86  5080.5  367.84  5085.9  368.61  5134.1  368.70
  5163.6  369.97  5211.8  370.47  5223.2  371.85  5277.2  374.71  5533.2  384.58
  5557.3  386.20  5616.3  388.16  5676.5  391.26  5730.4  393.22  5844.2  395.36
#Mann=3,-1,0
  4588.9    0.16       0  4999.9    0.07       0  5005.9    0.16       0
Bank Sta=4999.9,5005.9
Exp/Cntr=0.3,0.1

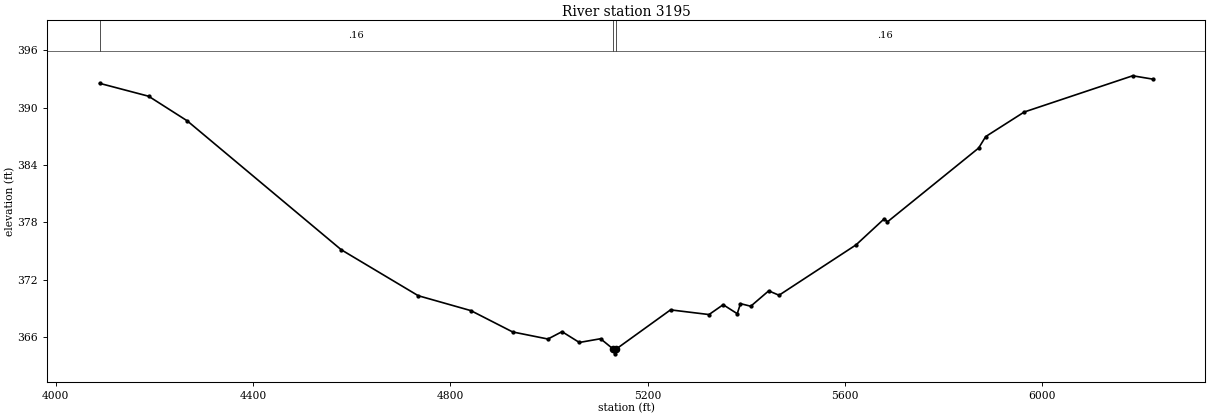
Type RM Length L Ch R = 1,3195,0,0,0
BEGIN DESCRIPTION:
UNT0554 IN SAND CR 1.0
END DESCRIPTION:
XS GIS Cut Line= 2
      3518901.51     10520401.21      3517530.35     10522037.05
#Sta/Elev= 30
  4089.2  392.54  4188.5  391.19  4266.6  388.62  4578.9  375.13  4735.0  370.32
  4841.7  368.76  4926.3  366.53  4997.8  365.79  5026.4  366.56  5061.5  365.43
  5104.5  365.82  5130.1  364.74  5132.8  364.24  5136.1  364.74  5246.3  368.84
  5324.3  368.35  5353.0  369.38  5381.5  368.44  5388.1  369.49  5408.9  369.22
  5445.3  370.83  5466.2  370.37  5622.3  375.64  5679.5  378.37  5686.0  378.05
  5870.8  385.77  5885.1  386.97  5963.2  389.54  6183.0  393.33  6223.7  392.98
#Mann=3,-1,0
  4089.2    0.16       0  5130.1    0.07       0  5136.1    0.16       0
Bank Sta=5130.1,5136.1
Exp/Cntr=0.3,0.1

Chan Stop Cuts=-1