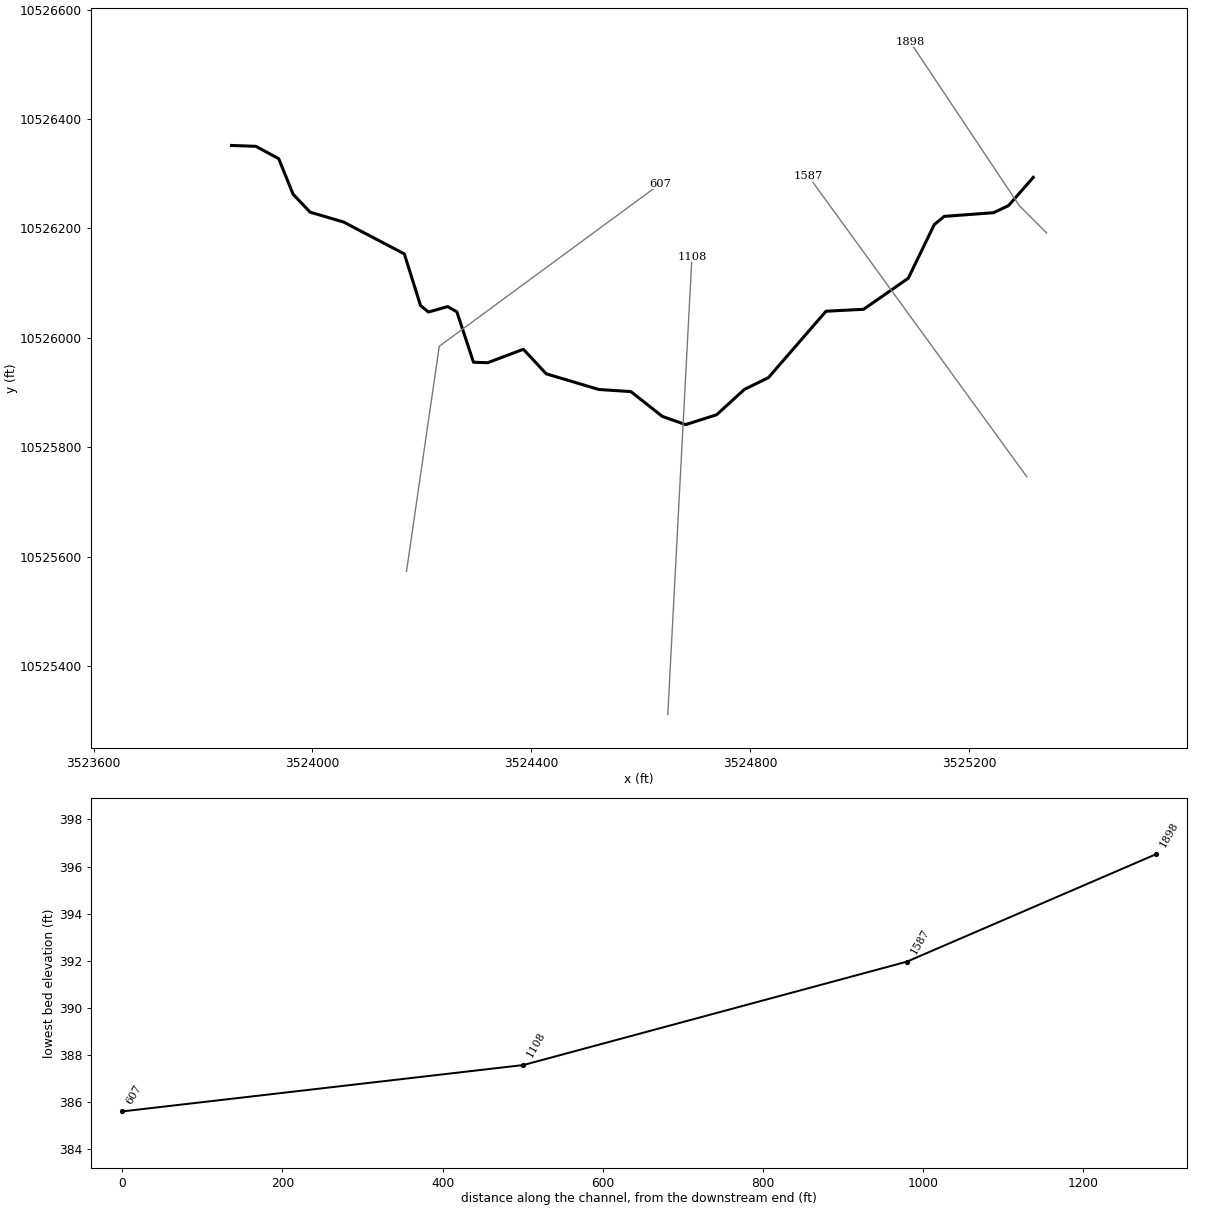
--- UNT0561 IN SAND CR.prj (project) ---

Proj Title=UNT0561 IN SAND CR Base Level Engineering
Current Plan=p01
Default Exp/Contr=0.3,0.1
English Units
Geom File=g01
Flow File=f01
Plan File=p01
Y Axis Title=Elevation
X Axis Title(PF)=Main Channel Distance
X Axis Title(XS)=Station
BEGIN DESCRIPTION:
UNT0561 IN SAND CR
END DESCRIPTION:
DSS Export Rating Curves= 0
DSS Export Rating Curve Sorted= 0
DSS Export Volume Flow Curves= 0
DXF OffsetX= 0
DXF OffsetY= 0
DXF ScaleX= 1
DXF ScaleY= 10

--- UNT0561 IN SAND CR.p01 (plan) ---

Plan Title=Multiple Run
Short Identifier=Multiple
Geom File=g01
Flow File=f01
Subcritical Flow
K Sum by GR= 0
Std Step Tol= 0.01
Critical Tol= 0.01
Num of Std Step Trials= 20
Max Error Tol= 0.3
Flow Tol Ratio= 0.001
Split Flow NTrial= 30
Split Flow Tol= 0.02
Split Flow Ratio= 0.02
Log Output Level= 0
Friction Slope Method= 1
Unsteady Friction Slope Method= 2
Unsteady Bridges Friction Slope Method= 1
Parabolic Critical Depth
Global Vel Dist=  1 , 1 , 1
Global Log Level= 0
CheckData=True
Encroach Param= -1, 0, 0, 0
BEGIN DESCRIPTION:
Multiple Run
END DESCRIPTION:

--- UNT0561 IN SAND CR.f01 (steady flow) ---

Flow Title=Multiple
Number of Profiles=7
Profile Names=10-year,25-year,50-year,1pct_min,100-year,1pct_plu,500-year
River Rch & RM= UNT0561 IN SAND ,Reach-1,1898
     527     699     836     733     991    1340    1384
Boundary for River Rch & Prof#=UNT0561 IN SAND ,Reach-1,1
Up Type=0
Dn Type=3
Dn Slope=0.005
Boundary for River Rch & Prof#=UNT0561 IN SAND ,Reach-1,2
Up Type=0
Dn Type=3
Dn Slope=0.005
Boundary for River Rch & Prof#=UNT0561 IN SAND ,Reach-1,3
Up Type=0
Dn Type=3
Dn Slope=0.005
Boundary for River Rch & Prof#=UNT0561 IN SAND ,Reach-1,4
Up Type=0
Dn Type=3
Dn Slope=0.005
Boundary for River Rch & Prof#=UNT0561 IN SAND ,Reach-1,5
Up Type=0
Dn Type=3
Dn Slope=0.005
Boundary for River Rch & Prof#=UNT0561 IN SAND ,Reach-1,6
Up Type=0
Dn Type=3
Dn Slope=0.005
Boundary for River Rch & Prof#=UNT0561 IN SAND ,Reach-1,7
Up Type=0
Dn Type=3
Dn Slope=0.005

--- UNT0561 IN SAND CR.g01 (geometry) ---

Geom Title=Existing Conditions
Program Version=4.10

River Reach=UNT0561 IN SAND ,Reach-1
Reach XY= 30
      3525317.69     10526293.28      3525272.51     10526241.71
      3525245.17     10526228.69      3525154.87     10526221.97
      3525136.64     10526206.87      3525089.25     10526108.95
      3525007.49     10526052.11      3524938.74     10526048.55
      3524833.58     10525927.21      3524789.67     10525905.65
      3524738.82     10525859.32      3524682.24      10525841.3
      3524639.45     10525856.38      3524582.09     10525901.65
      3524523.35     10525905.54      3524427.34     10525934.17
      3524385.59     10525979.08      3524320.29     10525954.43
      3524294.36     10525955.35      3524263.97     10526047.52
      3524247.19     10526057.02      3524212.08     10526047.14
      3524197.56     10526059.03      3524167.94     10526153.35
      3524057.05     10526211.56      3523995.77     10526229.66
      3523964.56      10526262.5       3523938.3     10526327.45
      3523896.71     10526349.99      3523852.11     10526351.64

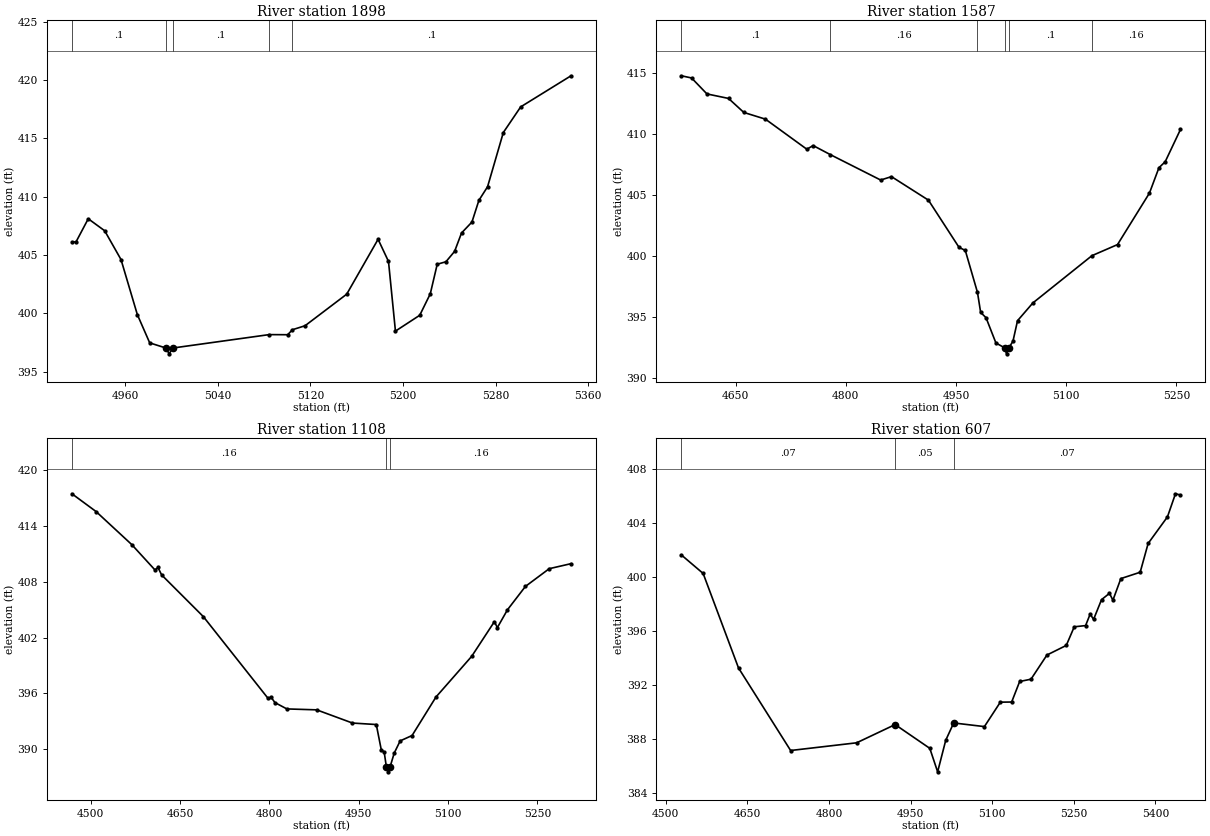
Type RM Length L Ch R = 1 ,1898    ,311,311,311
BEGIN DESCRIPTION:
UNT0561 IN SAND CR 4.0
END DESCRIPTION:
XS GIS Cut Line= 3
      3525342.09     10526191.66      3525292.11     10526241.64
      3525092.13     10526541.61
#Sta/Elev= 30
    4914  406.12  4917.5  406.12  4928.1  408.11  4942.3  407.08  4956.4  404.61
  4970.5  399.89  4981.2  397.46  4995.2  397.02    4998  396.52  5001.2  397.02
  5084.4  398.17  5100.4  398.16  5104.5  398.59  5115.4  398.93  5151.4  401.64
  5178.5  406.35  5187.5  404.45  5193.5  398.47  5214.5  399.83  5223.6  401.67
  5229.6  404.21  5237.1  404.42  5244.6  405.31  5250.6  406.89  5259.6  407.83
  5265.6  409.69  5273.1  410.86  5286.7  415.51  5301.7  417.71  5345.2  420.38
#Mann= 5 ,-1 , 0
    4914      .1       0  4995.2     .07       0  5001.2      .1       0
  5084.4     .16       0  5104.5      .1       0
Bank Sta=4995.2,5001.2
XS Rating Curve= 0 ,0
Exp/Cntr=0.3,0.1

Type RM Length L Ch R = 1 ,1587    ,479,479,479
BEGIN DESCRIPTION:
UNT0561 IN SAND CR 3.0
END DESCRIPTION:
XS GIS Cut Line= 2
      3525305.82     10525746.08      3524906.52     10526295.76
#Sta/Elev= 30
  4576.2  414.79  4590.1  414.61    4611   413.3  4640.4  412.93  4661.2  411.78
  4690.6  411.23    4747  408.76  4755.6  409.06  4779.2  408.31  4847.5  406.23
  4862.2  406.51  4912.5  404.58  4954.2   400.7  4962.7  400.45  4979.3     397
  4983.6  395.36  4990.9  394.93  5004.4  392.85  5016.1  392.46  5018.9  391.96
  5022.1  392.46  5027.6     393  5033.8  394.68  5054.7  396.14  5135.1  400.02
  5169.9  400.93  5213.4  405.16  5226.3  407.24  5234.8  407.73  5255.6  410.38
#Mann= 6 ,-1 , 0
  4576.2      .1       0  4779.2     .16       0  4979.3      .1       0
  5016.1     .07       0  5022.1      .1       0  5135.1     .16       0
Bank Sta=5016.1,5022.1
XS Rating Curve= 0 ,0
Exp/Cntr=0.3,0.1

Type RM Length L Ch R = 1 ,1108    ,501,501,501
BEGIN DESCRIPTION:
UNT0561 IN SAND CR 2.0
END DESCRIPTION:
XS GIS Cut Line= 2
      3524649.55     10525311.24      3524693.73     10526148.17
#Sta/Elev= 30
  4468.3  417.49  4508.8  415.58  4568.8  412.02  4607.8  409.29  4612.8  409.56
  4618.9  408.76    4689  404.27  4797.7  395.47  4802.7   395.6  4809.2  395.02
  4829.2  394.34  4879.3  394.24  4939.4  392.82  4979.4  392.66  4987.7  389.96
  4992.7  389.68  4996.4  388.07  4999.2  387.57  5002.4  388.07  5009.5  389.59
  5019.5   390.9  5039.5  391.48  5079.6  395.62  5139.6     400  5177.7  403.73
  5182.7  403.09  5199.7  405.01  5229.8  407.52  5269.8  409.43  5306.4  409.97
#Mann= 3 ,-1 , 0
  4468.3     .16       0  4996.4     .07       0  5002.4     .16       0
Bank Sta=4996.4,5002.4
XS Rating Curve= 0 ,0
Exp/Cntr=0.3,0.1

Type RM Length L Ch R = 1 ,607     ,0,0,0
BEGIN DESCRIPTION:
UNT0561 IN SAND CR 1.0
END DESCRIPTION:
XS GIS Cut Line= 3
      3524171.92     10525573.04      3524231.82     10525984.53
      3524635.48     10526281.41
#Sta/Elev= 30
    4529  401.66    4569  400.29    4634  393.29  4729.7  387.18    4851  387.75
  4921.7   389.1  4985.4  387.34  4999.8   385.6  5014.7  387.94  5029.3  389.22
  5085.7  388.95    5115  390.76  5135.8  390.77  5150.5  392.29  5171.3  392.46
  5200.6  394.25  5236.1  394.96  5250.8  396.34  5271.6  396.43    5280  397.28
  5286.3  396.89  5300.9  398.35  5315.5  398.82  5321.8  398.31  5336.4  399.91
  5371.9  400.38  5386.5  402.51    5422  404.48  5436.7  406.19  5445.9   406.1
#Mann= 3 , 0 , 0
    4529     .07       0  4921.7     .05       0  5029.3     .07       0
Bank Sta=4921.7,5029.3
XS Rating Curve= 0 ,0
Exp/Cntr=0.3,0.1

Chan Stop Cuts=-1
Use User Specified Reach Order=0
Composite Channel Slope=5