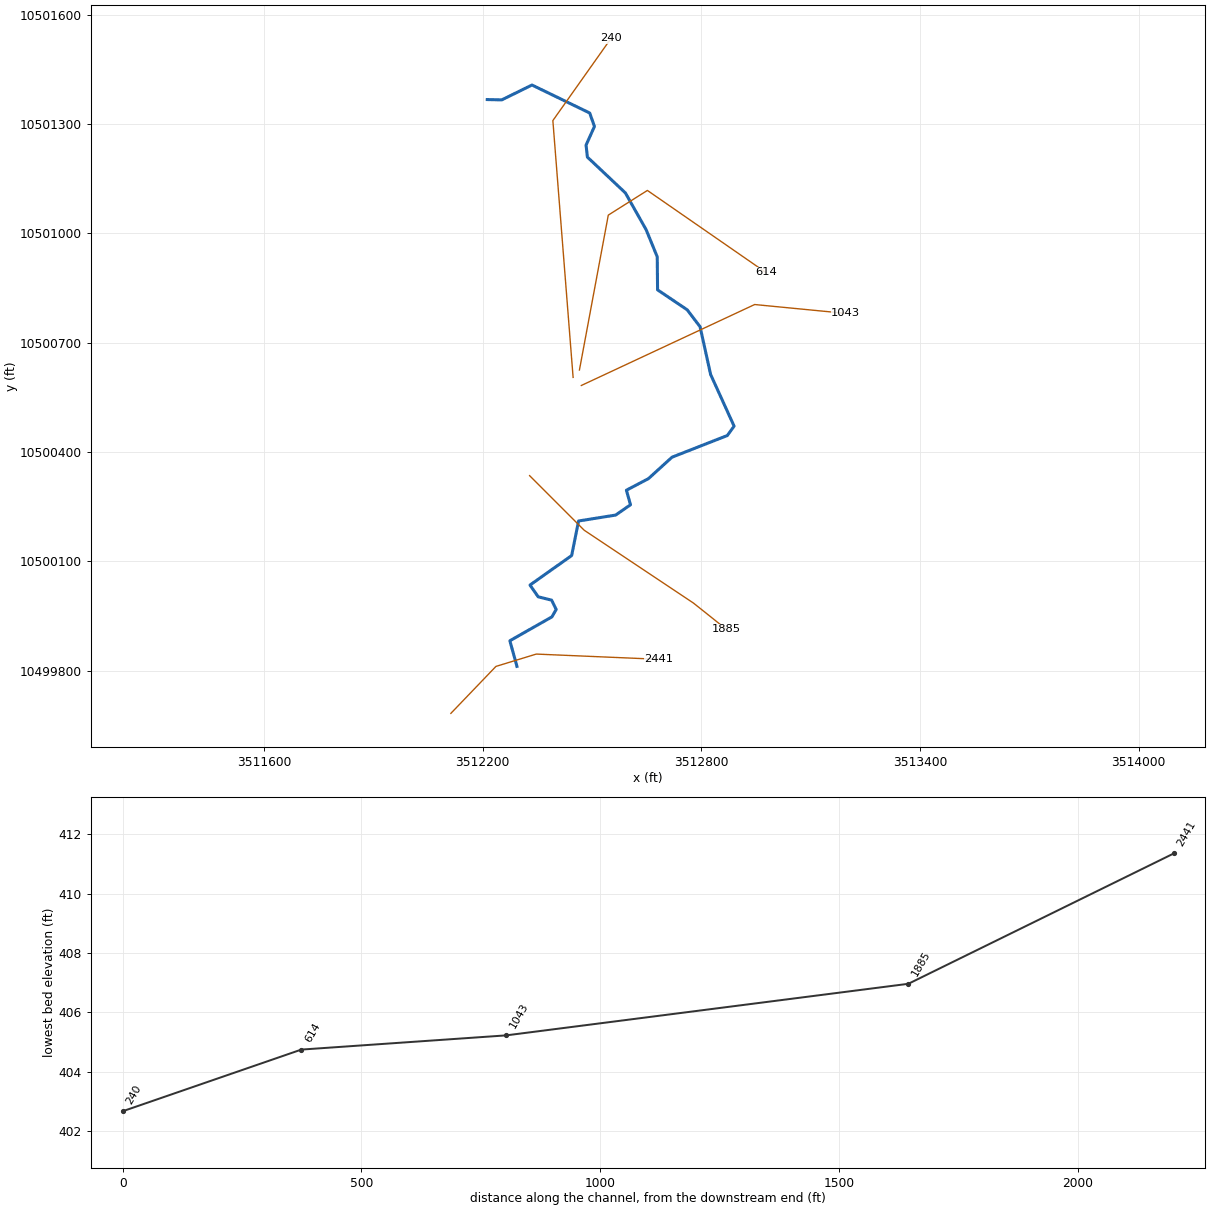
--- UNT0571 IN SAND CR.prj (project) ---

Proj Title=UNT0571 IN SAND CR Base Level Engineering
Current Plan=p01
Default Exp/Contr=0.3,0.1
English Units
Geom File=g01
Flow File=f01
Plan File=p01
Y Axis Title=Elevation
X Axis Title(PF)=Main Channel Distance
X Axis Title(XS)=Station
BEGIN DESCRIPTION:
UNT0571 IN SAND CR
END DESCRIPTION:
DSS Export Rating Curves= 0
DSS Export Rating Curve Sorted= 0
DSS Export Volume Flow Curves= 0
DXF OffsetX= 0
DXF OffsetY= 0
DXF ScaleX= 1
DXF ScaleY= 10

--- UNT0571 IN SAND CR.p01 (plan) ---

Plan Title=Multiple Run
Short Identifier=Multiple
Geom File=g01
Flow File=f01
Subcritical Flow
K Sum by GR= 0
Std Step Tol= 0.01
Critical Tol= 0.01
Num of Std Step Trials= 20
Max Error Tol= 0.3
Flow Tol Ratio= 0.001
Split Flow NTrial= 30
Split Flow Tol= 0.02
Split Flow Ratio= 0.02
Log Output Level= 0
Friction Slope Method= 1
Unsteady Friction Slope Method= 2
Unsteady Bridges Friction Slope Method= 1
Parabolic Critical Depth
Global Vel Dist=  1 , 1 , 1
Global Log Level= 0
CheckData=True
Encroach Param= -1, 0, 0, 0
BEGIN DESCRIPTION:
Multiple Run
END DESCRIPTION:

--- UNT0571 IN SAND CR.f01 (steady flow) ---

Flow Title=Multiple
Number of Profiles=7
Profile Names=10-year,25-year,50-year,1pct_min,100-year,1pct_plu,500-year
River Rch & RM= UNT0571 IN SAND ,Reach-1,2441
     639     854    1027     902    1220    1650    1717
Boundary for River Rch & Prof#=UNT0571 IN SAND ,Reach-1,1
Up Type=0
Dn Type=3
Dn Slope=0.005
Boundary for River Rch & Prof#=UNT0571 IN SAND ,Reach-1,2
Up Type=0
Dn Type=3
Dn Slope=0.005
Boundary for River Rch & Prof#=UNT0571 IN SAND ,Reach-1,3
Up Type=0
Dn Type=3
Dn Slope=0.005
Boundary for River Rch & Prof#=UNT0571 IN SAND ,Reach-1,4
Up Type=0
Dn Type=3
Dn Slope=0.005
Boundary for River Rch & Prof#=UNT0571 IN SAND ,Reach-1,5
Up Type=0
Dn Type=3
Dn Slope=0.005
Boundary for River Rch & Prof#=UNT0571 IN SAND ,Reach-1,6
Up Type=0
Dn Type=3
Dn Slope=0.005
Boundary for River Rch & Prof#=UNT0571 IN SAND ,Reach-1,7
Up Type=0
Dn Type=3
Dn Slope=0.005

--- UNT0571 IN SAND CR.g01 (geometry) ---

Geom Title=Existing Conditions
Program Version=4.10

River Reach=UNT0571 IN SAND ,Reach-1
Reach XY= 30
      3512293.82     10499811.89      3512274.35     10499882.14
       3512389.8     10499947.68      3512401.52     10499968.08
      3512388.93     10499993.68      3512352.12     10500002.76
      3512329.66     10500035.05      3512443.96     10500115.98
      3512462.92     10500210.84      3512564.74     10500227.13
      3512605.51      10500255.4      3512594.23     10500295.33
      3512654.66     10500327.05      3512719.49     10500385.99
      3512871.27     10500445.46      3512889.85     10500471.14
       3512825.4     10500613.01      3512796.42     10500744.12
      3512761.17     10500790.46      3512679.79      10500845.3
       3512678.9     10500935.97      3512648.53     10501010.17
       3512591.4     10501111.46      3512487.16     10501209.68
      3512483.55      10501242.6      3512506.55     10501293.81
      3512493.53     10501330.71      3512335.11     10501407.53
      3512252.21     10501366.73      3512212.31     10501367.59

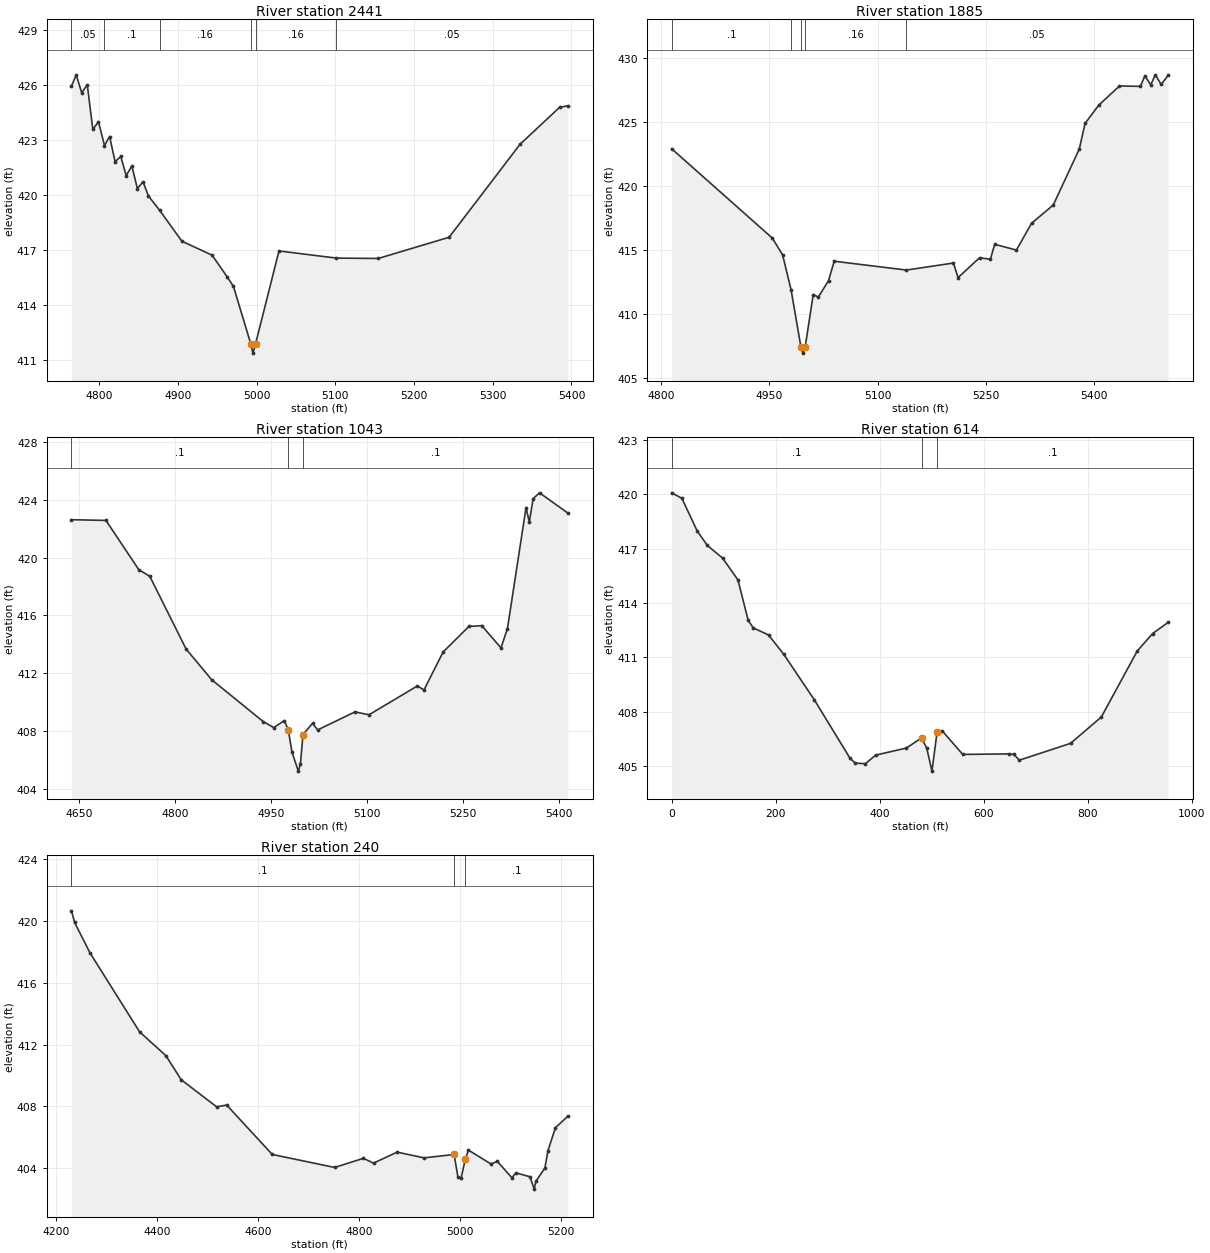
Type RM Length L Ch R = 1 ,2441    ,556,556,556
BEGIN DESCRIPTION:
UNT0571 IN SAND CR 4.1
END DESCRIPTION:
XS GIS Cut Line= 4
      3512112.47     10499682.83      3512236.16     10499811.73
      3512346.84     10499845.59      3512682.74     10499831.27
#Sta/Elev= 30
  4764.8  425.94  4770.8  426.56  4777.7  425.59  4784.9  426.01  4791.9  423.58
  4799.1     424  4806.7   422.7  4813.2  423.19  4820.2  421.82  4827.4   422.1
  4834.3  421.06  4841.5  421.58  4848.5  420.35  4855.7  420.72  4862.6  419.94
  4876.8  419.16  4905.1  417.47  4943.5  416.71  4962.8  415.51  4970.6     415
  4992.6  411.86  4995.3  411.36  4998.6  411.86  5028.4  416.94  5101.4  416.55
  5154.5  416.53  5244.6  417.69  5334.7  422.77  5384.8  424.78  5395.4  424.87
#Mann= 6 ,-1 , 0
  4764.8     .05       0  4806.7      .1       0  4876.8     .16       0
  4992.6     .07       0  4998.6     .16       0  5101.4     .05       0
Bank Sta=4992.6,4998.6
XS Rating Curve= 0 ,0
Exp/Cntr=0.3,0.1

Type RM Length L Ch R = 1 ,1885    ,842,842,842
BEGIN DESCRIPTION:
UNT0571 IN SAND CR 4.0
END DESCRIPTION:
XS GIS Cut Line= 4
      3512328.54     10500335.41      3512478.56     10500185.39
      3512778.56     10499985.39      3512868.49     10499913.73
#Sta/Elev= 30
  4814.6   422.9  4954.1  415.93  4968.3  414.62    4980   411.9  4993.6  407.46
  4996.3  406.96  4999.6  407.46  5010.7  411.53  5017.8  411.33  5031.9  412.62
  5039.8  414.13  5139.9  413.44    5205  413.99  5211.3  412.85  5241.1   414.4
  5256.1  414.28  5262.1  415.45  5292.2     415  5313.2  417.09  5343.2  418.51
  5379.3  422.88  5387.3  424.88  5406.2   426.3    5435   427.8  5463.9  427.77
  5470.2  428.59  5478.3  427.89  5484.7  428.67  5492.7  427.92  5502.3  428.62
#Mann= 5 ,-1 , 0
  4814.6      .1       0    4980     .16       0  4993.6     .07       0
  4999.6     .16       0  5139.9     .05       0
Bank Sta=4993.6,4999.6
XS Rating Curve= 0 ,0
Exp/Cntr=0.3,0.1

Type RM Length L Ch R = 1 ,1043    ,429,429,429
BEGIN DESCRIPTION:
UNT0571 IN SAND CR 2.0
END DESCRIPTION:
XS GIS Cut Line= 3
      3512470.51     10500582.78      3512946.23     10500805.01
      3513196.18     10500780.71
#Sta/Elev= 30
  4638.2  422.62  4692.1  422.57  4743.3  419.17  4760.7   418.7  4817.4  413.67
  4857.6  411.54    4938  408.65  4954.5  408.23  4971.1  408.72  4977.4  408.04
  4982.9  406.55  4992.9  405.22  4996.2  405.72  5000.2  407.75  5015.2  408.53
  5023.1  408.07  5081.5  409.32  5103.5  409.12  5179.2  411.12  5189.3  410.83
  5219.4  413.47  5259.6  415.23  5279.7  415.29  5309.8  413.75  5319.9  415.08
    5349  423.46  5354.1  422.46  5360.1  424.08  5370.1  424.48  5414.4  423.08
#Mann= 3 , 0 , 0
  4638.2      .1       0  4977.4     .05       0  5000.2      .1       0
Bank Sta=4977.4,5000.2
XS Rating Curve= 0 ,0
Exp/Cntr=0.3,0.1

Type RM Length L Ch R = 1 ,614     ,374,374,374
XS GIS Cut Line= 4
     3512465.349     10500625.33     3512544.537    10501050.445
     3512651.858    10501118.172     3512976.945    10500893.111
#Sta/Elev= 30
       0  420.07   19.61  419.77   49.02  417.97   68.63  417.17   98.05  416.47
  127.46  415.27  147.07  413.05  156.87  412.63  186.29  412.24   215.7  411.17
  274.53  408.66  343.16  405.44  352.97  405.18  372.58  405.15  392.18  405.62
  451.15  406.01  480.77  406.57  490.64  405.99  500.51  404.74  510.38  406.89
  520.25  406.96  559.74  405.66  648.59  405.69  658.46  405.66  668.34  405.34
  767.05  406.27  826.29  407.72  895.39  411.36     925  412.32  954.62  412.93
#Mann= 3 , 0 , 0
       0      .1       0  480.77     .05       0  510.38      .1       0
Bank Sta=480.77,510.38
XS Rating Curve= 0 ,0
Exp/Cntr=0.3,0.1

Type RM Length L Ch R = 1 ,240     ,0,0,0
BEGIN DESCRIPTION:
UNT0571 IN SAND CR 1.0
END DESCRIPTION:
XS GIS Cut Line= 3
      3512447.95     10500605.03      3512392.39     10501309.91
      3512552.14     10501535.64
#Sta/Elev= 30
  4230.7  420.64  4236.9  419.89  4267.4  417.92  4365.7  412.82  4417.9  411.28
    4448  409.73  4518.2  407.98  4538.3  408.09  4628.5   404.9  4752.2  404.06
  4809.1  404.65  4829.2  404.34    4876  405.05  4929.5  404.68  4988.9   404.9
  4996.4  403.46  5002.6  403.35  5011.2  404.61  5017.3  405.18  5061.7  404.29
  5074.6  404.45  5103.5  403.39  5111.4  403.71  5139.2  403.46  5147.6  402.66
  5150.8  403.16  5168.7  404.02  5174.9  405.15  5189.7  406.63  5214.3  407.37
#Mann= 3 , 0 , 0
  4230.7      .1       0  4988.9     .05       0  5011.2      .1       0
Bank Sta=4988.9,5011.2
XS Rating Curve= 0 ,0
Exp/Cntr=0.3,0.1

Chan Stop Cuts=-1
Use User Specified Reach Order=0
Composite Channel Slope=5