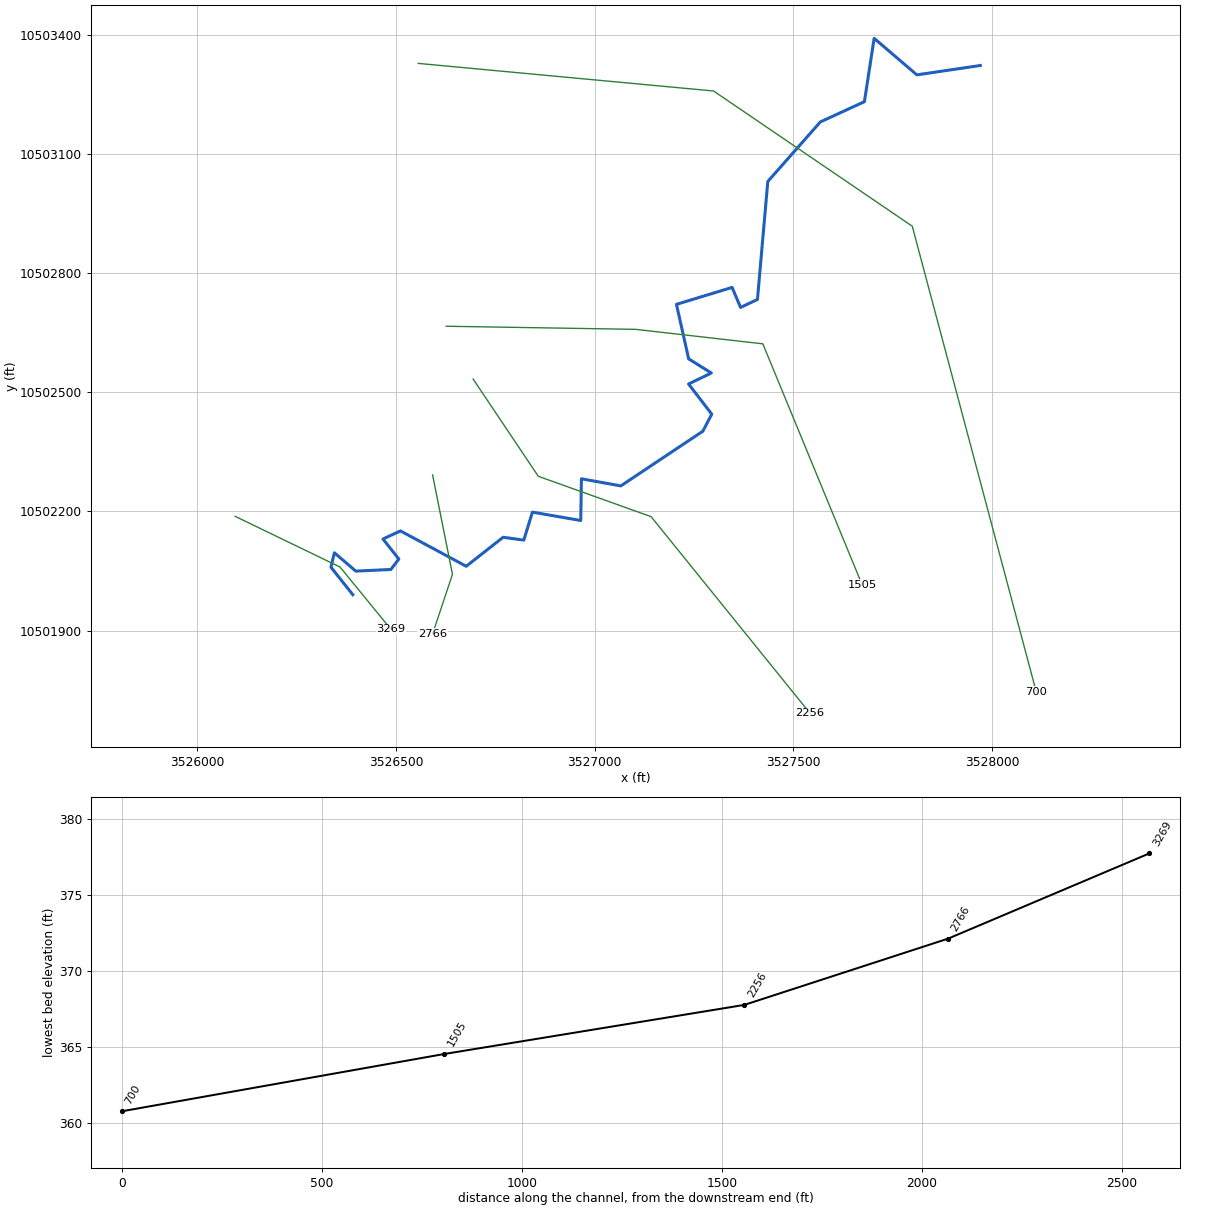
--- UNT0575 IN SAND CR.prj (project) ---

Proj Title=UNT0575 IN SAND CR Base Level Engineering
Current Plan=p01
Default Exp/Contr=0.3,0.1
English Units
Geom File=g01
Flow File=f01
Plan File=p01
BEGIN DESCRIPTION:
UNT0575 IN SAND CR
END DESCRIPTION:

--- UNT0575 IN SAND CR.p01 (plan) ---

Plan Title=Multiple Run
Short Identifier=Multiple
Geom File=g01
Flow File=f01
Subcritical Flow
K Sum by GR= 0
Std Step Tol= 0.01
Critical Tol= 0.01
Num of Std Step Trials= 20
Max Error Tol= 0.3
Flow Tol Ratio= 0.001
Split Flow NTrial= 30
Split Flow Tol= 0.02
Split Flow Ratio= 0.02
Log Output Level= 0
Friction Slope Method= 1
Unsteady Friction Slope Method= 2
Unsteady Bridges Friction Slope Method= 1
Parabolic Critical Depth
Global Vel Dist=  1 , 1 , 1
Global Log Level= 0
CheckData=True
Encroach Param= -1, 0, 0, 0
BEGIN DESCRIPTION:
Multiple Run
END DESCRIPTION:

--- UNT0575 IN SAND CR.f01 (steady flow) ---

Flow Title=Multiple
Number of Profiles=7
Profile Names=10-year,25-year,50-year,1pct_min,100-year,1pct_plu,500-year
River Rch & RM= UNT0575 IN SAND ,Reach-1,3269
     540     718     860     754    1019    1379    1426
Boundary for River Rch & Prof#=UNT0575 IN SAND ,Reach-1,1
Up Type=0
Dn Type=3
Dn Slope=0.005
Boundary for River Rch & Prof#=UNT0575 IN SAND ,Reach-1,2
Up Type=0
Dn Type=3
Dn Slope=0.005
Boundary for River Rch & Prof#=UNT0575 IN SAND ,Reach-1,3
Up Type=0
Dn Type=3
Dn Slope=0.005
Boundary for River Rch & Prof#=UNT0575 IN SAND ,Reach-1,4
Up Type=0
Dn Type=3
Dn Slope=0.005
Boundary for River Rch & Prof#=UNT0575 IN SAND ,Reach-1,5
Up Type=0
Dn Type=3
Dn Slope=0.005
Boundary for River Rch & Prof#=UNT0575 IN SAND ,Reach-1,6
Up Type=0
Dn Type=3
Dn Slope=0.005
Boundary for River Rch & Prof#=UNT0575 IN SAND ,Reach-1,7
Up Type=0
Dn Type=3
Dn Slope=0.005

--- UNT0575 IN SAND CR.g01 (geometry) ---

Geom Title=Existing Conditions

River Reach=UNT0575 IN SAND ,Reach-1
Reach XY= 30
      3526391.28     10501990.40      3526336.26     10502059.49
      3526345.00     10502095.77      3526398.72     10502049.69
      3526486.99     10502053.76      3526507.13     10502080.03
      3526467.20     10502130.48      3526511.23     10502150.81
      3526676.70     10502061.87      3526769.66     10502134.86
      3526821.62     10502127.68      3526843.31     10502198.12
      3526964.94     10502177.02      3526966.59     10502281.97
      3527065.82     10502264.11      3527272.11     10502401.64
      3527294.64     10502444.66      3527236.27     10502520.53
      3527293.56     10502548.31      3527236.51     10502583.79
      3527205.78     10502720.98      3527345.82     10502763.62
      3527367.09     10502713.27      3527409.62     10502733.24
      3527435.65     10503030.18      3527567.86     10503180.04
      3527678.80     10503231.08      3527703.28     10503390.46
      3527810.83     10503298.53      3527970.42     10503322.13

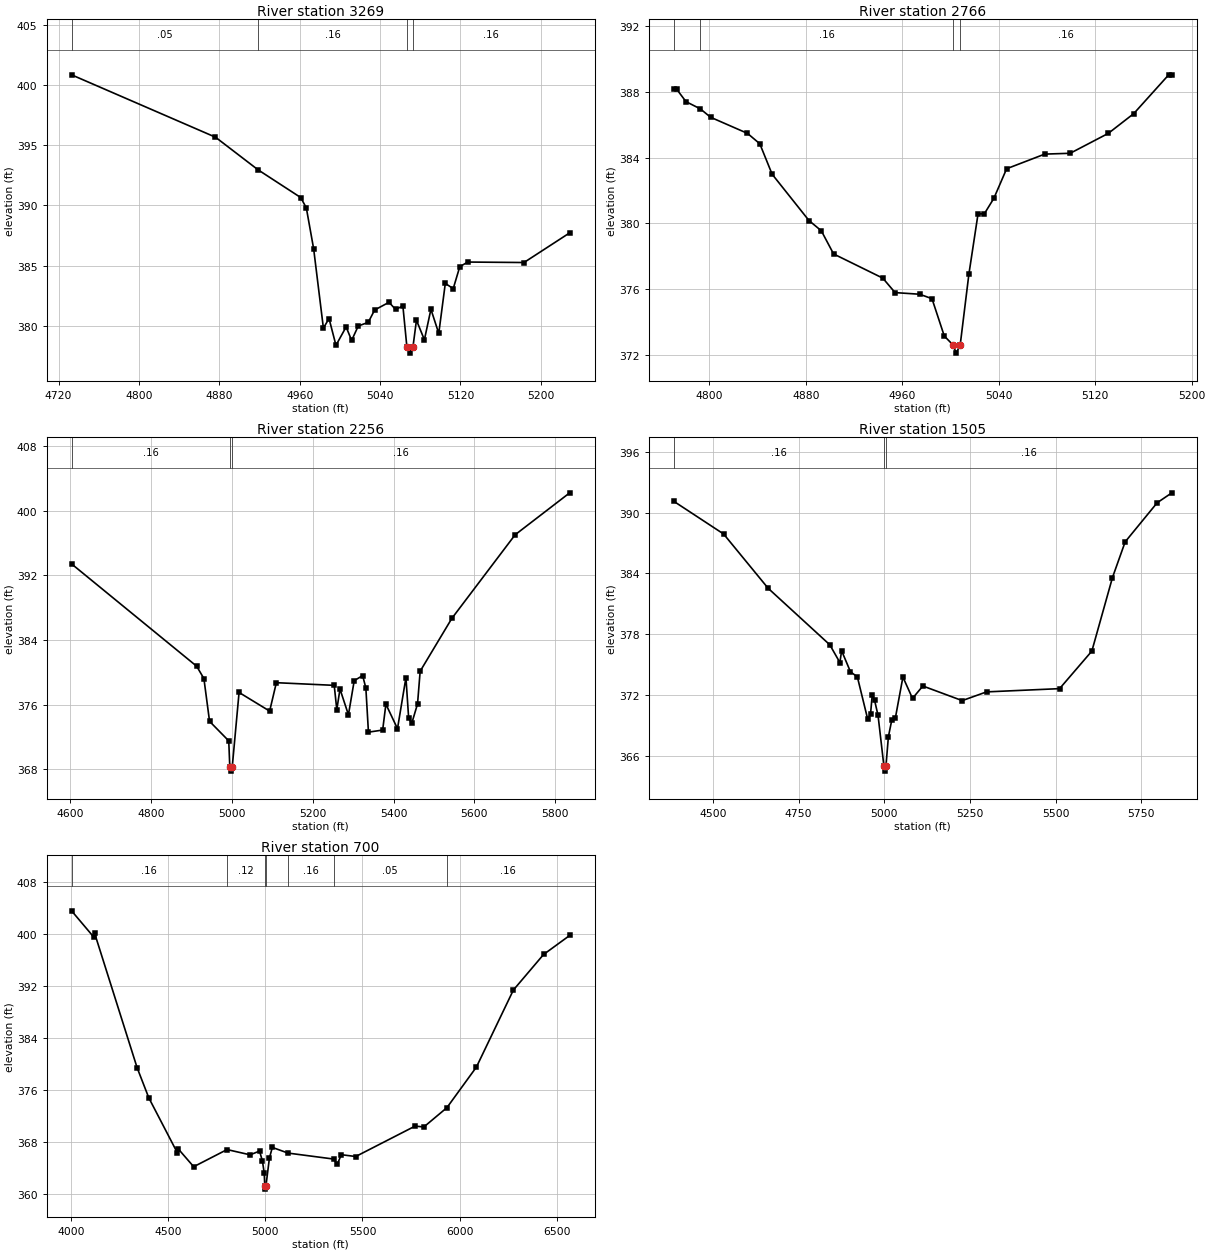
Type RM Length L Ch R = 1,3269,503,503,503
BEGIN DESCRIPTION:
UNT0575 IN SAND CR 4.1
END DESCRIPTION:
XS GIS Cut Line= 3
      3526095.22     10502187.53      3526359.09     10502059.94
      3526487.34     10501903.10
#Sta/Elev= 30
  4733.0  400.87  4876.2  395.68  4918.5  392.97  4961.0  390.66  4966.6  389.80
  4973.9  386.39  4983.6  379.79  4989.2  380.59  4996.1  378.36  5006.2  379.89
  5011.7  378.77  5018.3  379.97  5028.2  380.27  5034.6  381.30  5048.9  381.94
  5055.4  381.35  5062.7  381.63  5066.7  378.21  5069.5  377.71  5072.7  378.21
  5076.2  380.45  5084.1  378.82  5090.6  381.36  5098.4  379.35  5104.9  383.51
  5112.8  383.08  5119.3  384.90  5127.2  385.29  5183.2  385.25  5228.7  387.72
#Mann=4,-1,0
  4733.0    0.05       0  4918.5    0.16       0  5066.7    0.07       0
  5072.7    0.16       0
Bank Sta=5066.7,5072.7
Exp/Cntr=0.3,0.1

Type RM Length L Ch R = 1,2766,510,510,510
BEGIN DESCRIPTION:
UNT0575 IN SAND CR 4.0
END DESCRIPTION:
XS GIS Cut Line= 3
      3526592.10     10502291.68      3526642.11     10502041.64
      3526592.11     10501891.65
#Sta/Elev= 30
  4770.4  388.14  4773.0  388.14  4780.6  387.40  4792.5  386.96  4801.0  386.45
  4831.6  385.47  4841.8  384.84  4852.0  382.99  4882.6  380.17  4892.8  379.55
  4903.0  378.14  4943.8  376.67  4954.0  375.79  4974.4  375.69  4984.6  375.42
  4994.8  373.15  5002.0  372.61  5004.7  372.11  5008.0  372.61  5015.2  376.91
  5022.8  380.58  5028.0  380.58  5035.9  381.52  5046.5  383.32  5078.1  384.21
  5099.2  384.26  5130.8  385.47  5151.9  386.67  5180.9  389.03  5183.5  389.03
#Mann=4,-1,0
  4770.4    0.05       0  4792.5    0.16       0  5002.0    0.07       0
  5008.0    0.16       0
Bank Sta=5002,5008
Exp/Cntr=0.3,0.1

Type RM Length L Ch R = 1,2256,751,751,751
BEGIN DESCRIPTION:
UNT0575 IN SAND CR 3.0
END DESCRIPTION:
XS GIS Cut Line= 4
      3526694.01     10502533.14      3526858.10     10502288.31
      3527141.95     10502186.74      3527542.10     10501691.65
#Sta/Elev= 30
  4603.2  393.43  4912.8  380.75  4930.7  379.22  4944.7  373.92  4992.2  371.50
  4994.8  368.25  4997.5  367.75  5000.8  368.25  5017.7  377.50  5093.4  375.19
  5110.0  378.71  5253.2  378.38  5259.6  375.37  5267.5  377.92  5288.4  374.73
  5302.7  378.96  5323.5  379.59  5331.5  378.06  5337.9  372.58  5373.1  372.84
  5381.1  376.05  5409.8  373.01  5430.7  379.34  5437.4  374.35  5445.0  373.66
  5459.4  376.08  5465.9  380.13  5544.2  386.67  5700.9  397.04  5836.0  402.24
#Mann=3,-1,0
  4603.2    0.16       0  4994.8    0.07       0  5000.8    0.16       0
Bank Sta=4994.8,5000.8
Exp/Cntr=0.3,0.1

Type RM Length L Ch R = 1,1505,805,805,805
BEGIN DESCRIPTION:
UNT0575 IN SAND CR 2.0
END DESCRIPTION:
XS GIS Cut Line= 4
      3526626.34     10502665.91      3527102.89     10502658.10
      3527423.20     10502621.64      3527672.84     10502015.75
#Sta/Elev= 30
  4385.3  391.12  4531.1  387.89  4661.1  382.54  4841.1  376.97  4870.5  375.22
  4875.5  376.39  4901.4  374.31  4921.5  373.81  4951.7  369.64  4960.0  370.15
  4965.0  372.05  4971.8  371.50  4981.9  370.01  4999.0  365.02  5001.8  364.52
  5005.0  365.02  5012.1  367.91  5022.2  369.59  5032.2  369.71  5054.5  373.79
  5082.5  371.69  5112.7  372.91  5227.6  371.47  5298.7  372.33  5511.9  372.65
  5606.1  376.35  5666.3  383.60  5703.4  387.12  5796.8  390.97  5839.6  391.95
#Mann=3,-1,0
  4385.3    0.16       0  4999.0    0.07       0  5005.0    0.16       0
Bank Sta=4999,5005
Exp/Cntr=0.3,0.1

Type RM Length L Ch R = 1,700,0,0,0
BEGIN DESCRIPTION:
UNT0575 IN SAND CR 1.0
END DESCRIPTION:
XS GIS Cut Line= 4
      3526556.19     10503327.37      3527299.24     10503257.92
      3527799.24     10502917.65      3528111.38     10501745.38
#Sta/Elev= 30
  4002.7  403.60  4116.0  399.59  4121.0  400.18  4340.1  379.45  4400.3  374.81
  4546.9  366.37  4551.9  366.95  4631.3  364.21  4803.1  366.85  4921.8  366.04
  4970.4  366.62  4985.3  365.06  4994.2  363.28  4997.3  361.26  5000.0  360.76
  5003.3  361.26  5021.2  365.56  5036.2  367.18  5116.8  366.31  5351.7  365.39
  5370.4  364.56  5391.1  366.06  5465.4  365.78  5770.9  370.46  5816.2  370.33
  5934.8  373.30  6086.7  379.55  6277.0  391.41  6432.4  396.88  6566.9  399.81
#Mann=7,-1,0
  4002.7    0.16       0  4803.1    0.12       0  4997.3    0.07       0
  5003.3    0.12       0  5116.8    0.16       0  5351.7    0.05       0
  5934.8    0.16       0
Bank Sta=4997.3,5003.3
Exp/Cntr=0.3,0.1

Chan Stop Cuts=-1