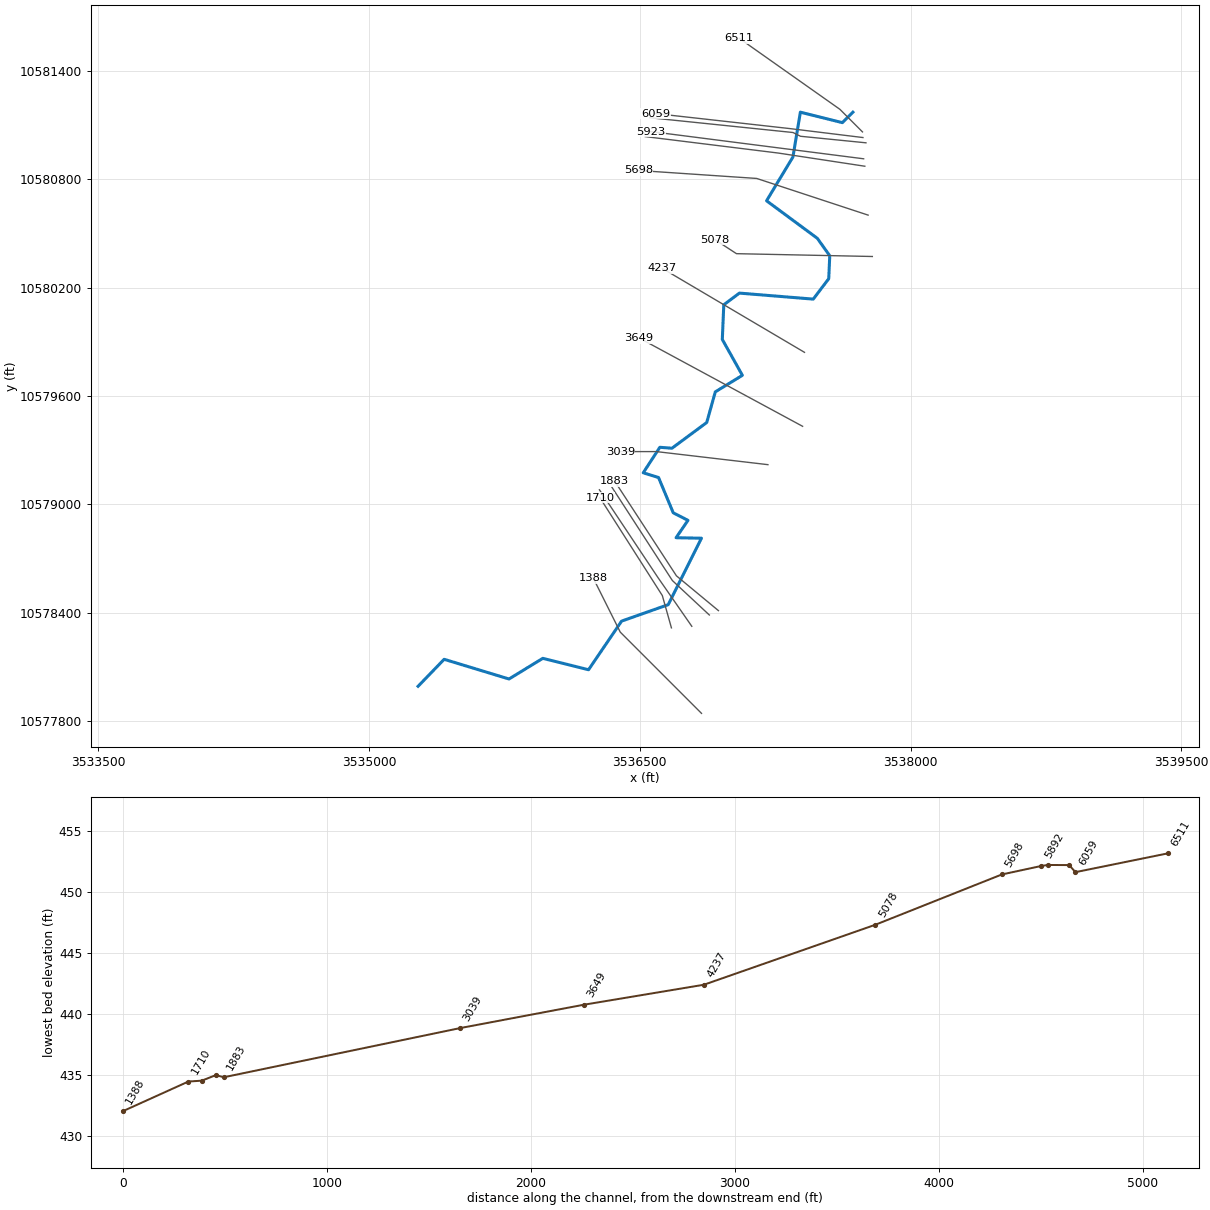
--- UNT0587 IN SAND CR.prj (project) ---

Proj Title=UNT0587 IN SAND CR Base Level Engineering
Current Plan=p01
Default Exp/Contr=0.3,0.1
English Units
Geom File=g01
Flow File=f01
Plan File=p01
Y Axis Title=Elevation
X Axis Title(PF)=Main Channel Distance
X Axis Title(XS)=Station
BEGIN DESCRIPTION:
UNT0587 IN SAND CR
END DESCRIPTION:
DSS Export Rating Curves= 0
DSS Export Rating Curve Sorted= 0
DSS Export Volume Flow Curves= 0
DXF OffsetX= 0
DXF OffsetY= 0
DXF ScaleX= 1
DXF ScaleY= 10

--- UNT0587 IN SAND CR.p01 (plan) ---

Plan Title=Multiple Run
Short Identifier=Multiple
Geom File=g01
Flow File=f01
Subcritical Flow
K Sum by GR= 0
Std Step Tol= 0.01
Critical Tol= 0.01
Num of Std Step Trials= 20
Max Error Tol= 0.3
Flow Tol Ratio= 0.001
Split Flow NTrial= 30
Split Flow Tol= 0.02
Split Flow Ratio= 0.02
Log Output Level= 0
Friction Slope Method= 1
Unsteady Friction Slope Method= 2
Unsteady Bridges Friction Slope Method= 1
Parabolic Critical Depth
Global Vel Dist=  1 , 1 , 1
Global Log Level= 0
CheckData=True
Encroach Param= -1, 0, 0, 0
BEGIN DESCRIPTION:
Multiple Run
END DESCRIPTION:

--- UNT0587 IN SAND CR.f01 (steady flow) ---

Flow Title=Multiple
Number of Profiles=7
Profile Names=10-year,25-year,50-year,1pct_min,100-year,1pct_plu,500-year
River Rch & RM= UNT0587 IN SAND ,Reach-1,6511
     492     641     758     655     886    1198    1204
River Rch & RM= UNT0587 IN SAND ,Reach-1,5923
     851    1149    1391    1229    1662    2247    2363
Boundary for River Rch & Prof#=UNT0587 IN SAND ,Reach-1,1
Up Type=0
Dn Type=3
Dn Slope=0.005
Boundary for River Rch & Prof#=UNT0587 IN SAND ,Reach-1,2
Up Type=0
Dn Type=3
Dn Slope=0.005
Boundary for River Rch & Prof#=UNT0587 IN SAND ,Reach-1,3
Up Type=0
Dn Type=3
Dn Slope=0.005
Boundary for River Rch & Prof#=UNT0587 IN SAND ,Reach-1,4
Up Type=0
Dn Type=3
Dn Slope=0.005
Boundary for River Rch & Prof#=UNT0587 IN SAND ,Reach-1,5
Up Type=0
Dn Type=3
Dn Slope=0.005
Boundary for River Rch & Prof#=UNT0587 IN SAND ,Reach-1,6
Up Type=0
Dn Type=3
Dn Slope=0.005
Boundary for River Rch & Prof#=UNT0587 IN SAND ,Reach-1,7
Up Type=0
Dn Type=3
Dn Slope=0.005

--- UNT0587 IN SAND CR.g01 (geometry) ---

Geom Title=Existing Conditions
Program Version=4.10

River Reach=UNT0587 IN SAND ,Reach-1
Reach XY= 30
      3537680.67     10581171.68      3537622.28     10581113.68
       3537389.6     10581171.61      3537348.41     10580923.24
      3537202.28     10580680.89      3537483.49     10580473.15
      3537552.36     10580376.48      3537546.81     10580249.51
      3537461.11     10580136.22      3537052.11     10580169.49
      3536965.43      10580104.8       3536957.3     10579912.81
      3537068.47     10579714.09      3536918.48     10579622.48
      3536870.94     10579452.71      3536678.35     10579310.25
      3536611.32     10579315.51      3536519.25     10579174.23
      3536604.17     10579147.96      3536685.51     10578952.54
      3536767.11     10578910.88      3536701.14     10578814.52
      3536841.76     10578811.92      3536657.74     10578443.86
      3536399.49     10578352.71      3536216.37     10578083.37
      3535962.96     10578146.55      3535775.87      10578032.1
      3535416.58      10578141.2      3535272.11     10577991.64

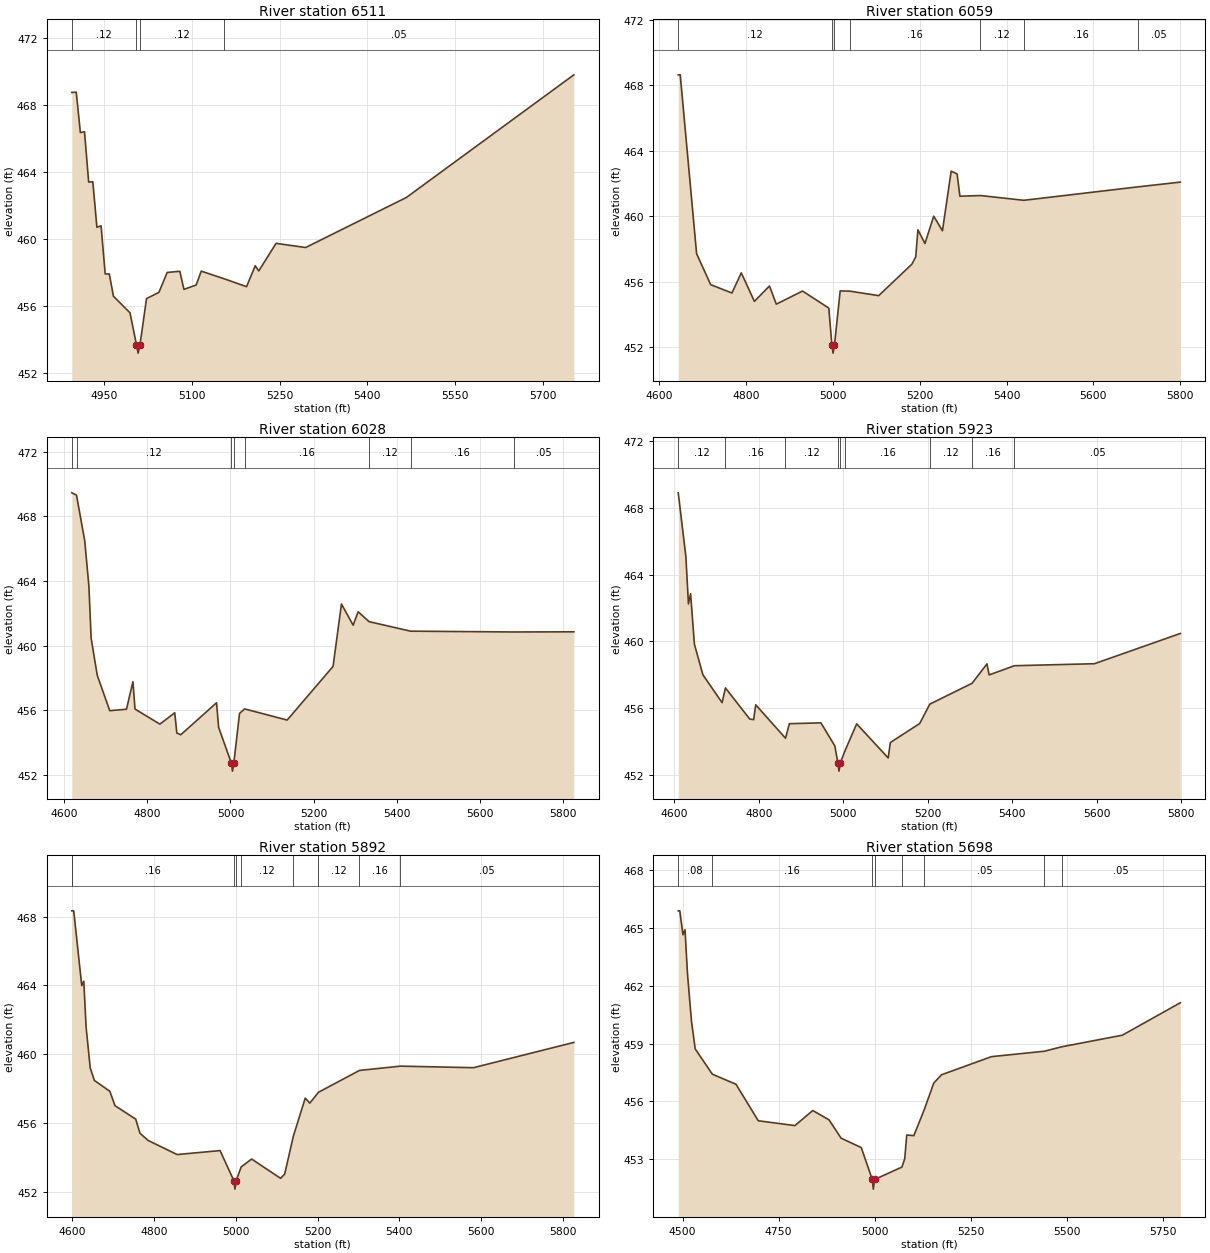
Type RM Length L Ch R = 1 ,6511    ,452,452,452
BEGIN DESCRIPTION:
UNT0587 IN SAND CR 8.3
END DESCRIPTION:
XS GIS Cut Line= 3
      3537733.68     10581062.36      3537608.65     10581187.39
      3537051.33     10581580.64
#Sta/Elev= 30
  4894.4  468.77  4902.1  468.78  4909.1  466.37  4916.2  466.42  4923.3  463.41
  4930.4  463.43  4937.4  460.71  4944.5   460.8  4951.6  457.92  4958.6  457.92
  4965.7  456.59    4994   455.6  5005.1  453.69  5007.9  453.19  5011.1  453.69
  5022.3  456.45  5043.5  456.82  5057.6  458.01  5079.2  458.08  5086.3     457
  5107.2  457.26  5115.9  458.09  5154.6  457.64  5193.4  457.16  5208.2  458.41
  5214.3   458.1  5243.9  459.75  5294.4   459.5  5466.8  462.49  5753.3  469.82
#Mann= 4 ,-1 , 0
  4894.4     .12       0  5005.1     .07       0  5011.1     .12       0
  5154.6     .05       0
Bank Sta=5005.1,5011.1
XS Rating Curve= 0 ,0
Exp/Cntr=0.3,0.1

Type RM Length L Ch R = 1 ,6059    ,31,31,31
BEGIN DESCRIPTION:
UNT0587 IN SAND CR 8.2
END DESCRIPTION:
XS GIS Cut Line= 3
      3537736.22     10581031.14      3537332.61     10581080.62
      3536587.79     10581163.95
#Sta/Elev= 30
  4644.1  468.64  4648.7  468.64  4686.4  457.72  4718.8  455.83  4767.8  455.32
  4789.3  456.55  4819.5  454.81  4854.2  455.75  4869.9  454.64  4930.3  455.44
  4990.8   454.4  4997.9  452.15  5000.6  451.65  5003.9  452.15    5017  455.45
  5040.1  455.43  5105.7  455.16  5182.1  457.08    5191  457.53    5196  459.18
  5212.2  458.34  5232.4  460.01  5252.5  459.12  5272.6  462.76  5286.2  462.59
  5292.7  461.23  5340.1  461.27    5440  460.98  5702.5   461.8  5800.2  462.09
#Mann= 7 ,-1 , 0
  4644.1     .12       0  4997.9     .07       0  5003.9     .12       0
  5040.1     .16       0  5340.1     .12       0    5440     .16       0
  5702.5     .05       0
Bank Sta=4997.9,5003.9
XS Rating Curve= 0 ,0
Exp/Cntr=0.3,0.1

Type RM Length L Ch R = 1 ,6028    ,105,105,105
BEGIN DESCRIPTION:
UNT0587 IN SAND CR 10.0
END DESCRIPTION:
XS GIS Cut Line= 4
      3537753.08     10581001.97      3537390.42     10581038.17
      3537348.75       10581059.      3536555.82      10581140.9
#Sta/Elev= 30
  4618.1  469.45  4629.5  469.31  4649.2   466.5  4659.3  463.69  4664.7  460.46
  4679.4  458.16  4709.5  455.97  4749.7  456.06  4765.3  457.76  4770.3  456.07
  4830.1  455.14  4865.9  455.84  4870.9  454.59  4880.4  454.48  4966.5  456.46
  4971.5  454.94  5002.1  452.73  5004.8  452.23  5008.1  452.73  5021.8   455.8
    5034  456.08  5136.4  455.39  5246.9  458.71  5267.1  462.57  5295.2  461.26
  5307.3  462.09  5333.5  461.48  5433.4  460.89  5681.2  460.84  5826.3  460.85
#Mann= 8 ,-1 , 0
  4618.1     .05       0  4629.5     .12       0  5002.1     .07       0
  5008.1     .12       0    5034     .16       0  5333.5     .12       0
  5433.4     .16       0  5681.2     .05       0
Bank Sta=5002.1,5008.1
XS Rating Curve= 0 ,0
Exp/Cntr=0.3,0.1

Type RM Length L Ch R = 1 ,5923    ,31,31,31
BEGIN DESCRIPTION:
UNT0587 IN SAND CR 9.0
END DESCRIPTION:
XS GIS Cut Line= 2
      3537740.07     10580913.43       3536560.3     10581064.48
#Sta/Elev= 30
    4609   468.9  4627.1  465.08  4633.2  462.25  4638.3  462.86  4647.3  459.84
  4667.4  458.01  4712.9  456.34  4720.8  457.22  4778.3  455.36  4787.6  455.32
  4792.6  456.21  4863.1  454.21  4872.3  455.08    4947  455.13    4980  453.75
  4987.1  452.74  4989.8  452.24  4993.1  452.74  5004.6  453.49  5031.7  455.07
  5106.4  453.03  5111.4  453.95    5181  455.09    5205  456.25  5305.2   457.5
  5340.4  458.66  5345.5     458  5405.5  458.55    5595  458.67  5798.4  460.48
#Mann= 9 ,-1 , 0
    4609     .12       0  4720.8     .16       0  4863.1     .12       0
  4987.1     .07       0  4993.1     .12       0  5004.6     .16       0
    5205     .12       0  5305.2     .16       0  5405.5     .05       0
Bank Sta=4987.1,4993.1
XS Rating Curve= 0 ,0
Exp/Cntr=0.3,0.1

Type RM Length L Ch R = 1 ,5892    ,194,194,194
BEGIN DESCRIPTION:
UNT0587 IN SAND CR 8.1
END DESCRIPTION:
XS GIS Cut Line= 3
      3537746.67     10580872.28       3537267.5      10580945.2
       3536530.5     10581036.35
#Sta/Elev= 30
  4599.1  468.34  4600.2  468.34  4603.9  468.34  4623.5  463.99  4628.5  464.25
  4634.1  461.59  4644.2  459.21  4654.3  458.48  4692.1  457.85  4704.9  457.01
  4755.4  456.23  4765.8  455.41  4785.8  454.99  4856.6  454.17  4961.6   454.4
  4995.2  452.66    4998  452.16  5001.2  452.66  5013.2  453.45  5038.7  453.91
  5109.4  452.79  5119.5  453.03  5140.9  455.25  5169.8  457.45    5181  457.16
  5202.1  457.79  5302.3  459.06  5402.4  459.31  5581.1  459.22  5826.4  460.69
#Mann= 9 ,-1 , 0
  4599.1     .08       0  4600.2     .16       0  4995.2     .07       0
  5001.2     .16       0  5013.2     .12       0  5140.9     .16       0
  5202.1     .12       0  5302.3     .16       0  5402.4     .05       0
Bank Sta=4995.2,5001.2
XS Rating Curve= 0 ,0
Exp/Cntr=0.3,0.1

Type RM Length L Ch R = 1 ,5698    ,620,620,620
BEGIN DESCRIPTION:
UNT0587 IN SAND CR 8.0
END DESCRIPTION:
XS GIS Cut Line= 3
      3537764.93     10580601.44      3537147.71     10580804.58
      3536491.49     10580848.85
#Sta/Elev= 30
  4488.7  465.87  4492.8  465.87  4501.1  464.63  4506.4  464.89  4512.7  462.63
  4523.3  460.13  4532.9  458.72  4577.6  457.41  4639.1  456.89  4697.1     455
  4792.5  454.75  4839.1  455.53  4881.2  455.05  4912.8   454.1  4965.4  453.61
    4994  451.96  4996.8  451.46    5000  451.96  5071.1   452.6  5078.5  453.03
  5083.8  454.26  5102.3  454.23  5129.5  455.58  5154.1  456.95  5174.2  457.38
  5304.5  458.32  5442.2   458.6  5487.4  458.83  5645.2  459.43  5796.2  461.11
#Mann= 8 ,-1 , 0
  4488.7     .08       0  4577.6     .16       0    4994     .07       0
    5000     .16       0  5071.1     .12       0  5129.5     .05       0
  5442.2     .16       0  5487.4     .05       0
Bank Sta=4994,5000
XS Rating Curve= 0 ,0
Exp/Cntr=0.3,0.1

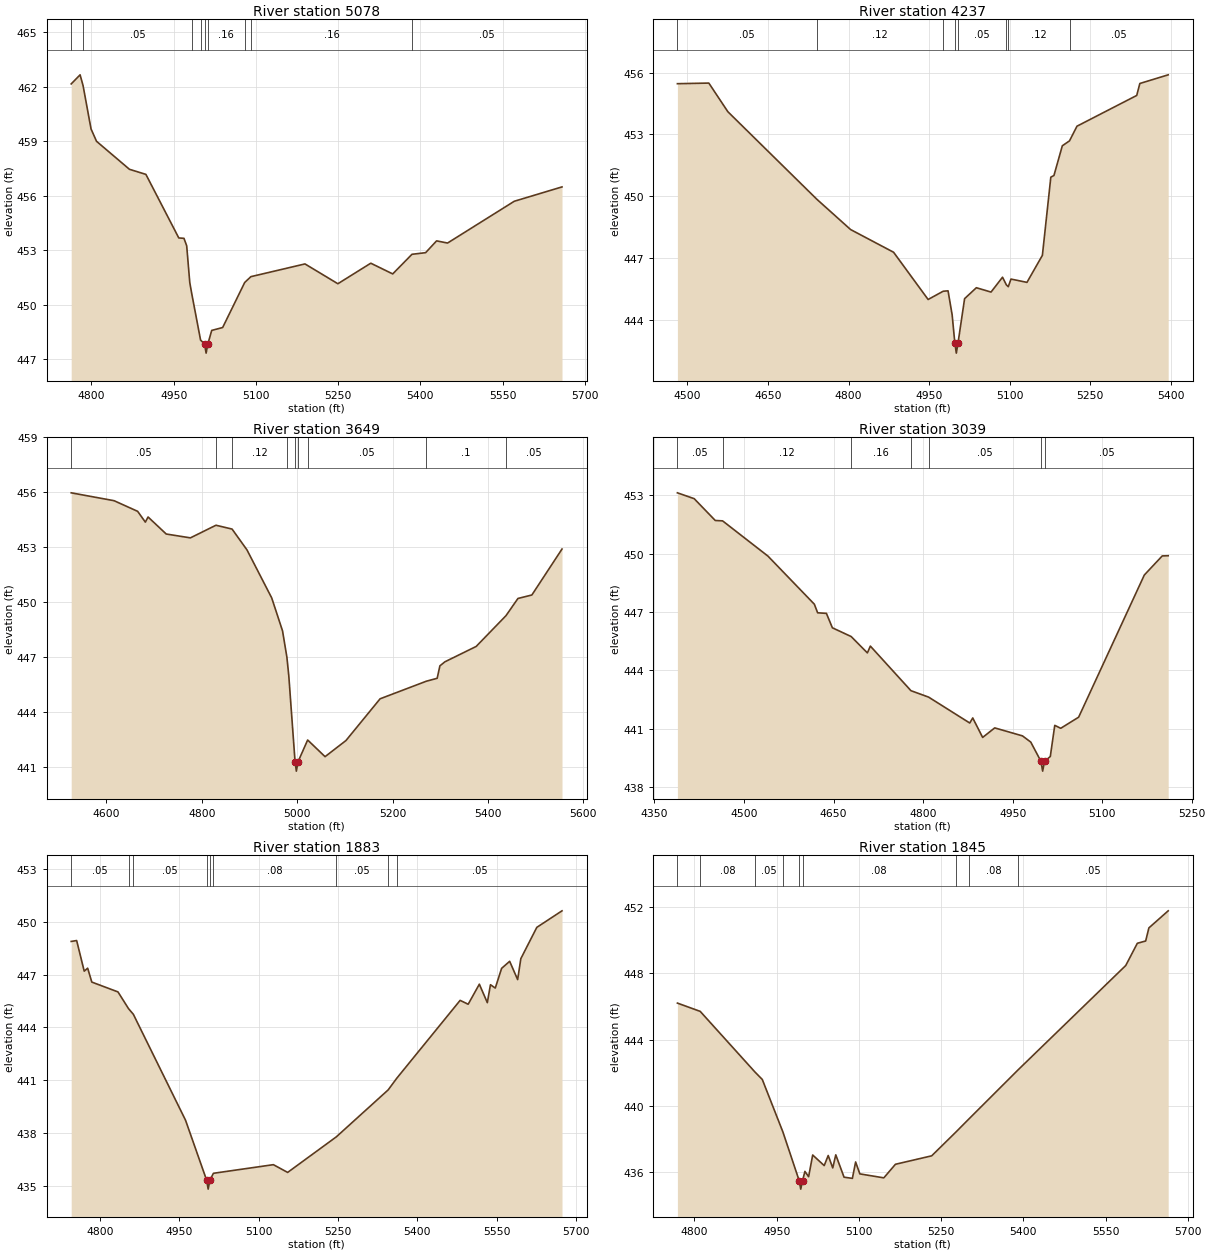
Type RM Length L Ch R = 1 ,5078    ,841,841,841
BEGIN DESCRIPTION:
UNT0587 IN SAND CR 7.0
END DESCRIPTION:
XS GIS Cut Line= 3
      3537788.29     10580372.29      3537035.73     10580387.91
      3536916.56     10580465.63
#Sta/Elev= 30
  4763.2  462.15  4779.4  462.65  4784.8  462.06  4799.4  459.67  4809.4  458.99
  4869.4  457.45  4899.4  457.17  4959.4  453.67  4968.8  453.65  4973.8  453.24
  4979.4  451.22  4982.8  450.64  4999.1  448.05  5006.4  447.83  5009.2  447.33
  5012.4  447.83  5019.4  448.58  5039.4  448.74  5079.6  451.22  5090.9  451.54
  5189.5  452.24  5249.5  451.15  5309.5  452.28  5349.5  451.69  5384.6  452.77
  5409.5  452.86  5429.5  453.51  5449.5  453.39  5571.2  455.69  5658.2  456.48
#Mann= 9 ,-1 , 0
  4763.2     .08       0  4784.8     .05       0  4982.8     .12       0
  4999.1     .16       0  5006.4     .07       0  5012.4     .16       0
  5079.6     .12       0  5090.9     .16       0  5384.6     .05       0
Bank Sta=5006.4,5012.4
XS Rating Curve= 0 ,0
Exp/Cntr=0.3,0.1

Type RM Length L Ch R = 1 ,4237    ,588,588,588
BEGIN DESCRIPTION:
UNT0587 IN SAND CR 6.0
END DESCRIPTION:
XS GIS Cut Line= 2
      3537412.48     10579841.43      3536625.73     10580305.86
#Sta/Elev= 30
  4481.3  455.46  4539.8  455.49  4575.3   454.1  4740.8  449.86  4803.7  448.39
  4883.7  447.29    4948     445    4976   445.4  4985.1  445.42  4992.7  444.26
  4997.7   442.9  5000.5   442.4  5003.7   442.9  5015.9  445.04  5037.8  445.57
  5065.1  445.36  5086.5  446.08  5093.6  445.71  5097.2  445.62  5102.2  445.99
    5132  445.83  5160.7  447.14  5176.4  450.93  5182.2  451.01  5197.8  452.45
  5211.2  452.69  5225.1   453.4  5336.3  454.89  5342.1  455.47  5394.9  455.89
#Mann= 8 ,-1 , 0
  4481.3     .05       0  4740.8     .12       0    4976     .05       0
  4997.7     .03       0  5003.7     .05       0  5093.6     .16       0
  5097.2     .12       0  5211.2     .05       0
Bank Sta=4997.7,5003.7
XS Rating Curve= 0 ,0
Exp/Cntr=0.3,0.1

Type RM Length L Ch R = 1 ,3649    ,610,610,610
BEGIN DESCRIPTION:
UNT0587 IN SAND CR 5.0
END DESCRIPTION:
XS GIS Cut Line= 2
      3537402.08      10579431.7      3536496.48     10579920.94
#Sta/Elev= 30
  4526.1  455.96    4616  455.53  4665.4  454.95  4681.6  454.36  4687.3  454.64
  4725.4  453.71  4776.1   453.5  4829.7  454.19  4863.5  453.98  4894.8  452.84
  4946.6  450.22  4969.3  448.42  4978.4  446.99  4982.4  445.98  4995.6  441.26
  4998.3  440.76  5001.6  441.26    5022  442.46  5058.5  441.55  5102.3  442.43
  5173.9  444.71  5270.8  445.67  5293.6  445.83  5299.3  446.51  5309.8  446.73
  5375.4  447.57  5437.9  449.25    5463  450.19  5492.2  450.38  5555.4  452.89
#Mann= 9 ,-1 , 0
  4526.1     .05       0  4829.7     .16       0  4863.5     .12       0
  4978.4     .16       0  4995.6     .07       0  5001.6     .16       0
    5022     .05       0  5270.8      .1       0  5437.9     .05       0
Bank Sta=4995.6,5001.6
XS Rating Curve= 0 ,0
Exp/Cntr=0.3,0.1

Type RM Length L Ch R = 1 ,3039    ,1156,1156,1156
BEGIN DESCRIPTION:
UNT0587 IN SAND CR 4.0
END DESCRIPTION:
XS GIS Cut Line= 3
      3537209.97     10579219.26      3536592.11     10579291.64
      3536392.09     10579291.64
#Sta/Elev= 30
  4388.5  453.12  4416.6  452.82  4451.9   451.7  4464.2  451.68  4540.2  449.87
  4617.9   447.4  4623.4  446.96  4638.1  446.93  4648.1  446.19  4679.6  445.74
  4706.7   444.9  4711.7  445.25  4779.7  442.96  4809.3  442.63  4878.2   441.3
  4883.2  441.56  4899.8  440.56    4920  441.05  4966.5  440.64  4980.4  440.32
  4997.5  439.33  5000.3  438.83  5003.5  439.33  5013.1  439.58  5020.6  441.18
  5030.6  441.03  5060.6   441.6  5170.6   448.9  5200.6  449.88  5210.6  449.89
#Mann= 7 ,-1 , 0
  4388.5     .05       0  4464.2     .12       0  4679.6     .16       0
  4779.7     .12       0  4809.3     .05       0  4997.5     .03       0
  5003.5     .05       0
Bank Sta=4997.5,5003.5
XS Rating Curve= 0 ,0
Exp/Cntr=0.3,0.1

Type RM Length L Ch R = 1 ,1883    ,38,38,38
BEGIN DESCRIPTION:
UNT0587 IN SAND CR 2.1
END DESCRIPTION:
XS GIS Cut Line= 3
      3536935.83     10578410.78      3536703.21     10578603.48
      3536361.56     10579127.23
#Sta/Elev= 30
    4746  448.88  4756.3  448.93  4770.6  447.19  4777.1  447.36  4784.9  446.57
  4834.4  446.01  4854.3  445.06  4863.4  444.74    4962  438.72    5002   435.3
  5004.8   434.8    5008   435.3  5014.7   435.7    5128  436.19    5155  435.75
  5246.9  437.77  5344.9  440.44  5361.1   441.1  5480.9  445.53  5496.1  445.31
  5517.2  446.45  5532.3   445.4  5538.2  446.42  5547.3  446.23  5559.3  447.35
  5574.5  447.75  5589.6  446.71  5595.6   447.9  5625.8  449.68  5673.4  450.62
#Mann= 9 ,-1 , 0
    4746     .05       0  4854.3     .08       0  4863.4     .05       0
    5002     .03       0    5008     .05       0  5014.7     .08       0
  5246.9     .05       0  5344.9     .08       0  5361.1     .05       0
Bank Sta=5002,5008
XS Rating Curve= 0 ,0
Exp/Cntr=0.3,0.1

Type RM Length L Ch R = 1 ,1845    ,70,70,70
BEGIN DESCRIPTION:
UNT0587 IN SAND CR 2.0
END DESCRIPTION:
XS GIS Cut Line= 3
      3536885.47      10578386.5      3536680.64     10578577.44
      3536346.34     10579093.62
#Sta/Elev= 30
    4769  446.21  4810.6  445.71  4910.7  442.04  4923.8   441.6  4961.4  438.43
  4991.2  435.48  4993.9  434.98  4997.2  435.48  5001.5  436.05  5008.3  435.73
  5015.7  437.04  5036.7   436.4    5044  437.01  5052.3  436.26  5057.8  437.05
  5072.9   435.7  5088.1  435.63    5094  436.62  5101.7   435.9  5145.4  435.66
  5166.6  436.48  5232.7  436.99  5276.7  438.42  5301.3  439.24  5390.6  442.19
  5586.6  448.48  5607.7  449.82  5622.9  449.96  5628.8  450.75    5664  451.78
#Mann= 9 ,-1 , 0
    4769     .05       0  4810.6     .08       0  4910.7     .05       0
  4961.4     .08       0  4991.2     .07       0  4997.2     .08       0
  5276.7     .05       0  5301.3     .08       0  5390.6     .05       0
Bank Sta=4991.2,4997.2
XS Rating Curve= 0 ,0
Exp/Cntr=0.3,0.1

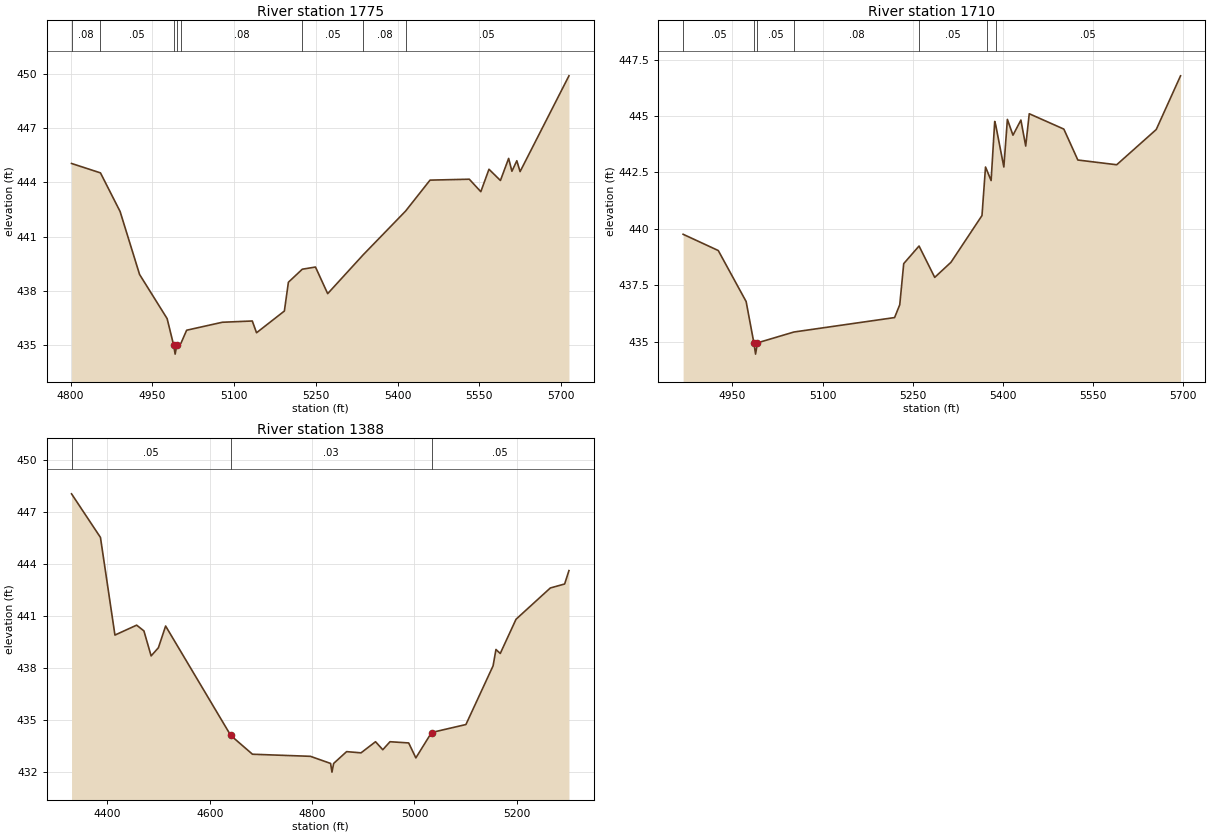
Type RM Length L Ch R = 1 ,1775    ,65,65,65
BEGIN DESCRIPTION:
UNT0587 IN SAND CR 3.0
END DESCRIPTION:
XS GIS Cut Line= 3
      3536788.28     10578323.97      3536599.04     10578596.53
      3536276.61     10579080.19
#Sta/Elev= 30
  4801.6  445.05  4854.7  444.53  4890.7   442.4  4926.5  438.92  4977.1  436.48
    4989  435.02  4991.8  434.52    4995  435.02  5002.3  435.11  5012.9  435.84
  5078.4  436.28  5133.4  436.35  5141.2   435.7  5192.3   436.9  5199.7  438.49
  5225.2  439.21  5249.4  439.33  5271.8  437.86  5336.8     440  5414.8  442.42
  5459.7  444.13  5531.8  444.18  5552.9  443.49  5567.9  444.73  5588.9  444.11
    5604  445.33    5610  444.62    5619   445.2    5625   444.6  5714.7  449.89
#Mann= 8 ,-1 , 0
  4801.6     .08       0  4854.7     .05       0    4989     .03       0
    4995     .05       0  5002.3     .08       0  5225.2     .05       0
  5336.8     .08       0  5414.8     .05       0
Bank Sta=4989,4995
XS Rating Curve= 0 ,0
Exp/Cntr=0.3,0.1

Type RM Length L Ch R = 1 ,1710    ,322,322,322
BEGIN DESCRIPTION:
UNT0587 IN SAND CR 2.2
END DESCRIPTION:
XS GIS Cut Line= 3
      3536675.42     10578315.33      3536625.09      10578494.1
      3536279.59     10579035.78
#Sta/Elev= 30
  4867.8  439.76  4926.3  439.04  4972.7  436.78  4985.6  434.95  4988.4  434.45
  4991.6  434.95  5052.3  435.43  5219.9  436.07  5228.5  436.64  5235.1  438.46
  5260.6  439.24  5286.7  437.85  5313.8  438.52  5365.4  440.59  5371.3  442.74
  5374.1  442.56  5380.6  442.14  5386.6  444.76  5388.2  444.61  5401.8  442.74
  5407.7  444.85    5417  444.15  5430.2  444.82  5438.2  443.67  5444.1   445.1
  5501.7  444.42    5525  443.05  5589.7  442.84  5655.5   444.4    5696  446.78
#Mann= 7 ,-1 , 0
  4867.8     .05       0  4985.6     .03       0  4991.6     .05       0
  5052.3     .08       0  5260.6     .05       0  5374.1     .08       0
  5388.2     .05       0
Bank Sta=4985.6,4991.6
XS Rating Curve= 0 ,0
Exp/Cntr=0.3,0.1

Type RM Length L Ch R = 1 ,1388    ,0,0,0
BEGIN DESCRIPTION:
UNT0587 IN SAND CR 1.0
END DESCRIPTION:
XS GIS Cut Line= 3
      3536842.08     10577841.67      3536392.11     10578291.64
      3536242.09     10578591.67
#Sta/Elev= 30
    4330  448.03  4386.5  445.52  4414.8   439.9  4457.2  440.47  4471.4  440.14
  4485.5   438.7  4499.7  439.17  4513.8  440.42  4641.1  434.12  4683.5  433.04
  4796.7  432.92  4836.1  432.51  4838.8  432.01  4842.1  432.51  4867.4  433.19
  4895.6  433.12  4923.9  433.76  4938.1   433.3  4952.2  433.76  4988.7  433.69
  5002.7  432.83  5033.4  434.29  5100.5  434.75  5153.6  438.13  5159.2  439.07
  5167.6  438.84  5198.4  440.81  5265.4  442.61  5293.4  442.84  5301.8  443.61
#Mann= 3 , 0 , 0
    4330     .05       0  4641.1     .03       0  5033.4     .05       0
Bank Sta=4641.1,5033.4
XS Rating Curve= 0 ,0
Exp/Cntr=0.3,0.1

Chan Stop Cuts=-1
Use User Specified Reach Order=0
Composite Channel Slope=5