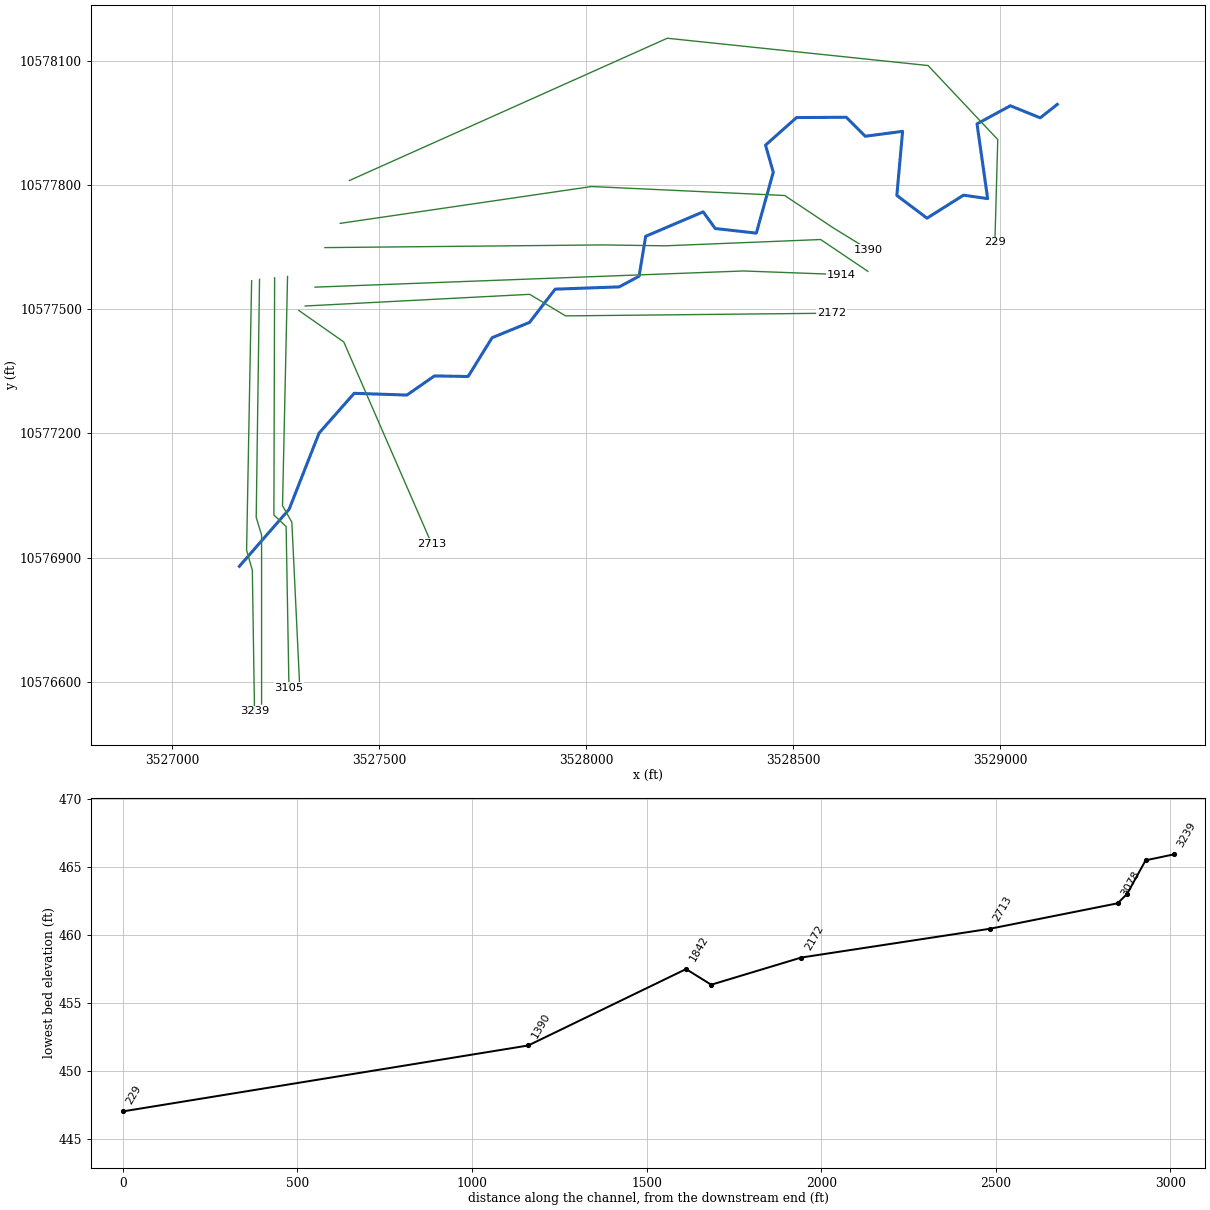
--- UNT0591 IN SAND CR.prj (project) ---

Proj Title=UNT0591 IN SAND CR Base Level Engineering
Current Plan=p01
Default Exp/Contr=0.3,0.1
English Units
Geom File=g01
Flow File=f01
Plan File=p01
Y Axis Title=Elevation
X Axis Title(PF)=Main Channel Distance
X Axis Title(XS)=Station
BEGIN DESCRIPTION:
UNT0591 IN SAND CR
END DESCRIPTION:
DSS Export Rating Curves= 0
DSS Export Rating Curve Sorted= 0
DSS Export Volume Flow Curves= 0
DXF OffsetX= 0
DXF OffsetY= 0
DXF ScaleX= 1
DXF ScaleY= 10

--- UNT0591 IN SAND CR.p01 (plan) ---

Plan Title=Multiple Run
Short Identifier=Multiple
Geom File=g01
Flow File=f01
Subcritical Flow
K Sum by GR= 0
Std Step Tol= 0.01
Critical Tol= 0.01
Num of Std Step Trials= 20
Max Error Tol= 0.3
Flow Tol Ratio= 0.001
Split Flow NTrial= 30
Split Flow Tol= 0.02
Split Flow Ratio= 0.02
Log Output Level= 0
Friction Slope Method= 1
Unsteady Friction Slope Method= 2
Unsteady Bridges Friction Slope Method= 1
Parabolic Critical Depth
Global Vel Dist=  1 , 1 , 1
Global Log Level= 0
CheckData=True
Encroach Param= -1, 0, 0, 0
BEGIN DESCRIPTION:
Multiple Run
END DESCRIPTION:

--- UNT0591 IN SAND CR.f01 (steady flow) ---

Flow Title=Multiple
Number of Profiles=7
Profile Names=10-year,25-year,50-year,1pct_min,100-year,1pct_plu,500-year
River Rch & RM= UNT0591 IN SAND ,Reach-1,3239
     849    1158    1411    1256    1698    2297    2452
Boundary for River Rch & Prof#=UNT0591 IN SAND ,Reach-1,1
Up Type=0
Dn Type=3
Dn Slope=0.005
Boundary for River Rch & Prof#=UNT0591 IN SAND ,Reach-1,2
Up Type=0
Dn Type=3
Dn Slope=0.005
Boundary for River Rch & Prof#=UNT0591 IN SAND ,Reach-1,3
Up Type=0
Dn Type=3
Dn Slope=0.005
Boundary for River Rch & Prof#=UNT0591 IN SAND ,Reach-1,4
Up Type=0
Dn Type=3
Dn Slope=0.005
Boundary for River Rch & Prof#=UNT0591 IN SAND ,Reach-1,5
Up Type=0
Dn Type=3
Dn Slope=0.005
Boundary for River Rch & Prof#=UNT0591 IN SAND ,Reach-1,6
Up Type=0
Dn Type=3
Dn Slope=0.005
Boundary for River Rch & Prof#=UNT0591 IN SAND ,Reach-1,7
Up Type=0
Dn Type=3
Dn Slope=0.005

--- UNT0591 IN SAND CR.g01 (geometry) ---

Geom Title=Existing Conditions
Program Version=4.10

River Reach=UNT0591 IN SAND ,Reach-1
Reach XY= 30
      3527162.09     10576878.82      3527282.29     10577016.47
       3527354.7     10577200.58      3527439.55     10577296.67
      3527566.97     10577292.48       3527633.4     10577338.65
      3527714.84     10577337.33      3527772.82       10577431.
      3527863.23     10577467.96      3527925.21     10577548.25
      3528080.07     10577553.81      3528127.98      10577579.5
      3528143.96     10577676.03      3528282.85     10577735.06
      3528312.01     10577694.78      3528411.32     10577683.67
      3528452.29     10577830.89      3528433.54     10577896.17
      3528508.54     10577962.83      3528628.68     10577963.53
      3528674.51     10577917.69      3528764.79      10577929.5
       3528750.9     10577774.64      3528823.82     10577719.78
      3528912.01     10577775.33      3528970.35       10577767.
      3528944.65     10577947.56      3529025.21     10577991.31
      3529097.43     10577962.14      3529138.75     10577994.75

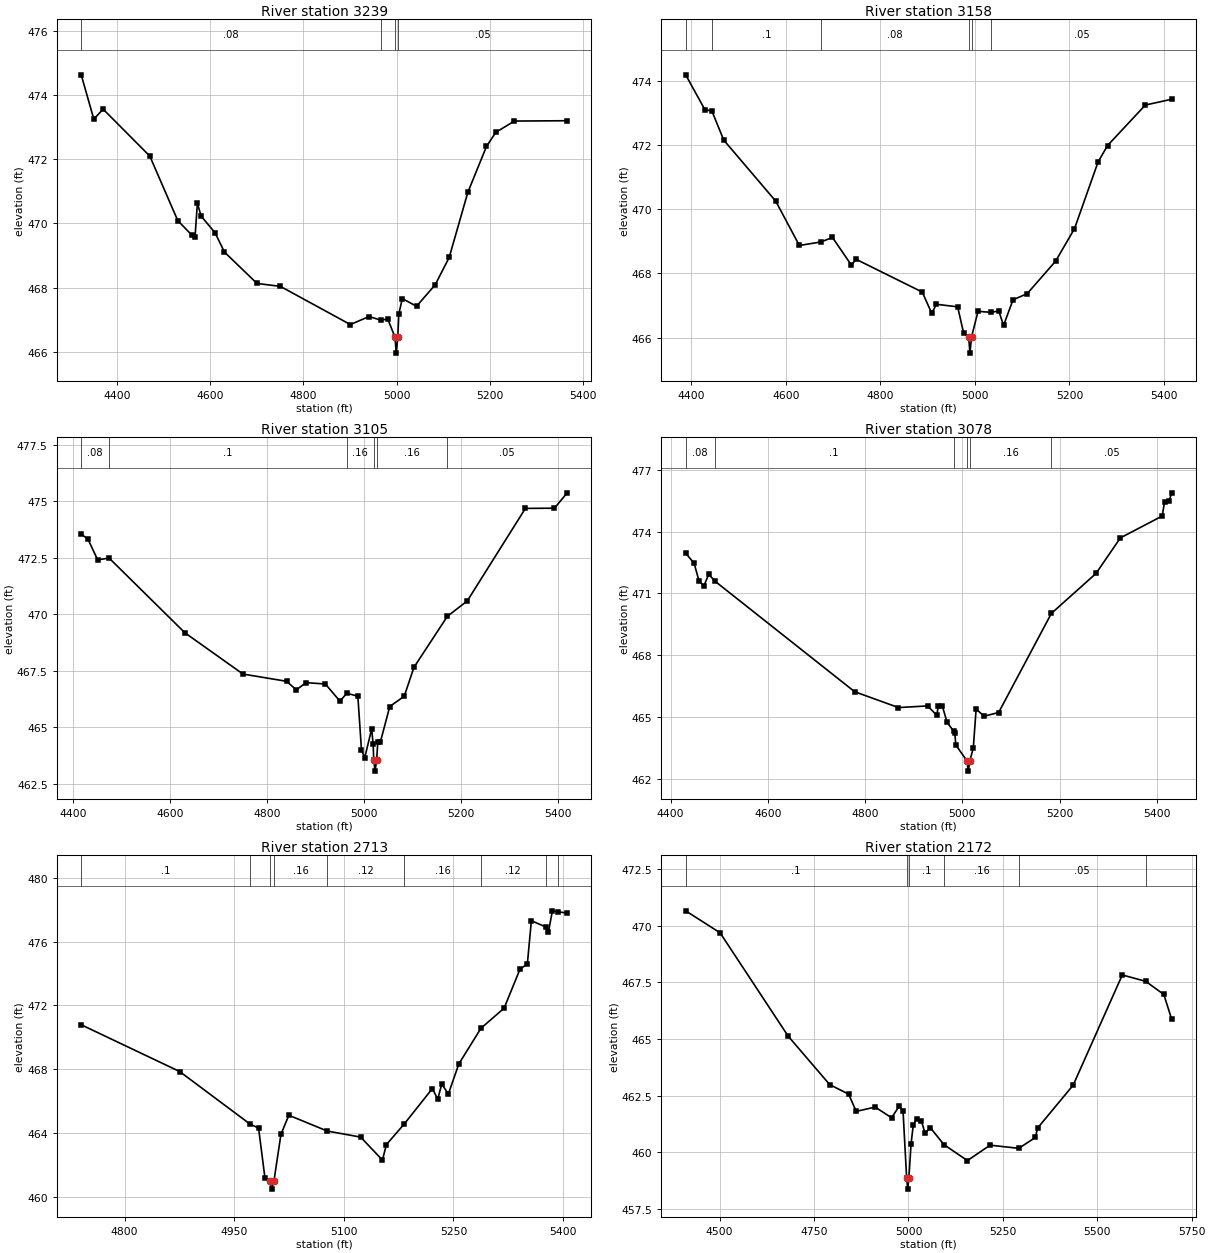
Type RM Length L Ch R = 1 ,3239    ,81,81,81
BEGIN DESCRIPTION:
UNT0591 IN SAND CR 4.2
END DESCRIPTION:
XS GIS Cut Line= 4
       3527191.7      10577568.6      3527179.55     10576917.58
      3527193.44     10576868.97      3527198.65     10576528.69
#Sta/Elev= 30
  4323.7  474.63  4350.7  473.25  4370.7  473.56  4470.7   472.1  4530.7  470.09
  4560.7  469.64  4567.8  469.59  4572.8  470.63  4580.7  470.23  4610.7  469.71
  4630.7  469.11  4700.7  468.13  4750.7  468.04  4900.8  466.85  4940.8   467.1
  4965.6  466.99    4981  467.02  4996.5  466.46  4999.2  465.96  5002.5  466.46
  5004.7  467.18  5012.2  467.66  5042.7  467.42  5082.7  468.09  5112.7  468.94
  5152.7  470.97  5192.7   472.4  5212.7  472.84  5252.7  473.19  5365.7   473.2
#Mann= 4 ,-1 , 0
  4323.7     .08       0  4965.6     .05       0  4996.5     .04       0
  5002.5     .05       0
Bank Sta=4996.5,5002.5
XS Rating Curve= 0 ,0
Exp/Cntr=0.3,0.1

Type RM Length L Ch R = 1 ,3158    ,53,53,53
BEGIN DESCRIPTION:
UNT0591 IN SAND CR 4.3
END DESCRIPTION:
XS GIS Cut Line= 4
       3527210.8     10577572.11      3527202.77     10576996.79
      3527215.79     10576954.47      3527215.79     10576546.02
#Sta/Elev= 30
  4388.2  474.18  4428.7   473.1  4443.8  473.05  4468.7  472.15  4578.7  470.25
  4628.7  468.87  4674.6  468.98  4698.7  469.12  4738.7  468.26  4748.7  468.44
  4888.7  467.42  4908.7  466.76  4918.7  467.04  4963.6  466.96  4976.3  466.14
  4986.9  466.02  4989.6  465.52  4992.9  466.02  5006.7  466.82  5034.1  466.79
  5050.7  466.83  5060.7  466.38  5080.7  467.18  5110.7  467.37  5170.7  468.38
  5210.7  469.39  5260.7  471.47  5280.7  471.98  5360.7  473.24  5416.3  473.42
#Mann= 6 ,-1 , 0
  4388.2     .08       0  4443.8      .1       0  4674.6     .08       0
  4986.9     .07       0  4992.9     .08       0  5034.1     .05       0
Bank Sta=4986.9,4992.9
XS Rating Curve= 0 ,0
Exp/Cntr=0.3,0.1

Type RM Length L Ch R = 1 ,3105    ,27,27,27
BEGIN DESCRIPTION:
UNT0591 IN SAND CR 4.0
END DESCRIPTION:
XS GIS Cut Line= 4
      3527247.26     10577575.55      3527245.52     10577002.65
      3527275.03     10576974.87      3527281.96     10576585.46
#Sta/Elev= 30
    4416  473.55  4429.9  473.33  4449.9  472.41  4473.6  472.49  4629.9  469.18
  4749.9  467.35  4839.9  467.03  4859.9  466.65  4879.9  466.97  4919.9  466.91
  4949.9  466.15  4964.1   466.5  4986.9  466.37  4994.4  463.98  5001.2  463.65
  5015.4  464.92  5018.5  464.23  5019.7  463.55  5022.4  463.05  5025.7  463.55
  5028.1  464.35  5033.5  464.35  5052.7  465.91  5082.7  466.37  5102.7  467.65
  5171.7  469.91  5212.7  470.59  5332.7  474.69  5392.7   474.7  5418.9  475.38
#Mann= 6 ,-1 , 0
    4416     .08       0  4473.6      .1       0  4964.1     .16       0
  5019.7     .07       0  5025.7     .16       0  5171.7     .05       0
Bank Sta=5019.7,5025.7
XS Rating Curve= 0 ,0
Exp/Cntr=0.3,0.1

Type RM Length L Ch R = 1 ,3078    ,365,365,365
BEGIN DESCRIPTION:
UNT0591 IN SAND CR 4.1
END DESCRIPTION:
XS GIS Cut Line= 4
      3527278.51     10577579.02      3527266.35     10577025.22
      3527288.92     10576985.29        3527308.     10576586.35
#Sta/Elev= 30
    4431  472.96  4448.4  472.46  4458.4  471.61  4468.4  471.36  4478.4  471.93
  4490.9   471.6  4778.5  466.22  4868.5  465.45  4928.5  465.53  4947.1  465.08
  4950.7  465.53  4958.5  465.54  4968.5  464.73  4981.8  464.31  4984.2  464.23
  4986.5  463.63  5009.3  462.86    5012  462.36  5015.3  462.86  5022.4  463.49
  5028.2  465.38  5044.5  465.03  5074.5  465.21    5183  470.03  5274.7  471.97
  5324.8   473.7  5410.7  474.76  5415.7  475.45  5424.9  475.48  5430.2  475.89
#Mann= 6 ,-1 , 0
    4431     .08       0  4490.9      .1       0  4981.8     .16       0
  5009.3     .07       0  5015.3     .16       0    5183     .05       0
Bank Sta=5009.3,5015.3
XS Rating Curve= 0 ,0
Exp/Cntr=0.3,0.1

Type RM Length L Ch R = 1 ,2713    ,541,541,541
BEGIN DESCRIPTION:
UNT0591 IN SAND CR 2.2
END DESCRIPTION:
XS GIS Cut Line= 3
       3527305.9     10577496.74       3527414.4     10577420.79
      3527627.06     10576932.54
#Sta/Elev= 30
  4740.6  470.79  4875.3  467.86  4972.1  464.55  4983.3  464.32  4992.1  461.16
  4998.3  460.99    5001  460.49  5004.3  460.99  5013.9  463.92  5024.7  465.12
  5077.3  464.13    5123  463.75  5152.8  462.31  5158.2  463.28  5182.4  464.56
  5221.1  466.79  5228.5  466.13    5234  467.08    5243  466.45  5257.4  468.34
  5287.6  470.57  5319.3  471.83  5341.1  474.28  5351.1   474.6  5356.6  477.31
  5376.3  476.92    5380  476.63  5385.4  477.93  5392.8  477.87  5405.6  477.79
#Mann= 9 ,-1 , 0
  4740.6      .1       0  4972.1     .16       0  4998.3     .07       0
  5004.3     .16       0  5077.3     .12       0  5182.4     .16       0
  5287.6     .12       0  5376.3     .05       0  5392.8     .16       0
Bank Sta=4998.3,5004.3
XS Rating Curve= 0 ,0
Exp/Cntr=0.3,0.1

Type RM Length L Ch R = 1 ,2172    ,258,258,258
BEGIN DESCRIPTION:
UNT0591 IN SAND CR 2.1
END DESCRIPTION:
XS GIS Cut Line= 4
      3527321.12      10577507.6      3527863.62     10577535.81
      3527950.42     10577483.73      3528592.83     10577490.24
#Sta/Elev= 30
  4410.1  470.65  4501.2  469.68  4681.5  465.12  4791.6  462.98  4841.7  462.56
  4861.7   461.8  4911.8  461.99  4955.4  461.52  4975.9  462.04  4985.7  461.82
  4995.2  458.87    4998  458.37  5001.2  458.87    5007  460.37  5012.9  461.22
  5021.5  461.46  5034.2  461.39    5044  460.83  5057.9  461.08  5094.3  460.33
  5156.2  459.63  5216.3  460.31  5292.1  460.17  5336.3  460.65  5341.8  461.06
  5436.3  462.96  5566.3  467.82  5628.2  467.54  5676.3  466.96    5697  465.87
#Mann= 6 ,-1 , 0
  4410.1      .1       0  4995.2     .07       0  5001.2      .1       0
  5094.3     .16       0  5292.1     .05       0  5628.2      .1       0
Bank Sta=4995.2,5001.2
XS Rating Curve= 0 ,0
Exp/Cntr=0.3,0.1

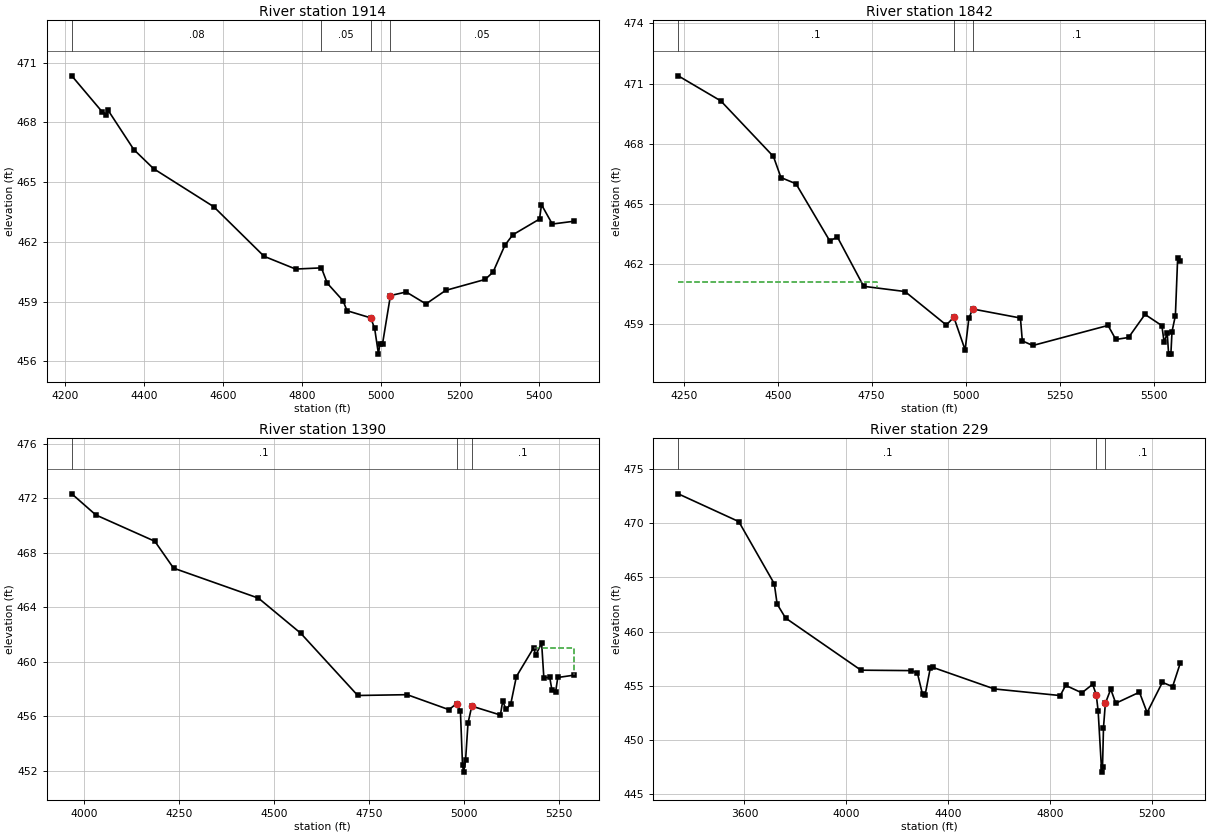
Type RM Length L Ch R = 1 ,1914    ,72,72,72
BEGIN DESCRIPTION:
UNT0591 IN SAND CR 2.0
END DESCRIPTION:
XS GIS Cut Line= 3
      3527344.98     10577553.17      3528380.11     10577592.23
      3528616.69     10577583.55
#Sta/Elev= 30
  4216.2  470.34  4293.4  468.53  4303.3  468.36  4308.3  468.61  4373.4  466.64
  4423.5  465.68    4576  463.77  4703.7  461.28  4783.7  460.64    4849   460.7
  4863.8  459.93  4903.8  459.05  4913.8  458.55  4973.9  458.19  4983.9  457.66
  4993.6  456.37  4996.9  456.87  5003.9  456.89  5023.9  459.31  5063.9  459.49
    5114  458.89    5164  459.57  5264.1  460.12  5284.1  460.49  5314.1  461.84
  5334.1  462.36  5401.8  463.15  5406.8  463.87  5434.2   462.9  5488.8  463.04
#Mann= 4 ,-1 , 0
  4216.2     .08       0    4849     .05       0  4973.9     .04       0
  5023.9     .05       0
Bank Sta=4973.9,5023.9
XS Rating Curve= 0 ,0
Exp/Cntr=0.3,0.1

Type RM Length L Ch R = 1 ,1842    ,452,452,452
BEGIN DESCRIPTION:
UNT0591 IN SAND CR 1.0
END DESCRIPTION:
XS GIS Cut Line= 5
      3527368.85     10577648.66      3528041.57     10577655.17
      3528191.31       10577653.      3528566.74     10577668.19
      3528680.94     10577591.32
#Sta/Elev= 30
  4235.3  471.39  4348.6  470.14  4488.6  467.37  4508.6  466.32  4548.6  466.01
  4638.6  463.16  4658.6  463.36  4728.6   460.9  4838.6  460.64  4948.6  458.97
  4968.6  459.36  4998.6  457.73  5008.6   459.3  5018.6  459.77  5145.8  459.32
  5150.8  458.18  5178.7  457.95  5378.9  458.95  5399.6  458.25  5433.5  458.35
  5477.2   459.5  5522.1  458.94  5528.1  458.12  5536.4  458.56  5540.1  457.52
  5546.1  457.52  5549.1  458.64  5558.1  459.44  5564.1  462.29  5571.2  462.14
#Mann= 3 , 0 , 0
  4235.3      .1       0  4968.6     .04       0  5018.6      .1       0
#XS Ineff= 2 , 0
         4763.78  461.12
Permanent Ineff=
       F       F
Bank Sta=4968.6,5018.6
XS Rating Curve= 0 ,0
Exp/Cntr=0.3,0.1

Type RM Length L Ch R = 1 ,1390    ,1161,1161,1161
BEGIN DESCRIPTION:
UNT0591 IN SAND CR 1.1
END DESCRIPTION:
XS GIS Cut Line= 5
      3527405.76     10577707.26      3528013.36     10577796.23
      3528479.94     10577774.52      3528597.12      10577696.4
       3528682.3     10577644.02
#Sta/Elev= 30
    3967  472.31  4030.4  470.76  4185.7  468.83    4235  466.86  4458.5  464.66
  4569.7  462.09    4720  457.52  4850.1  457.58  4960.2  456.48  4980.3  456.93
  4990.3  456.39  4995.9   452.4  4998.7   451.9  5003.9  452.78  5010.3  455.49
  5020.3  456.74  5095.6  456.09  5101.6   457.1  5110.7   456.5  5122.9   456.9
  5137.7  458.91  5182.8     461  5188.8   460.5  5204.2  461.36    5210  458.82
  5225.5  458.85  5231.3  457.92  5240.9  457.77  5246.7  458.84    5289  459.01
#Mann= 3 , 0 , 0
    3967      .1       0  4980.3     .05       0  5020.3      .1       0
#XS Ineff= 2 , 0
                         5183.13          461.01
Permanent Ineff=
       F       F
Bank Sta=4980.3,5020.3
XS Rating Curve= 0 ,0
Exp/Cntr=0.3,0.1

Type RM Length L Ch R = 1 ,229     ,0,0,0
BEGIN DESCRIPTION:
UNT0591 IN SAND CR 1.11
END DESCRIPTION:
XS GIS Cut Line= 5
      3527427.93      10577810.7      3528196.16     10578154.45
      3528826.37     10578088.48      3528994.77     10577909.66
      3528987.83     10577661.37
#Sta/Elev= 30
  3340.4  472.71  3577.9  470.15  3717.1  464.42  3728.4  462.54  3761.3  461.26
  4057.1  456.45  4255.2  456.41  4278.5  456.18  4298.6  454.22  4308.7  454.16
  4328.8  456.62  4338.8  456.71  4580.1  454.72  4838.8  454.11    4860  455.05
  4923.5  454.36    4966  455.15  4980.1  454.16  4987.4  452.68  5001.3  447.05
  5004.6  447.55  5008.4  451.16  5015.7  453.39  5036.8   454.7  5056.5   453.4
  5149.4  454.42  5179.4  452.54  5239.4  455.33  5279.4  454.93  5309.7  457.11
#Mann= 3 , 0 , 0
  3340.4      .1       0  4980.1     .05       0  5015.7      .1       0
#XS Ineff= 2 , 0
         4334.36  456.61
Permanent Ineff=
       F       F
Bank Sta=4980.1,5015.7
XS Rating Curve= 0 ,0
Exp/Cntr=0.3,0.1

Chan Stop Cuts=-1
Use User Specified Reach Order=0
Composite Channel Slope=5