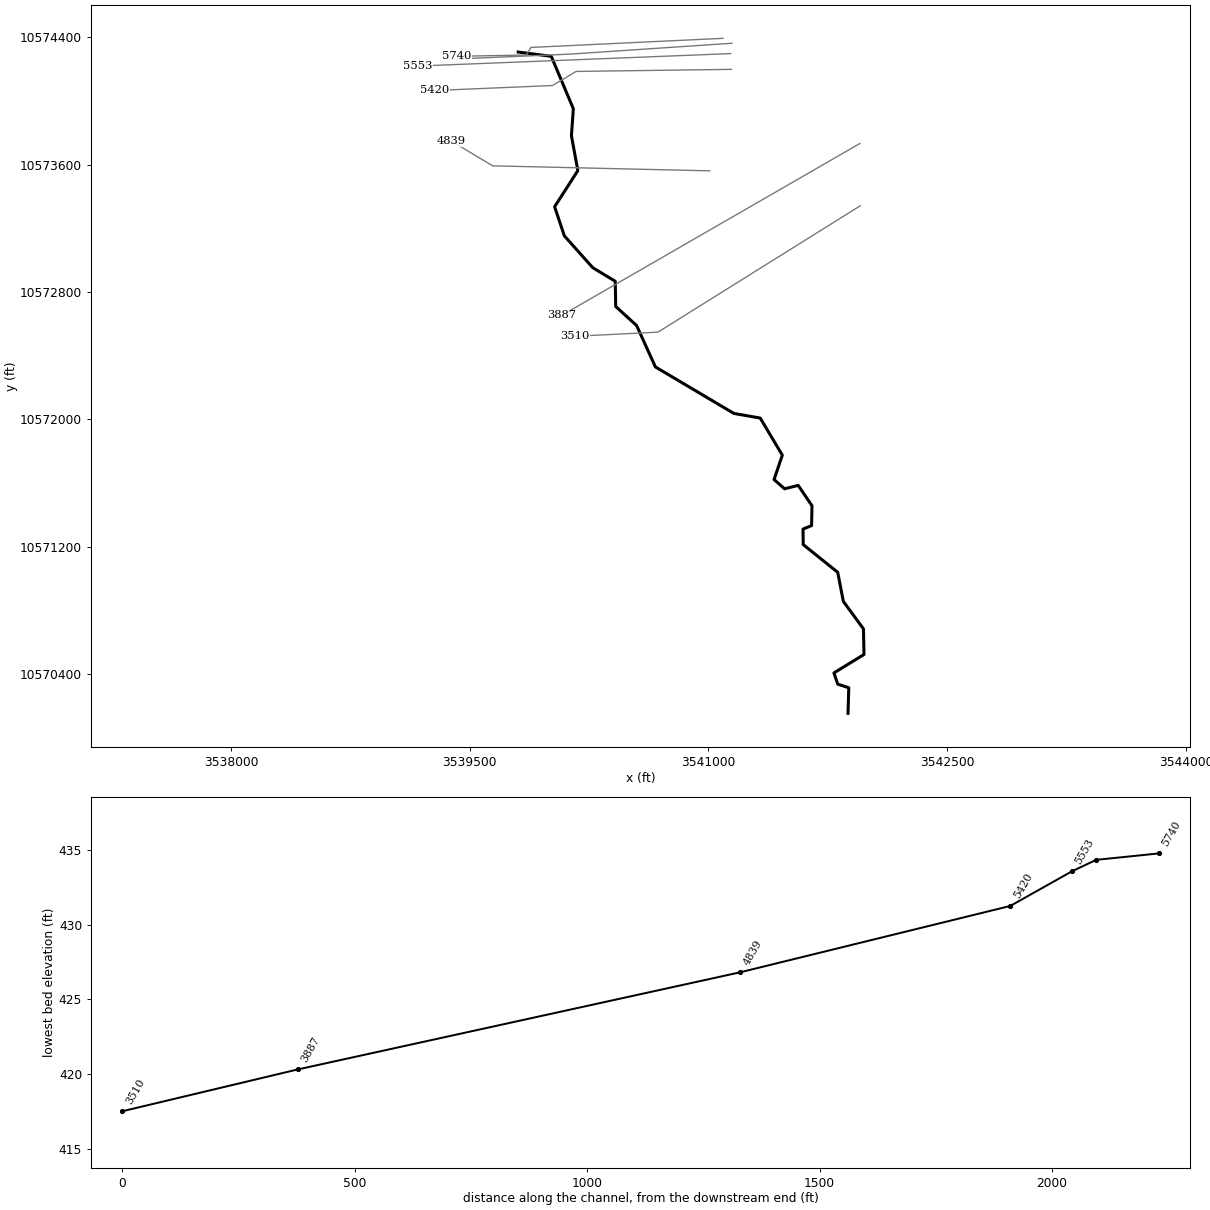
--- UNT0592 IN SAND CR.prj (project) ---

Proj Title=UNT0592 IN SAND CR Base Level Engineering
Current Plan=p01
Default Exp/Contr=0.3,0.1
English Units
Geom File=g01
Flow File=f01
Plan File=p01
BEGIN DESCRIPTION:
UNT0592 IN SAND CR
END DESCRIPTION:

--- UNT0592 IN SAND CR.p01 (plan) ---

Plan Title=Multiple Run
Short Identifier=Multiple
Geom File=g01
Flow File=f01
Subcritical Flow
K Sum by GR= 0
Std Step Tol= 0.01
Critical Tol= 0.01
Num of Std Step Trials= 20
Max Error Tol= 0.3
Flow Tol Ratio= 0.001
Split Flow NTrial= 30
Split Flow Tol= 0.02
Split Flow Ratio= 0.02
Log Output Level= 0
Friction Slope Method= 1
Unsteady Friction Slope Method= 2
Unsteady Bridges Friction Slope Method= 1
Parabolic Critical Depth
Global Vel Dist=  1 , 1 , 1
Global Log Level= 0
CheckData=True
Encroach Param= -1, 0, 0, 0
BEGIN DESCRIPTION:
Multiple Run
END DESCRIPTION:

--- UNT0592 IN SAND CR.f01 (steady flow) ---

Flow Title=Multiple
Number of Profiles=7
Profile Names=10-year,25-year,50-year,1pct_min,100-year,1pct_plu,500-year
River Rch & RM= UNT0592 IN SAND ,Reach-1,5740
     510     666     787     681     920    1245    1252
Boundary for River Rch & Prof#=UNT0592 IN SAND ,Reach-1,1
Up Type=0
Dn Type=3
Dn Slope=0.005
Boundary for River Rch & Prof#=UNT0592 IN SAND ,Reach-1,2
Up Type=0
Dn Type=3
Dn Slope=0.005
Boundary for River Rch & Prof#=UNT0592 IN SAND ,Reach-1,3
Up Type=0
Dn Type=3
Dn Slope=0.005
Boundary for River Rch & Prof#=UNT0592 IN SAND ,Reach-1,4
Up Type=0
Dn Type=3
Dn Slope=0.005
Boundary for River Rch & Prof#=UNT0592 IN SAND ,Reach-1,5
Up Type=0
Dn Type=3
Dn Slope=0.005
Boundary for River Rch & Prof#=UNT0592 IN SAND ,Reach-1,6
Up Type=0
Dn Type=3
Dn Slope=0.005
Boundary for River Rch & Prof#=UNT0592 IN SAND ,Reach-1,7
Up Type=0
Dn Type=3
Dn Slope=0.005

--- UNT0592 IN SAND CR.g01 (geometry) ---

Geom Title=Existing Conditions

River Reach=UNT0592 IN SAND ,Reach-1
Reach XY= 30
      3539804.52     10574307.79      3540012.13     10574281.25
      3540150.99     10573951.53      3540138.90     10573782.02
      3540179.21     10573562.93      3540033.31     10573335.94
      3540094.55     10573152.65      3540273.17     10572952.76
      3540414.18     10572867.51      3540417.21     10572709.07
      3540548.50     10572589.36      3540666.61     10572329.22
      3541159.72     10572037.03      3541325.19     10572008.04
      3541464.08     10571774.87      3541412.11     10571621.64
      3541478.04     10571563.54      3541563.93     10571584.89
      3541650.51     10571456.94      3541647.97     10571332.20
      3541594.02     10571310.18      3541595.46     10571212.76
      3541812.18     10571038.72      3541847.55     10570855.69
      3541973.93     10570683.47      3541977.43     10570522.30
      3541788.41     10570406.54      3541812.29     10570336.02
      3541881.73     10570313.23      3541876.93     10570152.27

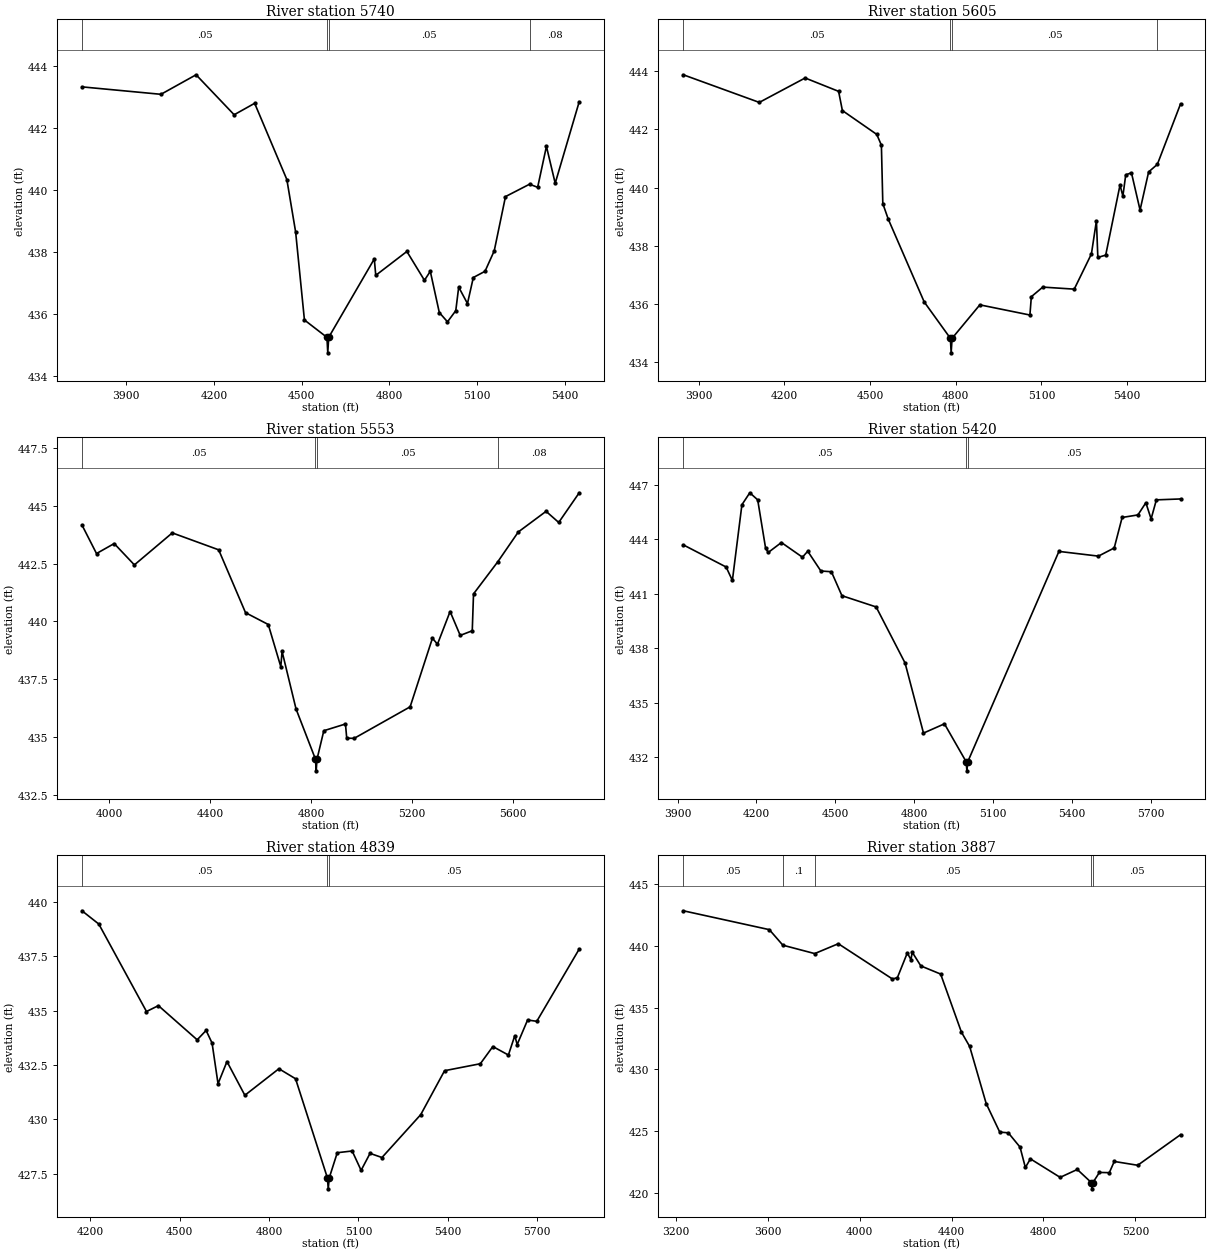
Type RM Length L Ch R = 1,5740,135,135,135
BEGIN DESCRIPTION:
UNT0592 IN SAND CR 3.1
END DESCRIPTION:
XS GIS Cut Line= 4
      3541091.91     10574394.07      3539884.47     10574336.93
      3539855.83     10574289.18      3539420.06     10574281.37
#Sta/Elev= 30
  3748.6  443.33  4018.7  443.09  4138.8  443.72  4269.0  442.43  4339.1  442.80
  4449.2  440.34  4479.2  438.65  4509.3  435.81  4586.3  435.25  4589.1  434.75
  4592.3  435.25  4748.2  437.78  4753.2  437.25  4859.6  438.02  4919.7  437.09
  4939.7  437.38  4970.5  436.05  4998.5  435.75  5026.8  436.11  5036.8  436.87
  5066.8  436.34  5086.8  437.18  5126.8  437.38  5158.3  438.04  5196.8  439.79
  5279.1  440.19  5306.8  440.09  5336.8  441.41  5366.8  440.22  5448.9  442.85
#Mann=4,-1,0
  3748.6    0.05       0  4586.3    0.04       0  4592.3    0.05       0
  5279.1    0.08       0
Bank Sta=4586.3,4592.3
Exp/Cntr=0.3,0.1

Type RM Length L Ch R = 1,5605,52,52,52
BEGIN DESCRIPTION:
UNT0592 IN SAND CR 3.0
END DESCRIPTION:
XS GIS Cut Line= 3
      3541147.45     10574363.17      3540130.92     10574294.90
      3539410.49     10574264.22
#Sta/Elev= 30
  3846.8  443.88  4112.7  442.93  4273.1  443.77  4390.2  443.31  4403.4  442.65
  4523.7  441.83  4539.9  441.46  4544.9  439.45  4563.8  438.92  4689.7  436.07
  4781.3  434.82  4784.0  434.32  4787.3  434.82  4884.4  435.97  5059.6  435.62
  5064.6  436.25  5104.6  436.58  5214.7  436.51  5274.8  437.72  5292.3  438.86
  5297.3  437.60  5324.8  437.68  5374.9  440.09  5384.9  439.71  5394.9  440.44
  5414.9  440.51  5445.0  439.23  5475.0  440.54  5505.5  440.80  5586.7  442.88
#Mann=4,-1,0
  3846.8    0.05       0  4781.3    0.03       0  4787.3    0.05       0
  5505.5    0.08       0
Bank Sta=4781.3,4787.3
Exp/Cntr=0.3,0.1

Type RM Length L Ch R = 1,5553,133,133,133
BEGIN DESCRIPTION:
UNT0592 IN SAND CR 1.0
END DESCRIPTION:
XS GIS Cut Line= 2
      3541139.68     10574298.07      3539170.93     10574219.95
#Sta/Elev= 30
  3892.2  444.16  3949.8  442.93  4019.9  443.36  4099.9  442.44  4250.1  443.82
  4433.9  443.09  4540.3  440.38  4630.4  439.87  4680.1  438.05  4685.1  438.71
  4740.4  436.23  4817.5  434.06  4820.3  433.56  4823.5  434.06  4850.5  435.29
  4936.3  435.58  4941.3  434.97  4970.6  434.96  5192.5  436.32  5280.9  439.28
  5300.9  439.02  5350.9  440.43  5391.0  439.40  5438.7  439.60  5443.7  441.19
  5540.2  442.58  5621.1  443.86  5731.2  444.75  5781.3  444.27  5862.5  445.55
#Mann=4,-1,0
  3892.2    0.05       0  4817.5    0.03       0  4823.5    0.05       0
  5540.2    0.08       0
Bank Sta=4817.5,4823.5
Exp/Cntr=0.3,0.1

Type RM Length L Ch R = 1,5420,581,581,581
BEGIN DESCRIPTION:
UNT0592 IN SAND CR 2.0
END DESCRIPTION:
XS GIS Cut Line= 4
      3541144.83     10574199.11      3540168.30     10574186.09
      3540019.87     10574097.55      3539280.27     10574066.30
#Sta/Elev= 30
  3921.9  443.69  4084.6  442.47  4108.4  441.73  4144.6  445.90  4174.6  446.56
  4204.6  446.17  4234.6  443.51  4244.6  443.27  4294.7  443.82  4374.7  443.01
  4394.7  443.34  4444.7  442.25  4484.7  442.21  4524.7  440.89  4654.7  440.27
  4764.7  437.18  4834.7  433.32  4914.3  433.83  4996.9  431.74  4999.6  431.24
  5002.9  431.74  5349.4  443.33  5499.5  443.07  5559.5  443.52  5589.6  445.20
  5649.6  445.34  5679.7  446.01  5699.7  445.12  5719.7  446.17  5811.6  446.22
#Mann=3,-1,0
  3921.9    0.05       0  4996.9    0.03       0  5002.9    0.05       0
Bank Sta=4996.9,5002.9
Exp/Cntr=0.3,0.1

Type RM Length L Ch R = 1,4839,952,952,952
BEGIN DESCRIPTION:
UNT0592 IN SAND CR 2.1
END DESCRIPTION:
XS GIS Cut Line= 3
      3541008.57     10573561.53      3539644.02     10573592.78
      3539383.61     10573749.03
#Sta/Elev= 30
  4172.3  439.59  4228.8  438.98  4388.8  434.96  4428.8  435.23  4558.9  433.66
  4588.9  434.09  4608.9  433.51  4628.9  431.64  4658.9  432.66  4718.9  431.11
  4833.2  432.33  4889.0  431.87  4996.0  427.31  4998.7  426.81  5002.0  427.31
  5029.0  428.47  5079.0  428.55  5109.0  427.66  5139.0  428.44  5179.0  428.25
  5309.1  430.22  5389.1  432.24  5509.1  432.56  5551.1  433.35  5603.3  432.96
  5624.7  433.85  5632.7  433.44  5667.7  434.57  5698.5  434.51  5840.9  437.83
#Mann=3,-1,0
  4172.3    0.05       0  4996.0    0.03       0  5002.0    0.05       0
Bank Sta=4996,5002
Exp/Cntr=0.3,0.1

Type RM Length L Ch R = 1,3887,377,377,377
BEGIN DESCRIPTION:
UNT0592 IN SAND CR 5.0
END DESCRIPTION:
XS GIS Cut Line= 2
      3541951.80     10573733.37      3540076.94     10572652.73
#Sta/Elev= 30
  3232.7  442.86  3607.0  441.33  3666.0  440.07  3804.5  439.39  3907.3  440.19
  4142.9  437.33  4164.4  437.44  4207.5  439.44  4223.3  438.90  4229.1  439.50
  4266.4  438.39  4352.6  437.73  4443.1  433.02  4478.9  431.86  4550.9  427.23
  4609.8  424.92  4647.1  424.86  4698.2  423.70  4721.3  422.05  4743.3  422.75
  4872.7  421.25  4947.3  421.89  5009.0  420.82  5011.7  420.32  5015.0  420.82
  5043.6  421.65  5086.7  421.63  5108.2  422.54  5210.2  422.23  5396.7  424.71
#Mann=5,-1,0
  3232.7    0.05       0  3666.0     0.1       0  3804.5    0.05       0
  5009.0    0.03       0  5015.0    0.05       0
Bank Sta=5009,5015
Exp/Cntr=0.3,0.1

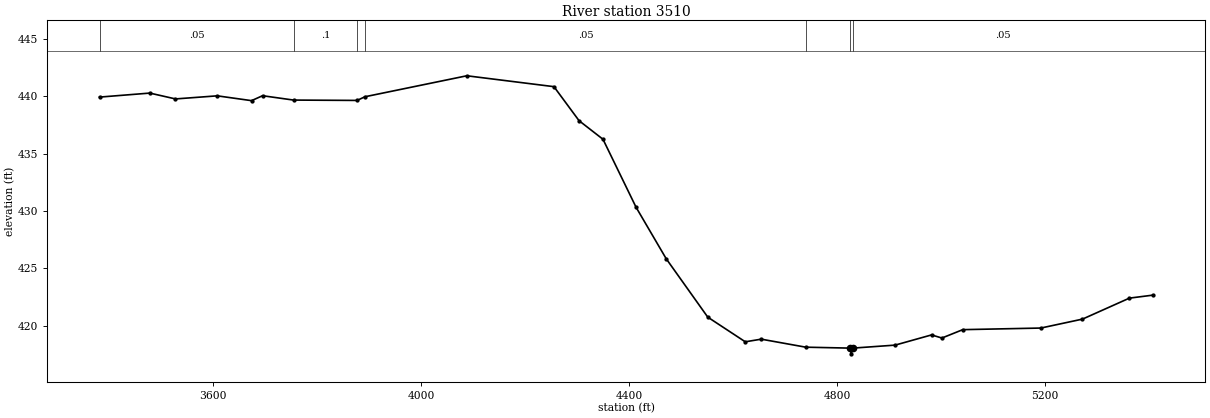
Type RM Length L Ch R = 1,3510,0,0,0
BEGIN DESCRIPTION:
UNT0592 IN SAND CR 6.0
END DESCRIPTION:
XS GIS Cut Line= 3
      3541954.10     10573342.06      3540682.37     10572547.77
      3540157.21     10572521.73
#Sta/Elev= 30
  3381.6  439.93  3478.3  440.28  3527.7  439.77  3608.0  440.04  3673.9  439.62
  3695.1  440.05  3754.8  439.67  3876.9  439.64  3892.0  439.96  4087.9  441.79
  4255.4  440.84  4303.7  437.87  4349.7  436.25  4413.4  430.31  4471.2  425.83
  4551.2  420.73  4623.3  418.58  4654.0  418.81  4739.7  418.11  4824.4  418.03
  4827.1  417.53  4830.4  418.03  4911.3  418.29  4981.4  419.18  5001.4  418.91
  5041.5  419.64  5191.6  419.78  5271.7  420.56  5361.9  422.39  5406.8  422.65
#Mann=7,-1,0
  3381.6    0.05       0  3754.8     0.1       0  3876.9    0.16       0
  3892.0    0.05       0  4739.7     0.1       0  4824.4    0.03       0
  4830.4    0.05       0
Bank Sta=4824.4,4830.4
Exp/Cntr=0.3,0.1

Chan Stop Cuts=-1