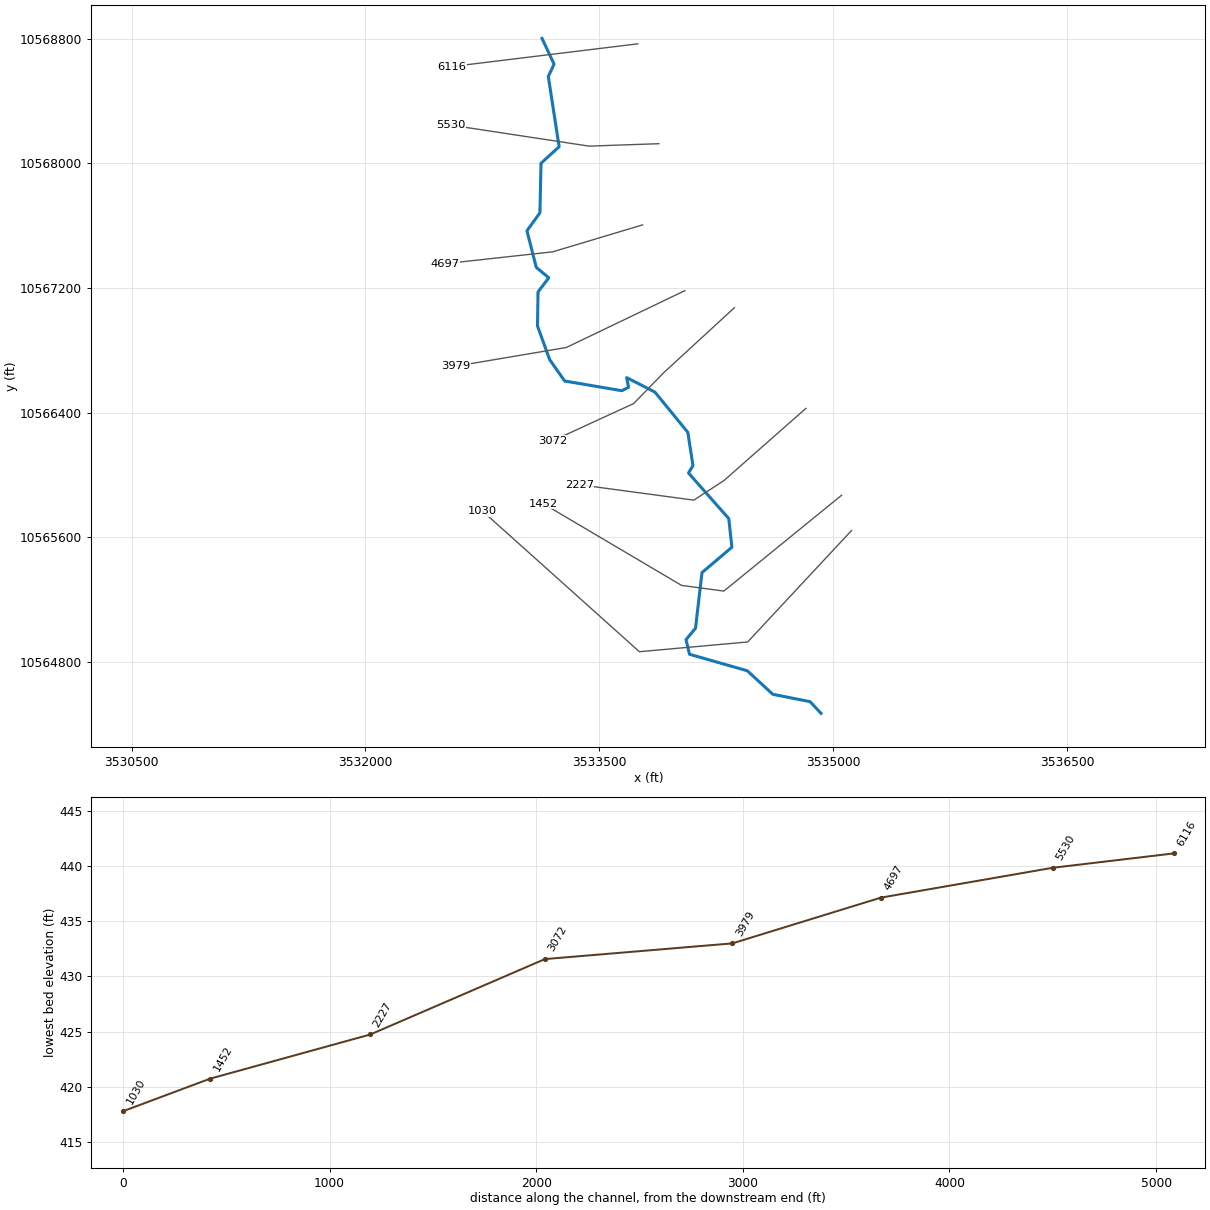
--- UNT0613 IN SAND CR.prj (project) ---

Proj Title=UNT0613 IN SAND CR Base Level Engineering
Current Plan=p01
Default Exp/Contr=0.3,0.1
English Units
Geom File=g01
Flow File=f01
Plan File=p01
BEGIN DESCRIPTION:
UNT0613 IN SAND CR
END DESCRIPTION:

--- UNT0613 IN SAND CR.p01 (plan) ---

Plan Title=Multiple Run
Short Identifier=Multiple
Geom File=g01
Flow File=f01
Subcritical Flow
K Sum by GR= 0
Std Step Tol= 0.01
Critical Tol= 0.01
Num of Std Step Trials= 20
Max Error Tol= 0.3
Flow Tol Ratio= 0.001
Split Flow NTrial= 30
Split Flow Tol= 0.02
Split Flow Ratio= 0.02
Log Output Level= 0
Friction Slope Method= 1
Unsteady Friction Slope Method= 2
Unsteady Bridges Friction Slope Method= 1
Parabolic Critical Depth
Global Vel Dist=  1 , 1 , 1
Global Log Level= 0
CheckData=True
Encroach Param= -1, 0, 0, 0
BEGIN DESCRIPTION:
Multiple Run
END DESCRIPTION:

--- UNT0613 IN SAND CR.f01 (steady flow) ---

Flow Title=Multiple
Number of Profiles=7
Profile Names=10-year,25-year,50-year,1pct_min,100-year,1pct_plu,500-year
River Rch & RM= UNT0613 IN SAND ,Reach-1,6116
     935    1279    1561    1391    1882    2545    2724
Boundary for River Rch & Prof#=UNT0613 IN SAND ,Reach-1,1
Up Type=0
Dn Type=3
Dn Slope=0.005
Boundary for River Rch & Prof#=UNT0613 IN SAND ,Reach-1,2
Up Type=0
Dn Type=3
Dn Slope=0.005
Boundary for River Rch & Prof#=UNT0613 IN SAND ,Reach-1,3
Up Type=0
Dn Type=3
Dn Slope=0.005
Boundary for River Rch & Prof#=UNT0613 IN SAND ,Reach-1,4
Up Type=0
Dn Type=3
Dn Slope=0.005
Boundary for River Rch & Prof#=UNT0613 IN SAND ,Reach-1,5
Up Type=0
Dn Type=3
Dn Slope=0.005
Boundary for River Rch & Prof#=UNT0613 IN SAND ,Reach-1,6
Up Type=0
Dn Type=3
Dn Slope=0.005
Boundary for River Rch & Prof#=UNT0613 IN SAND ,Reach-1,7
Up Type=0
Dn Type=3
Dn Slope=0.005

--- UNT0613 IN SAND CR.g01 (geometry) ---

Geom Title=Existing Conditions

River Reach=UNT0613 IN SAND ,Reach-1
Reach XY= 30
      3533132.11     10568801.64      3533209.57     10568636.10
      3533172.64     10568556.97      3533242.01     10568106.37
      3533125.81     10568000.17      3533118.84     10567682.61
      3533035.59     10567566.86      3533095.35     10567332.67
      3533175.64     10567265.76      3533106.76     10567175.13
      3533103.30     10566956.56      3533181.35     10566740.79
      3533277.36     10566603.61      3533643.77     10566541.51
      3533687.20     10566563.20      3533675.30     10566625.46
      3533856.42     10566532.61      3534067.62     10566274.15
      3534100.57     10566060.98      3534072.15     10566013.21
      3534330.37     10565720.89      3534350.07     10565537.11
      3534158.45     10565374.61      3534116.70     10565017.41
      3534055.87     10564944.49      3534078.30     10564850.78
      3534448.85     10564745.15      3534612.85     10564593.82
      3534851.37     10564547.05      3534922.11     10564471.64

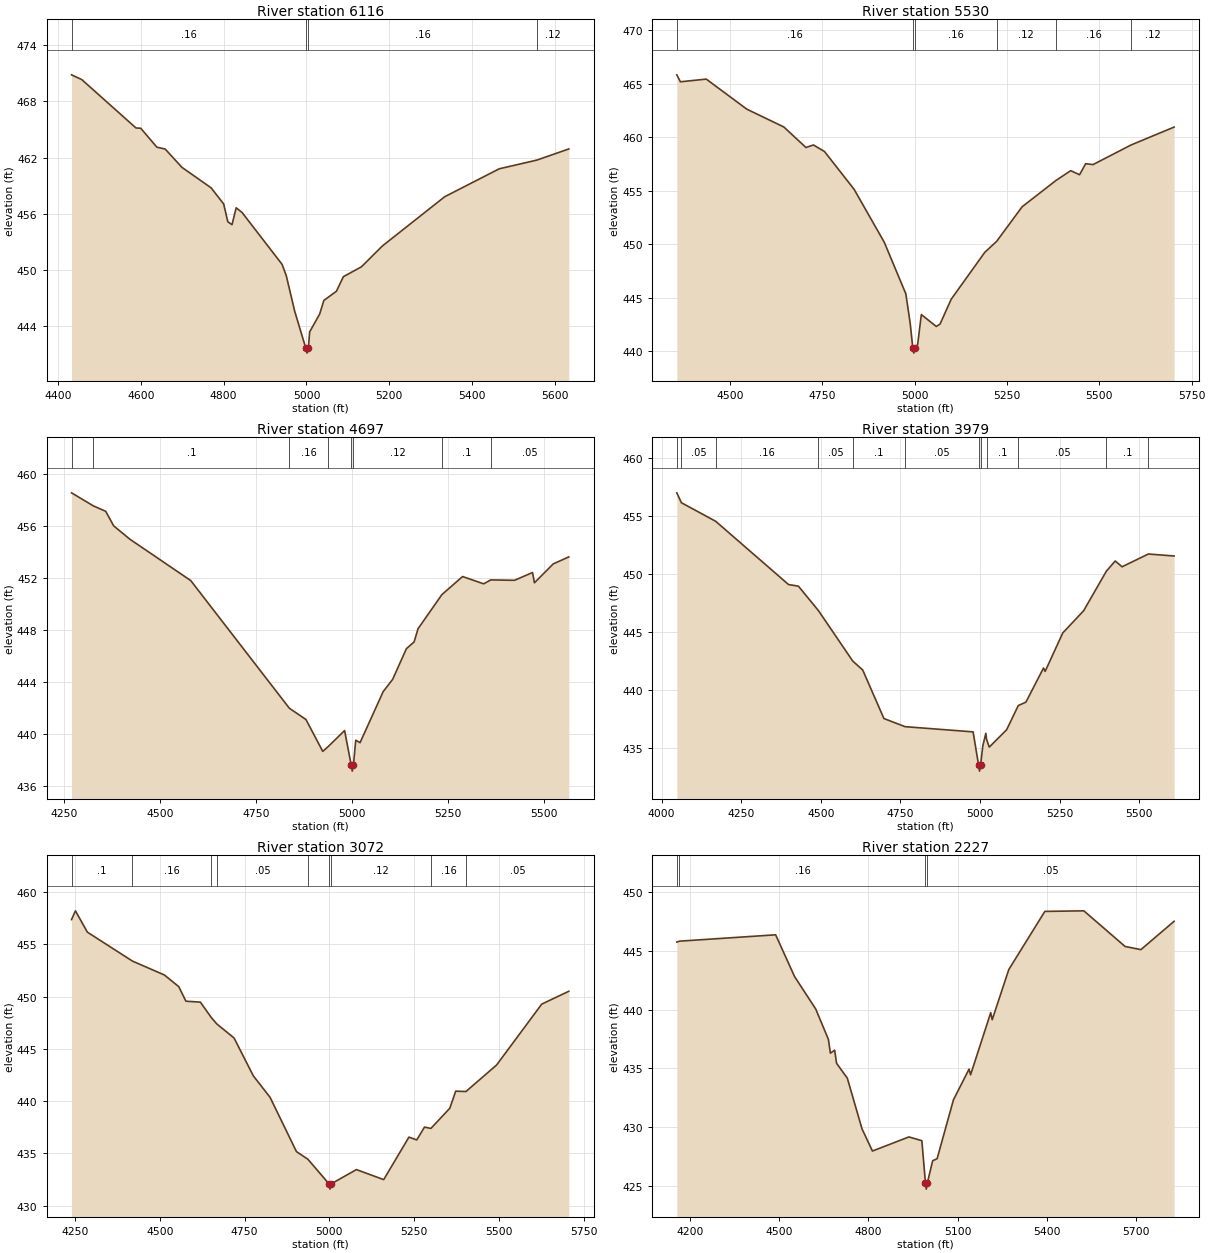
Type RM Length L Ch R = 1,6116,586,586,586
BEGIN DESCRIPTION:
UNT0613 IN SAND CR 12.0
END DESCRIPTION:
XS GIS Cut Line= 2
      3533746.45     10568766.47      3532555.42     10568620.84
#Sta/Elev= 30
  4433.1  470.84  4457.6  470.34  4588.6  465.17  4600.1  465.14  4639.0  463.12
  4659.1  462.92  4699.4  460.97  4769.9  458.78  4800.2  457.06  4810.2  455.16
  4820.3  454.85  4830.4  456.65  4844.6  456.15  4941.2  450.61  4951.3  449.40
  4971.4  445.64  4998.6  441.64  5001.4  441.14  5004.6  441.64  5007.6  443.40
  5031.9  445.32  5041.9  446.76  5072.2  447.74  5089.1  449.30  5132.6  450.35
  5183.0  452.57  5333.5  457.83  5465.1  460.81  5555.9  461.74  5633.0  462.93
#Mann=4,-1,0
  4433.1    0.16       0  4998.6    0.07       0  5004.6    0.16       0
  5555.9    0.12       0
Bank Sta=4998.6,5004.6
Exp/Cntr=0.3,0.1

Type RM Length L Ch R = 1,5530,833,833,833
BEGIN DESCRIPTION:
UNT0613 IN SAND CR 11.0
END DESCRIPTION:
XS GIS Cut Line= 3
      3533881.83     10568125.84      3533433.95     10568110.22
      3532545.22     10568245.35
#Sta/Elev= 30
  4355.4  465.83  4365.1  465.18  4435.2  465.43  4545.2  462.62  4645.3  460.96
  4705.3  459.04  4725.4  459.28  4755.4  458.67  4835.8  455.13  4917.3  450.20
  4975.8  445.38  4987.5  442.65  4994.6  440.34  4997.4  439.84  5000.6  440.34
  5007.7  440.63  5017.8  443.44  5058.3  442.33  5068.4  442.55  5098.8  444.88
  5189.8  449.26  5221.6  450.27  5290.9  453.51  5382.3  455.96  5422.4  456.88
  5446.4  456.50  5462.9  457.53  5483.1  457.45  5586.0  459.28  5702.5  460.95
#Mann=6,-1,0
  4355.4    0.16       0  4994.6    0.07       0  5000.6    0.16       0
  5221.6    0.12       0  5382.3    0.16       0  5586.0    0.12       0
Bank Sta=4994.6,5000.6
Exp/Cntr=0.3,0.1

Type RM Length L Ch R = 1,4697,718,718,718
BEGIN DESCRIPTION:
UNT0613 IN SAND CR 9.0
END DESCRIPTION:
XS GIS Cut Line= 3
      3533777.32     10567604.99      3533200.88     10567432.20
      3532511.61     10567356.49
#Sta/Elev= 30
  4269.5  458.54  4326.6  457.53  4358.5  457.12  4379.3  456.00  4421.1  454.98
  4580.0  451.79  4836.8  441.97  4880.1  441.10  4923.8  438.65  4936.9  438.99
  4980.7  440.25  4997.8  437.63  5000.6  437.13  5003.8  437.63  5009.8  439.51
  5021.0  439.32  5081.3  443.25  5105.9  444.19  5141.7  446.55  5161.8  447.07
  5171.9  448.08  5234.1  450.71  5288.0  452.10  5342.9  451.54  5361.4  451.84
  5423.4  451.81  5470.2  452.41  5475.2  451.62  5524.0  453.07  5564.7  453.61
#Mann=8,-1,0
  4269.5    0.16       0  4326.6     0.1       0  4836.8    0.16       0
  4936.9    0.12       0  4997.8    0.07       0  5003.8    0.12       0
  5234.1     0.1       0  5361.4    0.05       0
Bank Sta=4997.8,5003.8
Exp/Cntr=0.3,0.1

Type RM Length L Ch R = 1,3979,907,907,907
BEGIN DESCRIPTION:
UNT0613 IN SAND CR 7.0
END DESCRIPTION:
XS GIS Cut Line= 3
      3534048.54     10567183.14      3533288.12     10566818.55
      3532579.78     10566698.76
#Sta/Elev= 30
  4047.6  456.96  4061.9  456.11  4169.6  454.51  4398.5  449.06  4429.5  448.92
  4492.5  446.81  4600.1  442.47  4631.4  441.70  4698.0  437.52  4764.3  436.82
  4978.1  436.37  4995.4  433.49  4998.2  432.99  5001.4  433.49  5008.6  435.17
  5018.0  436.25  5020.3  435.73  5028.8  435.06  5083.5  436.56  5120.0  438.64
  5143.9  438.93  5199.2  441.87  5204.3  441.58  5259.6  444.89  5325.1  446.80
  5396.8  450.22  5424.4  451.09  5445.9  450.59  5528.5  451.69  5609.3  451.52
#Mann=12,-1,0
  4047.6    0.16       0  4061.9    0.05       0  4169.6    0.16       0
  4492.5    0.05       0  4600.1     0.1       0  4764.3    0.05       0
  4995.4    0.03       0  5001.4    0.05       0  5020.3     0.1       0
  5120.0    0.05       0  5396.8     0.1       0  5528.5    0.05       0
Bank Sta=4995.4,5001.4
Exp/Cntr=0.3,0.1

Type RM Length L Ch R = 1,3072,845,845,845
BEGIN DESCRIPTION:
UNT0613 IN SAND CR 6.0
END DESCRIPTION:
XS GIS Cut Line= 4
      3534366.26     10567073.77      3533913.12     10566657.09
      3533720.41     10566459.18      3533199.60     10566219.61
#Sta/Elev= 30
  4240.2  457.37  4251.7  458.21  4286.8  456.17  4419.6  453.40  4513.7  452.07
  4556.2  450.95  4577.2  449.56  4619.8  449.47  4651.9  448.00  4668.3  447.38
  4719.0  446.04  4775.7  442.42  4825.1  440.36  4902.9  435.16  4936.6  434.43
  4998.9  432.07  5001.6  431.57  5004.9  432.07  5079.6  433.44  5159.9  432.48
  5234.3  436.55  5257.2  436.28  5280.2  437.51  5299.0  437.38  5354.6  439.31
  5372.1  440.95  5402.1  440.91  5492.5  443.45  5625.5  449.28  5705.3  450.51
#Mann=9,-1,0
  4240.2     0.1       0  4419.6    0.16       0  4651.9     0.1       0
  4668.3    0.05       0  4936.6    0.12       0  4998.9    0.07       0
  5004.9    0.12       0  5299.0    0.16       0  5402.1    0.05       0
Bank Sta=4998.9,5004.9
Exp/Cntr=0.3,0.1

Type RM Length L Ch R = 1,2227,775,775,775
BEGIN DESCRIPTION:
UNT0613 IN SAND CR 4.0
END DESCRIPTION:
XS GIS Cut Line= 4
      3534824.58     10566427.93      3534298.53     10565964.39
      3534105.83     10565839.39      3533371.41     10565938.35
#Sta/Elev= 30
  4156.0  445.75  4164.9  445.83  4488.3  446.37  4551.9  442.82  4623.0  440.06
  4665.7  437.47  4672.3  436.30  4686.6  436.56  4693.2  435.44  4729.2  434.18
  4778.6  429.87  4813.7  427.98  4936.3  429.18  4979.8  428.86  4992.0  425.24
  4994.7  424.74  4998.0  425.24  5016.1  427.15  5031.2  427.33  5086.1  432.34
  5138.6  434.95  5143.6  434.46  5211.4  439.75  5216.4  439.15  5272.2  443.42
  5393.3  448.36  5524.5  448.41  5663.0  445.38  5716.2  445.11  5827.9  447.52
#Mann=4,-1,0
  4156.0    0.05       0  4164.9    0.16       0  4992.0    0.04       0
  4998.0    0.05       0
Bank Sta=4992,4998
Exp/Cntr=0.3,0.1

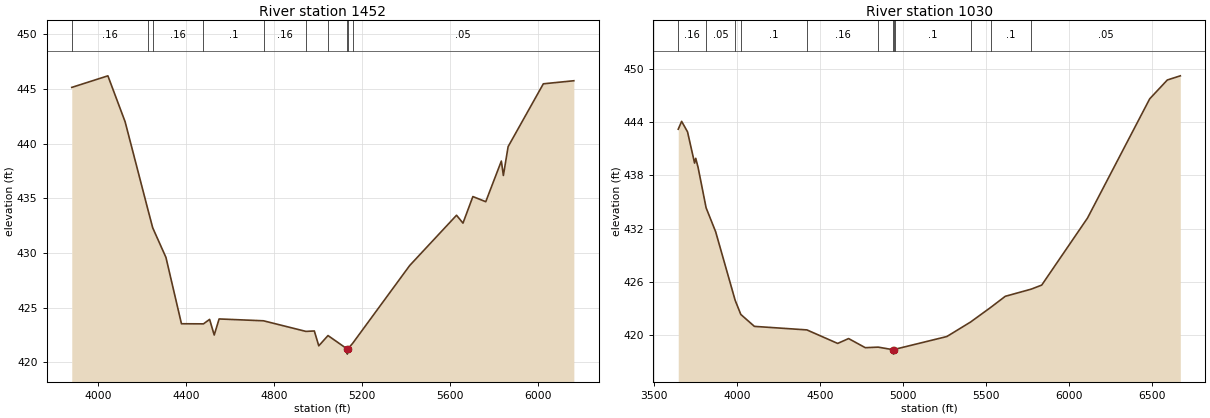
Type RM Length L Ch R = 1,1452,422,422,422
BEGIN DESCRIPTION:
UNT0613 IN SAND CR 2.0
END DESCRIPTION:
XS GIS Cut Line= 4
      3535053.73     10565870.63      3534298.53     10565256.05
      3534027.70     10565292.51      3533138.73     10565817.58
#Sta/Elev= 30
  3882.0  445.15  4046.0  446.21  4124.3  442.00  4227.4  433.99  4249.5  432.30
  4309.6  429.59  4380.0  423.52  4480.0  423.51  4507.8  423.92  4528.7  422.49
  4550.9  423.96  4752.7  423.79  4945.0  422.82  4983.2  422.86  5003.4  421.50
  5045.3  422.44  5130.4  421.24  5133.1  420.74  5136.4  421.24  5157.3  421.73
  5416.2  428.85  5628.8  433.45  5658.1  432.73  5703.0  435.16  5761.5  434.69
  5832.3  438.41  5841.5  437.09  5863.0  439.73  6022.9  445.48  6161.4  445.76
#Mann=10,-1,0
  3882.0    0.16       0  4227.4    0.05       0  4249.5    0.16       0
  4480.0     0.1       0  4752.7    0.16       0  4945.0    0.08       0
  5045.3     0.1       0  5130.4    0.07       0  5136.4     0.1       0
  5157.3    0.05       0
Bank Sta=5130.4,5136.4
Exp/Cntr=0.3,0.1

Type RM Length L Ch R = 1,1030,0,0,0
BEGIN DESCRIPTION:
UNT0613 IN SAND CR 1.0
END DESCRIPTION:
XS GIS Cut Line= 4
      3535117.97     10565644.93      3534451.31     10564929.66
      3533756.87     10564867.16      3532749.93     10565769.93
#Sta/Elev= 30
  3644.1  443.23  3664.6  444.12  3700.2  442.93  3742.7  439.40  3749.6  439.94
  3763.8  438.91  3812.2  434.34  3869.8  431.63  3987.3  423.88  4021.4  422.28
  4103.3  420.93  4419.8  420.53  4605.5  419.00  4671.3  419.55  4771.9  418.52
  4849.9  418.58  4939.4  418.29  4942.1  417.79  4945.4  418.29  4948.8  418.33
  5263.7  419.78  5406.8  421.42  5527.9  423.07  5616.1  424.33  5772.2  425.14
  5835.9  425.60  6111.8  433.18  6487.0  446.67  6593.2  448.80  6671.5  449.27
#Mann=12,-1,0
  3644.1    0.16       0  3812.2    0.05       0  3987.3    0.16       0
  4021.4     0.1       0  4419.8    0.16       0  4849.9    0.08       0
  4939.4    0.07       0  4945.4    0.08       0  4948.8     0.1       0
  5406.8    0.05       0  5527.9     0.1       0  5772.2    0.05       0
Bank Sta=4939.4,4945.4
Exp/Cntr=0.3,0.1

Chan Stop Cuts=-1