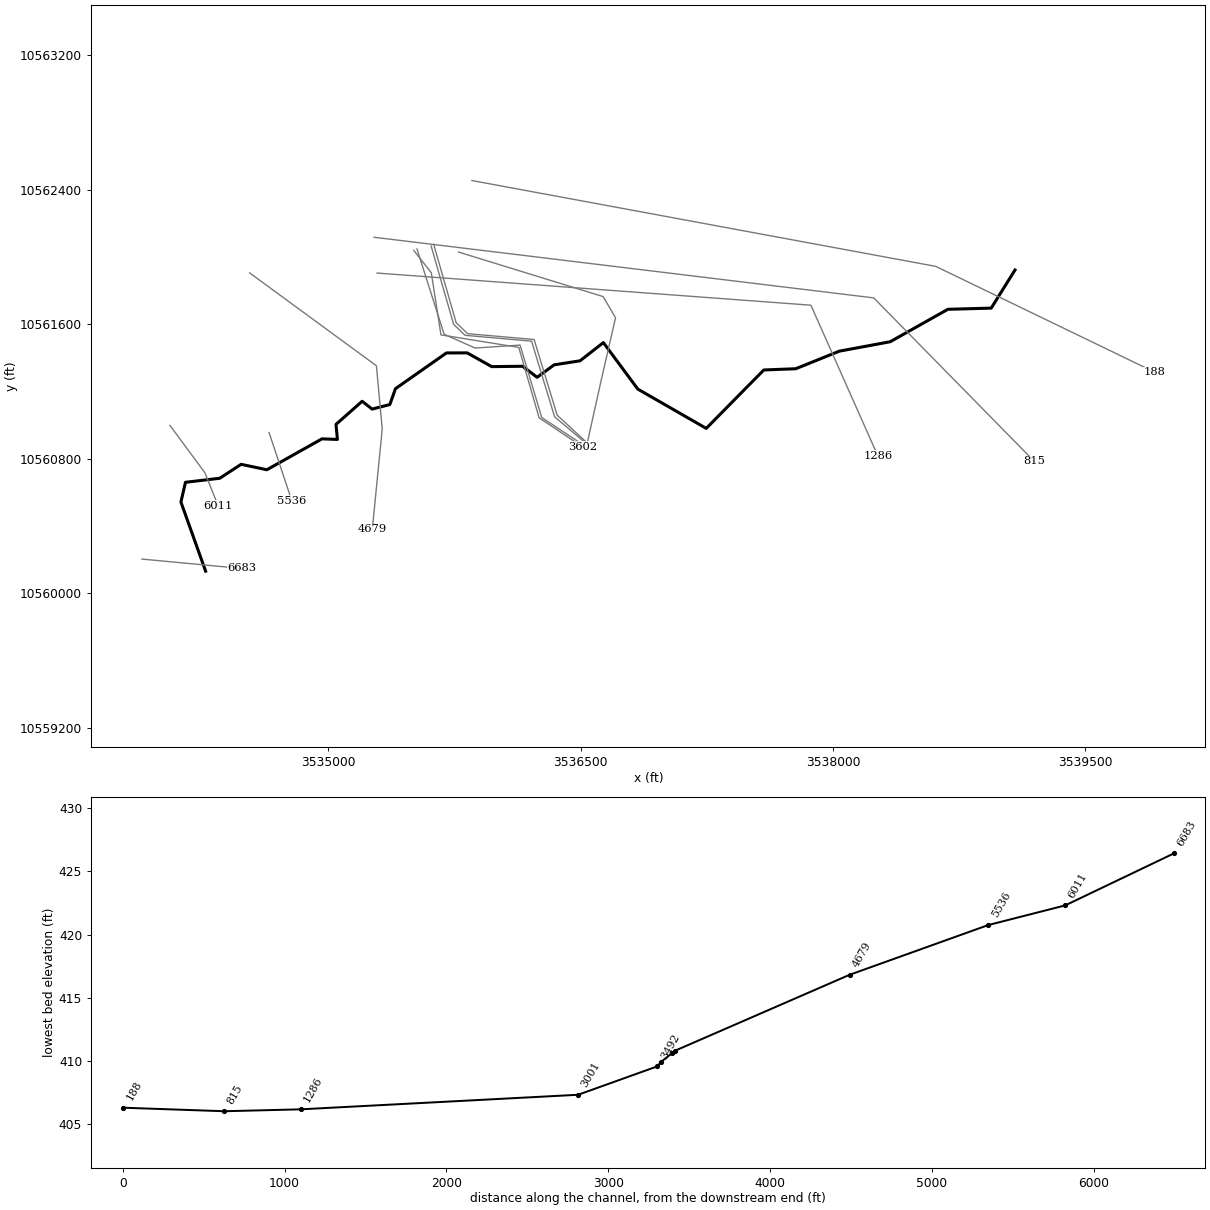
--- UNT0615 IN SAND CR.prj (project) ---

Proj Title=UNT0615 IN SAND CR Base Level Engineering
Current Plan=p01
Default Exp/Contr=0.3,0.1
English Units
Geom File=g01
Flow File=f01
Plan File=p01
BEGIN DESCRIPTION:
UNT0615 IN SAND CR
END DESCRIPTION:

--- UNT0615 IN SAND CR.p01 (plan) ---

Plan Title=Multiple Run
Short Identifier=Multiple
Geom File=g01
Flow File=f01
Subcritical Flow
K Sum by GR= 0
Std Step Tol= 0.01
Critical Tol= 0.01
Num of Std Step Trials= 20
Max Error Tol= 0.3
Flow Tol Ratio= 0.001
Split Flow NTrial= 30
Split Flow Tol= 0.02
Split Flow Ratio= 0.02
Log Output Level= 0
Friction Slope Method= 1
Unsteady Friction Slope Method= 2
Unsteady Bridges Friction Slope Method= 1
Parabolic Critical Depth
Global Vel Dist=  1 , 1 , 1
Global Log Level= 0
CheckData=True
Encroach Param= -1, 0, 0, 0
BEGIN DESCRIPTION:
Multiple Run
END DESCRIPTION:

--- UNT0615 IN SAND CR.f01 (steady flow) ---

Flow Title=Multiple
Number of Profiles=7
Profile Names=10-year,25-year,50-year,1pct_min,100-year,1pct_plu,500-year
River Rch & RM= UNT0615 IN SAND ,Reach-1,6683
     891    1213    1476    1311    1773    2398    2550
River Rch & RM= UNT0615 IN SAND ,Reach-1,1286
    1353    1881    2321    2086    2821    3816    4159
Boundary for River Rch & Prof#=UNT0615 IN SAND ,Reach-1,1
Up Type=0
Dn Type=3
Dn Slope=0.005
Boundary for River Rch & Prof#=UNT0615 IN SAND ,Reach-1,2
Up Type=0
Dn Type=3
Dn Slope=0.005
Boundary for River Rch & Prof#=UNT0615 IN SAND ,Reach-1,3
Up Type=0
Dn Type=3
Dn Slope=0.005
Boundary for River Rch & Prof#=UNT0615 IN SAND ,Reach-1,4
Up Type=0
Dn Type=3
Dn Slope=0.005
Boundary for River Rch & Prof#=UNT0615 IN SAND ,Reach-1,5
Up Type=0
Dn Type=3
Dn Slope=0.005
Boundary for River Rch & Prof#=UNT0615 IN SAND ,Reach-1,6
Up Type=0
Dn Type=3
Dn Slope=0.005
Boundary for River Rch & Prof#=UNT0615 IN SAND ,Reach-1,7
Up Type=0
Dn Type=3
Dn Slope=0.005

--- UNT0615 IN SAND CR.g01 (geometry) ---

Geom Title=Existing Conditions

River Reach=UNT0615 IN SAND ,Reach-1
Reach XY= 30
      3534272.11     10560131.64      3534125.30     10560542.68
      3534152.32     10560659.89      3534356.17     10560683.81
      3534483.14     10560766.71      3534636.22     10560734.41
      3534963.73     10560918.12      3535055.34     10560914.61
      3535046.93     10561003.94      3535202.49     10561141.43
      3535261.35     10561094.97      3535366.85     10561121.84
      3535400.30     10561216.28      3535703.42     10561428.70
      3535826.50     10561429.10      3535972.25     10561347.36
      3536156.09     10561349.45      3536242.11     10561283.84
      3536343.59     10561358.04      3536497.12     10561381.88
      3536635.86     10561490.16      3536840.42     10561213.86
      3537247.21     10560980.29      3537589.36     10561327.47
      3537779.20     10561334.79      3538037.94     10561439.20
      3538340.59     10561495.29      3538683.23     10561688.05
      3538940.78     10561695.12      3539082.11     10561921.64

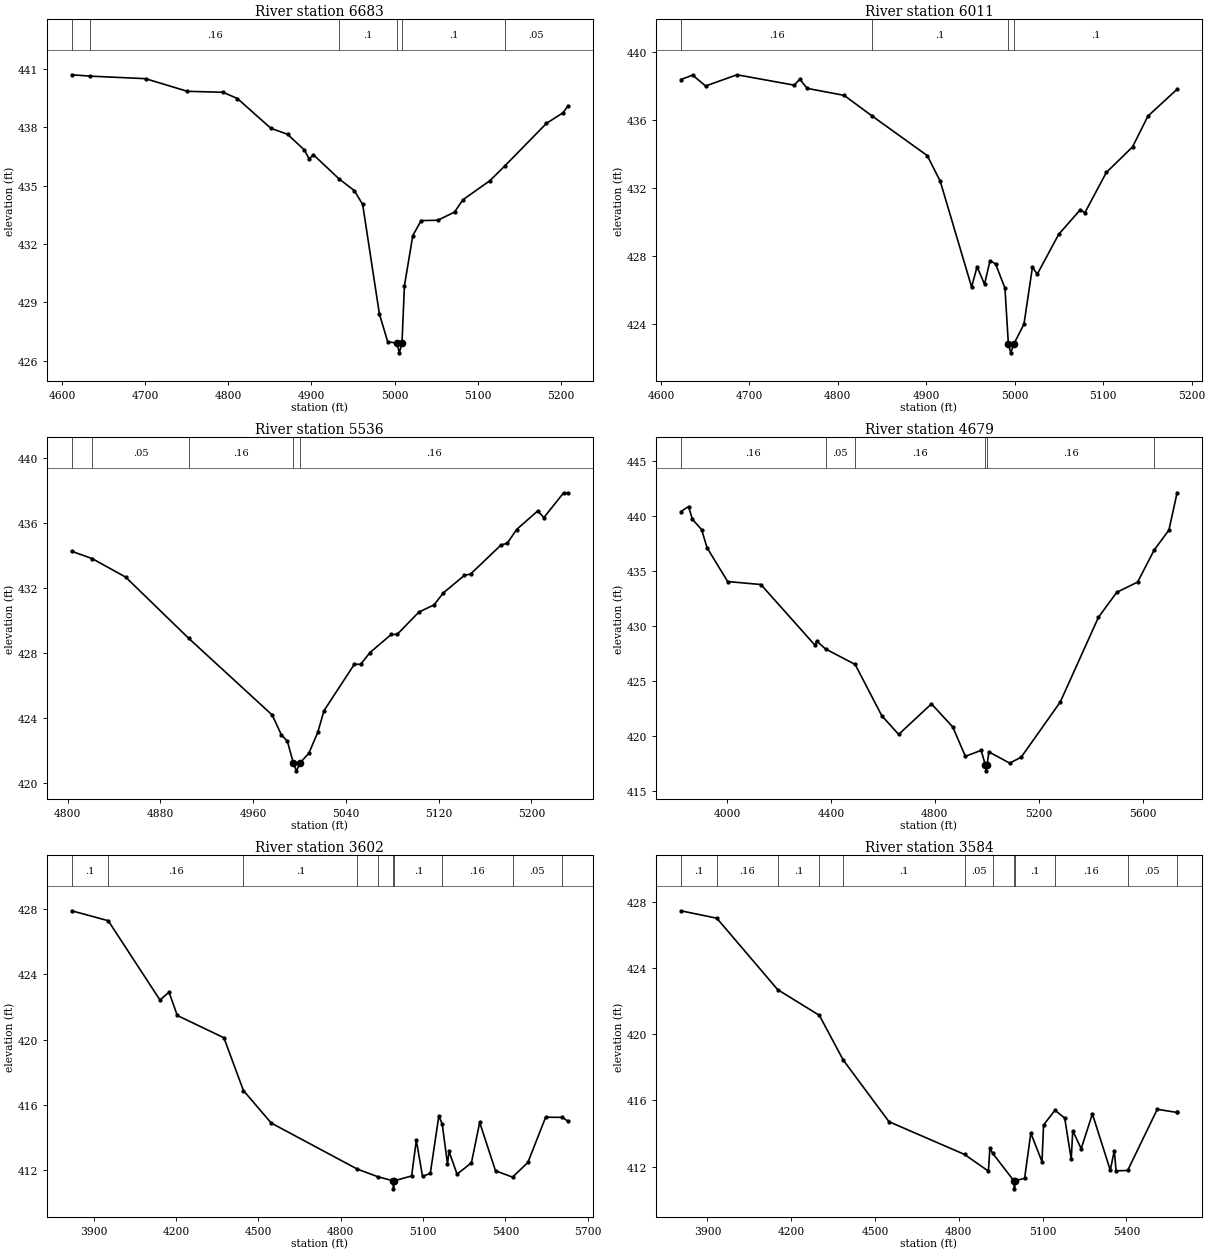
Type RM Length L Ch R = 1,6683,672,672,672
BEGIN DESCRIPTION:
UNT0615 IN SAND CR 6.0
END DESCRIPTION:
XS GIS Cut Line= 2
      3533893.65     10560203.50      3534487.92     10560147.58
#Sta/Elev= 30
  4611.6  440.71  4634.0  440.64  4700.4  440.51  4750.7  439.86  4793.7  439.81
  4810.9  439.49  4851.1  437.96  4871.2  437.65  4891.3  436.85  4897.3  436.38
  4902.3  436.60  4933.1  435.36  4951.6  434.75  4961.6  434.04  4981.7  428.41
  4991.7  426.98  5002.9  426.91  5005.7  426.41  5008.9  426.91  5011.8  429.85
  5021.9  432.44  5031.9  433.21  5052.0  433.23  5072.1  433.65  5082.1  434.28
  5114.5  435.26  5132.5  436.02  5182.6  438.21  5202.7  438.76  5208.5  439.11
#Mann=6,-1,0
  4611.6     0.1       0  4634.0    0.16       0  4933.1     0.1       0
  5002.9    0.07       0  5008.9     0.1       0  5132.5    0.05       0
Bank Sta=5002.9,5008.9
Exp/Cntr=0.3,0.1

Type RM Length L Ch R = 1,6011,475,475,475
BEGIN DESCRIPTION:
UNT0615 IN SAND CR 5.0
END DESCRIPTION:
XS GIS Cut Line= 3
      3534059.84     10560998.35      3534268.15     10560716.27
      3534346.27     10560520.97
#Sta/Elev= 30
  4622.5  438.36  4635.9  438.62  4650.5  437.98  4686.0  438.64  4750.7  438.03
  4757.0  438.38  4765.4  437.84  4807.1  437.43  4838.7  436.22  4901.1  433.89
  4915.7  432.39  4951.2  426.17  4957.4  427.36  4965.8  426.33  4972.0  427.71
  4978.3  427.53  4988.9  426.10  4992.8  422.80  4995.5  422.30  4998.8  422.80
  5010.4  423.99  5020.0  427.34  5025.4  426.92  5049.6  429.26  5073.9  430.70
  5079.3  430.54  5103.5  432.90  5133.1  434.40  5150.5  436.21  5183.5  437.79
#Mann=4,-1,0
  4622.5    0.16       0  4838.7     0.1       0  4992.8    0.07       0
  4998.8     0.1       0
Bank Sta=4992.8,4998.8
Exp/Cntr=0.3,0.1

Type RM Length L Ch R = 1,5536,857,857,857
BEGIN DESCRIPTION:
UNT0615 IN SAND CR 4.0
END DESCRIPTION:
XS GIS Cut Line= 2
      3534649.17     10560955.85      3534784.57     10560549.63
#Sta/Elev= 30
  4803.4  434.26  4821.1  433.81  4850.0  432.67  4904.3  428.91  4976.5  424.18
  4984.2  422.98  4989.5  422.57  4994.6  421.25  4997.3  420.75  5000.6  421.25
  5008.1  421.84  5015.8  423.13  5021.1  424.45  5047.4  427.32  5052.7  427.30
  5060.8  428.03  5079.1  429.14  5084.3  429.15  5103.0  430.52  5116.0  430.96
  5124.1  431.70  5142.3  432.78  5147.6  432.86  5173.9  434.65  5179.2  434.75
  5187.3  435.60  5205.6  436.75  5210.8  436.33  5227.9  437.86  5231.6  437.86
#Mann=5,-1,0
  4803.4    0.16       0  4821.1    0.05       0  4904.3    0.16       0
  4994.6    0.07       0  5000.6    0.16       0
Bank Sta=4994.6,5000.6
Exp/Cntr=0.3,0.1

Type RM Length L Ch R = 1,4679,1077,1077,1077
BEGIN DESCRIPTION:
UNT0615 IN SAND CR 2.0
END DESCRIPTION:
XS GIS Cut Line= 4
      3534533.53     10561904.60      3535287.03     10561352.50
      3535321.76     10560977.50      3535262.72     10560380.24
#Sta/Elev= 30
  3821.8  440.36  3851.6  440.82  3866.3  439.67  3901.8  438.73  3922.6  437.09
  4002.1  434.01  4130.0  433.74  4338.7  428.22  4344.9  428.61  4378.9  427.89
  4493.1  426.48  4595.7  421.82  4660.6  420.13  4786.9  422.90  4868.7  420.81
  4917.5  418.14  4978.2  418.68  4994.8  417.32  4997.6  416.82  5000.8  417.32
  5007.9  418.54  5088.2  417.52  5132.5  418.06  5282.8  423.07  5429.8  430.76
  5500.2  433.03  5580.6  433.96  5644.1  436.86  5701.1  438.68  5732.7  442.07
#Mann=6,-1,0
  3821.8    0.16       0  4378.9    0.05       0  4493.1    0.16       0
  4994.8    0.07       0  5000.8    0.16       0  5644.1     0.1       0
Bank Sta=4994.8,5000.8
Exp/Cntr=0.3,0.1

Type RM Length L Ch R = 1,3602,18,18,18
BEGIN DESCRIPTION:
UNT0615 IN SAND CR 1.1
END DESCRIPTION:
XS GIS Cut Line= 6
      3535509.07     10562037.84      3535613.27     10561905.86
      3535670.56     10561536.07      3536133.17     10561461.65
      3536253.83     10561043.24      3536513.34     10560869.66
#Sta/Elev= 30
  3820.5  427.91  3953.6  427.30  4142.0  422.43  4175.1  422.91  4205.0  421.48
  4374.8  420.11  4445.8  416.87  4547.2  414.87  4860.9  412.04  4934.2  411.58
  4989.6  411.33  4992.3  410.83  4995.6  411.33  5058.2  411.62  5075.4  413.81
  5098.1  411.59  5126.3  411.78  5157.3  415.30  5169.7  414.82  5188.9  412.35
  5194.4  413.13  5223.8  411.73  5276.1  412.43  5306.1  414.91  5363.7  411.94
  5425.8  411.55  5481.6  412.45  5546.3  415.23  5606.4  415.22  5627.5  414.99
#Mann=10,-1,0
  3820.5     0.1       0  3953.6    0.16       0  4445.8     0.1       0
  4860.9    0.05       0  4934.2     0.1       0  4989.6    0.07       0
  4995.6     0.1       0  5169.7    0.16       0  5425.8    0.05       0
  5606.4    0.08       0
Bank Sta=4989.6,4995.6
Exp/Cntr=0.3,0.1

Type RM Length L Ch R = 1,3584,73,73,73
BEGIN DESCRIPTION:
UNT0615 IN SAND CR 1.0
END DESCRIPTION:
XS GIS Cut Line= 6
      3535528.20     10562046.48      3535689.65     10561539.54
      3535873.68     10561457.94      3536141.04     10561475.30
      3536269.52     10561044.75      3536508.11     10560887.50
#Sta/Elev= 30
  3804.6  427.46  3933.5  427.01  4151.5  422.69  4300.5  421.14  4385.9  418.44
  4549.8  414.71  4820.3  412.73  4905.8  411.72  4911.1  413.11  4921.0  412.80
  4996.3  411.15  4999.0  410.65  5002.3  411.15  5035.3  411.28  5057.6  414.02
  5097.7  412.29  5103.2  414.51  5144.1  415.40  5178.9  414.93  5202.3  412.44
  5207.7  414.16  5237.9  413.08  5278.1  415.18  5342.0  411.78  5356.6  412.96
  5362.8  411.74  5404.3  411.76  5510.3  415.46  5580.2  415.27  5581.3  415.30
#Mann=12,-1,0
  3804.6     0.1       0  3933.5    0.16       0  4151.5     0.1       0
  4300.5    0.16       0  4385.9     0.1       0  4820.3    0.05       0
  4921.0     0.1       0  4996.3    0.07       0  5002.3     0.1       0
  5144.1    0.16       0  5404.3    0.05       0  5580.2    0.08       0
Bank Sta=4996.3,5002.3
Exp/Cntr=0.3,0.1

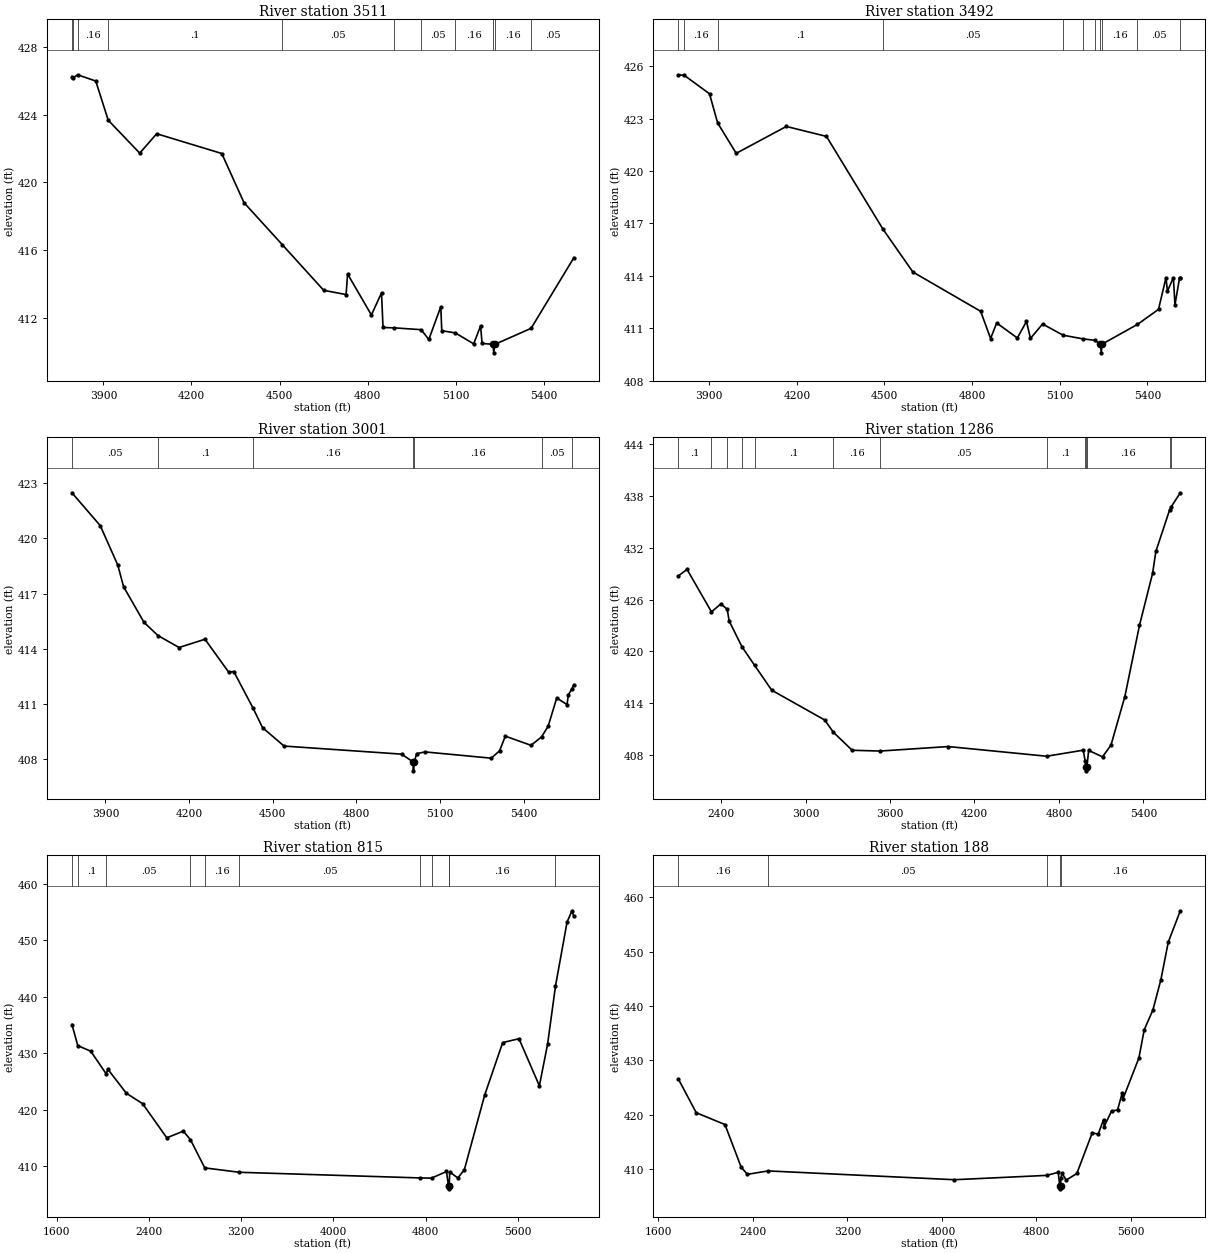
Type RM Length L Ch R = 1,3511,19,19,19
BEGIN DESCRIPTION:
UNT0615 IN SAND CR 1.2
END DESCRIPTION:
XS GIS Cut Line= 6
      3535612.45     10562064.04      3535745.93     10561598.51
      3535814.29     10561533.41      3536209.26     10561498.69
      3536345.98     10561049.47      3536522.59     10560900.05
#Sta/Elev= 30
  3792.8  426.25  3798.0  426.20  3812.2  426.37  3873.9  426.00  3916.4  423.68
  4023.7  421.73  4081.5  422.88  4303.2  421.71  4378.9  418.80  4509.0  416.32
  4650.5  413.61  4726.8  413.36  4731.8  414.58  4813.0  412.15  4847.4  413.46
  4852.6  411.41  4890.1  411.39  4982.5  411.28  5008.5  410.70  5049.4  412.64
  5052.7  411.22  5098.9  411.09  5161.5  410.44  5185.0  411.51  5190.0  410.47
  5227.2  410.41  5229.9  409.91  5233.2  410.41  5357.0  411.36  5502.7  415.54
#Mann=11,-1,0
  3792.8    0.05       0  3798.0     0.1       0  3812.2    0.16       0
  3916.4     0.1       0  4509.0    0.05       0  4890.1     0.1       0
  4982.5    0.05       0  5098.9    0.16       0  5227.2    0.04       0
  5233.2    0.16       0  5357.0    0.05       0
Bank Sta=5227.2,5233.2
Exp/Cntr=0.3,0.1

Type RM Length L Ch R = 1,3492,491,491,491
BEGIN DESCRIPTION:
UNT0615 IN SAND CR 1.3
END DESCRIPTION:
XS GIS Cut Line= 6
      3535627.67     10562073.76      3535761.12     10561608.28
      3535829.48     10561543.17      3536224.45     10561508.45
      3536361.17     10561059.23      3536533.44     10560899.62
#Sta/Elev= 30
  3794.8  425.52  3814.8  425.49  3901.2  424.43  3929.0  422.76  3992.6  421.02
  4164.1  422.56  4301.4  421.99  4495.4  416.66  4597.2  414.22  4829.1  411.97
  4863.2  410.41  4883.9  411.30  4954.7  410.44  4985.9  411.39  4999.6  410.42
  5041.0  411.24  5111.5  410.60  5178.7  410.39  5219.1  410.31  5238.9  410.09
  5241.7  409.59  5244.9  410.09  5365.8  411.22  5437.8  412.08  5463.2  413.89
  5468.5  413.13  5488.7  413.90  5494.0  412.33  5509.7  413.88  5512.4  413.88
#Mann=11,-1,0
  3794.8    0.05       0  3814.8    0.16       0  3929.0     0.1       0
  4495.4    0.05       0  5111.5    0.16       0  5178.7    0.05       0
  5219.1    0.16       0  5238.9    0.04       0  5244.9    0.16       0
  5365.8    0.05       0  5509.7    0.08       0
Bank Sta=5238.9,5244.9
Exp/Cntr=0.3,0.1

Type RM Length L Ch R = 1,3001,1715,1715,1715
BEGIN DESCRIPTION:
UNT0615 IN SAND CR 1.4
END DESCRIPTION:
XS GIS Cut Line= 5
      3535775.19     10562028.30      3536634.53     10561763.55
      3536708.32     10561637.68      3536621.51     10561260.08
      3536541.97     10560901.66
#Sta/Elev= 30
  3779.8  422.49  3881.2  420.70  3944.0  418.56  3964.9  417.37  4038.2  415.43
  4088.3  414.71  4164.0  414.06  4256.8  414.51  4341.6  412.72  4360.1  412.75
  4429.1  410.76  4463.3  409.69  4540.4  408.69  4961.8  408.25  5001.6  407.84
  5004.4  407.34  5007.6  407.84  5015.8  408.28  5046.6  408.37  5283.2  408.03
  5313.2  408.43  5333.7  409.23  5425.9  408.73  5463.8  409.19  5487.3  409.77
  5518.1  411.31  5554.9  410.95  5560.0  411.48  5572.8  411.82  5579.5  412.03
#Mann=7,-1,0
  3779.8    0.05       0  4088.3     0.1       0  4429.1    0.16       0
  5001.6    0.07       0  5007.6    0.16       0  5463.8    0.05       0
  5572.8    0.08       0
Bank Sta=5001.6,5007.6
Exp/Cntr=0.3,0.1

Type RM Length L Ch R = 1,1286,471,471,471
BEGIN DESCRIPTION:
UNT0615 IN SAND CK 1.0
END DESCRIPTION:
XS GIS Cut Line= 3
      3535291.11     10561903.47      3537869.19     10561712.50
      3538267.11     10560816.64
#Sta/Elev= 30
  2097.1  428.75  2158.3  429.50  2331.9  424.58  2398.9  425.51  2444.2  424.87
  2457.2  423.54  2548.0  420.56  2638.1  418.40  2759.9  415.52  3136.5  412.07
  3198.0  410.65  3331.5  408.57  3530.8  408.48  4013.3  409.00  4713.7  407.88
  4972.9  408.58  4986.5  407.31  4993.2  406.69  4995.9  406.19  4999.2  406.69
  5011.4  408.55  5109.9  407.81  5170.0  409.17  5268.5  414.78  5372.5  423.03
  5465.5  429.04  5488.7  431.57  5586.3  436.37  5597.6  436.74  5662.5  438.36
#Mann=13,-1,0
  2097.1     0.1       0  2331.9    0.16       0  2444.2     0.1       0
  2548.0    0.05       0  2638.1     0.1       0  3198.0    0.16       0
  3530.8    0.05       0  4713.7     0.1       0  4986.5    0.16       0
  4993.2    0.07       0  4999.2    0.16       0  5586.3     0.1       0
  5597.6    0.16       0
Bank Sta=4993.2,4999.2
Exp/Cntr=0.3,0.1

Type RM Length L Ch R = 1,815,627,627,627
BEGIN DESCRIPTION:
UNT0615 IN SAND CK 2.0
END DESCRIPTION:
XS GIS Cut Line= 3
      3535273.66     10562116.15      3538242.46     10561755.90
      3539197.19     10560783.81
#Sta/Elev= 30
  1732.6  435.13  1783.2  431.39  1895.9  430.40  2030.4  426.37  2043.3  427.23
  2204.5  422.96  2345.5  421.11  2555.3  415.07  2698.1  416.25  2760.6  414.74
  2884.4  409.75  3184.7  408.97  4753.9  407.97  4852.2  407.94  4980.6  409.11
  4998.7  406.54  5001.5  406.04  5004.7  406.54  5008.8  409.03  5079.6  407.96
  5136.0  409.43  5312.9  422.68  5468.5  431.93  5609.9  432.61  5786.6  424.28
  5857.4  431.59  5926.4  441.93  6027.1  453.29  6069.5  455.26  6085.7  454.26
#Mann=11,-1,0
  1732.6    0.05       0  1783.2     0.1       0  2030.4    0.05       0
  2760.6     0.1       0  2884.4    0.16       0  3184.7    0.05       0
  4753.9     0.1       0  4852.2    0.16       0  4998.7    0.07       0
  5004.7    0.16       0  5926.4     0.1       0
Bank Sta=4998.7,5004.7
Exp/Cntr=0.3,0.1

Type RM Length L Ch R = 1,188,0,0,0
BEGIN DESCRIPTION:
UNT0615 IN SAND CK 3.0
END DESCRIPTION:
XS GIS Cut Line= 3
      3535854.71     10562453.33      3538610.75     10561943.35
      3539912.81     10561314.02
#Sta/Elev= 30
  1769.4  426.53  1920.2  420.34  2163.4  418.16  2300.7  410.31  2353.6  408.99
  2528.9  409.62  4105.8  408.00  4889.4  408.80  4984.7  409.37  4998.3  406.82
  5001.1  406.32  5004.3  406.82  5006.9  408.36  5018.0  409.18  5052.1  407.93
  5142.4  409.15  5272.5  416.62  5323.2  416.40  5368.4  419.07  5374.0  417.80
  5436.2  420.65  5486.9  420.84  5526.6  423.96  5532.1  422.84  5667.7  430.42
  5712.9  435.62  5786.3  439.26  5854.0  444.86  5916.3  451.75  6018.4  457.53
#Mann=5,-1,0
  1769.4    0.16       0  2528.9    0.05       0  4889.4    0.16       0
  4998.3    0.07       0  5004.3    0.16       0
Bank Sta=4998.3,5004.3
Exp/Cntr=0.3,0.1

Chan Stop Cuts=-1