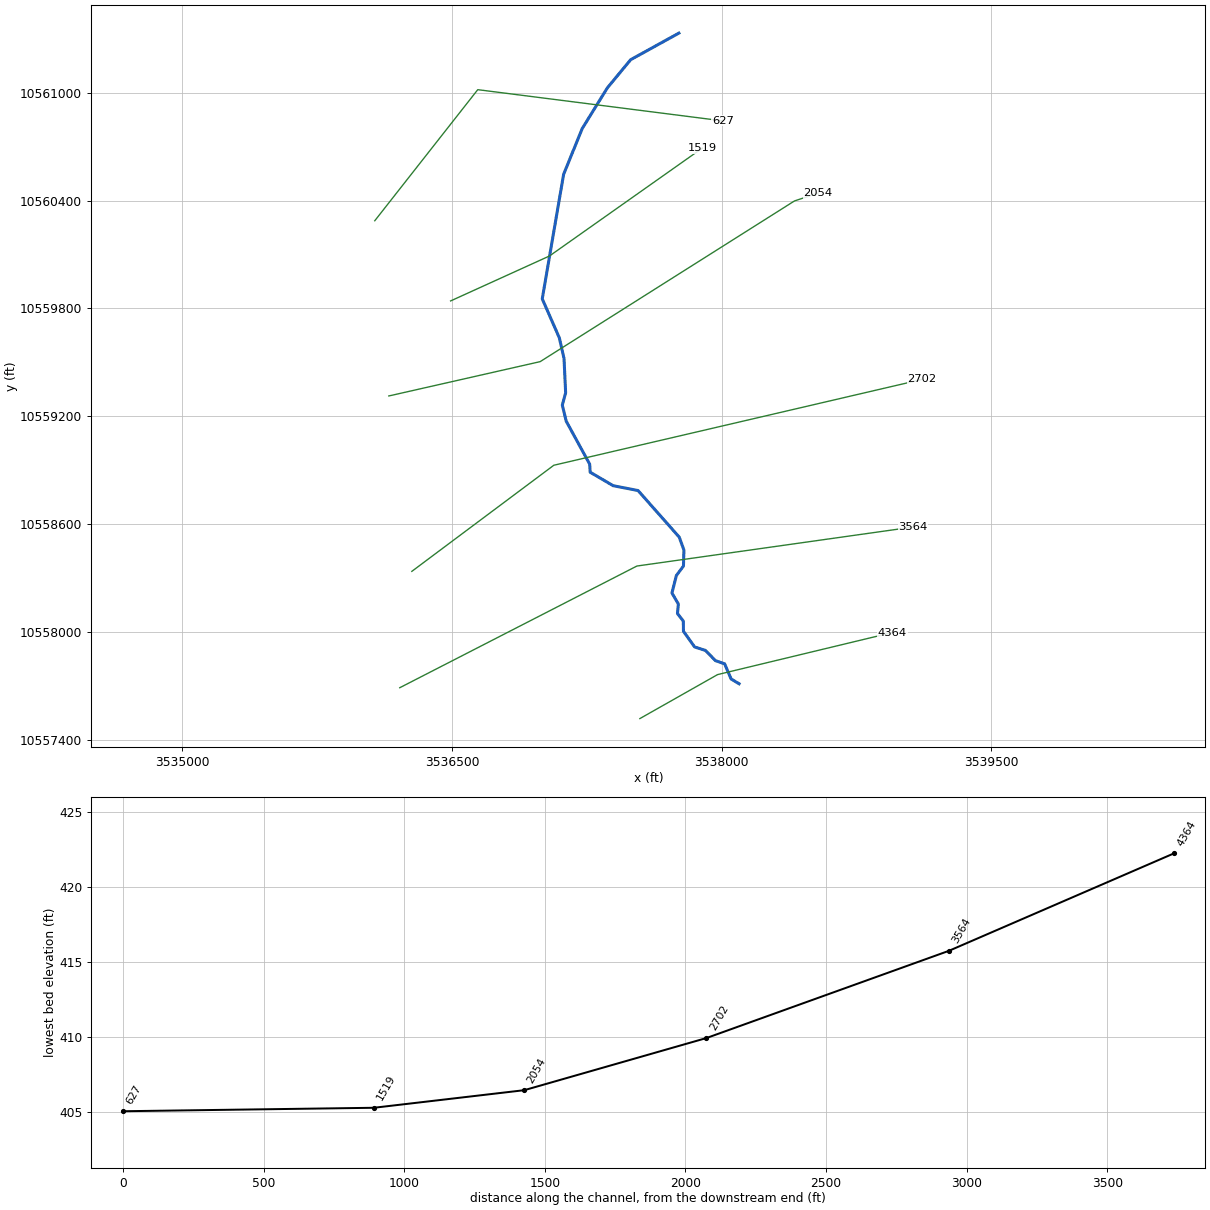
--- UNT0616 IN SAND CR.prj (project) ---

Proj Title=UNT0616 IN SAND CR Base Level Engineering
Current Plan=p01
Default Exp/Contr=0.3,0.1
English Units
Geom File=g01
Flow File=f01
Plan File=p01
BEGIN DESCRIPTION:
UNT0616 IN SAND CR
END DESCRIPTION:

--- UNT0616 IN SAND CR.p01 (plan) ---

Plan Title=Multiple Run
Short Identifier=Multiple
Geom File=g01
Flow File=f01
Subcritical Flow
K Sum by GR= 0
Std Step Tol= 0.01
Critical Tol= 0.01
Num of Std Step Trials= 20
Max Error Tol= 0.3
Flow Tol Ratio= 0.001
Split Flow NTrial= 30
Split Flow Tol= 0.02
Split Flow Ratio= 0.02
Log Output Level= 0
Friction Slope Method= 1
Unsteady Friction Slope Method= 2
Unsteady Bridges Friction Slope Method= 1
Parabolic Critical Depth
Global Vel Dist=  1 , 1 , 1
Global Log Level= 0
CheckData=True
Encroach Param= -1, 0, 0, 0
BEGIN DESCRIPTION:
Multiple Run
END DESCRIPTION:

--- UNT0616 IN SAND CR.f01 (steady flow) ---

Flow Title=Multiple
Number of Profiles=7
Profile Names=10-year,25-year,50-year,1pct_min,100-year,1pct_plu,500-year
River Rch & RM= UNT0616 IN SAND ,Reach-1,4364
     707     952    1150    1016    1374    1858    1952
River Rch & RM= UNT0616 IN SAND ,Reach-1,627
    1353    1881    2321    2086    2821    3816    4159
Boundary for River Rch & Prof#=UNT0616 IN SAND ,Reach-1,1
Up Type=0
Dn Type=3
Dn Slope=0.005
Boundary for River Rch & Prof#=UNT0616 IN SAND ,Reach-1,2
Up Type=0
Dn Type=3
Dn Slope=0.005
Boundary for River Rch & Prof#=UNT0616 IN SAND ,Reach-1,3
Up Type=0
Dn Type=3
Dn Slope=0.005
Boundary for River Rch & Prof#=UNT0616 IN SAND ,Reach-1,4
Up Type=0
Dn Type=3
Dn Slope=0.005
Boundary for River Rch & Prof#=UNT0616 IN SAND ,Reach-1,5
Up Type=0
Dn Type=3
Dn Slope=0.005
Boundary for River Rch & Prof#=UNT0616 IN SAND ,Reach-1,6
Up Type=0
Dn Type=3
Dn Slope=0.005
Boundary for River Rch & Prof#=UNT0616 IN SAND ,Reach-1,7
Up Type=0
Dn Type=3
Dn Slope=0.005

--- UNT0616 IN SAND CR.g01 (geometry) ---

Geom Title=Existing Conditions

River Reach=UNT0616 IN SAND ,Reach-1
Reach XY= 30
      3538097.11     10557711.64      3538052.98     10557738.19
      3538016.60     10557822.77      3537966.22     10557840.05
      3537909.63     10557897.29      3537849.57     10557916.66
      3537787.64     10558003.77      3537786.90     10558060.36
      3537754.32     10558102.28      3537759.18     10558155.63
      3537723.54     10558216.62      3537748.10     10558314.09
      3537787.65     10558366.81      3537790.16     10558455.96
      3537764.05     10558527.70      3537534.89     10558786.86
      3537396.94     10558813.53      3537268.70     10558888.60
      3537265.76     10558933.83      3537135.22     10559172.95
      3537113.64     10559261.94      3537132.08     10559330.78
      3537123.11     10559521.47      3537097.18     10559635.88
      3537002.04     10559853.24      3537120.79     10560545.61
      3537224.26     10560800.47      3537364.54     10561027.55
      3537494.03     10561183.82      3537762.11     10561331.64

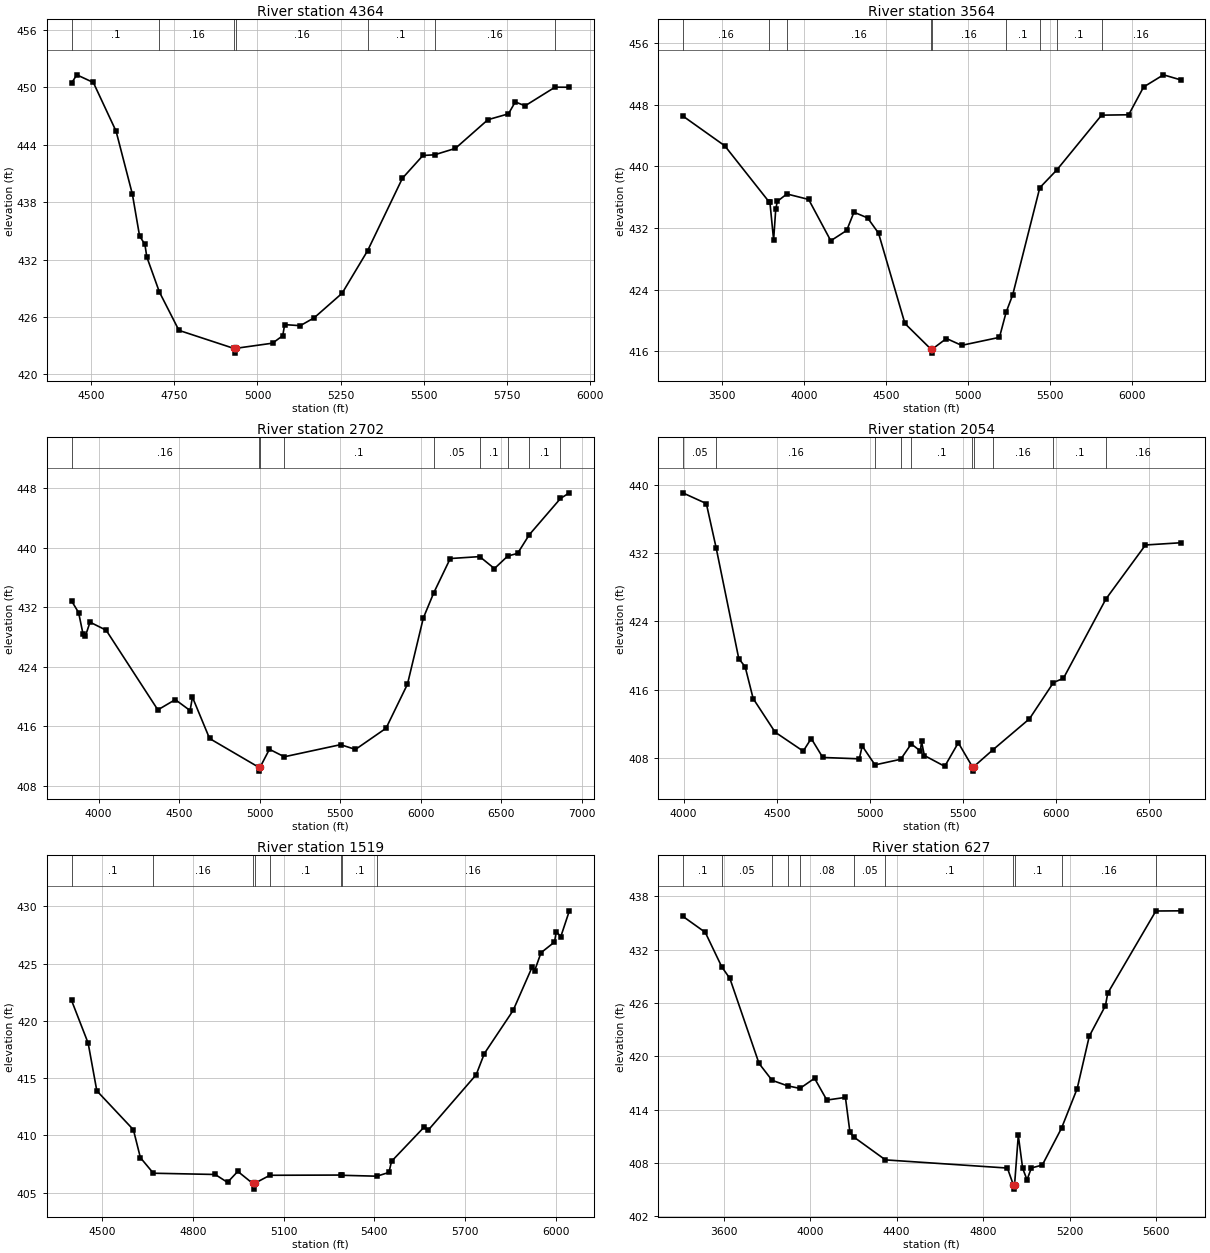
Type RM Length L Ch R = 1,4364,800,800,800
BEGIN DESCRIPTION:
UNT0616 IN SAND CR 6.1
END DESCRIPTION:
XS GIS Cut Line= 3
      3537545.10     10557517.99      3537977.36     10557762.76
      3538950.33     10557996.90
#Sta/Elev= 30
  4440.7  450.44  4456.4  451.31  4506.2  450.51  4574.7  445.41  4623.7  438.83
  4645.4  434.45  4661.3  433.60  4667.1  432.27  4704.9  428.61  4763.7  424.60
  4928.4  422.72  4931.2  422.22  4934.4  422.72  5045.2  423.26  5076.0  424.04
  5081.7  425.20  5128.8  425.09  5170.8  425.92  5254.6  428.48  5331.2  432.92
  5436.0  440.50  5497.7  442.88  5532.7  442.95  5595.3  443.62  5693.2  446.62
  5754.9  447.23  5775.5  448.48  5805.0  448.07  5895.1  450.02  5938.2  450.01
#Mann=7,-1,0
  4440.7     0.1       0  4704.9    0.16       0  4928.4    0.07       0
  4934.4    0.16       0  5331.2     0.1       0  5532.7    0.16       0
  5895.1     0.1       0
Bank Sta=4928.4,4934.4
Exp/Cntr=0.3,0.1

Type RM Length L Ch R = 1,3564,862,862,862
BEGIN DESCRIPTION:
UNT0616 IN SAND CR 6.0
END DESCRIPTION:
XS GIS Cut Line= 3
      3536209.17     10557689.67      3537528.57     10558366.73
      3539065.04     10558583.74
#Sta/Elev= 30
  3259.0  446.56  3515.2  442.68  3783.7  435.44  3790.6  435.32  3813.1  430.44
  3825.9  434.41  3835.5  435.46  3894.0  436.42  4026.6  435.71  4161.5  430.34
  4258.5  431.68  4302.9  434.05  4386.0  433.31  4452.6  431.33  4613.5  419.59
  4772.9  416.24  4775.6  415.74  4778.9  416.24  4866.7  417.64  4959.3  416.75
  5189.9  417.79  5230.3  421.04  5270.7  423.32  5435.7  437.23  5539.1  439.53
  5812.5  446.66  5977.7  446.71  6068.6  450.32  6189.7  451.90  6293.7  451.25
#Mann=9,-1,0
  3259.0    0.16       0  3783.7     0.1       0  3894.0    0.16       0
  4772.9    0.07       0  4778.9    0.16       0  5230.3     0.1       0
  5435.7    0.16       0  5539.1     0.1       0  5812.5    0.16       0
Bank Sta=4772.9,4778.9
Exp/Cntr=0.3,0.1

Type RM Length L Ch R = 1,2702,648,648,648
BEGIN DESCRIPTION:
UNT0616 IN SAND CR 4.0
END DESCRIPTION:
XS GIS Cut Line= 3
      3536276.47     10558337.20      3537066.42     10558927.49
      3539114.99     10559404.91
#Sta/Elev= 30
  3832.0  432.84  3875.7  431.27  3902.8  428.43  3917.4  428.08  3946.6  429.98
  4046.6  428.90  4367.6  418.18  4475.7  419.56  4567.7  418.09  4582.3  419.89
  4688.6  414.33  4995.5  410.44  4998.3  409.94  5001.5  410.44  5060.1  412.88
  5152.4  411.87  5501.7  413.50  5594.1  412.86  5783.9  415.71  5916.7  421.63
  6015.1  430.53  6079.4  433.90  6182.3  438.54  6365.1  438.80  6456.6  437.19
  6539.4  438.88  6600.3  439.23  6673.2  441.75  6866.6  446.62  6921.6  447.38
#Mann=9,-1,0
  3832.0    0.16       0  4995.5    0.07       0  5001.5    0.16       0
  5152.4     0.1       0  6079.4    0.05       0  6365.1     0.1       0
  6539.4    0.16       0  6673.2     0.1       0  6866.6    0.16       0
Bank Sta=4995.5,5001.5
Exp/Cntr=0.3,0.1

Type RM Length L Ch R = 1,2054,535,535,535
BEGIN DESCRIPTION:
UNT0616 IN SAND CR 2.0
END DESCRIPTION:
XS GIS Cut Line= 4
      3536148.33     10559312.90      3536990.38     10559503.88
      3538405.31     10560397.98      3538535.48     10560441.37
#Sta/Elev= 30
  3995.1  439.07  4122.0  437.81  4174.3  432.66  4296.3  419.64  4330.4  418.70
  4373.5  414.97  4491.2  411.04  4642.4  408.81  4685.5  410.29  4747.5  408.07
  4943.9  407.91  4959.2  409.42  5028.1  407.20  5166.3  407.86  5222.8  409.66
  5272.1  408.82  5278.0  409.95  5293.3  408.30  5402.7  407.03  5475.6  409.79
  5551.5  406.97  5554.2  406.47  5557.5  406.97  5660.1  408.94  5858.0  412.60
  5987.0  416.85  6040.3  417.34  6268.6  426.63  6481.2  432.96  6669.5  433.22
#Mann=10,-1,0
  3995.1    0.05       0  4174.3    0.16       0  5028.1     0.1       0
  5166.3    0.16       0  5222.8     0.1       0  5551.5    0.07       0
  5557.5     0.1       0  5660.1    0.16       0  5987.0     0.1       0
  6268.6    0.16       0
Bank Sta=5551.5,5557.5
Exp/Cntr=0.3,0.1

Type RM Length L Ch R = 1,1519,892,892,892
BEGIN DESCRIPTION:
UNT0616 IN SAND CR 1.0
END DESCRIPTION:
XS GIS Cut Line= 3
      3536492.10     10559841.64      3537042.11     10560091.64
      3537892.11     10560691.65
#Sta/Elev= 30
  4399.4  421.79  4454.3  418.05  4482.9  413.89  4603.7  410.49  4626.8  408.05
  4669.7  406.69  4873.9  406.58  4914.6  405.89  4948.6  406.85  4997.8  405.80
  5000.6  405.30  5003.8  405.80  5054.6  406.51  5290.2  406.53  5291.9  406.51
  5408.0  406.43  5448.0  406.76  5456.5  407.73  5563.8  410.71  5578.6  410.48
  5736.2  415.30  5763.2  417.15  5858.1  420.91  5921.6  424.74  5929.5  424.40
  5950.4  425.96  5994.8  426.89  6000.9  427.81  6015.7  427.36  6044.0  429.62
#Mann=8,-1,0
  4399.4     0.1       0  4669.7    0.16       0  4997.8    0.07       0
  5003.8    0.16       0  5054.6     0.1       0  5290.2    0.07       0
  5291.9     0.1       0  5408.0    0.16       0
Bank Sta=4997.8,5003.8
Exp/Cntr=0.3,0.1

Type RM Length L Ch R = 1,627,0,0,0
BEGIN DESCRIPTION:
UNT0616 IN SAND CR 1.1
END DESCRIPTION:
XS GIS Cut Line= 3
      3536070.32     10560287.88      3536643.21     10561017.02
      3538006.02     10560843.42
#Sta/Elev= 30
  3411.4  435.77  3515.5  433.96  3592.2  430.06  3629.4  428.77  3764.1  419.21
  3824.5  417.31  3896.3  416.69  3953.2  416.40  4020.8  417.54  4077.5  415.09
  4163.5  415.39  4184.4  411.46  4201.1  410.95  4348.4  408.36  4912.2  407.44
  4939.4  405.57  4942.2  405.07  4945.4  405.57  4962.6  411.12  4982.7  407.42
  5002.9  406.12  5023.1  407.45  5073.5  407.78  5162.3  411.92  5234.8  416.38
  5290.8  422.28  5365.6  425.72  5375.9  427.11  5598.5  436.36  5712.5  436.38
#Mann=11,-1,0
  3411.4     0.1       0  3592.2    0.05       0  3824.5    0.08       0
  3896.3    0.05       0  3953.2    0.08       0  4201.1    0.05       0
  4348.4     0.1       0  4939.4    0.07       0  4945.4     0.1       0
  5162.3    0.16       0  5598.5     0.1       0
Bank Sta=4939.4,4945.4
Exp/Cntr=0.3,0.1

Chan Stop Cuts=-1