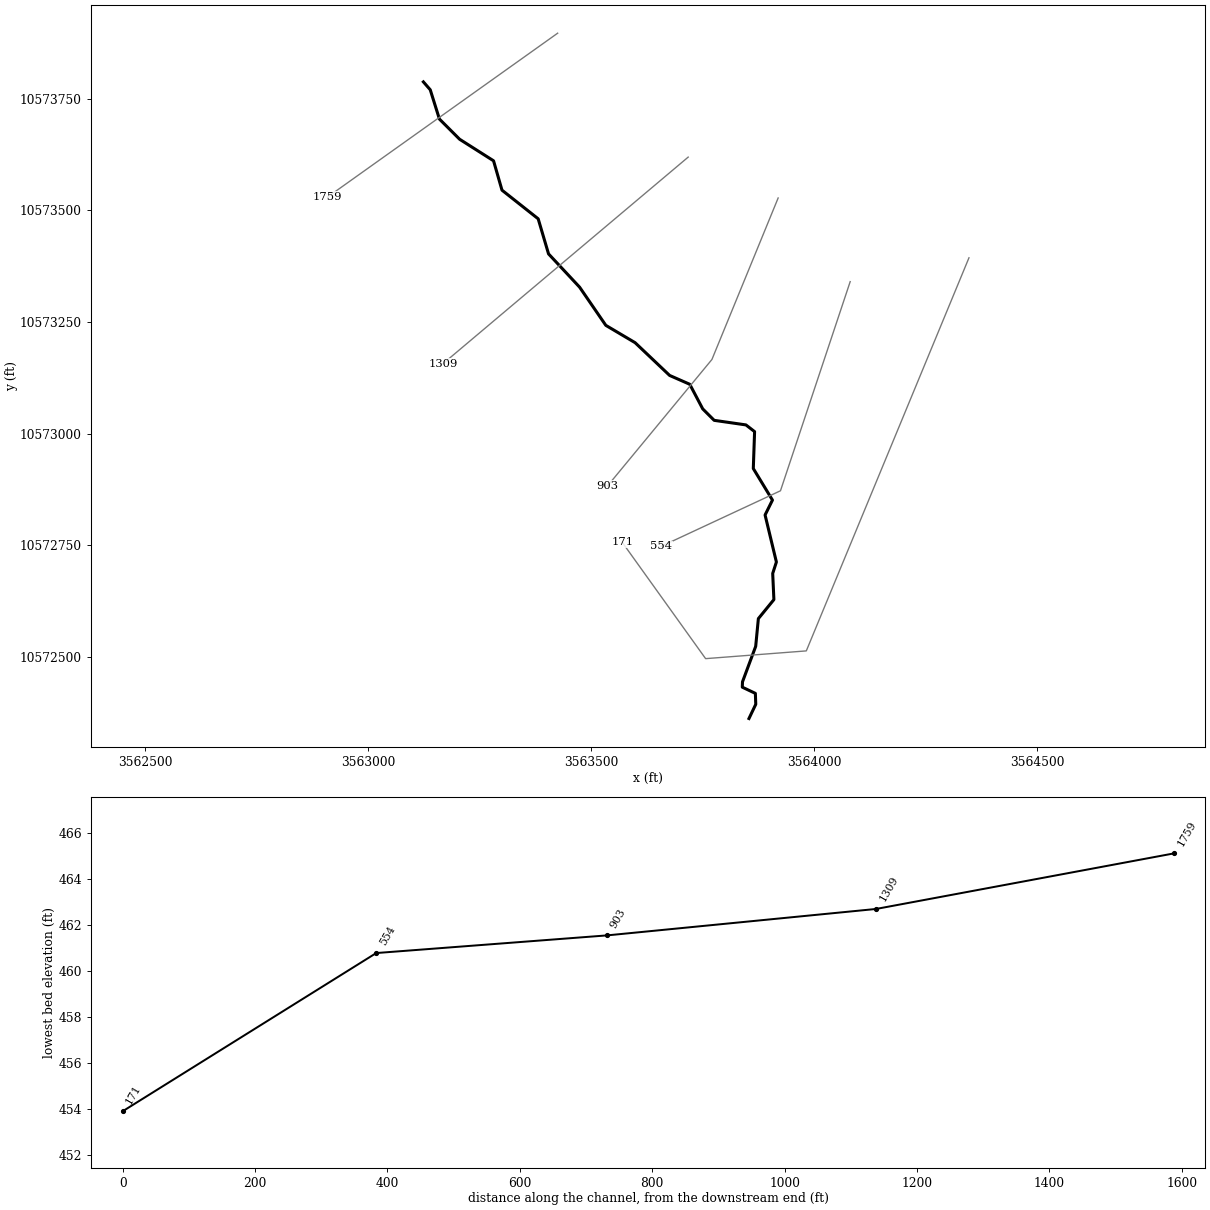
--- UNT0619 IN SAND CR.prj (project) ---

Proj Title=UNT0619 IN SAND CR Base Level Engineering
Current Plan=p01
Default Exp/Contr=0.3,0.1
English Units
Geom File=g01
Flow File=f01
Plan File=p01
Y Axis Title=Elevation
X Axis Title(PF)=Main Channel Distance
X Axis Title(XS)=Station
BEGIN DESCRIPTION:
UNT0619 IN SAND CR
END DESCRIPTION:
DSS Export Rating Curves= 0
DSS Export Rating Curve Sorted= 0
DSS Export Volume Flow Curves= 0
DXF OffsetX= 0
DXF OffsetY= 0
DXF ScaleX= 1
DXF ScaleY= 10

--- UNT0619 IN SAND CR.p01 (plan) ---

Plan Title=Multiple Run
Short Identifier=Multiple
Geom File=g01
Flow File=f01
Subcritical Flow
K Sum by GR= 0
Std Step Tol= 0.01
Critical Tol= 0.01
Num of Std Step Trials= 20
Max Error Tol= 0.3
Flow Tol Ratio= 0.001
Split Flow NTrial= 30
Split Flow Tol= 0.02
Split Flow Ratio= 0.02
Log Output Level= 0
Friction Slope Method= 1
Unsteady Friction Slope Method= 2
Unsteady Bridges Friction Slope Method= 1
Parabolic Critical Depth
Global Vel Dist=  1 , 1 , 1
Global Log Level= 0
CheckData=True
Encroach Param= -1, 0, 0, 0
BEGIN DESCRIPTION:
Multiple Run
END DESCRIPTION:

--- UNT0619 IN SAND CR.f01 (steady flow) ---

Flow Title=Multiple
Number of Profiles=7
Profile Names=10-year,25-year,50-year,1pct_min,100-year,1pct_plu,500-year
River Rch & RM= UNT0619 IN SAND ,Reach-1,1759
     523     688     818     712     963    1303    1328
Boundary for River Rch & Prof#=UNT0619 IN SAND ,Reach-1,1
Up Type=0
Dn Type=3
Dn Slope=0.005
Boundary for River Rch & Prof#=UNT0619 IN SAND ,Reach-1,2
Up Type=0
Dn Type=3
Dn Slope=0.005
Boundary for River Rch & Prof#=UNT0619 IN SAND ,Reach-1,3
Up Type=0
Dn Type=3
Dn Slope=0.005
Boundary for River Rch & Prof#=UNT0619 IN SAND ,Reach-1,4
Up Type=0
Dn Type=3
Dn Slope=0.005
Boundary for River Rch & Prof#=UNT0619 IN SAND ,Reach-1,5
Up Type=0
Dn Type=3
Dn Slope=0.005
Boundary for River Rch & Prof#=UNT0619 IN SAND ,Reach-1,6
Up Type=0
Dn Type=3
Dn Slope=0.005
Boundary for River Rch & Prof#=UNT0619 IN SAND ,Reach-1,7
Up Type=0
Dn Type=3
Dn Slope=0.005

--- UNT0619 IN SAND CR.g01 (geometry) ---

Geom Title=Existing Conditions
Program Version=4.10

River Reach=UNT0619 IN SAND ,Reach-1
Reach XY= 30
      3563124.05     10573788.18      3563139.44     10573770.52
      3563159.99     10573704.87       3563205.3     10573659.59
      3563281.32     10573611.31      3563300.24     10573545.49
      3563381.35     10573481.32      3563404.58     10573402.68
      3563474.13     10573328.17      3563532.96     10573242.49
      3563598.56     10573203.66      3563675.99     10573130.22
       3563721.1      10573110.4      3563750.14     10573055.28
      3563775.82     10573029.58        3563847.     10573019.33
      3563866.41     10573004.29      3563863.53     10572921.54
      3563906.47     10572850.82      3563889.92     10572817.46
      3563915.29     10572712.04      3563907.01     10572686.35
      3563909.69     10572627.79      3563874.88     10572585.16
      3563868.87     10572522.98       3563839.3     10572443.44
      3563838.86      10572431.5      3563868.16     10572417.61
      3563869.03     10572393.09      3563853.83     10572361.23

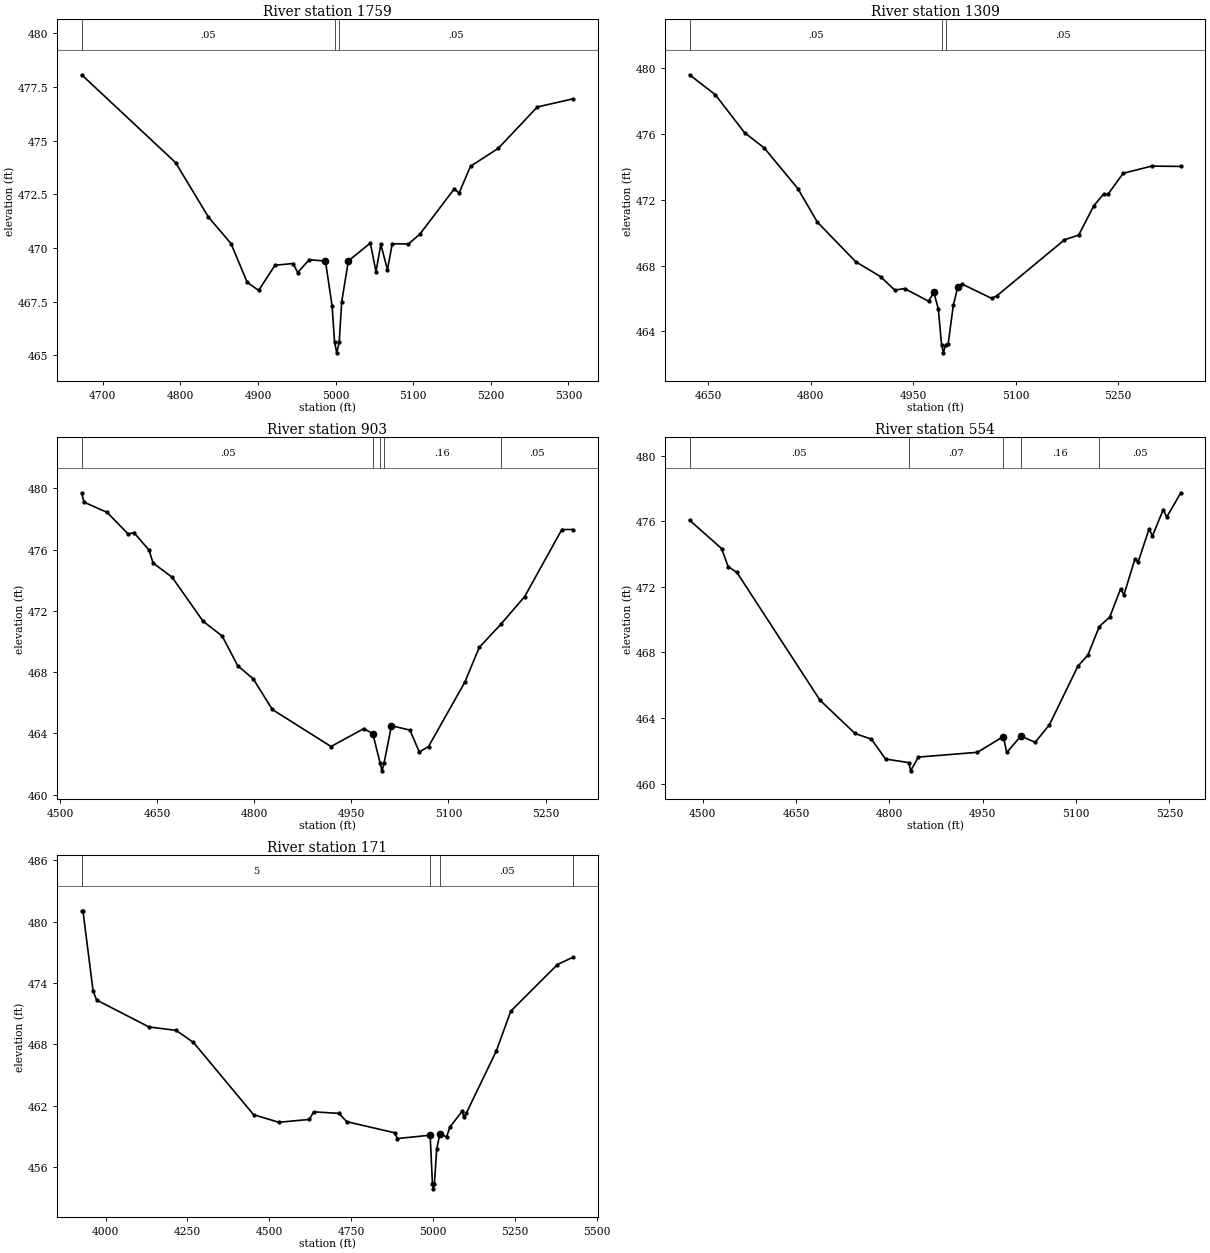
Type RM Length L Ch R = 1 ,1759    ,450,450,450
BEGIN DESCRIPTION:
UNT0619 IN SAND CR 3.0
END DESCRIPTION:
XS GIS Cut Line= 2
      3563425.02     10573897.34       3562909.4     10573530.16
#Sta/Elev= 30
  4672.9  478.07  4793.9  473.98  4836.1  471.45  4865.3  470.21  4886.2   468.4
  4900.9  468.03    4922   469.2  4945.2  469.28  4951.3  468.86  4966.1  469.46
    4987  469.39  4995.6  467.29  4998.7  465.62  5001.5  465.12  5004.7  465.62
  5007.9  467.49  5016.5   469.4  5044.8  470.23  5052.1   468.9  5058.3  470.17
  5066.9  468.99    5073   470.2  5093.9  470.19  5108.7  470.65    5153  472.76
  5159.1  472.56  5173.9  473.81  5209.5  474.64  5259.9  476.57  5305.9  476.95
#Mann= 3 ,-1 , 0
  4672.9     .05       0  4998.7     .03       0  5004.7     .05       0
Bank Sta=4987,5016.5
XS Rating Curve= 0 ,0
Exp/Cntr=0.3,0.1

Type RM Length L Ch R = 1 ,1309    ,406,406,406
BEGIN DESCRIPTION:
UNT0619 IN SAND CR 2.0
END DESCRIPTION:
XS GIS Cut Line= 2
      3563717.58     10573619.58      3563167.64     10573156.25
#Sta/Elev= 30
  4622.7   479.6  4660.4  478.39  4703.3  476.08  4731.9  475.16  4781.3  472.68
  4809.9  470.64  4865.9  468.24  4902.3  467.33  4923.1  466.51  4937.4  466.61
  4972.5  465.84  4980.3  466.37  4986.8  465.37  4991.6   463.2  4994.3   462.7
  4997.6   463.2  5001.1  463.21  5008.9  465.62  5015.4   466.7  5022.1  466.87
  5064.9  466.01  5072.6  466.17  5171.5  469.57  5192.3  469.86  5214.4  471.64
  5228.7  472.35  5235.2  472.34  5257.3  473.61    5299  474.05  5341.8  474.03
#Mann= 3 ,-1 , 0
  4622.7     .05       0  4991.6     .03       0  4997.6     .05       0
Bank Sta=4980.3,5015.4
XS Rating Curve= 0 ,0
Exp/Cntr=0.3,0.1

Type RM Length L Ch R = 1 ,903     ,349,349,349
BEGIN DESCRIPTION:
UNT0619 IN SAND CR 1.02
END DESCRIPTION:
XS GIS Cut Line= 3
      3563919.24     10573527.98       3563770.8     10573165.99
      3563536.77     10572882.56
#Sta/Elev= 30
  4533.6  479.72  4537.1  479.11  4572.9  478.44  4605.3  477.03  4614.5  477.11
  4637.7  475.97  4643.9  475.13  4673.3   474.2  4721.2  471.32  4750.6  470.36
  4774.6  468.42  4798.6  467.56    4828  465.56  4918.7  463.14  4969.4  464.31
  4983.3  463.98  4983.9  463.86  4994.6  462.05  4997.4  461.55  5000.6  462.05
    5012   464.5  5040.6  464.21    5055  462.78  5069.3  463.14  5125.3  467.34
  5147.5  469.61  5180.8  471.12  5217.8  472.94  5275.2  477.32  5292.4  477.32
#Mann= 5 ,-1 , 0
  4533.6     .05       0  4983.9     .16       0  4994.6     .07       0
  5000.6     .16       0  5180.8     .05       0
Bank Sta=4983.3,5012
XS Rating Curve= 0 ,0
Exp/Cntr=0.3,0.1

Type RM Length L Ch R = 1 ,554     ,383,383,383
BEGIN DESCRIPTION:
UNT0619 IN SAND CR 1.03
END DESCRIPTION:
XS GIS Cut Line= 3
      3564080.69     10573340.46      3563924.44     10572871.72
      3563656.69     10572746.94
#Sta/Elev= 30
    4479  476.07  4530.5  474.34    4541  473.24  4555.2  472.88  4688.6  465.09
  4744.9  463.06  4771.3  462.71    4794   461.5  4831.5  461.28  4834.3  460.78
  4846.7  461.62  4941.6  461.91  4983.2  462.87  4988.7   461.9  5011.5   462.9
  5034.4  462.52  5057.3  463.59    5103  467.16  5119.1  467.84  5137.4  469.58
  5154.3  470.16  5171.6  471.87  5177.1  471.52  5194.5  473.68    5200  473.53
  5217.4  475.53  5222.9  475.11  5240.2  476.71  5245.8  476.26  5268.5  477.74
#Mann= 5 ,-1 , 0
    4479     .05       0  4831.5     .07       0  4983.2     .05       0
  5011.5     .16       0  5137.4     .05       0
Bank Sta=4983.2,5011.5
XS Rating Curve= 0 ,0
Exp/Cntr=0.3,0.1

Type RM Length L Ch R = 1 ,171     ,0,0,0
BEGIN DESCRIPTION:
UNT0619 IN SAND CR 1.01
END DESCRIPTION:
XS GIS Cut Line= 4
      3564346.92      10573393.9      3563982.33     10572512.81
      3563756.64     10572495.45      3563570.01     10572755.87
#Sta/Elev= 30
  3926.9  481.05  3930.8  481.05  3961.8  473.21  3972.6  472.33  4132.6   469.7
  4215.1  469.37  4268.3  468.19  4451.9  461.13    4529  460.39    4622  460.67
  4635.4  461.41  4712.5  461.26  4736.4  460.45  4883.1  459.36  4890.7   458.8
    4991  459.13    4998  454.39  5000.8  453.89    5004  454.39  5011.1  457.81
  5021.1  459.29  5041.1  458.95  5051.2  459.92  5088.8  461.47  5093.8  460.88
  5101.3  461.27  5193.1  467.36  5237.3  471.25  5379.8   475.8  5427.2  476.51
#Mann= 4 ,-1 , 0
  3926.9       5       0    4991     .03       0  5021.1     .05       0
  5427.2     .05       0
Bank Sta=4991,5021.1
XS Rating Curve= 0 ,0
Exp/Cntr=0.3,0.1

Chan Stop Cuts=-1
Use User Specified Reach Order=0
Composite Channel Slope=5