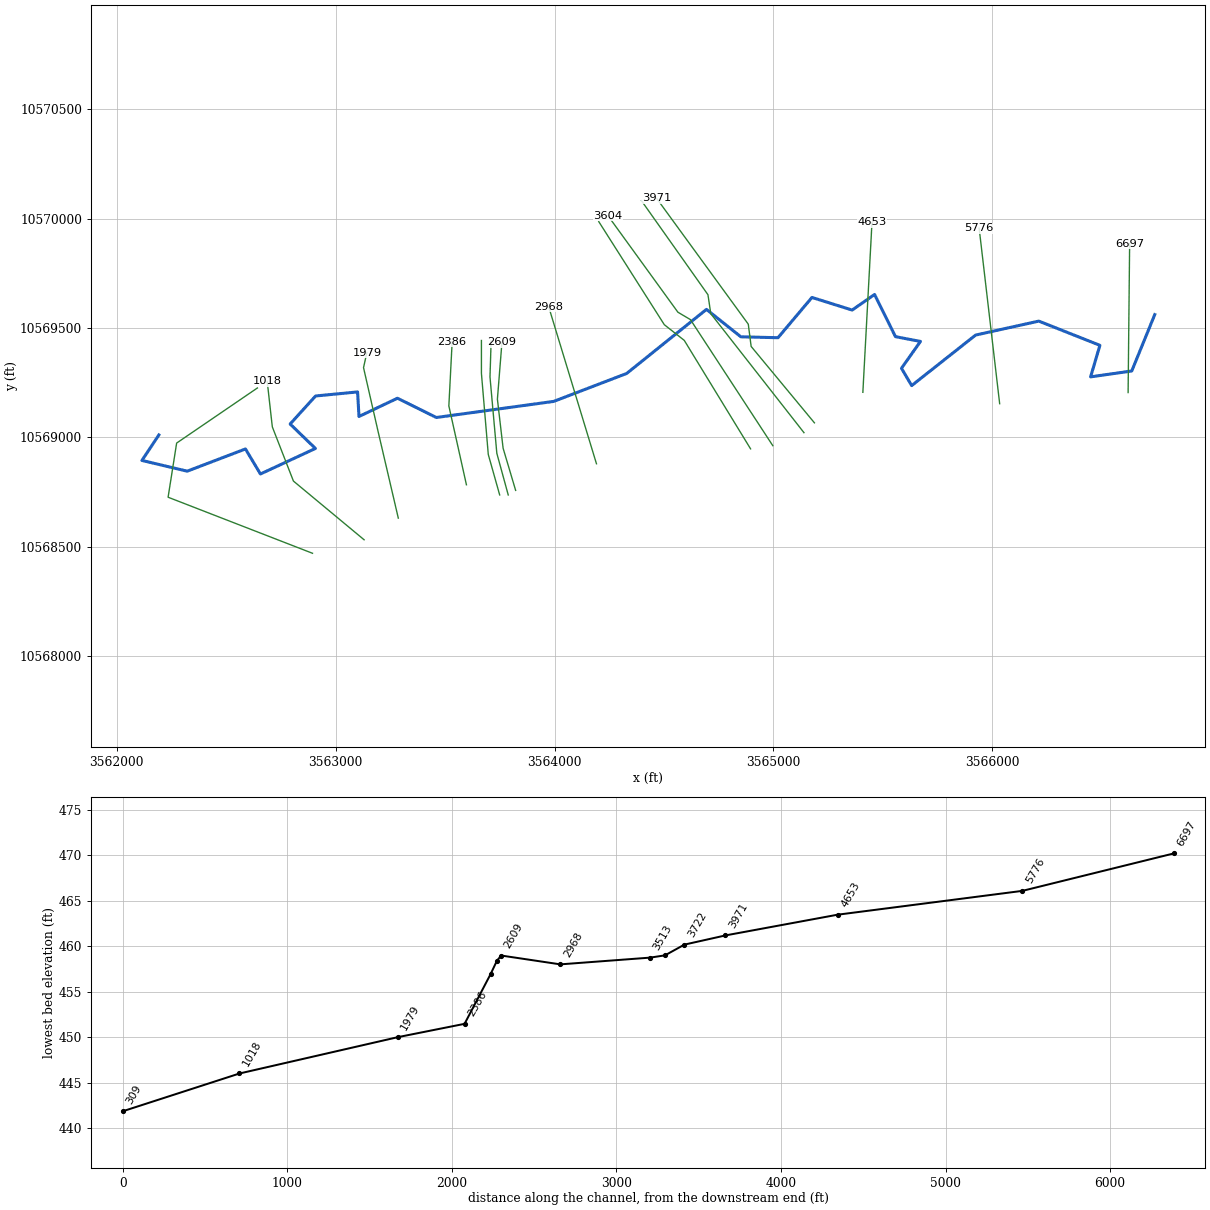
--- UNT0621 IN SAND CR.prj (project) ---

Proj Title=UNT0621 IN SAND CR Base Level Engineering
Current Plan=p01
Default Exp/Contr=0.3,0.1
English Units
Geom File=g01
Flow File=f01
Plan File=p01
Y Axis Title=Elevation
X Axis Title(PF)=Main Channel Distance
X Axis Title(XS)=Station
BEGIN DESCRIPTION:
UNT0621 IN SAND CR
END DESCRIPTION:
DSS Export Rating Curves= 0
DSS Export Rating Curve Sorted= 0
DSS Export Volume Flow Curves= 0
DXF OffsetX= 0
DXF OffsetY= 0
DXF ScaleX= 1
DXF ScaleY= 10

--- UNT0621 IN SAND CR.p01 (plan) ---

Plan Title=Multiple Run
Short Identifier=Multiple
Geom File=g01
Flow File=f01
Subcritical Flow
K Sum by GR= 0
Std Step Tol= 0.01
Critical Tol= 0.01
Num of Std Step Trials= 20
Max Error Tol= 0.3
Flow Tol Ratio= 0.001
Split Flow NTrial= 30
Split Flow Tol= 0.02
Split Flow Ratio= 0.02
Log Output Level= 0
Friction Slope Method= 1
Unsteady Friction Slope Method= 2
Unsteady Bridges Friction Slope Method= 1
Parabolic Critical Depth
Global Vel Dist=  1 , 1 , 1
Global Log Level= 0
CheckData=True
Encroach Param= -1, 0, 0, 0
BEGIN DESCRIPTION:
Multiple Run
END DESCRIPTION:

--- UNT0621 IN SAND CR.f01 (steady flow) ---

Flow Title=Multiple
Number of Profiles=7
Profile Names=10-year,25-year,50-year,1pct_min,100-year,1pct_plu,500-year
River Rch & RM= UNT0621 IN SAND ,Reach-1,6697
     718     966    1166    1029    1392    1883    1975
River Rch & RM= UNT0621 IN SAND ,Reach-1,3604
     824    1118    1357    1203    1627    2201    2331
Boundary for River Rch & Prof#=UNT0621 IN SAND ,Reach-1,1
Up Type=0
Dn Type=3
Dn Slope=0.005
Boundary for River Rch & Prof#=UNT0621 IN SAND ,Reach-1,2
Up Type=0
Dn Type=3
Dn Slope=0.005
Boundary for River Rch & Prof#=UNT0621 IN SAND ,Reach-1,3
Up Type=0
Dn Type=3
Dn Slope=0.005
Boundary for River Rch & Prof#=UNT0621 IN SAND ,Reach-1,4
Up Type=0
Dn Type=3
Dn Slope=0.005
Boundary for River Rch & Prof#=UNT0621 IN SAND ,Reach-1,5
Up Type=0
Dn Type=3
Dn Slope=0.005
Boundary for River Rch & Prof#=UNT0621 IN SAND ,Reach-1,6
Up Type=0
Dn Type=3
Dn Slope=0.005
Boundary for River Rch & Prof#=UNT0621 IN SAND ,Reach-1,7
Up Type=0
Dn Type=3
Dn Slope=0.005

--- UNT0621 IN SAND CR.g01 (geometry) ---

Geom Title=Existing Conditions
Program Version=4.10

River Reach=UNT0621 IN SAND ,Reach-1
Reach XY= 30
      3566742.11     10569561.64       3566636.9     10569303.82
      3566448.99      10569277.1      3566491.44     10569421.09
      3566212.26      10569531.7      3565923.62     10569467.99
      3565631.36     10569237.09      3565584.83     10569316.26
      3565671.64     10569438.83       3565557.4      10569460.7
      3565461.92     10569653.41      3565359.49     10569582.23
      3565175.81     10569639.87       3565020.6     10569455.84
      3564851.15     10569460.01      3564693.86     10569585.36
      3564329.34     10569292.53      3563996.01     10569164.92
      3563459.88     10569091.34      3563282.13     10569179.39
      3563106.31     10569095.99      3563099.95     10569208.16
      3562908.07     10569189.62       3562791.8     10569061.65
      3562907.23     10568949.87      3562656.03     10568833.25
      3562587.69     10568947.61      3562321.63      10568846.1
      3562114.68     10568895.16      3562192.11     10569011.64

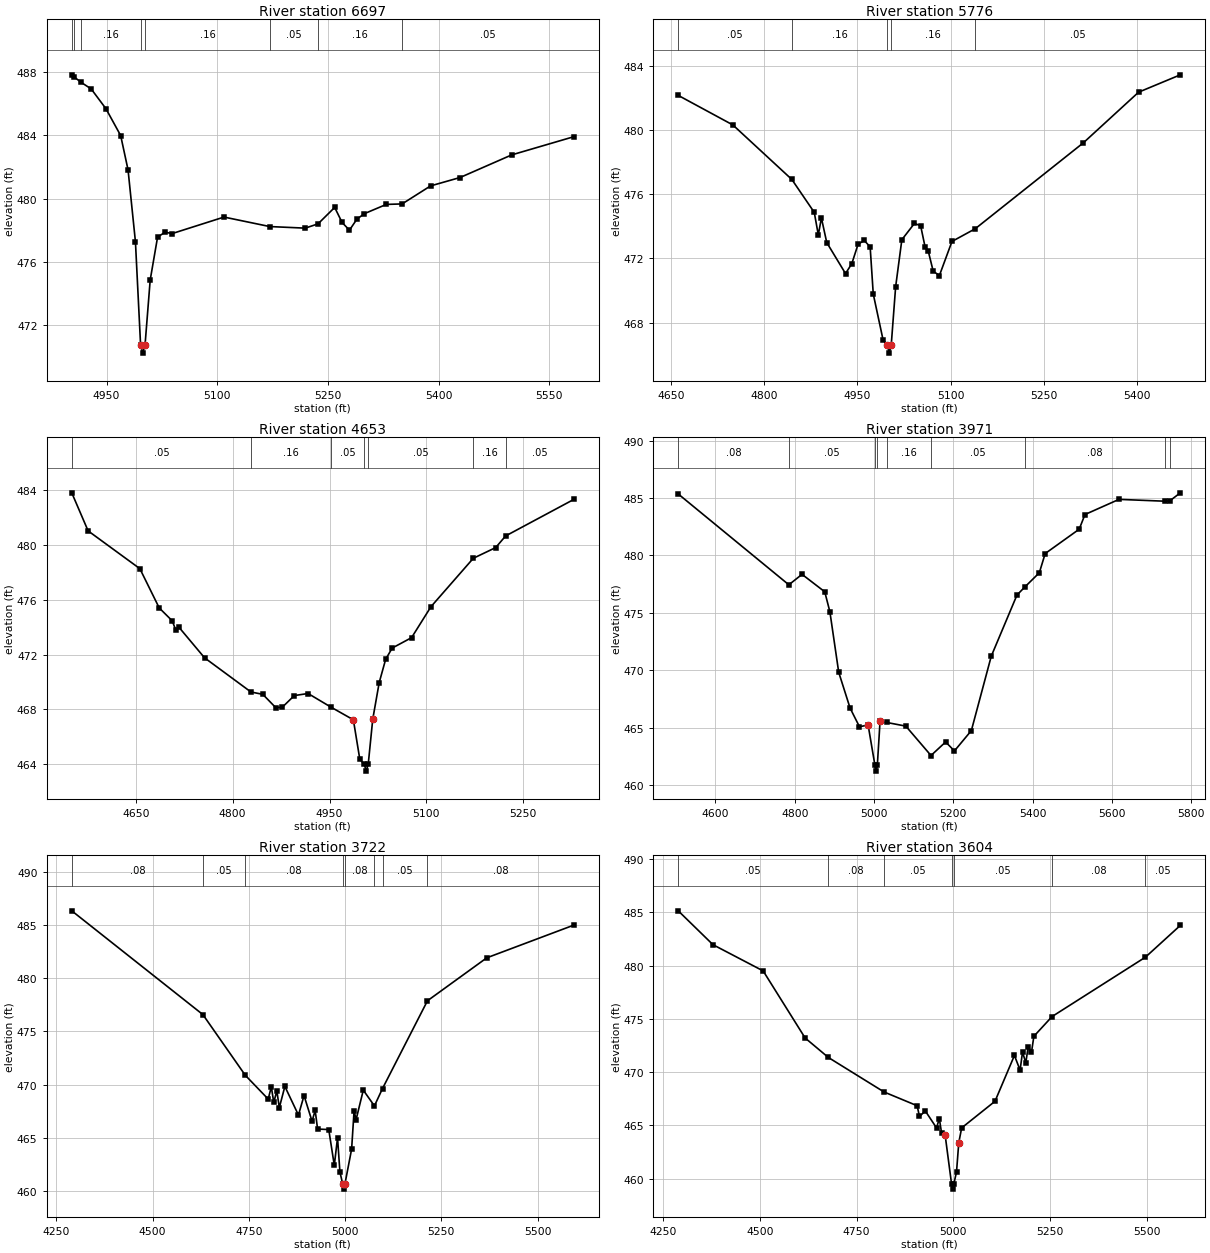
Type RM Length L Ch R = 1 ,6697    ,921,921,921
BEGIN DESCRIPTION:
UNT0621 IN SAND CR 10.0
END DESCRIPTION:
XS GIS Cut Line= 2
       3566620.3      10569205.3      3566627.24     10569885.86
#Sta/Elev= 30
  4902.8  487.82  4905.9  487.69  4915.6  487.34  4929.1  486.93  4949.1  485.68
  4969.1  483.98  4979.1  481.81  4989.1  477.27  4996.1  470.73  4998.9  470.23
  5002.1  470.73  5009.1  474.85  5019.1  477.56  5029.1  477.87  5039.1  477.79
  5109.2  478.83  5171.2  478.23  5219.2  478.13  5236.6   478.4  5259.2  479.44
  5269.2  478.49  5279.2     478  5289.2  478.69  5299.2  479.04  5329.2  479.63
  5350.6  479.66  5389.2   480.8  5429.2  481.33  5499.2  482.76  5583.4  483.91
#Mann= 8 ,-1 , 0
  4902.8     .16       0  4905.9     .05       0  4915.6     .16       0
  4996.1     .07       0  5002.1     .16       0  5171.2     .05       0
  5236.6     .16       0  5350.6     .05       0
Bank Sta=4996.1,5002.1
XS Rating Curve= 0 ,0
Exp/Cntr=0.3,0.1

Type RM Length L Ch R = 1 ,5776    ,1123,1123,1123
BEGIN DESCRIPTION:
UNT0621 IN SAND CR 9.0
END DESCRIPTION:
XS GIS Cut Line= 2
      3566033.44     10569154.34      3565939.68     10569956.48
#Sta/Elev= 30
  4661.9  482.15  4749.8  480.31  4844.6  476.92  4880.7  474.87  4887.2  473.47
  4892.2  474.52  4900.8  472.99    4931  471.06  4941.1  471.68  4951.2  472.89
  4961.2  473.12  4970.6  472.72  4975.6  469.79  4991.4  466.93  4998.5  466.61
  5001.2  466.11  5004.5  466.61  5011.6  470.24  5021.6  473.17  5041.8  474.18
  5051.8  474.04  5058.9  472.73    5064  472.47    5072  471.21    5082  470.94
  5102.2  473.06  5139.6  473.85  5313.6   479.2  5402.4  482.35  5469.5  483.43
#Mann= 5 ,-1 , 0
  4661.9     .05       0  4844.6     .16       0  4998.5     .07       0
  5004.5     .16       0  5139.6     .05       0
Bank Sta=4998.5,5004.5
XS Rating Curve= 0 ,0
Exp/Cntr=0.3,0.1

Type RM Length L Ch R = 1 ,4653    ,682,682,682
BEGIN DESCRIPTION:
UNT0621 IN SAND CR 8.0
END DESCRIPTION:
XS GIS Cut Line= 2
      3565408.43      10569206.4       3565450.1     10569982.48
#Sta/Elev= 30
    4551  483.82  4576.3  481.04  4656.4  478.28  4686.4  475.41  4706.5  474.47
  4712.1  473.78  4717.1  473.99  4756.5  471.77  4828.4  469.27  4846.7   469.1
  4866.7  468.13  4876.7  468.15  4895.5  469.01  4916.8  469.16  4952.4  468.16
  4986.9  467.24  4996.9  464.35  5003.9  463.99  5006.7  463.49  5009.9  463.99
  5016.9  467.28  5026.9  469.96  5036.9  471.66    5047  472.48    5077  473.24
    5107   475.5  5172.6  479.04  5207.2  479.82  5222.6  480.67  5328.2  483.34
#Mann= 7 ,-1 , 0
    4551     .05       0  4828.4     .16       0  4952.4     .05       0
  5003.9     .03       0  5009.9     .05       0  5172.6     .16       0
  5222.6     .05       0
Bank Sta=4986.9,5016.9
XS Rating Curve= 0 ,0
Exp/Cntr=0.3,0.1

Type RM Length L Ch R = 1 ,3971    ,249,249,249
BEGIN DESCRIPTION:
UNT0621 IN SAND CR 7.0
END DESCRIPTION:
XS GIS Cut Line= 4
      3565187.11     10569067.04      3564898.02     10569416.03
        3564885.      10569517.6      3564466.39     10570092.21
#Sta/Elev= 30
  4506.1  485.35  4785.1  477.44  4818.4  478.35  4875.7  476.83  4888.7  475.08
  4910.9  469.82  4939.6   466.7  4963.2  465.08  4985.1  465.22  5002.3  461.71
    5005  461.21  5008.3  461.71  5015.3  465.61  5031.7  465.45  5080.2  465.13
  5143.7  462.57  5180.6  463.75  5202.8  462.97  5245.5  464.74  5295.7  471.22
  5360.6  476.55  5379.6  477.22    5417  478.49  5431.7  480.16  5517.5  482.28
  5532.1  483.56  5617.9  484.88  5733.6  484.72  5746.1  484.75  5772.6  485.45
#Mann= 9 ,-1 , 0
  4506.1     .08       0  4785.1     .05       0  5002.3     .03       0
  5008.3     .05       0  5031.7     .16       0  5143.7     .05       0
  5379.6     .08       0  5733.6     .05       0  5746.1     .08       0
Bank Sta=4985.1,5015.3
XS Rating Curve= 0 ,0
Exp/Cntr=0.3,0.1

Type RM Length L Ch R = 1 ,3722    ,118,118,118
BEGIN DESCRIPTION:
UNT0621 IN SAND CR 6.0
END DESCRIPTION:
XS GIS Cut Line= 4
      3565139.36     10569022.04       3564713.7     10569565.47
      3564700.68     10569652.28      3564396.98     10570081.79
#Sta/Elev= 30
  4290.2  486.32  4630.8  476.58  4740.8  470.89  4800.4  468.65  4808.5   469.8
  4814.8  468.35  4822.9  469.41  4829.3  467.85  4843.7  469.84    4879  467.15
  4893.5  468.98  4914.3  466.57  4922.4  467.59  4928.7  465.84  4957.7  465.79
  4972.1  462.43  4980.5  465.02  4986.7  461.81  4993.8   460.7  4996.6   460.2
  4999.8   460.7  5017.1  463.96  5023.5  467.57  5028.6  466.71  5047.4  469.49
  5076.3  468.01  5097.3  469.64  5214.1  477.88  5368.2  481.91  5594.3  484.98
#Mann= 8 ,-1 , 0
  4290.2     .08       0  4630.8     .05       0  4740.8     .08       0
  4993.8     .03       0  4999.8     .08       0  5076.3     .08       0
  5097.3     .05       0  5214.1     .08       0
Bank Sta=4993.8,4999.8
XS Rating Curve= 0 ,0
Exp/Cntr=0.3,0.1

Type RM Length L Ch R = 1 ,3604    ,91,91,91
BEGIN DESCRIPTION:
UNT0621 IN SAND CR 5.0
END DESCRIPTION:
XS GIS Cut Line= 4
      3564996.99     10568962.58      3564620.67     10569538.56
      3564563.38     10569572.42      3564244.39      10570012.5
#Sta/Elev= 30
  4288.9  485.15  4378.7  481.97  4508.4  479.51    4617  473.21  4677.1  471.38
  4821.1  468.14  4906.6  466.85  4912.6  465.84  4927.7  466.36  4956.7  464.77
  4963.9  465.65  4969.9  464.26    4979  464.09  4995.5  459.52  4998.3  459.02
  5001.5  459.52  5008.4  460.64  5014.2  463.38  5021.7  464.77  5107.9  467.27
  5158.1  471.57  5172.8  470.19    5179  471.89  5187.5  470.88  5193.7  472.38
  5202.2  471.87  5208.4  473.37  5255.3  475.22  5496.9   480.8    5587  483.78
#Mann= 7 ,-1 , 0
  4288.9     .05       0  4677.1     .08       0  4821.1     .05       0
  4995.5     .03       0  5001.5     .05       0  5255.3     .08       0
  5496.9     .05       0
Bank Sta=4979,5014.2
XS Rating Curve= 0 ,0
Exp/Cntr=0.3,0.1

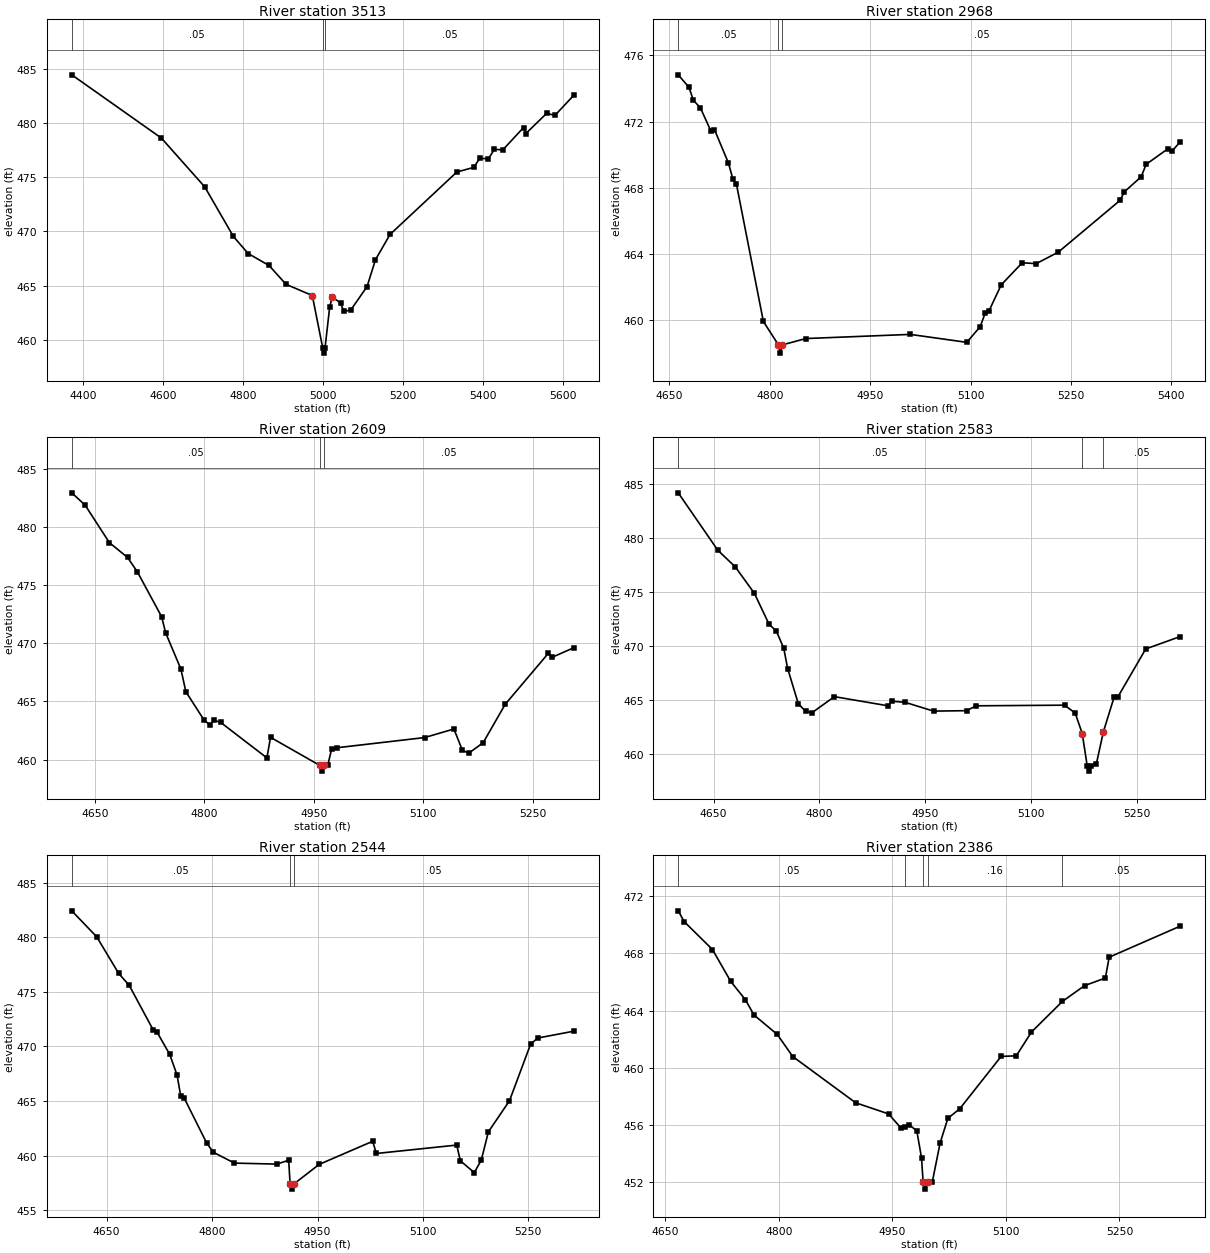
Type RM Length L Ch R = 1 ,3513    ,545,545,545
BEGIN DESCRIPTION:
UNT0621 IN SAND CR 5.1
END DESCRIPTION:
XS GIS Cut Line= 4
      3564895.43     10568948.04      3564592.46     10569443.73
      3564501.32     10569515.34      3564201.86     10569986.23
#Sta/Elev= 30
  4371.8  484.42  4595.8  478.59  4704.2  474.09  4775.8  469.52  4812.6  467.95
  4864.8  466.85  4907.4  465.11    4973  464.08  4998.9  459.27  5001.6  458.77
  5004.9  459.27  5016.3  462.98  5022.7  463.95  5043.5  463.39  5051.6  462.63
  5068.7  462.72  5109.8   464.9  5130.9  467.38  5167.3  469.71  5334.2  475.46
  5376.5  475.89  5391.7  476.74  5412.9  476.67  5428.1  477.55  5449.3  477.51
    5501  479.56  5506.9  479.01  5558.5  480.86  5579.7  480.69  5626.7  482.54
#Mann= 3 ,-1 , 0
  4371.8     .05       0  4998.9     .03       0  5004.9     .05       0
Bank Sta=4973,5022.7
XS Rating Curve= 0 ,0
Exp/Cntr=0.3,0.1

Type RM Length L Ch R = 1 ,2968    ,359,359,359
BEGIN DESCRIPTION:
UNT0621 IN SAND CR 3.0
END DESCRIPTION:
XS GIS Cut Line= 2
      3564191.36     10568879.96      3563972.93     10569597.65
#Sta/Elev= 30
  4663.2  474.82  4679.2  474.07  4685.9  473.28  4696.3  472.83  4712.1  471.42
  4717.3  471.52  4738.1  469.51  4744.9  468.53  4750.2  468.22  4790.4  459.94
  4812.9  458.53  4815.6  458.03  4818.9  458.53  4853.9  458.91  5009.9  459.16
  5094.4  458.68  5114.4  459.63    5122  460.46  5127.2  460.55  5145.8  462.15
  5177.2  463.48  5198.1  463.43    5231  464.12  5323.5  467.25  5329.5  467.75
  5354.9  468.67  5362.4  469.42  5395.2  470.37  5400.5   470.2  5413.4  470.78
#Mann= 3 ,-1 , 0
  4663.2     .05       0  4812.9    .035       0  4818.9     .05       0
Bank Sta=4812.9,4818.9
XS Rating Curve= 0 ,0
Exp/Cntr=0.3,0.1

Type RM Length L Ch R = 1 ,2609    ,26,26,26
BEGIN DESCRIPTION:
UNT0621 IN SAND CR 4.1
END DESCRIPTION:
XS GIS Cut Line= 4
      3563822.07     10568758.34      3563764.77     10568951.07
      3563738.73     10569175.03      3563759.56     10569435.46
#Sta/Elev= 30
  4618.6  482.97  4636.9  481.91  4670.1  478.68  4695.1   477.4  4708.5  476.16
  4741.7   472.3  4747.2  470.91  4768.1  467.79  4774.9  465.84  4799.4  463.44
    4808  462.95  4813.3  463.38  4822.5   463.2  4885.9  460.14  4890.9  461.91
  4958.2   459.5  4960.9     459  4964.2   459.5  4969.4  459.54  4974.5  460.88
  4981.3  461.01  5101.9  461.89  5142.1  462.63  5153.6  460.81  5162.1  460.53
  5182.2  461.45  5212.3  464.75  5271.5  469.15  5276.5   468.8  5306.4  469.63
#Mann= 3 ,-1 , 0
  4618.6     .05       0  4958.2    .035       0  4964.2     .05       0
Bank Sta=4958.2,4964.2
XS Rating Curve= 0 ,0
Exp/Cntr=0.3,0.1

Type RM Length L Ch R = 1 ,2583    ,39,39,39
BEGIN DESCRIPTION:
UNT0621 IN SAND CR 4.0
END DESCRIPTION:
XS GIS Cut Line= 4
      3563788.22     10568737.49      3563736.12     10568927.63
      3563704.87     10569276.59      3563710.08     10569440.61
#Sta/Elev= 30
  4599.9  484.22    4656   478.9  4680.9  477.35  4707.9   474.9  4728.6  472.05
    4739  471.41  4749.4  469.83    4755  467.94  4770.1  464.68  4780.5  463.97
  4789.5  463.85  4821.2  465.34  4897.3  464.49  4902.3  464.92  4921.6  464.81
  4961.7     464  5008.6  464.04    5022  464.49  5147.4  464.55  5162.5  463.82
  5172.5  461.92  5179.5  458.94  5182.2  458.44  5185.5  458.94  5192.5  459.11
  5202.5  462.09  5217.6  465.28  5222.6  465.27  5262.5  469.76  5311.5  470.91
#Mann= 3 , 0 , 0
  4599.9     .05       0  5172.5    .035       0  5202.5     .05       0
Bank Sta=5172.5,5202.5
XS Rating Curve= 0 ,0
Exp/Cntr=0.3,0.1

Type RM Length L Ch R = 1 ,2544    ,158,158,158
BEGIN DESCRIPTION:
UNT0621 IN SAND CR 4.2
END DESCRIPTION:
XS GIS Cut Line= 4
      3563749.16     10568737.49      3563697.06     10568922.42
      3563665.81     10569292.21      3563665.81     10569443.28
#Sta/Elev= 30
  4600.4  482.41  4635.9  480.03    4667   476.7  4682.2  475.58  4716.2  471.52
  4721.4  471.35  4739.8  469.27  4750.2  467.38  4755.4  465.48  4760.6  465.25
  4792.4  461.16  4801.8  460.32  4831.9  459.33  4892.1  459.24    4909  459.59
    4911  457.45  4913.7  456.95    4917  457.45  4952.3  459.21  5028.6  461.33
  5033.6  460.21  5148.1  460.98  5153.2  459.54  5173.1  458.46  5183.1  459.62
  5193.1  462.19  5223.1  465.03  5253.1   470.2  5263.1  470.77  5314.7   471.4
#Mann= 3 ,-1 , 0
  4600.4     .05       0    4911    .035       0    4917     .05       0
Bank Sta=4911,4917
XS Rating Curve= 0 ,0
Exp/Cntr=0.3,0.1

Type RM Length L Ch R = 1 ,2386    ,407,407,407
BEGIN DESCRIPTION:
UNT0621 IN SAND CR 2.0
END DESCRIPTION:
XS GIS Cut Line= 3
      3563597.24     10568783.94      3563516.94     10569144.21
      3563532.06     10569438.02
#Sta/Elev= 30
  4667.1  470.99    4675  470.23  4712.3  468.28  4736.5  466.04  4755.7  464.77
  4767.2  463.69  4797.9  462.33  4818.4  460.78  4901.5  457.54    4945  456.76
  4961.9  455.74  4966.1  455.85  4972.1  456.01  4982.3  455.57  4988.5  453.68
  4990.6  451.99  4993.4  451.49  4996.6  451.99  5002.8  452.01  5013.1  454.73
  5023.3  456.45    5039  457.12  5093.7  460.79  5113.7  460.83  5133.8   462.5
  5174.6  464.64  5203.9  465.75  5231.4  466.28  5236.4  467.74  5330.4  469.92
#Mann= 5 ,-1 , 0
  4667.1     .05       0  4966.1     .16       0  4990.6     .07       0
  4996.6     .16       0  5174.6     .05       0
Bank Sta=4990.6,4996.6
XS Rating Curve= 0 ,0
Exp/Cntr=0.3,0.1

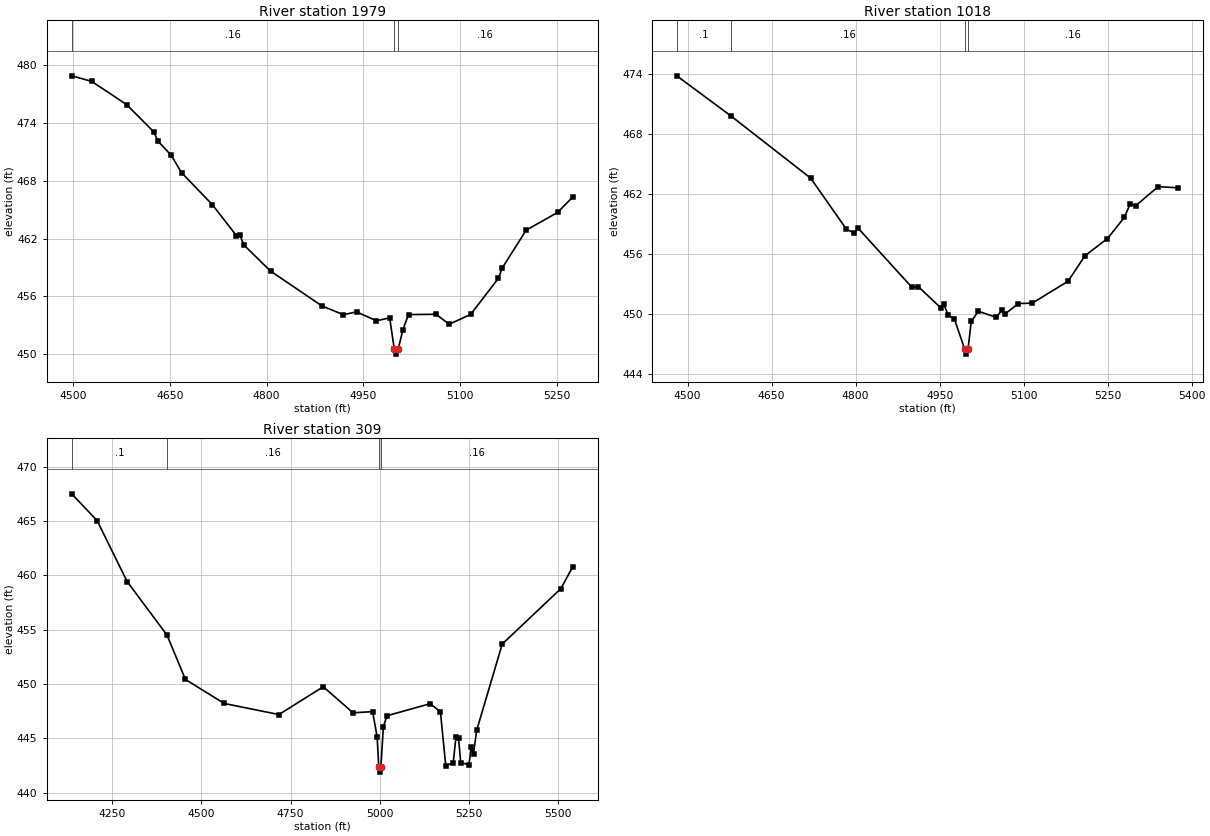
Type RM Length L Ch R = 1 ,1979    ,961,961,961
BEGIN DESCRIPTION:
UNT0621 IN SAND CR 2.1
END DESCRIPTION:
XS GIS Cut Line= 4
      3563285.95     10568631.67      3563193.79     10569026.71
      3563127.08     10569319.21      3563142.38     10569388.07
#Sta/Elev= 30
  4498.1  478.87  4528.9   478.3  4583.2  475.89  4625.7  473.03  4631.6  472.11
  4652.1  470.65  4668.3  468.83    4716  465.52  4753.4   462.3  4758.5  462.39
  4765.1  461.32  4806.2  458.63  4886.1  455.01  4919.1  454.11  4939.6   454.4
  4970.3  453.48  4990.9  453.78  4998.1  450.52  5000.9  450.02  5004.1  450.52
  5011.4  452.56  5020.1  454.12  5062.7  454.15  5083.2  453.12  5116.4  454.14
  5159.4  457.88  5165.2  458.93  5202.4  462.87  5251.2  464.71  5274.3  466.29
#Mann= 3 ,-1 , 0
  4498.1     .16       0  4998.1     .07       0  5004.1     .16       0
Bank Sta=4998.1,5004.1
XS Rating Curve= 0 ,0
Exp/Cntr=0.3,0.1

Type RM Length L Ch R = 1 ,1018    ,709,709,709
BEGIN DESCRIPTION:
UNT0621 IN SAND CR 1.0
END DESCRIPTION:
XS GIS Cut Line= 4
      3563129.72     10568532.73      3562806.77     10568800.98
      3562710.42     10569048.38      3562687.04     10569256.14
#Sta/Elev= 30
  4480.6  473.79  4577.2  469.79  4719.7  463.58  4783.5  458.49  4797.9  458.11
  4804.4  458.59  4900.2  452.71  4911.9  452.76    4952  450.65  4957.4  450.99
  4965.5  449.92  4976.3  449.54  4994.7  446.53  4997.5  446.03  5000.7  446.53
  5006.4   449.3  5019.2  450.31  5051.4  449.69  5060.8   450.4  5066.2  450.01
  5090.7  451.08  5115.2  451.11  5179.3   453.3  5209.5  455.84  5249.7  457.56
  5279.9  459.67    5290  460.99    5300  460.83  5340.3  462.74    5375  462.62
#Mann= 4 ,-1 , 0
  4480.6      .1       0  4577.2     .16       0  4994.7     .07       0
  5000.7     .16       0
Bank Sta=4994.7,5000.7
XS Rating Curve= 0 ,0
Exp/Cntr=0.3,0.1

Type RM Length L Ch R = 1 ,309     ,0,0,0
BEGIN DESCRIPTION:
UNT0621 IN SAND CR 1.1
END DESCRIPTION:
XS GIS Cut Line= 4
      3562893.94     10568471.01      3562234.21     10568727.09
      3562273.27     10568974.49      3562642.21     10569226.24
#Sta/Elev= 30
  4136.2   467.5  4207.5  465.03  4291.8  459.42  4403.6  454.49  4455.2  450.41
  4564.1   448.2  4717.4  447.18  4841.7  449.74  4925.5  447.34  4980.1  447.45
    4993  445.12  4997.4  442.38  5000.1  441.88  5003.4  442.38  5010.5  446.08
  5020.6  447.07  5141.4  448.18  5170.4  447.44  5185.3  442.49  5206.3  442.73
    5214  445.12  5221.2  445.03  5227.3  442.76  5250.3  442.56  5257.1  444.18
  5263.2  443.57    5272  445.72  5343.8  453.67  5508.4  458.78    5541  460.75
#Mann= 4 ,-1 , 0
  4136.2      .1       0  4403.6     .16       0  4997.4     .07       0
  5003.4     .16       0
Bank Sta=4997.4,5003.4
XS Rating Curve= 0 ,0
Exp/Cntr=0.3,0.1

Chan Stop Cuts=-1
Use User Specified Reach Order=0
Composite Channel Slope=5