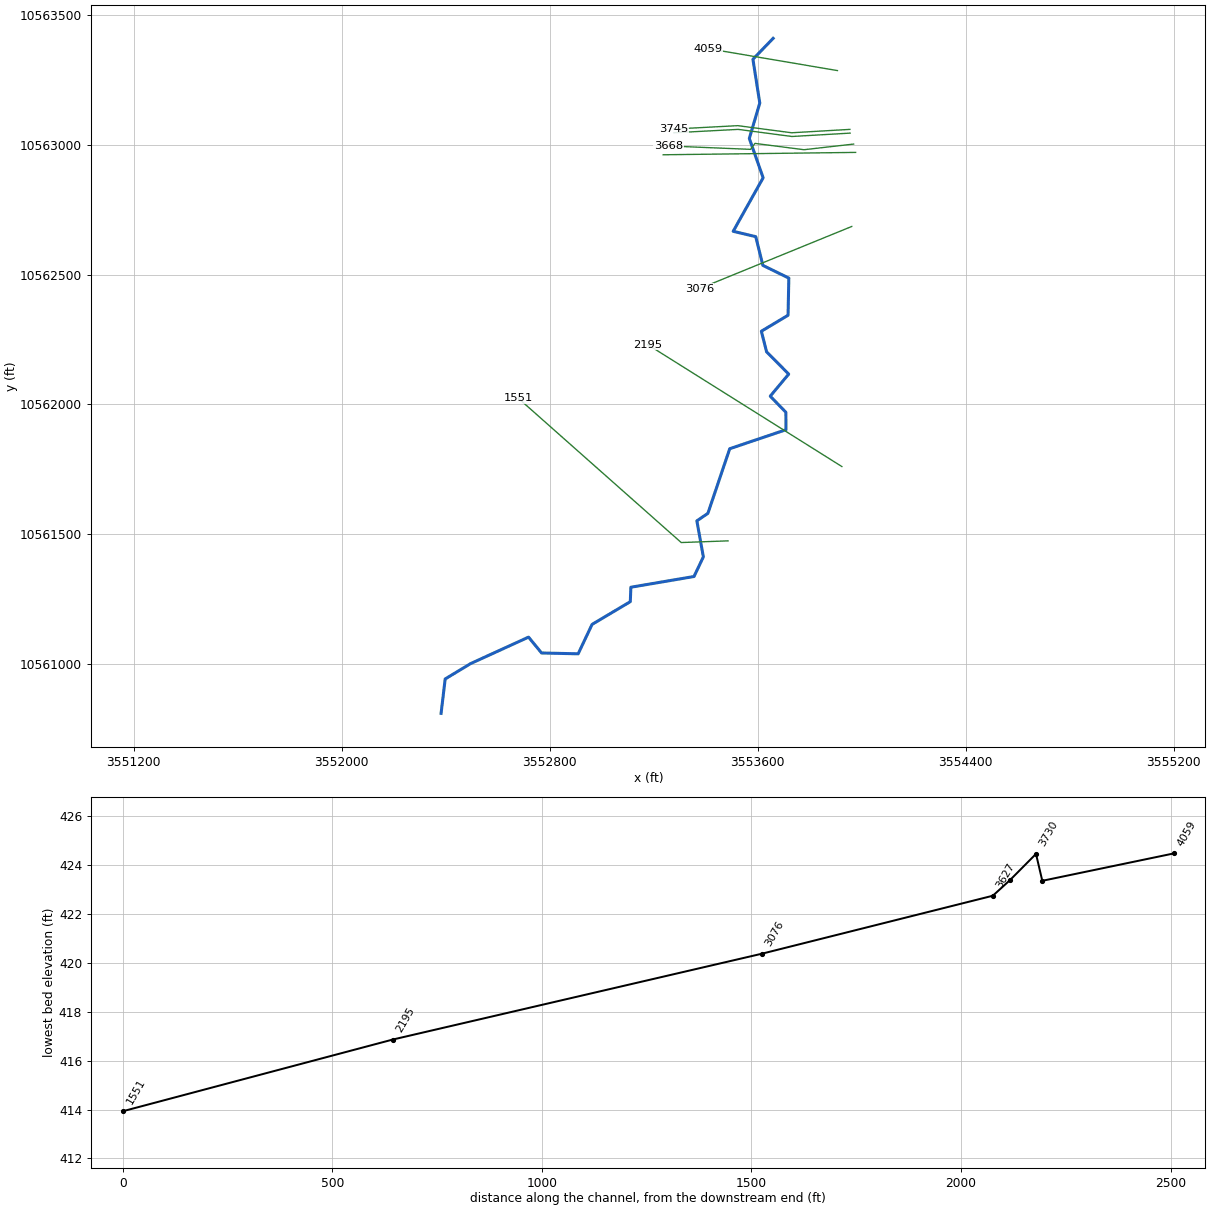
--- UNT0626 IN SAND CR.prj (project) ---

Proj Title=UNT0626 IN SAND CR Base Level Engineering
Current Plan=p01
Default Exp/Contr=0.3,0.1
English Units
Geom File=g01
Flow File=f01
Plan File=p01
BEGIN DESCRIPTION:
UNT0626 IN SAND CR
END DESCRIPTION:

--- UNT0626 IN SAND CR.p01 (plan) ---

Plan Title=Multiple Run
Short Identifier=Multiple
Geom File=g01
Flow File=f01
Subcritical Flow
K Sum by GR= 0
Std Step Tol= 0.01
Critical Tol= 0.01
Num of Std Step Trials= 20
Max Error Tol= 0.3
Flow Tol Ratio= 0.001
Split Flow NTrial= 30
Split Flow Tol= 0.02
Split Flow Ratio= 0.02
Log Output Level= 0
Friction Slope Method= 1
Unsteady Friction Slope Method= 2
Unsteady Bridges Friction Slope Method= 1
Parabolic Critical Depth
Global Vel Dist=  1 , 1 , 1
Global Log Level= 0
CheckData=True
Encroach Param= -1, 0, 0, 0
BEGIN DESCRIPTION:
Multiple Run
END DESCRIPTION:

--- UNT0626 IN SAND CR.f01 (steady flow) ---

Flow Title=Multiple
Number of Profiles=7
Profile Names=10-year,25-year,50-year,1pct_min,100-year,1pct_plu,500-year
River Rch & RM= UNT0626 IN SAND ,Reach-1,4059
     620     821     980     855    1157    1565    1605
Boundary for River Rch & Prof#=UNT0626 IN SAND ,Reach-1,1
Up Type=0
Dn Type=3
Dn Slope=0.005
Boundary for River Rch & Prof#=UNT0626 IN SAND ,Reach-1,2
Up Type=0
Dn Type=3
Dn Slope=0.005
Boundary for River Rch & Prof#=UNT0626 IN SAND ,Reach-1,3
Up Type=0
Dn Type=3
Dn Slope=0.005
Boundary for River Rch & Prof#=UNT0626 IN SAND ,Reach-1,4
Up Type=0
Dn Type=3
Dn Slope=0.005
Boundary for River Rch & Prof#=UNT0626 IN SAND ,Reach-1,5
Up Type=0
Dn Type=3
Dn Slope=0.005
Boundary for River Rch & Prof#=UNT0626 IN SAND ,Reach-1,6
Up Type=0
Dn Type=3
Dn Slope=0.005
Boundary for River Rch & Prof#=UNT0626 IN SAND ,Reach-1,7
Up Type=0
Dn Type=3
Dn Slope=0.005

--- UNT0626 IN SAND CR.g01 (geometry) ---

Geom Title=Existing Conditions

River Reach=UNT0626 IN SAND ,Reach-1
Reach XY= 30
      3553659.62     10563408.60      3553581.78     10563328.01
      3553608.17     10563159.61      3553567.89     10563023.50
      3553621.06     10562872.14      3553505.88     10562666.21
      3553592.56     10562645.67      3553620.02     10562535.17
      3553719.90     10562486.24      3553716.92     10562343.31
      3553614.20     10562281.72      3553634.38     10562202.55
      3553719.42     10562116.92      3553648.37     10562031.88
      3553708.61     10561969.99      3553708.97     10561902.89
      3553492.54     10561829.75      3553408.52     10561581.14
      3553366.10     10561552.28      3553391.10     10561413.73
      3553355.17     10561338.21      3553112.22     10561296.92
      3553110.05     10561241.37      3552962.91     10561153.91
      3552909.50     10561040.79      3552768.61     10561044.01
      3552718.61     10561104.99      3552495.77     10561003.18
      3552397.81     10560943.99      3552382.11     10560811.64

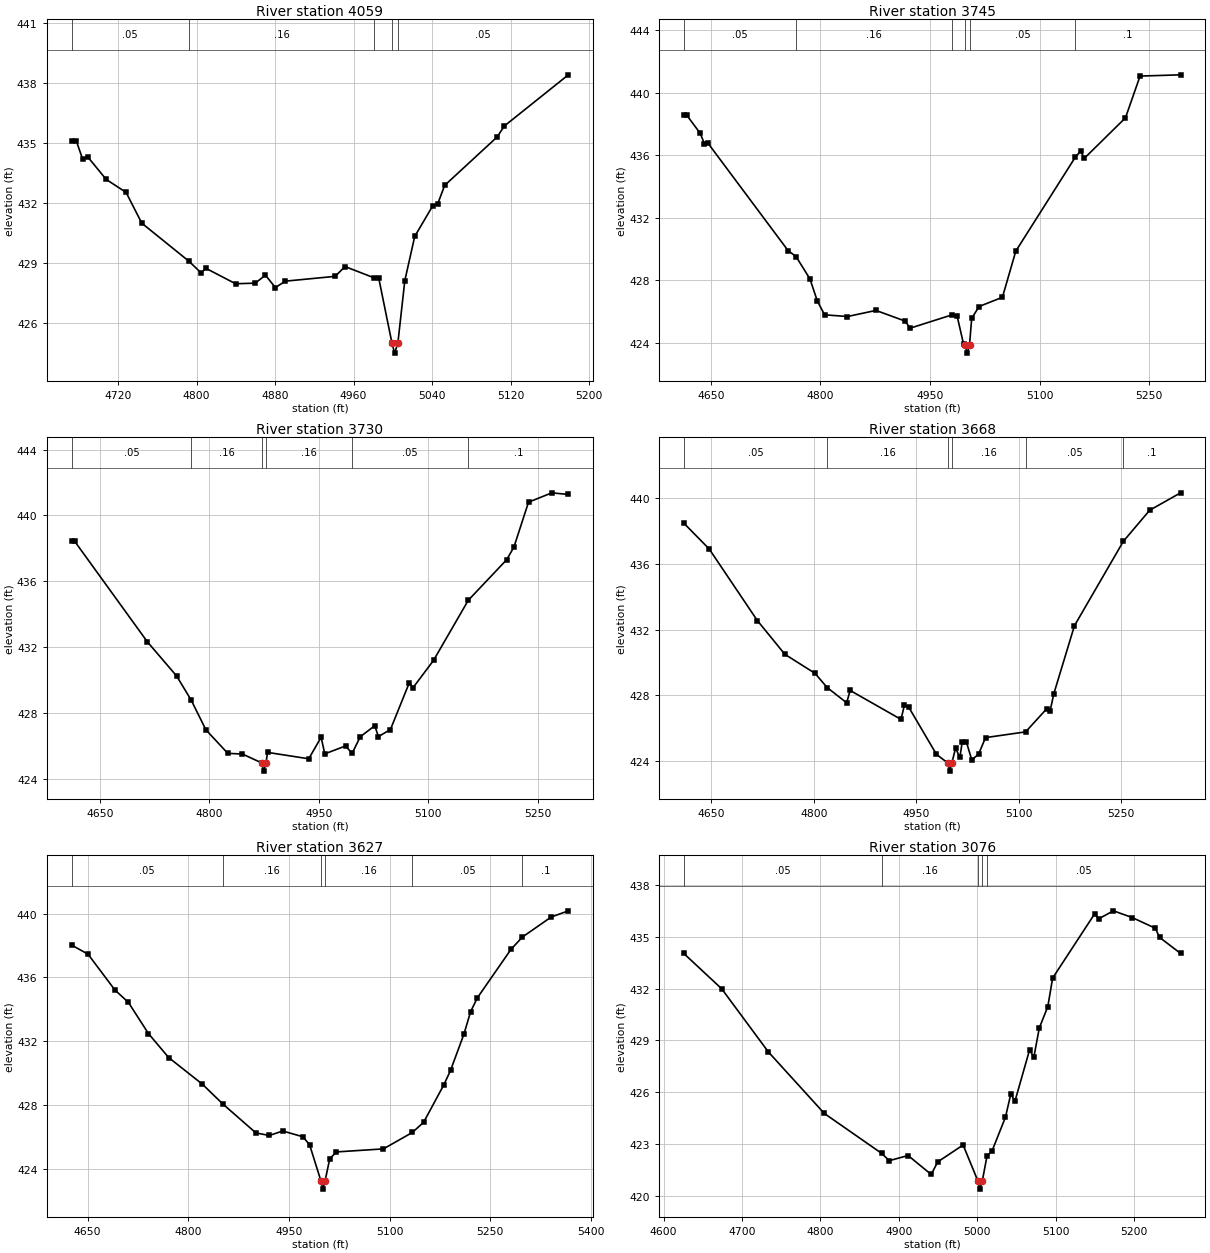
Type RM Length L Ch R = 1,4059,314,314,314
BEGIN DESCRIPTION:
UNT0626 IN SAND CR 3.4
END DESCRIPTION:
XS GIS Cut Line= 2
      3553906.93     10563284.56      3553407.85     10563369.18
#Sta/Elev= 30
  4672.6  435.07  4677.6  435.07  4683.8  434.19  4688.9  434.30  4707.9  433.16
  4728.2  432.51  4744.2  430.97  4792.4  429.06  4804.5  428.49  4809.6  428.71
  4839.8  427.94  4859.8  427.97  4870.2  428.37  4880.3  427.75  4890.5  428.07
  4941.2  428.31  4951.3  428.80  4980.7  428.24  4985.5  428.25  4999.1  424.97
  5001.8  424.47  5005.1  424.97  5012.2  428.10  5022.3  430.31  5040.8  431.85
  5045.8  431.95  5052.8  432.86  5106.2  435.28  5113.6  435.83  5178.8  438.39
#Mann=5,-1,0
  4672.6    0.05       0  4792.4    0.16       0  4980.7    0.05       0
  4999.1    0.03       0  5005.1    0.05       0
Bank Sta=4999.1,5005.1
Exp/Cntr=0.3,0.1

Type RM Length L Ch R = 1,3745,15,15,15
BEGIN DESCRIPTION:
UNT0626 IN SAND CR 3.3
END DESCRIPTION:
XS GIS Cut Line= 4
      3553954.70     10563058.32      3553730.74     10563045.30
      3553523.71     10563072.64      3553276.72     10563059.64
#Sta/Elev= 30
  4612.7  438.58  4616.5  438.58  4635.3  437.40  4640.9  436.75  4645.9  436.77
  4755.5  429.91  4766.6  429.52  4785.6  428.09  4795.6  426.69  4805.6  425.80
  4837.0  425.69  4876.0  426.08  4916.4  425.39  4922.5  424.94  4979.7  425.79
  4987.0  425.75  4996.0  423.92  4998.1  423.85  5000.8  423.35  5004.1  423.85
  5007.1  425.57  5017.2  426.33  5049.2  426.92  5067.5  429.87  5148.8  435.86
  5156.3  436.27  5161.3  435.80  5217.7  438.39  5237.7  441.06  5293.2  441.14
#Mann=6,-1,0
  4612.7    0.05       0  4766.6    0.16       0  4979.7    0.05       0
  4998.1    0.03       0  5004.1    0.05       0  5148.8     0.1       0
Bank Sta=4998.1,5004.1
Exp/Cntr=0.3,0.1

Type RM Length L Ch R = 1,3730,62,62,62
BEGIN DESCRIPTION:
UNT0626 IN SAND CR 3.2
END DESCRIPTION:
XS GIS Cut Line= 4
      3553955.96     10563043.99      3553732.04     10563030.97
      3553525.01     10563058.32      3553277.58     10563045.29
#Sta/Elev= 30
  4611.0  438.42  4615.4  438.42  4715.0  432.31  4755.1  430.23  4775.1  428.76
  4795.2  426.96  4825.2  425.53  4845.3  425.49  4871.6  424.95  4874.3  424.45
  4877.6  424.95  4879.6  425.59  4936.1  425.20  4953.1  426.51  4958.1  425.50
  4986.5  425.98  4995.6  425.53  5006.7  426.54  5026.6  427.21  5031.6  426.55
  5048.1  426.98  5074.0  429.83  5079.0  429.52  5107.1  431.18  5154.8  434.84
  5207.3  437.30  5217.3  438.07  5237.3  440.80  5269.3  441.37  5291.9  441.27
#Mann=6,-1,0
  4611.0    0.05       0  4775.1    0.16       0  4871.6    0.03       0
  4877.6    0.16       0  4995.6    0.05       0  5154.8     0.1       0
Bank Sta=4871.6,4877.6
Exp/Cntr=0.3,0.1

Type RM Length L Ch R = 1,3668,41,41,41
BEGIN DESCRIPTION:
UNT0626 IN SAND CR 3.0
END DESCRIPTION:
XS GIS Cut Line= 5
      3553969.18     10563001.84      3553778.19     10562980.13
      3553589.59     10563004.41      3553572.93     10562981.49
      3553256.90     10562994.51
#Sta/Elev= 30
  4609.7  438.48  4647.0  436.90  4717.5  432.54  4757.7  430.49  4801.9  429.33
  4819.5  428.47  4848.1  427.54  4853.2  428.29  4927.6  426.53  4932.7  427.41
  4939.1  427.26  4979.5  424.40  4996.0  423.88  4998.7  423.38  5002.0  423.88
  5007.5  424.78  5013.7  424.21  5017.2  425.15  5023.3  425.15  5031.2  424.06
  5041.2  424.42  5051.3  425.42  5110.0  425.77  5140.9  427.18  5145.9  427.07
  5151.3  428.10  5181.4  432.23  5253.0  437.37  5291.5  439.26  5336.7  440.32
#Mann=6,-1,0
  4609.7    0.05       0  4819.5    0.16       0  4996.0    0.07       0
  5002.0    0.16       0  5110.0    0.05       0  5253.0     0.1       0
Bank Sta=4996,5002
Exp/Cntr=0.3,0.1

Type RM Length L Ch R = 1,3627,551,551,551
BEGIN DESCRIPTION:
UNT0626 IN SAND CR 3.1
END DESCRIPTION:
XS GIS Cut Line= 2
      3553976.85     10562969.77      3553236.50     10562960.67
#Sta/Elev= 30
  4625.9  438.03  4650.6  437.45  4690.6  435.21  4710.6  434.44  4740.6  432.48
  4770.7  430.98  4820.7  429.32  4851.2  428.08  4900.7  426.26  4920.7  426.10
  4940.7  426.38  4970.7  426.02  4980.7  425.52  4997.7  423.24  5000.4  422.74
  5003.7  423.24  5010.7  424.64  5020.7  425.07  5090.7  425.26  5133.9  426.29
  5150.7  426.93  5180.7  429.27  5190.7  430.17  5210.7  432.45  5220.7  433.86
  5230.7  434.72  5280.7  437.75  5297.9  438.53  5340.7  439.78  5366.3  440.17
#Mann=6,-1,0
  4625.9    0.05       0  4851.2    0.16       0  4997.7    0.07       0
  5003.7    0.16       0  5133.9    0.05       0  5297.9     0.1       0
Bank Sta=4997.7,5003.7
Exp/Cntr=0.3,0.1

Type RM Length L Ch R = 1,3076,881,881,881
BEGIN DESCRIPTION:
UNT0626 IN SAND CR 2.1
END DESCRIPTION:
XS GIS Cut Line= 2
      3553962.04     10562684.86      3553375.26     10562445.28
#Sta/Elev= 30
  4625.6  434.04  4674.0  431.99  4733.5  428.33  4804.9  424.76  4878.2  422.44
  4887.8  422.02  4911.8  422.32  4941.3  421.22  4949.6  421.95  4982.0  422.93
  5000.6  420.87  5003.3  420.37  5006.6  420.87  5012.5  422.30  5018.7  422.56
  5036.0  424.54  5042.8  425.88  5048.2  425.48  5066.8  428.45  5072.2  428.02
  5079.2  429.72  5090.0  430.95  5096.2  432.61  5149.7  436.33  5155.1  436.05
  5173.7  436.51  5197.7  436.12  5227.2  435.50  5232.6  434.97  5259.4  434.04
#Mann=5,-1,0
  4625.6    0.05       0  4878.2    0.16       0  5000.6    0.07       0
  5006.6    0.16       0  5012.5    0.05       0
Bank Sta=5000.6,5006.6
Exp/Cntr=0.3,0.1

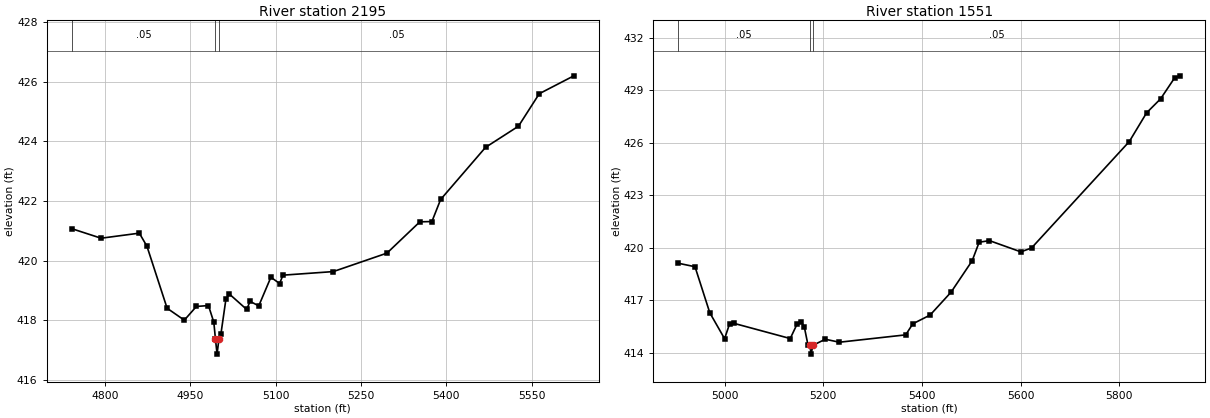
Type RM Length L Ch R = 1,2195,644,644,644
BEGIN DESCRIPTION:
UNT0626 IN SAND CR 2.0
END DESCRIPTION:
XS GIS Cut Line= 2
      3553923.91     10561761.24      3553177.38     10562230.00
#Sta/Elev= 30
  4742.2  421.07  4793.7  420.75  4860.8  420.92  4874.2  420.48  4909.6  418.40
  4939.8  418.00  4961.0  418.46  4982.2  418.49  4991.6  417.93  4994.5  417.36
  4997.3  416.86  5000.5  417.36  5004.1  417.54  5012.8  418.70  5018.7  418.88
  5049.3  418.36  5055.2  418.63  5070.5  418.48  5091.8  419.44  5107.1  419.23
  5113.0  419.51  5201.3  419.63  5295.6  420.25  5353.3  421.30  5374.5  421.31
  5389.8  422.05  5468.7  423.80  5526.5  424.51  5563.0  425.60  5623.7  426.20
#Mann=3,-1,0
  4742.2    0.05       0  4994.5    0.03       0  5000.5    0.05       0
Bank Sta=4994.5,5000.5
Exp/Cntr=0.3,0.1

Type RM Length L Ch R = 1,1551,0,0,0
BEGIN DESCRIPTION:
UNT0626 IN SAND CR 1.0
END DESCRIPTION:
XS GIS Cut Line= 3
      3553486.04     10561475.33      3553305.93     10561468.82
      3552678.74     10562024.39
#Sta/Elev= 30
  4905.8  419.12  4939.8  418.92  4969.8  416.29  4999.8  414.81  5009.8  415.65
  5019.8  415.68  5132.9  414.82  5147.2  415.67  5154.7  415.79  5161.4  415.49
  5168.9  414.45  5172.6  414.43  5175.4  413.93  5178.6  414.43  5204.0  414.78
  5232.5  414.61  5367.1  415.03  5381.4  415.66  5416.5  416.16  5459.1  417.47
  5501.8  419.26  5516.0  420.32  5536.9  420.41  5600.5  419.77  5622.2  419.99
  5820.5  426.07  5855.6  427.71  5884.0  428.51  5912.5  429.71  5923.9  429.82
#Mann=3,-1,0
  4905.8    0.05       0  5172.6    0.03       0  5178.6    0.05       0
Bank Sta=5172.6,5178.6
Exp/Cntr=0.3,0.1

Chan Stop Cuts=-1