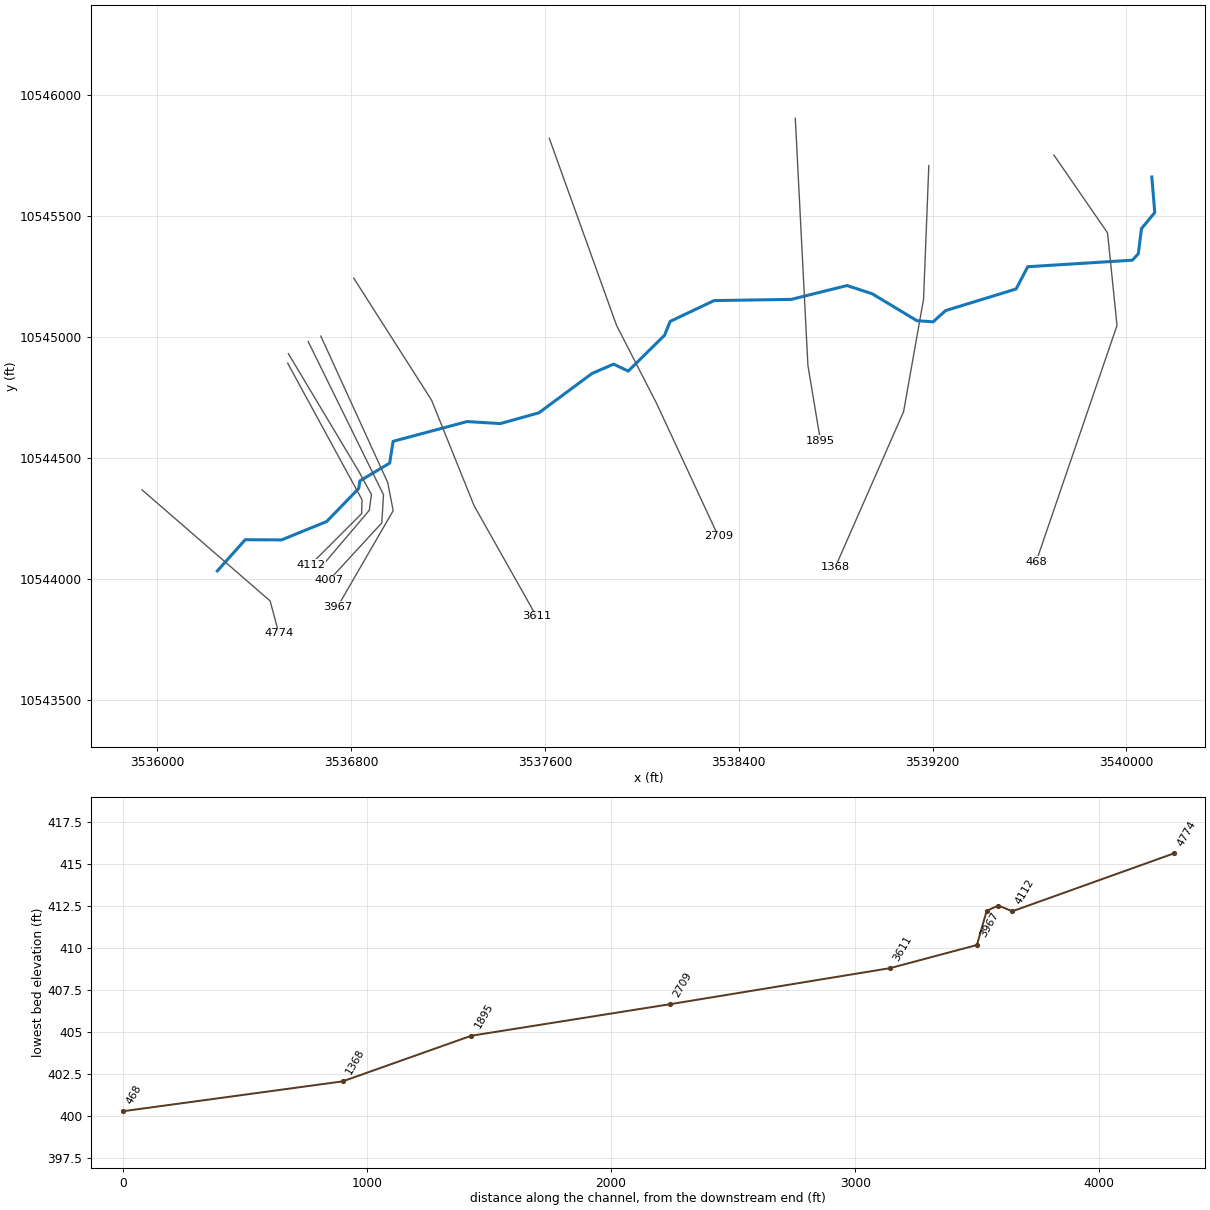
--- UNT0642 IN SAND CR.prj (project) ---

Proj Title=UNT0642 IN SAND CR Base Level Engineering
Current Plan=p01
Default Exp/Contr=0.3,0.1
English Units
Geom File=g01
Flow File=f01
Plan File=p01
BEGIN DESCRIPTION:
UNT0642 IN SAND CR
END DESCRIPTION:

--- UNT0642 IN SAND CR.p01 (plan) ---

Plan Title=Multiple Run
Short Identifier=Multiple
Geom File=g01
Flow File=f01
Subcritical Flow
K Sum by GR= 0
Std Step Tol= 0.01
Critical Tol= 0.01
Num of Std Step Trials= 20
Max Error Tol= 0.3
Flow Tol Ratio= 0.001
Split Flow NTrial= 30
Split Flow Tol= 0.02
Split Flow Ratio= 0.02
Log Output Level= 0
Friction Slope Method= 1
Unsteady Friction Slope Method= 2
Unsteady Bridges Friction Slope Method= 1
Parabolic Critical Depth
Global Vel Dist=  1 , 1 , 1
Global Log Level= 0
CheckData=True
Encroach Param= -1, 0, 0, 0
BEGIN DESCRIPTION:
Multiple Run
END DESCRIPTION:

--- UNT0642 IN SAND CR.f01 (steady flow) ---

Flow Title=Multiple
Number of Profiles=7
Profile Names=10-year,25-year,50-year,1pct_min,100-year,1pct_plu,500-year
River Rch & RM= UNT0642 IN SAND ,Reach-1,4774
     863    1174    1427    1267    1713    2316    2460
Boundary for River Rch & Prof#=UNT0642 IN SAND ,Reach-1,1
Up Type=0
Dn Type=3
Dn Slope=0.005
Boundary for River Rch & Prof#=UNT0642 IN SAND ,Reach-1,2
Up Type=0
Dn Type=3
Dn Slope=0.005
Boundary for River Rch & Prof#=UNT0642 IN SAND ,Reach-1,3
Up Type=0
Dn Type=3
Dn Slope=0.005
Boundary for River Rch & Prof#=UNT0642 IN SAND ,Reach-1,4
Up Type=0
Dn Type=3
Dn Slope=0.005
Boundary for River Rch & Prof#=UNT0642 IN SAND ,Reach-1,5
Up Type=0
Dn Type=3
Dn Slope=0.005
Boundary for River Rch & Prof#=UNT0642 IN SAND ,Reach-1,6
Up Type=0
Dn Type=3
Dn Slope=0.005
Boundary for River Rch & Prof#=UNT0642 IN SAND ,Reach-1,7
Up Type=0
Dn Type=3
Dn Slope=0.005

--- UNT0642 IN SAND CR.g01 (geometry) ---

Geom Title=Existing Conditions

River Reach=UNT0642 IN SAND ,Reach-1
Reach XY= 30
      3536247.36     10544033.44      3536362.21     10544162.19
      3536512.19     10544161.43      3536698.63     10544237.28
      3536830.92     10544373.74      3536835.61     10544404.99
      3536958.63     10544478.46      3536972.92     10544568.42
      3537278.01     10544649.90      3537415.70     10544641.64
      3537574.94     10544686.18      3537793.66     10544848.18
      3537882.94     10544887.04      3537943.64     10544858.35
      3538093.55     10545006.30      3538116.44     10545063.33
      3538298.14     10545149.37      3538616.57     10545154.27
      3538846.78     10545211.33      3538950.36     10545177.64
      3539135.26     10545066.35      3539202.11     10545061.64
      3539253.65     10545107.92      3539544.89     10545197.31
      3539592.84     10545289.06      3540025.00     10545316.08
      3540049.27     10545342.73      3540062.52     10545446.56
      3540117.30     10545512.65      3540105.07     10545659.33

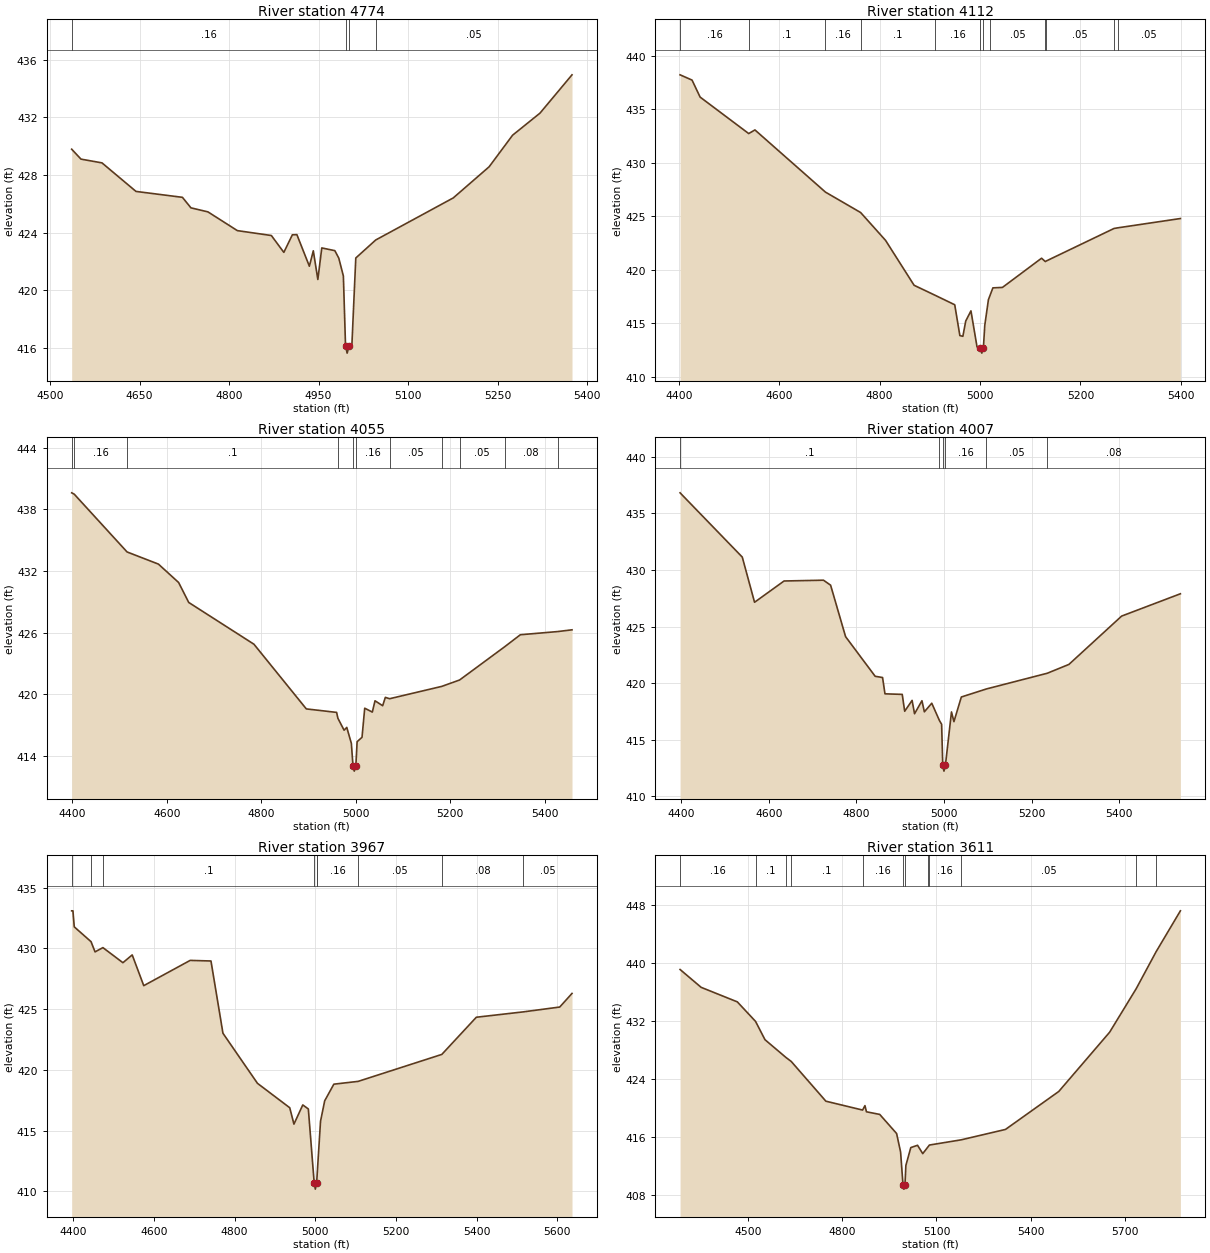
Type RM Length L Ch R = 1,4774,662,662,662
BEGIN DESCRIPTION:
UNT0642 IN SAND CR 10.0
END DESCRIPTION:
XS GIS Cut Line= 3
      3535936.46     10544367.90      3536465.15     10543909.53
      3536501.25     10543775.43
#Sta/Elev= 30
  4536.1  429.80  4551.7  429.11  4586.9  428.85  4643.9  426.87  4721.7  426.46
  4736.0  425.73  4764.5  425.45  4813.8  424.15  4870.8  423.81  4891.7  422.64
  4906.0  423.86  4913.6  423.87  4934.5  421.68  4941.1  422.75  4948.7  420.76
  4955.3  422.95  4977.2  422.76  4983.8  422.24  4991.5  421.00  4995.1  416.15
  4997.8  415.65  5001.1  416.15  5005.7  416.16  5012.3  422.25  5045.7  423.50
  5175.7  426.42  5235.8  428.58  5275.1  430.77  5321.0  432.30  5374.7  434.96
#Mann=4,-1,0
  4536.1    0.16       0  4995.1    0.07       0  5001.1    0.16       0
  5045.7    0.05       0
Bank Sta=4995.1,5001.1
Exp/Cntr=0.3,0.1

Type RM Length L Ch R = 1,4112,57,57,57
BEGIN DESCRIPTION:
UNT0642 IN SAND CR 10.2
END DESCRIPTION:
XS GIS Cut Line= 4
      3536537.62     10544890.97      3536844.67     10544327.21
      3536842.93     10544269.91      3536632.84     10544059.82
#Sta/Elev= 30
  4402.7  438.21  4426.5  437.72  4442.6  436.13  4539.4  432.72  4551.8  433.06
  4692.2  427.25  4762.3  425.34  4811.9  422.74  4868.8  418.54  4910.9  417.60
  4949.7  416.72  4959.9  413.84  4965.9  413.77  4971.6  415.20  4982.0  416.15
  4994.1  412.78  5000.8  412.70  5003.6  412.20  5006.8  412.70  5009.5  414.79
  5016.8  417.20  5020.3  417.63  5025.7  418.30  5044.7  418.34  5122.6  421.07
  5130.0  420.76  5132.4  420.82  5266.9  423.85  5274.4  423.91  5399.1  424.78
#Mann=12,-1,0
  4402.7    0.16       0  4539.4     0.1       0  4692.2    0.16       0
  4762.3     0.1       0  4910.9    0.16       0  5000.8    0.07       0
  5006.8    0.16       0  5020.3    0.05       0  5130.0    0.08       0
  5132.4    0.05       0  5266.9    0.16       0  5274.4    0.05       0
Bank Sta=5000.8,5006.8
Exp/Cntr=0.3,0.1

Type RM Length L Ch R = 1,4055,48,48,48
BEGIN DESCRIPTION:
UNT0642 IN SAND CR 10.1
END DESCRIPTION:
XS GIS Cut Line= 5
      3536540.45     10544930.44      3536831.23     10544444.36
      3536883.31     10544348.88      3536874.63     10544283.77
      3536668.45     10544040.70
#Sta/Elev= 30
  4398.4  439.60  4403.8  439.47  4515.7  433.85  4582.1  432.67  4624.9  430.88
  4646.3  428.94  4784.4  424.88  4895.3  418.59  4959.5  418.25  4962.2  417.68
  4975.3  416.52  4981.0  416.79  4990.7  415.24  4994.2  413.04  4996.9  412.54
  5000.2  413.04  5002.9  415.40  5013.3  415.83  5019.0  418.66  5035.1  418.28
  5040.8  419.38  5057.0  418.90  5062.7  419.71  5071.7  419.58  5182.2  420.78
  5219.9  421.40  5315.3  424.63  5348.6  425.80  5427.6  426.11  5458.0  426.28
#Mann=11,-1,0
  4398.4    0.05       0  4403.8    0.16       0  4515.7     0.1       0
  4962.2    0.16       0  4994.2    0.07       0  5000.2    0.16       0
  5071.7    0.05       0  5182.2    0.08       0  5219.9    0.05       0
  5315.3    0.08       0  5427.6    0.05       0
Bank Sta=4994.2,5000.2
Exp/Cntr=0.3,0.1

Type RM Length L Ch R = 1,4007,40,40,40
BEGIN DESCRIPTION:
UNT0642 IN SAND CR 10.3
END DESCRIPTION:
XS GIS Cut Line= 4
      3536622.46     10544979.95      3536933.21     10544348.04
      3536926.27     10544231.72      3536708.78     10543995.24
#Sta/Elev= 30
  4397.5  436.82  4539.5  431.14  4567.5  427.15  4634.9  429.03  4724.8  429.10
  4741.1  428.66  4775.3  424.11  4842.8  420.61  4859.7  420.50  4865.2  419.06
  4904.6  419.01  4910.2  417.52  4927.1  418.48  4932.7  417.30  4949.6  418.45
  4955.1  417.47  4972.0  418.23  4989.5  416.70  4994.5  416.37  4997.1  412.73
  4999.8  412.23  5003.1  412.73  5017.0  417.46  5022.6  416.60  5039.5  418.78
  5096.7  419.49  5235.8  420.88  5285.1  421.66  5405.4  425.93  5539.5  427.90
#Mann=6,-1,0
  4397.5     0.1       0  4989.5    0.16       0  4997.1    0.07       0
  5003.1    0.16       0  5096.7    0.05       0  5235.8    0.08       0
Bank Sta=4997.1,5003.1
Exp/Cntr=0.3,0.1

Type RM Length L Ch R = 1,3967,356,356,356
BEGIN DESCRIPTION:
UNT0642 IN SAND CR 10.4
END DESCRIPTION:
XS GIS Cut Line= 4
      3536674.51     10545002.59      3536950.57     10544398.39
      3536973.14     10544282.07      3536744.10     10543886.46
#Sta/Elev= 30
  4396.5  433.10  4399.6  433.10  4402.9  431.78  4444.5  430.56  4454.4  429.72
  4473.9  430.07  4523.5  428.83  4546.5  429.47  4575.1  426.94  4690.2  429.02
  4741.7  428.97  4771.4  423.02  4856.9  418.90  4936.9  416.89  4947.3  415.54
  4969.2  417.12  4983.0  416.79  4997.5  410.69  5000.3  410.19  5003.5  410.69
  5003.6  410.74  5013.2  415.78  5023.5  417.46  5046.2  418.83  5106.4  419.06
  5313.8  421.28  5399.3  424.34  5515.3  424.78  5606.0  425.18  5636.4  426.30
#Mann=9,-1,0
  4396.5     0.1       0  4444.5    0.16       0  4473.9     0.1       0
  4997.5    0.07       0  5003.5     0.1       0  5003.6    0.16       0
  5106.4    0.05       0  5313.8    0.08       0  5515.3    0.05       0
Bank Sta=4997.5,5003.5
Exp/Cntr=0.3,0.1

Type RM Length L Ch R = 1,3611,902,902,902
BEGIN DESCRIPTION:
UNT0642 IN SAND CR 8.0
END DESCRIPTION:
XS GIS Cut Line= 4
      3536810.31     10545242.06      3537131.50     10544738.57
      3537307.37     10544302.27      3537564.94     10543845.52
#Sta/Elev= 30
  4284.2  439.06  4351.3  436.60  4466.4  434.60  4524.4  431.91  4554.4  429.39
  4620.4  426.97  4638.0  426.39  4748.2  420.92  4865.0  419.70  4872.5  420.31
  4877.3  419.46  4919.5  419.10  4973.2  416.47  4985.9  413.92  4993.7  409.31
  4996.5  408.81  4999.7  409.31  5002.7  412.07  5018.3  414.53  5039.8  414.85
  5056.4  413.70  5074.5  414.71  5077.5  414.88  5178.7  415.60  5319.6  417.03
  5489.2  422.26  5651.0  430.42  5735.5  436.41  5798.8  441.50  5876.2  447.14
#Mann=12,-1,0
  4284.2    0.16       0  4524.4     0.1       0  4620.4    0.05       0
  4638.0     0.1       0  4865.0    0.16       0  4993.7    0.07       0
  4999.7    0.16       0  5074.5     0.1       0  5077.5    0.16       0
  5178.7    0.05       0  5735.5     0.1       0  5798.8    0.16       0
Bank Sta=4993.7,4999.7
Exp/Cntr=0.3,0.1

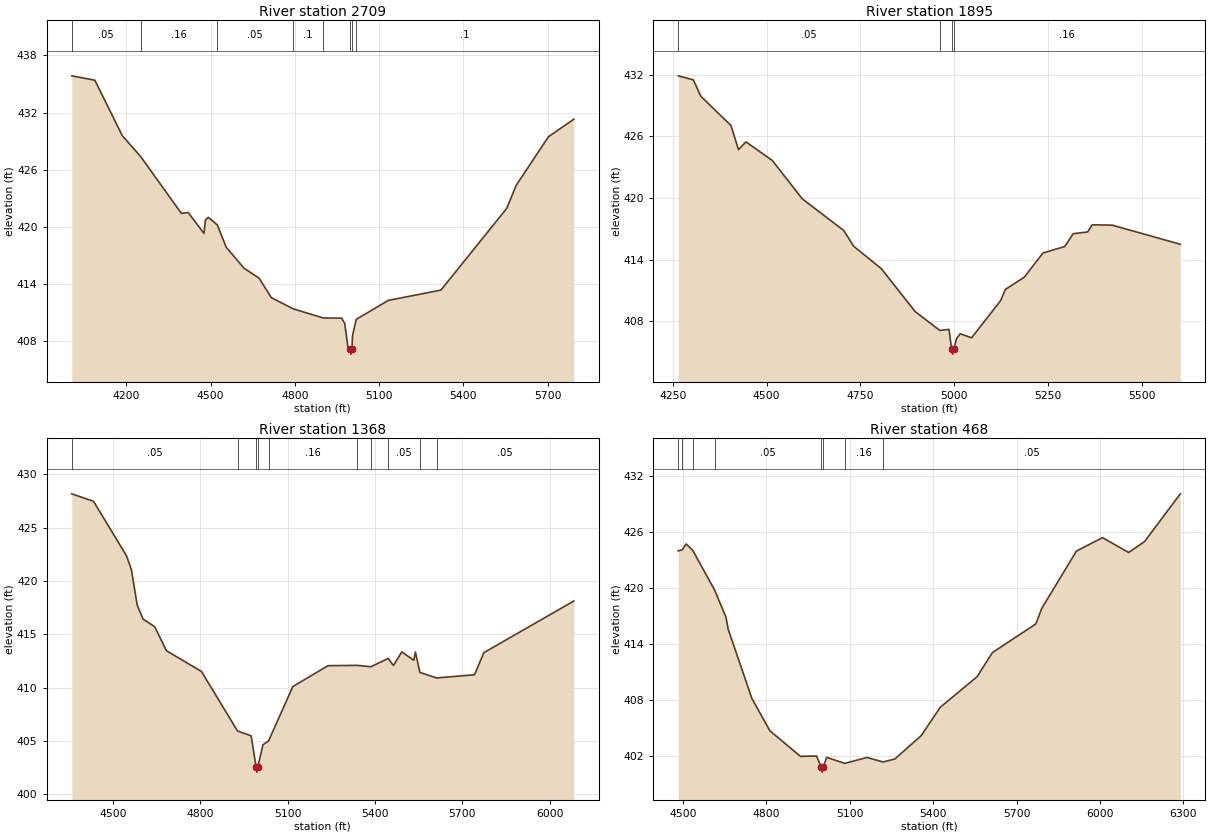
Type RM Length L Ch R = 1,2709,814,814,814
BEGIN DESCRIPTION:
UNT0642 IN SAND CR 6.0
END DESCRIPTION:
XS GIS Cut Line= 4
      3537617.62     10545819.28      3537895.39     10545046.73
      3538060.32     10544725.55      3538315.85     10544175.52
#Sta/Elev= 30
  4005.3  435.86  4087.5  435.40  4184.9  429.60  4250.9  427.38  4396.0  421.42
  4420.0  421.52  4476.2  419.33  4481.5  420.75  4491.6  421.01  4523.8  420.22
  4555.4  417.88  4619.1  415.67  4672.3  414.64  4716.6  412.58  4794.3  411.41
  4900.7  410.46  4966.9  410.43  4977.9  409.86  4989.4  407.31  4997.1  407.16
  4999.8  406.66  5003.1  407.16  5005.7  408.64  5018.7  410.31  5133.2  412.30
  5320.3  413.38  5554.7  421.95  5588.6  424.38  5703.1  429.46  5793.8  431.31
#Mann=8,-1,0
  4005.3    0.05       0  4250.9    0.16       0  4523.8    0.05       0
  4794.3     0.1       0  4900.7    0.16       0  4997.1    0.07       0
  5003.1    0.16       0  5018.7     0.1       0
Bank Sta=4997.1,5003.1
Exp/Cntr=0.3,0.1

Type RM Length L Ch R = 1,1895,527,527,527
BEGIN DESCRIPTION:
UNT0642 IN SAND CR 4.0
END DESCRIPTION:
XS GIS Cut Line= 3
      3538633.24     10545901.81      3538685.32     10544881.80
      3538737.25     10544570.24
#Sta/Elev= 30
  4264.9  431.91  4305.1  431.52  4325.1  429.92  4405.3  427.07  4425.3  424.72
  4445.3  425.47  4515.4  423.66  4595.5  419.91  4705.6  416.84  4731.8  415.31
  4805.8  413.11  4895.9  408.93  4961.7  407.09  4986.0  407.19  4993.0  405.28
  4995.8  404.78  4999.0  405.28  5006.0  406.29  5016.0  406.77  5046.1  406.37
  5123.2  409.98  5136.2  411.09  5186.3  412.27  5236.3  414.64  5294.3  415.27
  5316.8  416.52  5355.1  416.69  5367.5  417.39  5421.0  417.35  5602.1  415.49
#Mann=4,-1,0
  4264.9    0.05       0  4961.7    0.16       0  4993.0    0.07       0
  4999.0    0.16       0
Bank Sta=4993,4999
Exp/Cntr=0.3,0.1

Type RM Length L Ch R = 1,1368,900,900,900
BEGIN DESCRIPTION:
UNT0642 IN SAND CR 3.0
END DESCRIPTION:
XS GIS Cut Line= 4
      3539184.45     10545706.42      3539162.75     10545155.24
      3539080.29     10544690.83      3538798.15     10544048.43
#Sta/Elev= 30
  4358.6  428.18  4433.4  427.48  4546.9  422.35  4563.5  421.06  4583.5  417.73
  4603.6  416.42  4643.6  415.71  4683.6  413.46  4804.1  411.51  4928.1  405.92
  4974.8  405.47  4991.9  402.56  4994.6  402.06  4997.9  402.56  5015.4  404.63
  5034.5  404.98  5118.1  410.09  5238.9  412.05  5340.1  412.08  5386.2  411.95
  5445.6  412.73  5463.7  412.07  5492.5  413.34  5533.7  412.56  5539.2  413.33
  5554.6  411.42  5611.8  410.90  5742.4  411.20  5774.2  413.27  6083.5  418.12
#Mann=10,-1,0
  4358.6    0.05       0  4928.1     0.1       0  4991.9    0.07       0
  4997.9     0.1       0  5034.5    0.16       0  5340.1    0.05       0
  5386.2    0.16       0  5445.6    0.05       0  5554.6    0.16       0
  5611.8    0.05       0
Bank Sta=4991.9,4997.9
Exp/Cntr=0.3,0.1

Type RM Length L Ch R = 1,468,0,0,0
BEGIN DESCRIPTION:
UNT0642 IN SAND CR 1.0
END DESCRIPTION:
XS GIS Cut Line= 4
      3539700.96     10545749.84      3539922.30     10545428.68
      3539961.36     10545046.73      3539627.15     10544070.13
#Sta/Elev= 30
  4482.6  424.01  4497.6  424.14  4510.9  424.75  4534.6  424.08  4613.6  419.80
  4654.3  416.90  4662.6  415.58  4747.6  408.18  4812.5  404.71  4922.4  401.97
  4980.2  402.01  4997.3  400.78  5000.1  400.28  5003.3  400.78  5016.8  401.86
  5081.8  401.22  5161.2  401.85  5219.6  401.37  5262.0  401.69  5357.1  404.21
  5425.0  407.23  5557.9  410.52  5612.8  413.10  5769.3  416.18  5790.0  417.82
  5915.1  423.99  6009.0  425.43  6102.9  423.84  6160.2  425.01  6288.8  430.13
#Mann=8,-1,0
  4482.6    0.05       0  4497.6     0.1       0  4534.6    0.16       0
  4613.6    0.05       0  4997.3    0.03       0  5003.3    0.05       0
  5081.8    0.16       0  5219.6    0.05       0
Bank Sta=4997.3,5003.3
Exp/Cntr=0.3,0.1

Chan Stop Cuts=-1