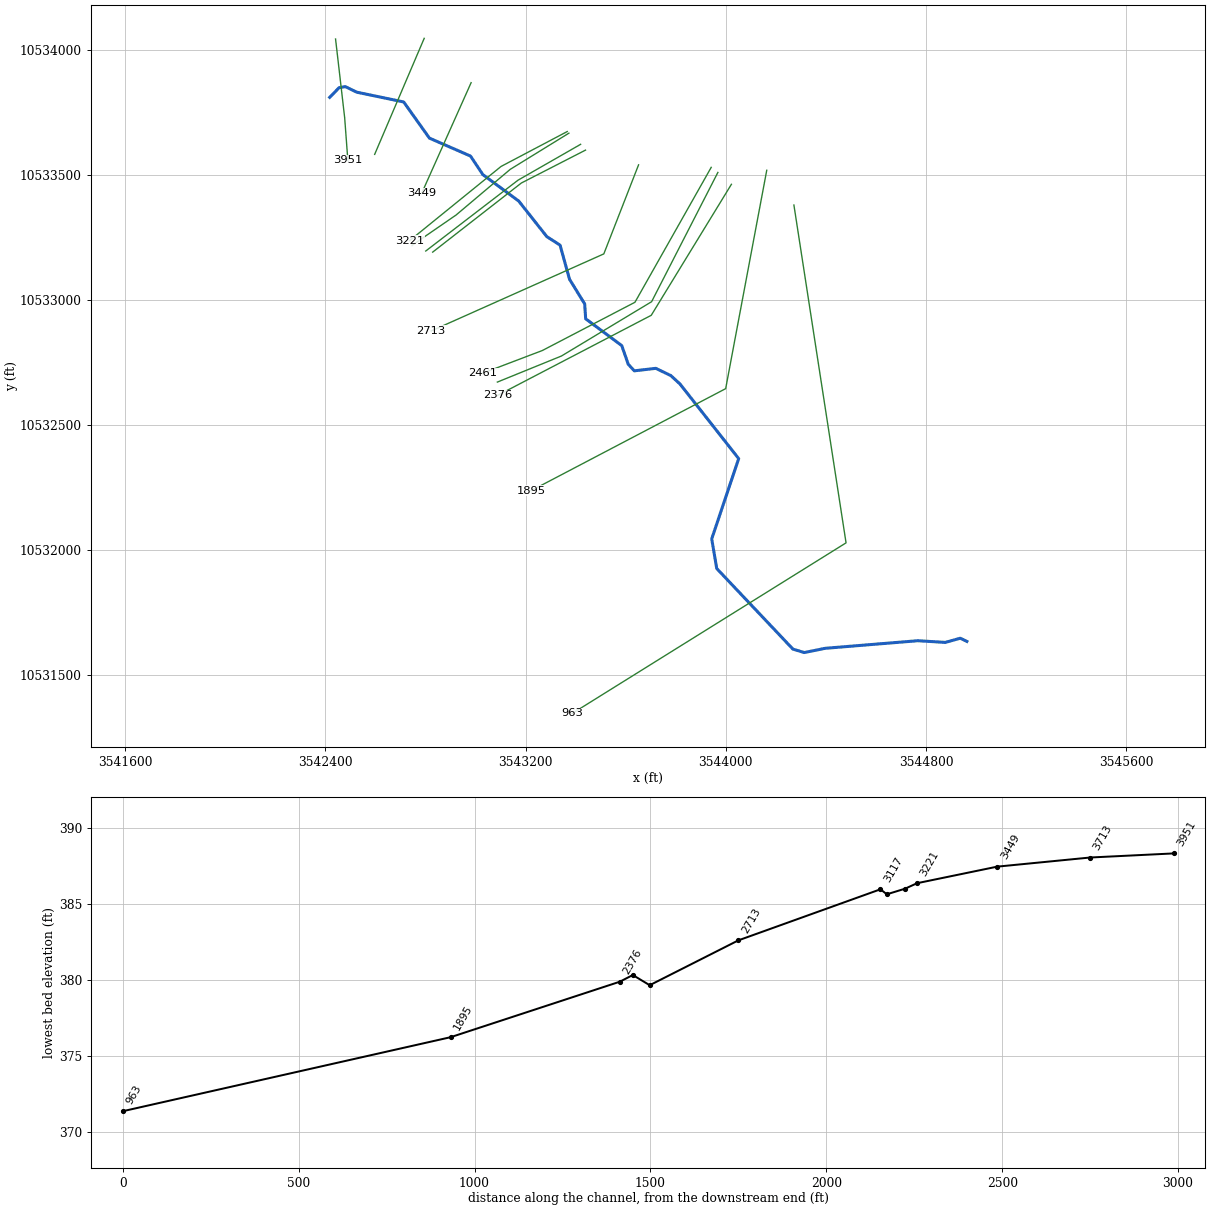
--- UNT0648 IN SAND CR.prj (project) ---

Proj Title=UNT0648 IN SAND CR Base Level Engineering
Current Plan=p01
Default Exp/Contr=0.3,0.1
English Units
Geom File=g01
Flow File=f01
Plan File=p01
Y Axis Title=Elevation
X Axis Title(PF)=Main Channel Distance
X Axis Title(XS)=Station
BEGIN DESCRIPTION:
UNT0648 IN SAND CR
END DESCRIPTION:
DSS Export Rating Curves= 0
DSS Export Rating Curve Sorted= 0
DSS Export Volume Flow Curves= 0
DXF OffsetX= 0
DXF OffsetY= 0
DXF ScaleX= 1
DXF ScaleY= 10

--- UNT0648 IN SAND CR.p01 (plan) ---

Plan Title=Multiple Run
Short Identifier=Multiple
Geom File=g01
Flow File=f01
Subcritical Flow
K Sum by GR= 0
Std Step Tol= 0.01
Critical Tol= 0.01
Num of Std Step Trials= 20
Max Error Tol= 0.3
Flow Tol Ratio= 0.001
Split Flow NTrial= 30
Split Flow Tol= 0.02
Split Flow Ratio= 0.02
Log Output Level= 0
Friction Slope Method= 1
Unsteady Friction Slope Method= 2
Unsteady Bridges Friction Slope Method= 1
Parabolic Critical Depth
Global Vel Dist=  1 , 1 , 1
Global Log Level= 0
CheckData=True
Encroach Param= -1, 0, 0, 0
BEGIN DESCRIPTION:
Multiple Run
END DESCRIPTION:

--- UNT0648 IN SAND CR.f01 (steady flow) ---

Flow Title=Multiple
Number of Profiles=7
Profile Names=10-year,25-year,50-year,1pct_min,100-year,1pct_plu,500-year
River Rch & RM= UNT0648 IN SAND ,Reach-1,3951
     785    1061    1284    1135    1535    2076    2186
Boundary for River Rch & Prof#=UNT0648 IN SAND ,Reach-1,1
Up Type=0
Dn Type=3
Dn Slope=0.005
Boundary for River Rch & Prof#=UNT0648 IN SAND ,Reach-1,2
Up Type=0
Dn Type=3
Dn Slope=0.005
Boundary for River Rch & Prof#=UNT0648 IN SAND ,Reach-1,3
Up Type=0
Dn Type=3
Dn Slope=0.005
Boundary for River Rch & Prof#=UNT0648 IN SAND ,Reach-1,4
Up Type=0
Dn Type=3
Dn Slope=0.005
Boundary for River Rch & Prof#=UNT0648 IN SAND ,Reach-1,5
Up Type=0
Dn Type=3
Dn Slope=0.005
Boundary for River Rch & Prof#=UNT0648 IN SAND ,Reach-1,6
Up Type=0
Dn Type=3
Dn Slope=0.005
Boundary for River Rch & Prof#=UNT0648 IN SAND ,Reach-1,7
Up Type=0
Dn Type=3
Dn Slope=0.005

--- UNT0648 IN SAND CR.g01 (geometry) ---

Geom Title=Existing Conditions
Program Version=4.10

River Reach=UNT0648 IN SAND ,Reach-1
Reach XY= 30
      3542417.54     10533809.78       3542455.3     10533848.84
      3542480.04     10533852.75      3542525.61     10533830.61
      3542713.11     10533791.55      3542815.98     10533647.02
      3542980.04     10533575.41      3543029.52     10533501.19
      3543172.75     10533395.72      3543284.98     10533253.56
      3543338.02     10533219.46       3543375.8     10533083.17
      3543436.42     10532984.51      3543440.28     10532925.23
      3543584.58     10532817.97      3543610.27     10532743.67
      3543634.58     10532717.28      3543720.57     10532727.19
      3543780.68     10532698.17      3543817.24     10532664.55
      3544051.73     10532366.48      3543943.93     10532045.79
      3543964.02     10531927.35       3544268.3     10531605.41
      3544313.65     10531591.66      3544397.61     10531608.57
      3544767.58      10531638.9       3544877.3     10531632.08
      3544937.18     10531648.91       3544963.5     10531636.08

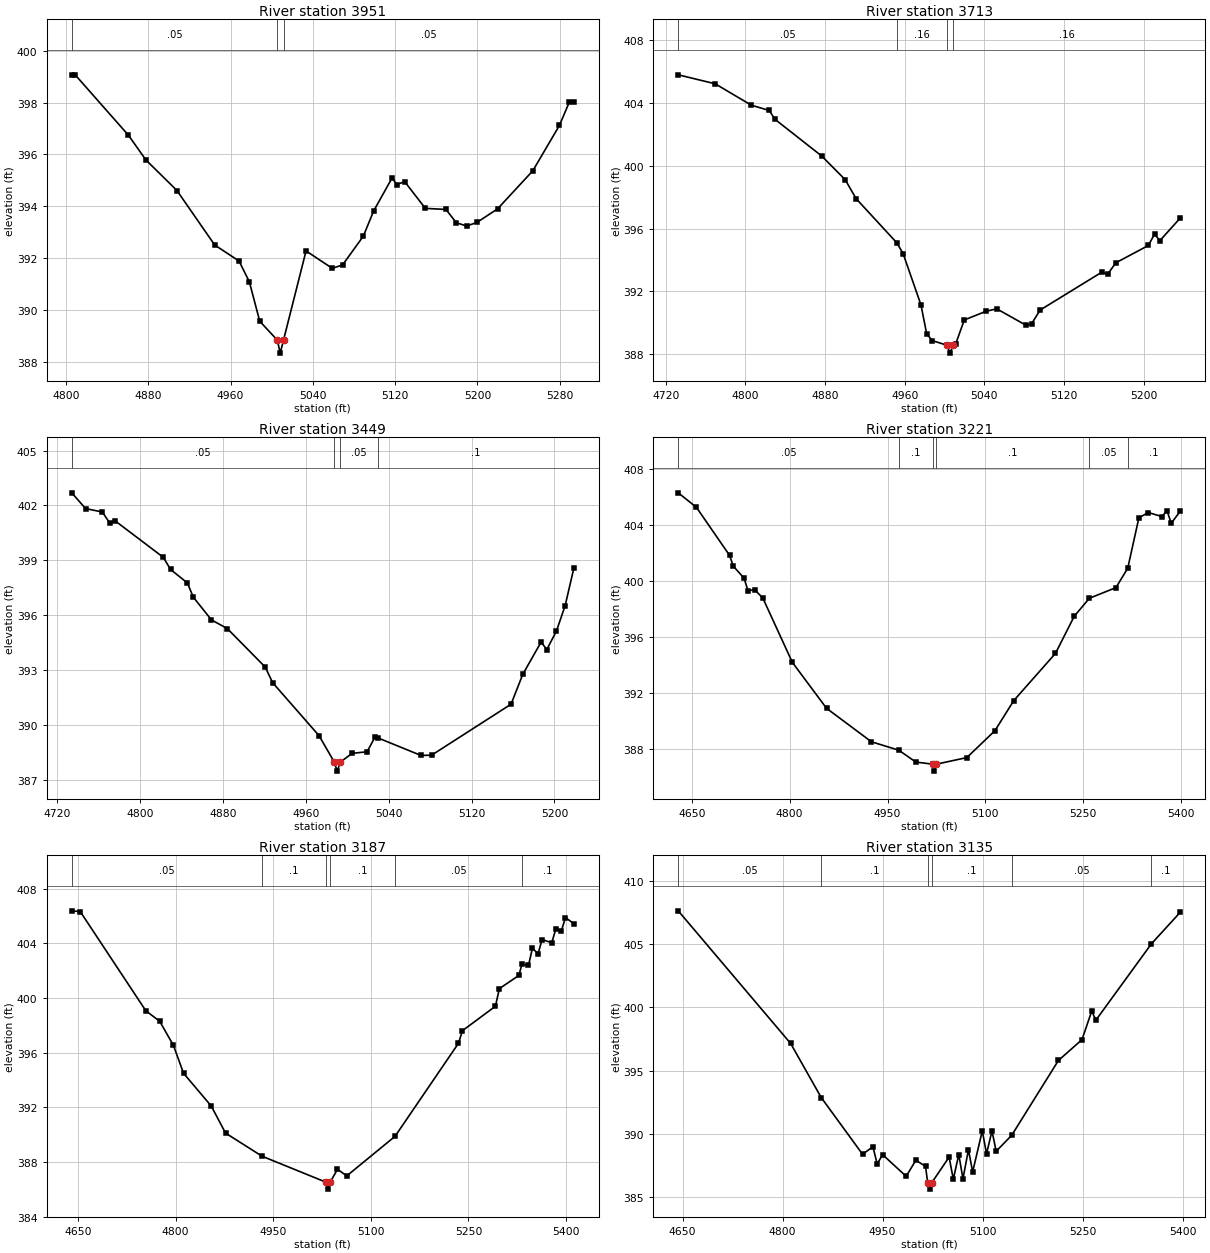
Type RM Length L Ch R = 1 ,3951    ,238,238,238
BEGIN DESCRIPTION:
UNT0648 IN SAND CR 3.5
END DESCRIPTION:
XS GIS Cut Line= 3
      3542440.97     10534043.12      3542477.43     10533728.01
      3542490.13     10533557.69
#Sta/Elev= 30
  4805.7  399.07    4809  399.07  4860.8  396.74  4877.7  395.79  4907.9  394.61
  4944.6  392.51  4968.3  391.89  4978.3  391.09  4988.4  389.57  5005.5  388.84
  5008.3  388.34  5011.5  388.84  5033.4  392.28  5058.9  391.61  5068.9  391.74
  5089.1  392.85  5099.1  393.82  5117.1   395.1  5121.5  394.84  5129.3  394.95
  5149.4  393.92  5169.4  393.88  5179.4  393.37  5189.5  393.24  5199.5  393.38
  5219.5   393.9  5253.8  395.37  5279.7  397.12  5289.2  398.01  5293.7  398.01
#Mann= 3 ,-1 , 0
  4805.7     .05       0  5005.5     .03       0  5011.5     .05       0
Bank Sta=5005.5,5011.5
XS Rating Curve= 0 ,0
Exp/Cntr=0.3,0.1

Type RM Length L Ch R = 1 ,3713    ,264,264,264
BEGIN DESCRIPTION:
UNT0648 IN SAND CR 3.6
END DESCRIPTION:
XS GIS Cut Line= 2
      3542795.16     10534045.76      3542597.21     10533582.15
#Sta/Elev= 30
  4732.6  405.78  4769.7  405.21  4805.9  403.85  4824.1  403.51  4829.5  402.96
  4876.7  400.61  4900.2  399.11  4911.2   397.9  4952.2  395.08  4958.4   394.4
  4976.3  391.14    4982  389.31  4987.5  388.87  5002.6  388.57  5005.4  388.07
  5008.6  388.57  5011.1  388.64  5019.8  390.18  5041.5  390.73  5052.4  390.89
  5081.9  389.84  5087.3  389.93  5095.9  390.81  5158.1  393.23  5163.6  393.08
    5172  393.82  5204.6  394.92  5210.8  395.64  5216.2  395.23  5236.7  396.67
#Mann= 4 ,-1 , 0
  4732.6     .05       0  4952.2     .16       0  5002.6     .07       0
  5008.6     .16       0
Bank Sta=5002.6,5008.6
XS Rating Curve= 0 ,0
Exp/Cntr=0.3,0.1

Type RM Length L Ch R = 1 ,3449    ,228,228,228
BEGIN DESCRIPTION:
UNT0648 IN SAND CR 3.7
END DESCRIPTION:
XS GIS Cut Line= 2
      3542982.63     10533868.61      3542784.89      10533426.3
#Sta/Elev= 30
  4734.2  402.69  4747.5  401.83  4763.7  401.64  4770.7  401.05  4776.2  401.15
  4822.6  399.16  4829.5   398.5  4845.8  397.76  4851.4  396.99    4869  395.74
  4884.2  395.27  4920.9  393.16    4928  392.31  4972.8  389.41  4987.5  387.97
  4990.3  387.47  4993.5  387.97  5004.7  388.44  5019.2  388.53  5026.6  389.31
  5029.5  389.29  5071.1  388.33  5081.4  388.34  5158.1  391.13  5169.4  392.76
  5187.1  394.53  5192.6  394.12  5201.9  395.13  5210.3  396.52  5218.7  398.57
#Mann= 4 ,-1 , 0
  4734.2     .05       0  4987.5     .03       0  4993.5     .05       0
  5029.5      .1       0
Bank Sta=4987.5,4993.5
XS Rating Curve= 0 ,0
Exp/Cntr=0.3,0.1

Type RM Length L Ch R = 1 ,3221    ,34,34,34
BEGIN DESCRIPTION:
UNT0648 IN SAND CR 3.3
END DESCRIPTION:
XS GIS Cut Line= 3
      3543366.78     10533673.34      3543102.43       10533534.
      3542736.86     10533237.38
#Sta/Elev= 30
  4629.2  406.31  4657.1  405.27  4707.9  401.83  4713.6  401.06    4730   400.2
  4736.2   399.3  4746.3  399.37  4758.8  398.78  4804.1  394.17  4856.5  390.88
  4925.4  388.48  4967.3  387.88  4993.3  387.03    5019  386.88  5021.8  386.38
    5025  386.88  5071.6  387.35  5114.7  389.28  5143.5  391.43  5207.4  394.81
  5236.2  397.47  5259.4  398.76  5300.1  399.52  5318.2  400.91  5335.3  404.52
  5349.7   404.9  5370.5  404.61  5378.4  405.03  5384.9  404.13  5398.8     405
#Mann= 6 ,-1 , 0
  4629.2     .05       0  4967.3      .1       0    5019     .07       0
    5025      .1       0  5259.4     .05       0  5318.2      .1       0
Bank Sta=5019,5025
XS Rating Curve= 0 ,0
Exp/Cntr=0.3,0.1

Type RM Length L Ch R = 1 ,3187    ,52,52,52
BEGIN DESCRIPTION:
UNT0648 IN SAND CR 3.2
END DESCRIPTION:
XS GIS Cut Line= 4
      3543373.25      10533666.8      3543138.89     10533522.28
      3542922.75     10533339.99        3542747.     10533218.92
#Sta/Elev= 30
  4640.5  406.38  4653.6  406.32  4754.3  399.07  4775.6   398.3  4796.8  396.53
  4812.2   394.5  4854.8   392.1  4876.8  390.12  4932.8  388.43  5031.5  386.52
  5034.3  386.02  5037.5  386.52  5048.8  387.47  5063.1  386.99  5137.2  389.88
  5234.7  396.69  5240.8  397.61  5291.5   399.4  5297.6  400.69  5327.4  401.65
  5332.3  402.47  5342.3  402.39  5348.3  403.63  5357.1  403.25  5363.2  404.28
  5378.1  404.04  5384.2  405.04    5393  404.93  5399.1  405.89    5412  405.44
#Mann= 6 ,-1 , 0
  4640.5     .05       0  4932.8      .1       0  5031.5     .07       0
  5037.5      .1       0  5137.2     .05       0  5332.3      .1       0
Bank Sta=5031.5,5037.5
XS Rating Curve= 0 ,0
Exp/Cntr=0.3,0.1

Type RM Length L Ch R = 1 ,3135    ,18,18,18
BEGIN DESCRIPTION:
UNT0648 IN SAND CR 3.1
END DESCRIPTION:
XS GIS Cut Line= 3
      3543420.17      10533622.3      3543170.14     10533479.05
      3542801.33     10533195.95
#Sta/Elev= 30
  4643.6  407.62  4812.2  397.15  4858.2  392.87  4920.1   388.4  4935.6     389
    4942  387.64  4950.2  388.37  4985.5  386.66    5000  387.93  5014.5  387.45
  5017.8  386.15  5020.6  385.65  5023.8  386.15  5049.9  388.18  5056.2  386.43
  5064.4  388.38  5070.7  386.47  5078.9  388.76  5085.2  387.01  5099.7  390.26
    5106  388.43  5114.2  390.25  5120.5  388.64  5143.8   389.9  5213.9  395.81
  5249.2  397.45  5263.8   399.7  5270.1  398.99  5353.4  405.02  5396.7  407.51
#Mann= 6 ,-1 , 0
  4643.6     .05       0  4858.2      .1       0  5017.8     .07       0
  5023.8      .1       0  5143.8     .05       0  5353.4      .1       0
Bank Sta=5017.8,5023.8
XS Rating Curve= 0 ,0
Exp/Cntr=0.3,0.1

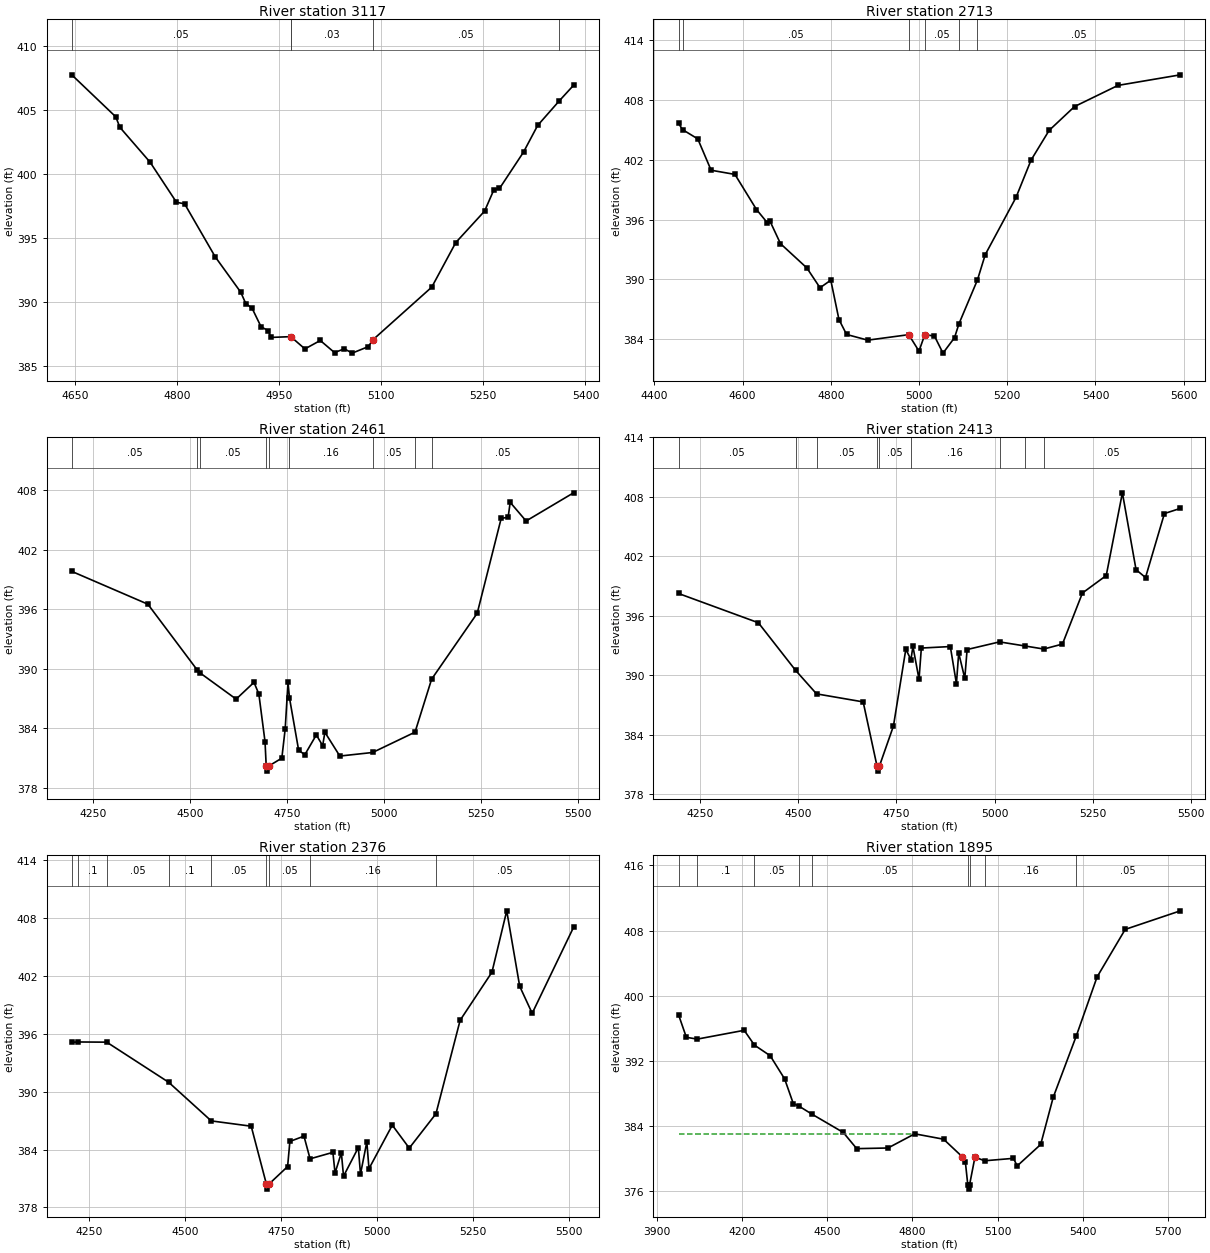
Type RM Length L Ch R = 1 ,3117    ,404,404,404
BEGIN DESCRIPTION:
UNT0648 IN SAND CR 3.4
END DESCRIPTION:
XS GIS Cut Line= 3
      3543439.68     10533599.11      3543183.16     10533467.59
        3542829.     10533191.55
#Sta/Elev= 30
  4645.2  407.77  4709.9  404.48  4715.9  403.66  4760.3  400.93  4799.1  397.79
    4811  397.67    4856  393.52  4893.5  390.75  4900.9  389.86  4910.1   389.5
  4923.4  388.04  4933.5  387.75  4938.1  387.21    4967  387.27  4987.8  386.31
  5010.4  386.97  5031.3  386.02  5045.7  386.32  5057.2  385.98    5081  386.49
  5087.4  387.01  5174.2  391.15  5209.5  394.64  5251.8   397.1  5265.6  398.79
  5273.7  398.87    5309  401.72  5329.8  403.81  5361.5  405.73  5382.5  406.95
#Mann= 5 ,-1 , 0
  4645.2     .05       0    4967      .1       0    4967     .03       0
  5087.4     .05       0  5361.5      .1       0
Bank Sta=4967,5087.4
XS Rating Curve= 0 ,0
Exp/Cntr=0.3,0.1

Type RM Length L Ch R = 1 ,2713    ,252,252,252
BEGIN DESCRIPTION:
UNT0648 IN SAND CR 3.0
END DESCRIPTION:
XS GIS Cut Line= 3
      3543651.71     10533540.37      3543512.82     10533184.45
      3542823.12     10532876.47
#Sta/Elev= 30
    4455  405.65    4464  405.02  4498.6  404.09  4528.8  400.95  4582.8  400.53
  4631.7  397.01  4656.2  395.69  4661.6  395.91  4686.1  393.59  4745.8  391.16
  4775.7  389.17  4800.1  389.93  4818.6  385.99  4835.9  384.49  4883.9  383.92
  4976.8  384.47    5000  382.82  5013.1  384.46    5035  384.34  5054.4  382.62
  5080.6  384.17  5090.6  385.56  5132.5  389.95  5150.2  392.49  5219.9  398.22
    5254  401.96    5295  404.94  5352.6  407.33  5451.1  409.45  5592.4  410.51
#Mann= 6 ,-1 , 0
    4455      .1       0    4464     .05       0  4976.8     .03       0
  5013.1     .05       0  5090.6      .1       0  5132.5     .05       0
Bank Sta=4976.8,5013.1
XS Rating Curve= 0 ,0
Exp/Cntr=0.3,0.1

Type RM Length L Ch R = 1 ,2461    ,48,48,48
BEGIN DESCRIPTION:
UNT0648 IN SAND CR 2.1
END DESCRIPTION:
XS GIS Cut Line= 4
      3543941.93     10533530.28      3543637.25     10532991.21
      3543267.45     10532798.51      3543027.91     10532707.37
#Sta/Elev= 30
  4195.5  399.81  4391.6   396.5    4519  389.85  4525.7  389.58  4618.9  386.93
  4664.9  388.62  4677.4  387.45  4693.3  382.65  4696.4  380.17  4699.1  379.67
  4702.4  380.17  4736.6  380.98  4745.3  383.94  4752.5  388.62  4756.2  387.08
  4779.9  381.78  4795.8  381.32  4825.4  383.32  4841.8  382.24  4847.5  383.59
    4886  381.19  4970.5  381.55  5079.7   383.6  5122.4  388.94  5239.9  395.59
  5301.6  405.15  5319.5  405.27  5324.8  406.77  5365.8  404.89    5488  407.73
#Mann= 9 ,-1 , 0
  4195.5     .05       0    4519      .1       0  4525.7     .05       0
  4696.4     .03       0  4702.4     .05       0  4756.2     .16       0
  4970.5     .05       0  5079.7     .16       0  5122.4     .05       0
Bank Sta=4696.4,4702.4
XS Rating Curve= 0 ,0
Exp/Cntr=0.3,0.1

Type RM Length L Ch R = 1 ,2413    ,37,37,37
BEGIN DESCRIPTION:
UNT0648 IN SAND CR 2.0
END DESCRIPTION:
XS GIS Cut Line= 4
      3543968.53     10533509.92      3543703.79     10532993.47
      3543343.55     10532776.46      3543087.43     10532672.28
#Sta/Elev= 30
  4195.3  398.25  4398.5   395.3  4493.1  390.51  4546.6  388.13  4665.3  387.32
  4700.6  380.84  4703.4  380.34  4706.6  380.84  4742.4  384.89  4773.9  392.63
  4786.9  391.58    4792  392.91  4807.5   389.6  4813.4  392.75  4887.2   392.9
  4902.7  389.16  4908.5  392.25    4924  389.69  4929.9   392.6  5012.4  393.37
  5078.5  392.95  5125.2  392.65  5172.6  393.15  5223.5   398.3  5284.1  400.06
  5325.2   408.4    5360  400.65  5384.1  399.86  5432.2  406.31  5472.7  406.83
#Mann= 9 ,-1 , 0
  4195.3     .05       0  4493.1      .1       0  4546.6     .05       0
  4700.6     .07       0  4706.6     .05       0  4786.9     .16       0
  5012.4     .05       0  5078.5     .16       0  5125.2     .05       0
Bank Sta=4700.6,4706.6
XS Rating Curve= 0 ,0
Exp/Cntr=0.3,0.1

Type RM Length L Ch R = 1 ,2376    ,481,481,481
BEGIN DESCRIPTION:
UNT0648 IN SAND CR 2.2
END DESCRIPTION:
XS GIS Cut Line= 3
      3544022.68      10533462.6      3543702.35     10532939.13
      3543087.81     10532618.84
#Sta/Elev= 30
  4205.7  395.12  4222.5  395.15  4296.8  395.13  4458.2  390.97    4569  386.97
    4673  386.42  4712.7   380.4  4715.4   379.9  4718.7   380.4  4767.8  382.24
  4773.7  384.84  4810.4  385.39  4826.3  383.04  4885.7  383.71  4891.3  381.57
  4907.8  383.66  4913.4  381.24    4952  384.21  4957.6  381.46  4974.1  384.79
  4979.7  382.02  5040.4  386.53  5084.6  384.15  5154.1  387.71  5217.1   397.4
  5299.9  402.38  5338.4  408.74  5372.2  400.92  5404.7  398.12  5512.4  407.03
#Mann= 9 ,-1 , 0
  4205.7     .05       0  4222.5      .1       0  4296.8     .05       0
  4458.2      .1       0    4569     .05       0  4712.7     .07       0
  4718.7     .05       0  4826.3     .16       0  5154.1     .05       0
Bank Sta=4712.7,4718.7
XS Rating Curve= 0 ,0
Exp/Cntr=0.3,0.1

Type RM Length L Ch R = 1 ,1895    ,932,932,932
BEGIN DESCRIPTION:
UNT0648 IN SAND CR 2.3
END DESCRIPTION:
XS GIS Cut Line= 3
      3544163.86     10533518.63      3543999.71     10532646.07
      3543222.01     10532238.26
#Sta/Elev= 30
  3976.6  397.66  4004.1  394.89  4042.6  394.67  4207.6  395.75  4243.8  393.93
  4299.1  392.63    4350  389.78  4380.5  386.75  4401.8  386.41  4444.9  385.48
  4556.3  383.21  4603.7  381.22  4713.8   381.3  4807.9  383.04  4909.4  382.38
  4975.6  380.21    4986   379.6  4994.7  376.75  4997.4  376.25  5000.7  376.75
  5019.8  380.18  5053.7  379.73  5155.3  380.03  5168.5   379.1  5251.1  381.73
  5295.2  387.52  5376.3  395.04  5449.6   402.3  5548.6  408.14  5742.6  410.42
#Mann= 9 ,-1 , 0
  3976.6     .05       0  4042.6      .1       0  4243.8     .05       0
  4401.8      .1       0  4444.9     .05       0  4994.7     .03       0
  5000.7     .05       0  5053.7     .16       0  5376.3     .05       0
#XS Ineff= 2 , 0
         4806.94  383.05
Permanent Ineff=
       F       F
Bank Sta=4975.6,5019.8
XS Rating Curve= 0 ,0
Exp/Cntr=0.3,0.1

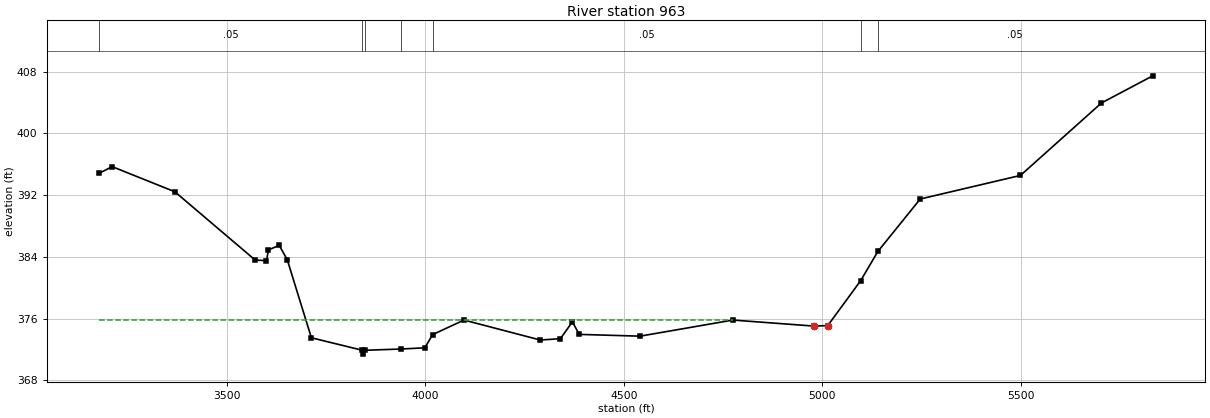
Type RM Length L Ch R = 1 ,963     ,0,0,0
BEGIN DESCRIPTION:
UNT0648 IN SAND CR 1.0
END DESCRIPTION:
XS GIS Cut Line= 3
      3544272.37     10533379.73       3544480.7     10532029.93
      3543387.06     10531348.58
#Sta/Elev= 30
  3178.6  394.85  3210.9   395.7  3368.9  392.44  3571.3  383.58  3599.8  383.51
  3604.8  384.91    3632  385.48  3652.2  383.61  3712.9   373.5  3841.5  371.88
  3844.2  371.38  3847.5  371.88  3937.6  372.04  3998.8   372.2  4018.3  373.91
  4097.4   375.8  4289.7  373.21  4340.3  373.38  4370.6  375.57  4387.8  373.94
    4541  373.71    4775   375.8  4978.7  375.02    5014  375.08  5097.1  380.92
  5140.3   384.7    5247   391.5  5499.6  394.56  5703.7  403.96  5832.9  407.48
#Mann= 7 ,-1 , 0
  3178.6     .05       0  3841.5     .03       0  3847.5     .05       0
  3937.6      .1       0  4018.3     .05       0  5097.1     .16       0
  5140.3     .05       0
#XS Ineff= 2 , 0
       0  4774.8  375.83               0
Permanent Ineff=
       T       F
Bank Sta=4978.7,5014
XS Rating Curve= 0 ,0
Exp/Cntr=0.3,0.1

Chan Stop Cuts=-1
Use User Specified Reach Order=0
Composite Channel Slope=5