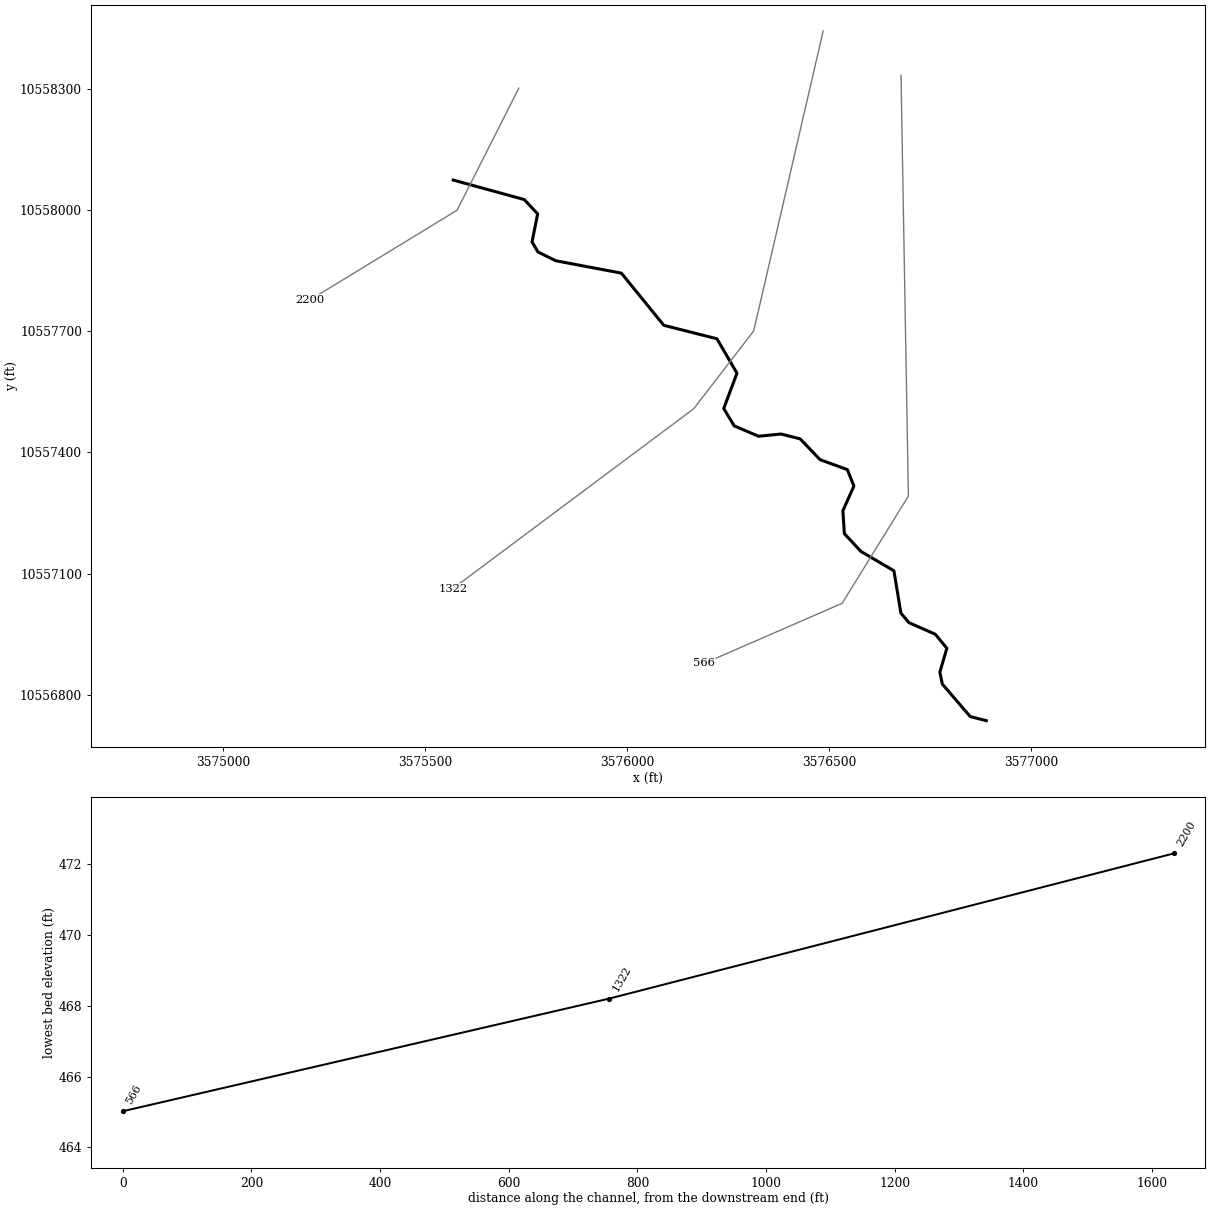
--- UNT0661 IN SAND CR.prj (project) ---

Proj Title=UNT0661 IN SAND CR Base Level Engineering
Current Plan=p01
Default Exp/Contr=0.3,0.1
English Units
Geom File=g01
Flow File=f01
Plan File=p01
Y Axis Title=Elevation
X Axis Title(PF)=Main Channel Distance
X Axis Title(XS)=Station
BEGIN DESCRIPTION:
UNT0661 IN SAND CR
END DESCRIPTION:
DSS Export Rating Curves= 0
DSS Export Rating Curve Sorted= 0
DSS Export Volume Flow Curves= 0
DXF OffsetX= 0
DXF OffsetY= 0
DXF ScaleX= 1
DXF ScaleY= 10

--- UNT0661 IN SAND CR.p01 (plan) ---

Plan Title=Multiple Run
Short Identifier=Multiple
Geom File=g01
Flow File=f01
Subcritical Flow
K Sum by GR= 0
Std Step Tol= 0.01
Critical Tol= 0.01
Num of Std Step Trials= 20
Max Error Tol= 0.3
Flow Tol Ratio= 0.001
Split Flow NTrial= 30
Split Flow Tol= 0.02
Split Flow Ratio= 0.02
Log Output Level= 0
Friction Slope Method= 1
Unsteady Friction Slope Method= 2
Unsteady Bridges Friction Slope Method= 1
Parabolic Critical Depth
Global Vel Dist=  1 , 1 , 1
Global Log Level= 0
CheckData=True
Encroach Param= -1, 0, 0, 0
BEGIN DESCRIPTION:
Multiple Run
END DESCRIPTION:

--- UNT0661 IN SAND CR.f01 (steady flow) ---

Flow Title=Multiple
Number of Profiles=7
Profile Names=10-year,25-year,50-year,1pct_min,100-year,1pct_plu,500-year
River Rch & RM= UNT0661 IN SAND ,Reach-1,2200
     593     782     931     811    1097    1483    1513
Boundary for River Rch & Prof#=UNT0661 IN SAND ,Reach-1,1
Up Type=0
Dn Type=3
Dn Slope=0.005
Boundary for River Rch & Prof#=UNT0661 IN SAND ,Reach-1,2
Up Type=0
Dn Type=3
Dn Slope=0.005
Boundary for River Rch & Prof#=UNT0661 IN SAND ,Reach-1,3
Up Type=0
Dn Type=3
Dn Slope=0.005
Boundary for River Rch & Prof#=UNT0661 IN SAND ,Reach-1,4
Up Type=0
Dn Type=3
Dn Slope=0.005
Boundary for River Rch & Prof#=UNT0661 IN SAND ,Reach-1,5
Up Type=0
Dn Type=3
Dn Slope=0.005
Boundary for River Rch & Prof#=UNT0661 IN SAND ,Reach-1,6
Up Type=0
Dn Type=3
Dn Slope=0.005
Boundary for River Rch & Prof#=UNT0661 IN SAND ,Reach-1,7
Up Type=0
Dn Type=3
Dn Slope=0.005

--- UNT0661 IN SAND CR.g01 (geometry) ---

Geom Title=Existing Conditions
Program Version=4.10

River Reach=UNT0661 IN SAND ,Reach-1
Reach XY= 30
      3575569.31     10558074.36      3575745.01     10558026.11
      3575778.27     10557990.57      3575764.42     10557921.41
      3575778.97      10557896.4      3575823.11     10557874.61
      3575985.53     10557843.94      3576090.45     10557714.88
      3576222.05     10557681.46      3576271.65     10557596.28
      3576238.89     10557508.77      3576264.93      10557465.8
      3576325.09     10557440.18      3576380.64     10557445.73
      3576428.04     10557433.74      3576477.42      10557382.2
      3576544.85     10557357.61      3576561.15     10557317.04
      3576533.82     10557255.71      3576537.46     10557199.15
       3576578.6     10557154.98      3576660.15     10557107.19
      3576677.52     10557002.16      3576697.48     10556978.72
      3576762.59     10556950.07      3576791.23     10556915.35
      3576773.87     10556856.32      3576779.95     10556826.81
      3576849.02     10556746.41      3576888.97     10556736.06

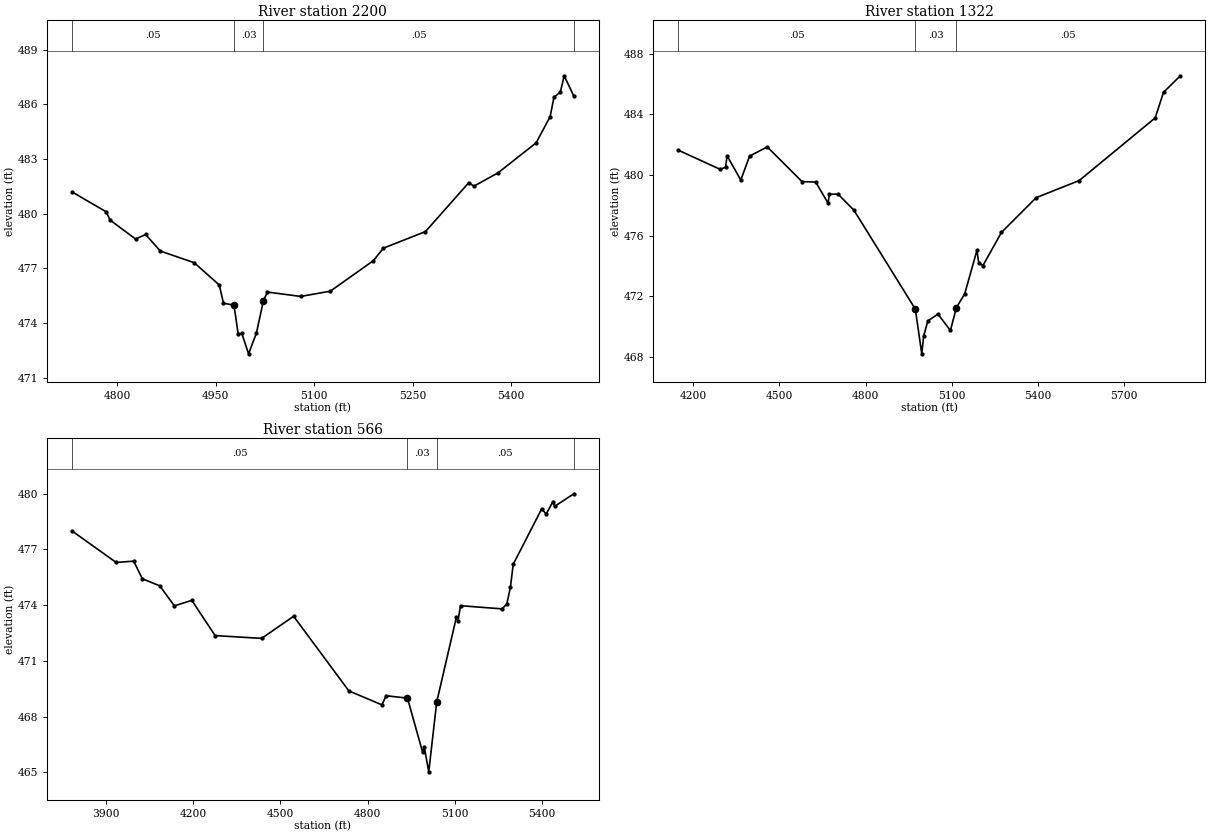
Type RM Length L Ch R = 1 ,2200    ,878,878,878
BEGIN DESCRIPTION:
UNT0661 IN SAND CR 4.0
END DESCRIPTION:
XS GIS Cut Line= 3
      3575731.56     10558301.72      3575578.78     10557999.63
      3575215.64     10557778.29
#Sta/Elev= 30
  4731.4  481.19  4783.7  480.09  4789.4  479.64  4828.3   478.6  4843.5  478.85
    4866  477.94  4917.5   477.3  4955.6  476.08    4962  475.08    4978  474.97
  4984.3   473.4  4989.9  473.42  5000.2   472.3  5012.2  473.45  5022.8  475.22
  5028.9  475.69  5079.6  475.45  5124.6  475.74    5190  477.41  5205.4   478.1
  5269.4  479.01  5335.4   481.7    5343   481.5  5379.7  482.23  5437.8  483.88
  5459.1  485.32    5465  486.39  5474.6  486.66  5480.5  487.56  5495.2  486.44
#Mann= 4 ,-1 , 0
  4731.4     .05       0    4978     .03       0  5022.8     .05       0
  5495.2     .08       0
Bank Sta=4978,5022.8
XS Rating Curve= 0 ,0
Exp/Cntr=0.3,0.1

Type RM Length L Ch R = 1 ,1322    ,756,756,756
BEGIN DESCRIPTION:
UNT0661 IN SAND CR 2.0
END DESCRIPTION:
XS GIS Cut Line= 4
      3576485.04      10558443.3      3576313.16     10557701.06
      3576164.72     10557508.35      3575568.36     10557063.04
#Sta/Elev= 30
  4147.8  481.63  4293.2  480.37  4312.3  480.51  4317.4  481.27  4365.2  479.66
  4395.8  481.24  4457.4  481.85  4578.7  479.56  4626.5  479.53  4669.2  478.14
  4674.3  478.72  4703.8  478.74  4759.7  477.67  4973.6  471.15    4996   468.2
  5002.6  469.37  5017.1  470.37  5052.4  470.82  5095.9  469.74  5116.7  471.25
  5145.7  472.16  5188.3  475.02  5194.5  474.21  5209.1  474.02  5273.8  476.21
  5394.7   478.5  5544.8  479.63  5809.5  483.76  5838.7  485.45  5897.2  486.54
#Mann= 3 , 0 , 0
  4147.8     .05       0  4973.6     .03       0  5116.7     .05       0
Bank Sta=4973.6,5116.7
XS Rating Curve= 0 ,0
Exp/Cntr=0.3,0.1

Type RM Length L Ch R = 1 ,566     ,0,0,0
BEGIN DESCRIPTION:
UNT0661 IN SAND CR 1.0
END DESCRIPTION:
XS GIS Cut Line= 4
      3576677.74     10558333.82      3576695.97     10557292.21
      3576531.91     10557026.58      3576190.78     10556878.15
#Sta/Elev= 30
  3783.3     478  3935.5   476.3  3995.5  476.37  4025.5  475.42  4085.5  475.04
  4135.5  473.96  4195.5  474.26  4275.6  472.36  4435.6  472.21  4545.6   473.4
  4735.6  469.38  4849.2  468.63  4863.9  469.12  4937.2  468.99  4989.3  466.07
  4995.2  466.34  5010.3  465.02  5037.7  468.78  5105.2  473.34    5111  473.17
  5119.6  473.97  5262.5   473.8  5278.8  474.06  5291.4  474.99  5300.7   476.2
  5398.8  479.19    5414  478.91  5437.4  479.58  5442.9  479.32  5509.3     480
#Mann= 4 ,-1 , 0
  3783.3     .05       0  4937.2     .03       0  5037.7     .05       0
  5509.3     .05       0
Bank Sta=4937.2,5037.7
XS Rating Curve= 0 ,0
Exp/Cntr=0.3,0.1

Chan Stop Cuts=-1
Use User Specified Reach Order=0
Composite Channel Slope=5