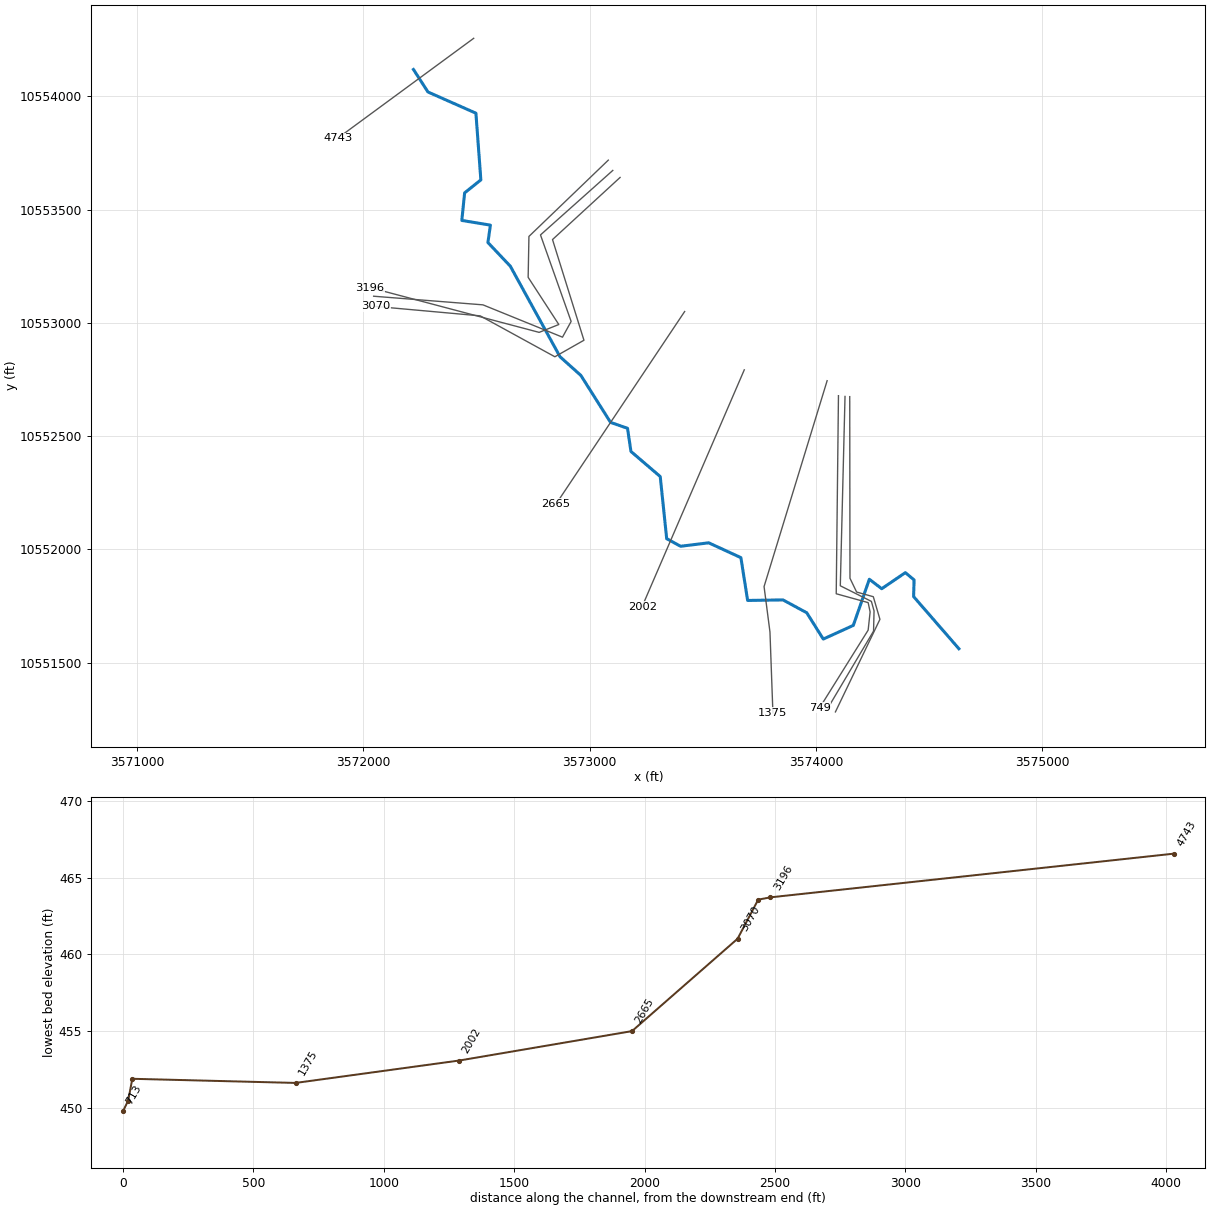
--- UNT0663 IN SAND CR.prj (project) ---

Proj Title=UNT0663 IN SAND CR Base Level Engineering
Current Plan=p01
Default Exp/Contr=0.3,0.1
English Units
Geom File=g01
Flow File=f01
Plan File=p01
Y Axis Title=Elevation
X Axis Title(PF)=Main Channel Distance
X Axis Title(XS)=Station
BEGIN DESCRIPTION:
UNT0663 IN SAND CR
END DESCRIPTION:
DSS Export Rating Curves= 0
DSS Export Rating Curve Sorted= 0
DSS Export Volume Flow Curves= 0
DXF OffsetX= 0
DXF OffsetY= 0
DXF ScaleX= 1
DXF ScaleY= 10

--- UNT0663 IN SAND CR.p01 (plan) ---

Plan Title=Multiple Run
Short Identifier=Multiple
Geom File=g01
Flow File=f01
Subcritical Flow
K Sum by GR= 0
Std Step Tol= 0.01
Critical Tol= 0.01
Num of Std Step Trials= 20
Max Error Tol= 0.3
Flow Tol Ratio= 0.001
Split Flow NTrial= 30
Split Flow Tol= 0.02
Split Flow Ratio= 0.02
Log Output Level= 0
Friction Slope Method= 1
Unsteady Friction Slope Method= 2
Unsteady Bridges Friction Slope Method= 1
Parabolic Critical Depth
Global Vel Dist=  1 , 1 , 1
Global Log Level= 0
CheckData=True
Encroach Param= -1, 0, 0, 0
BEGIN DESCRIPTION:
Multiple Run
END DESCRIPTION:

--- UNT0663 IN SAND CR.f01 (steady flow) ---

Flow Title=Multiple
Number of Profiles=7
Profile Names=10-year,25-year,50-year,1pct_min,100-year,1pct_plu,500-year
River Rch & RM= UNT0663 IN SAND ,Reach-1,4743
     820    1105    1336    1178    1594    2155    2260
Boundary for River Rch & Prof#=UNT0663 IN SAND ,Reach-1,1
Up Type=0
Dn Type=3
Dn Slope=0.005
Boundary for River Rch & Prof#=UNT0663 IN SAND ,Reach-1,2
Up Type=0
Dn Type=3
Dn Slope=0.005
Boundary for River Rch & Prof#=UNT0663 IN SAND ,Reach-1,3
Up Type=0
Dn Type=3
Dn Slope=0.005
Boundary for River Rch & Prof#=UNT0663 IN SAND ,Reach-1,4
Up Type=0
Dn Type=3
Dn Slope=0.005
Boundary for River Rch & Prof#=UNT0663 IN SAND ,Reach-1,5
Up Type=0
Dn Type=3
Dn Slope=0.005
Boundary for River Rch & Prof#=UNT0663 IN SAND ,Reach-1,6
Up Type=0
Dn Type=3
Dn Slope=0.005
Boundary for River Rch & Prof#=UNT0663 IN SAND ,Reach-1,7
Up Type=0
Dn Type=3
Dn Slope=0.005

--- UNT0663 IN SAND CR.g01 (geometry) ---

Geom Title=Existing Conditions
Program Version=4.10

River Reach=UNT0663 IN SAND ,Reach-1
Reach XY= 30
      3572222.01     10554118.79      3572285.82     10554019.75
      3572497.87     10553925.96      3572519.69     10553631.76
      3572447.97     10553574.28       3572435.5      10553452.5
      3572561.87      10553431.9      3572550.91     10553354.93
      3572649.84     10553250.59      3572869.51     10552850.69
      3572961.74     10552768.23      3573092.85     10552560.92
      3573167.69      10552534.9      3573182.94     10552432.59
       3573312.3     10552321.86       3573340.8     10552047.59
      3573401.96     10552014.09      3573526.61      10552029.3
       3573668.7     10551963.84      3573698.48     10551774.86
      3573854.54     10551777.26      3573959.74     10551720.49
      3574032.66     10551604.35      3574165.47     10551664.76
      3574236.31     10551868.41      3574290.99     10551826.67
      3574395.43     10551897.59      3574433.92     10551865.59
      3574431.86     10551791.86      3574632.11     10551561.64

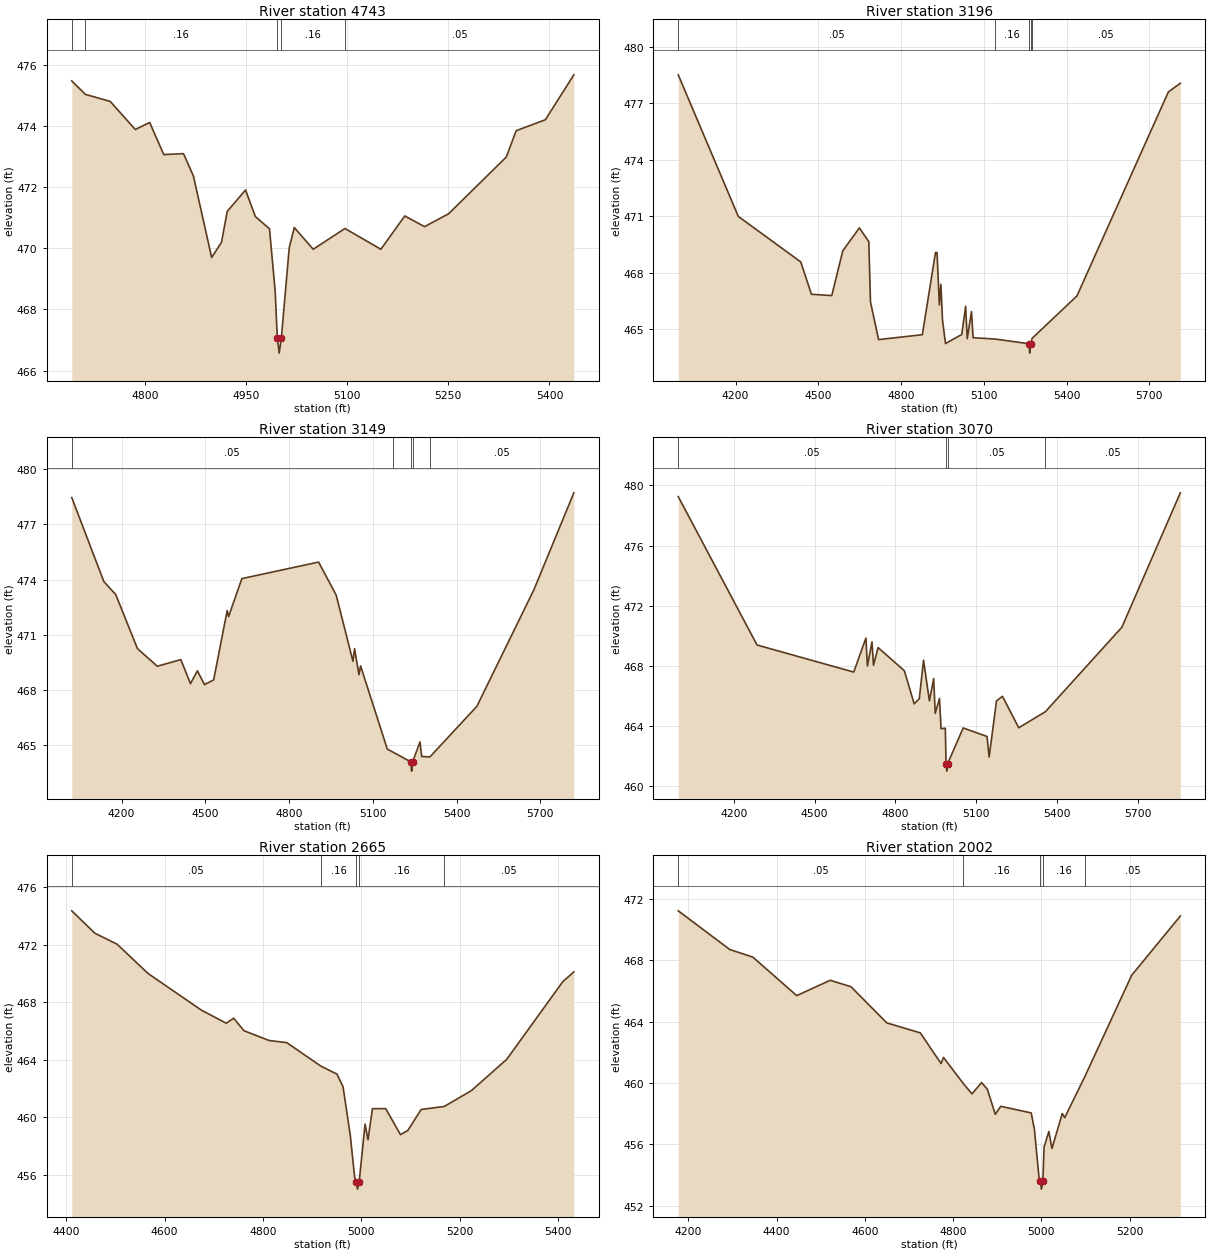
Type RM Length L Ch R = 1 ,4743    ,1547,1547,1547
BEGIN DESCRIPTION:
UNT0663 IN SAND CR 8.0
END DESCRIPTION:
XS GIS Cut Line= 2
      3572488.04     10554256.61      3571888.06     10553816.16
#Sta/Elev= 30
  4691.8  475.48    4712  475.04  4748.8  474.81    4786  473.89  4807.3  474.12
  4828.2  473.07  4857.5   473.1  4872.1  472.37  4899.2   469.7  4913.8   470.2
  4922.3  471.21  4949.4  471.91    4964  471.04  4984.9  470.64  4993.3  468.61
  4996.5  467.07  4999.3  466.57  5002.5  467.07  5014.2  470.02  5021.7  470.68
  5049.7  469.97  5096.8  470.65    5150  469.97  5185.5  471.06  5214.8  470.71
  5250.3  471.13    5336  472.99  5350.6  473.85  5393.9  474.21  5436.1  475.68
#Mann= 5 ,-1 , 0
  4691.8     .05       0    4712     .16       0  4996.5     .07       0
  5002.5     .16       0  5096.8     .05       0
Bank Sta=4996.5,5002.5
XS Rating Curve= 0 ,0
Exp/Cntr=0.3,0.1

Type RM Length L Ch R = 1 ,3196    ,47,47,47
BEGIN DESCRIPTION:
UNT0663 IN SAND CR 7.2
END DESCRIPTION:
XS GIS Cut Line= 6
      3573082.85     10553718.77      3572732.15     10553381.96
      3572728.67     10553201.41      3572864.09     10552993.08
      3572777.29     10552958.35      3572029.03     10553156.27
#Sta/Elev= 30
  3992.2  478.52    4210  470.99  4436.4  468.57  4475.1  466.85  4548.8  466.78
  4588.8  469.16  4648.8  470.38    4683  469.65  4689.2  466.44  4718.6  464.44
  4877.2   464.7  4924.8  469.07  4930.4  469.07    4939  466.28  4944.4  467.38
  4950.3  465.48  4961.1  464.23  5020.1  464.71  5034.1  466.21  5039.9  464.49
  5055.4  465.93  5061.2  464.54  5139.9  464.47  5263.8  464.22  5266.5  463.72
  5269.8  464.22  5275.4  464.51  5437.6  466.76  5769.1  477.61  5812.4  478.07
#Mann= 5 ,-1 , 0
  3992.2     .05       0  5139.9     .16       0  5263.8     .03       0
  5269.8     .16       0  5275.4     .05       0
Bank Sta=5263.8,5269.8
XS Rating Curve= 0 ,0
Exp/Cntr=0.3,0.1

Type RM Length L Ch R = 1 ,3149    ,79,79,79
BEGIN DESCRIPTION:
UNT0663 IN SAND CR 7.0
END DESCRIPTION:
XS GIS Cut Line= 6
      3573102.66     10553673.31      3572783.19     10553388.56
       3572918.6     10553006.62      3572880.41     10552937.17
      3572529.02     10553079.88      3572045.92     10553117.98
#Sta/Elev= 30
  4021.4  478.46  4136.3  473.89    4179  473.18  4256.7  470.24  4327.8  469.28
  4412.2  469.64  4446.7  468.33  4471.4  469.03    4497  468.28  4529.9  468.54
  4578.2  472.31  4583.2  471.98  4630.8  474.05  4905.7  474.95  4968.6  473.16
  5028.8  469.55  5034.6  470.24  5050.3  468.82  5056.1   469.3  5151.9  464.77
  5171.6  464.61  5236.3  464.07    5239  463.57  5242.3  464.07  5269.1  465.16
  5274.9  464.37  5304.3  464.34  5472.9   467.1  5677.3  473.45  5820.2  478.72
#Mann= 5 ,-1 , 0
  4021.4     .05       0  5171.6     .16       0  5236.3     .03       0
  5242.3     .16       0  5304.3     .05       0
Bank Sta=5236.3,5242.3
XS Rating Curve= 0 ,0
Exp/Cntr=0.3,0.1

Type RM Length L Ch R = 1 ,3070    ,405,405,405
BEGIN DESCRIPTION:
UNT0663 IN SAND CR 7.1
END DESCRIPTION:
XS GIS Cut Line= 6
       3573134.9     10553642.36      3572836.31     10553368.08
       3572975.2     10552923.63      3572846.73     10552850.71
      3572516.87     10553031.27       3572056.1     10553072.84
#Sta/Elev= 30
  3994.1  479.26  4286.6   469.4  4645.6   467.6  4690.8  469.86  4696.3     468
  4713.4  469.61  4718.9  468.05    4736  469.23  4833.5  467.69    4870  465.49
    4889  465.83  4904.8  468.39  4926.5  465.69  4942.4  467.17  4948.1  464.86
    4964  465.85  4969.7  463.84  4985.6  463.87  4988.4  461.52  4991.1  461.02
  4994.4  461.52    5052  463.89  5140.6  463.32  5148.2  461.96  5175.8  465.69
  5197.8  465.99  5258.2   463.9  5357.3  464.97  5641.1  470.58    5858  479.51
#Mann= 4 ,-1 , 0
  3994.1     .05       0  4988.4     .07       0  4994.4     .05       0
  5357.3     .05       0
Bank Sta=4988.4,4994.4
XS Rating Curve= 0 ,0
Exp/Cntr=0.3,0.1

Type RM Length L Ch R = 1 ,2665    ,663,663,663
BEGIN DESCRIPTION:
UNT0663 IN SAND CR 5.0
END DESCRIPTION:
XS GIS Cut Line= 2
      3573420.17     10553050.37      3572852.45      10552201.4
#Sta/Elev= 30
  4411.2  474.35  4458.3  472.79  4503.3  472.03  4566.4  469.99  4674.5  467.45
  4725.5  466.53  4740.5  466.88  4761.5  466.01  4812.6  465.33  4848.6  465.18
  4917.8  463.55  4950.7  462.99    4963  462.11  4977.7  458.75  4986.7   455.8
  4989.8  455.49  4992.5  454.99  4995.8  455.49  5007.8  459.51  5013.8  458.42
  5022.8  460.59  5049.8  460.59  5079.8  458.78  5094.8  459.07  5121.9  460.53
  5168.9  460.74    5224  461.84    5296  464.02  5410.2  469.43  5432.5   470.1
#Mann= 5 ,-1 , 0
  4411.2     .05       0  4917.8     .16       0  4989.8     .07       0
  4995.8     .16       0  5168.9     .05       0
Bank Sta=4989.8,4995.8
XS Rating Curve= 0 ,0
Exp/Cntr=0.3,0.1

Type RM Length L Ch R = 1 ,2002    ,627,627,627
BEGIN DESCRIPTION:
UNT0663 IN SAND CR 3.0
END DESCRIPTION:
XS GIS Cut Line= 2
      3573683.69     10552793.04      3573232.33     10551747.95
#Sta/Elev= 30
  4176.8  471.22  4293.5   468.7    4346   468.2  4445.4  465.69  4521.4  466.69
  4568.4  466.27  4649.8  463.91  4725.7  463.26  4772.7  461.26  4778.2  461.66
  4823.1  459.96  4842.8  459.28  4864.6  460.02  4877.6  459.59  4895.7  457.95
  4908.1  458.47  4977.1  458.04  4984.4  456.97  4995.2  453.72  4997.6  453.57
  5000.4  453.07  5003.6  453.57  5006.2   455.8  5017.1  456.83  5024.1  455.72
  5047.6     458  5053.1  457.73  5098.9  460.42    5205  467.02  5315.2  470.88
#Mann= 5 ,-1 , 0
  4176.8     .05       0  4823.1     .16       0  4997.6     .07       0
  5003.6     .16       0  5098.9     .05       0
Bank Sta=4997.6,5003.6
XS Rating Curve= 0 ,0
Exp/Cntr=0.3,0.1

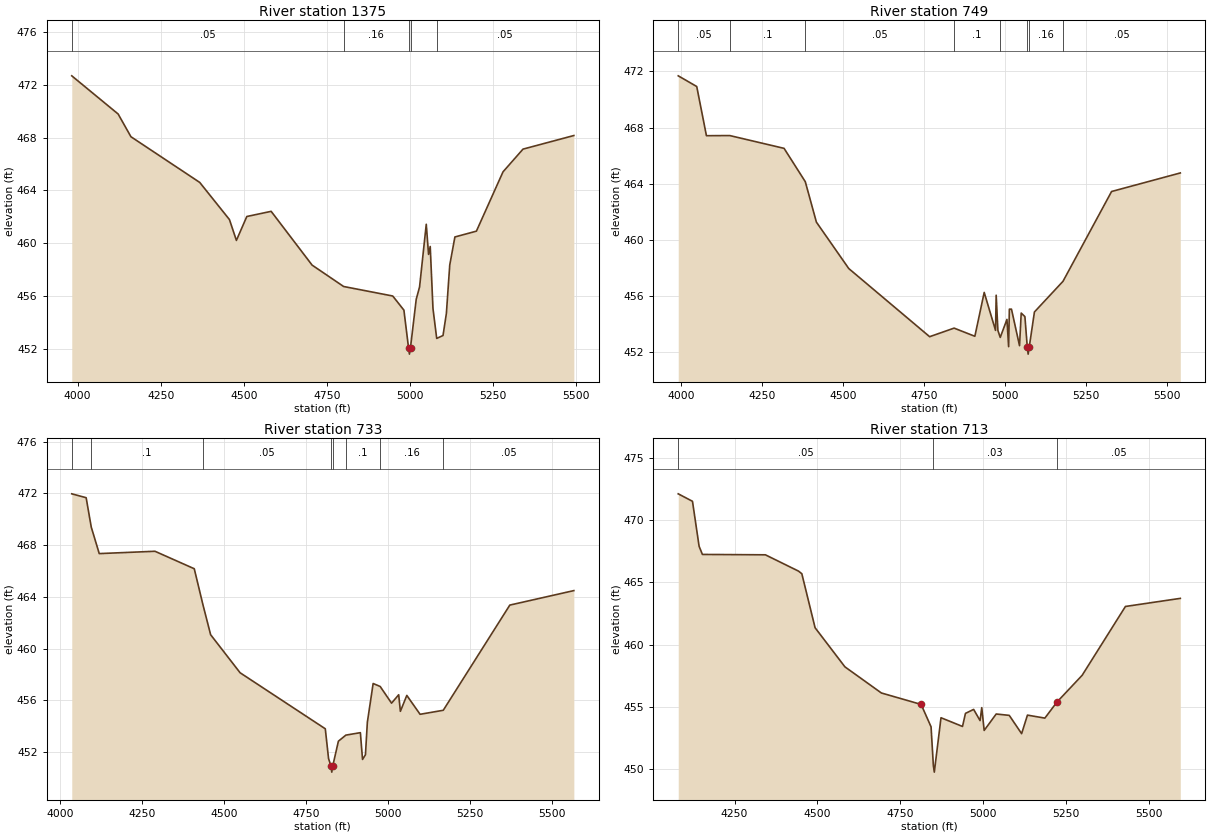
Type RM Length L Ch R = 1 ,1375    ,626,626,626
BEGIN DESCRIPTION:
UNT0663 IN SAND CR 2.0
END DESCRIPTION:
XS GIS Cut Line= 4
      3574049.77     10552744.95      3573771.12     10551836.09
      3573797.16     10551635.57      3573810.18     10551278.83
#Sta/Elev= 30
  3982.7  472.68  4122.1  469.79  4160.6  468.07  4367.5  464.61  4456.8   461.8
  4477.8  460.22  4509.1  462.03  4582.3  462.42  4705.4  458.35  4800.2  456.73
  4947.9  456.01  4981.5  454.94  4995.3  452.11  4998.1  451.61  5001.3  452.11
  5018.5  455.76  5028.6   456.7  5048.7  461.44  5055.6  459.16  5060.6  459.76
  5068.9  455.06  5080.1   452.8  5099.1  453.02  5109.2  454.69  5119.3  458.35
  5134.8  460.48  5199.5  460.92  5279.5  465.41  5339.6  467.13  5492.5  468.16
#Mann= 5 ,-1 , 0
  3982.7     .05       0  4800.2     .16       0  4995.3     .07       0
  5001.3     .16       0  5080.1     .05       0
Bank Sta=4995.3,5001.3
XS Rating Curve= 0 ,0
Exp/Cntr=0.3,0.1

Type RM Length L Ch R = 1 ,749     ,16,16,16
BEGIN DESCRIPTION:
UNT0663 IN SAND CR 1.1
END DESCRIPTION:
XS GIS Cut Line= 6
      3574099.81     10552678.84      3574089.97      10551804.4
      3574231.03     10551765.34      3574239.71     10551724.11
      3574231.03     10551643.81      3574017.26       10551302.
#Sta/Elev= 30
  3990.1  471.68  4047.3  470.92  4077.3  467.42  4149.4  467.43  4317.3  466.52
  4382.9  464.15  4417.3  461.27  4517.3  457.97  4767.4  453.12    4843  453.73
  4907.2  453.15  4936.1  456.27  4971.1  453.57  4973.1  456.07  4978.4  453.57
  4985.7  453.07  5006.4  454.35  5011.6  452.41  5013.9  455.08  5020.4  455.08
  5045.3  452.48  5050.5   454.8  5061.9  454.55  5069.3  452.38    5072  451.88
  5075.3  452.38  5091.4  454.88  5179.7  457.06  5329.9  463.45  5542.4  464.77
#Mann= 8 ,-1 , 0
  3990.1     .05       0  4149.4      .1       0  4382.9     .05       0
    4843      .1       0  4985.7     .16       0  5069.3     .07       0
  5075.3     .16       0  5179.7     .05       0
Bank Sta=5069.3,5075.3
XS Rating Curve= 0 ,0
Exp/Cntr=0.3,0.1

Type RM Length L Ch R = 1 ,733     ,20,20,20
BEGIN DESCRIPTION:
UNT0663 IN SAND CR 1.0
END DESCRIPTION:
XS GIS Cut Line= 6
      3574128.81     10552675.53      3574107.98     10551839.63
      3574245.35     10551770.62      3574257.07     10551728.95
       3574254.9     10551639.54      3574046.83      10551289.3
#Sta/Elev= 30
  4034.8  471.96  4078.7  471.66  4094.3  469.39  4118.7  467.34  4288.8  467.52
  4408.8  466.17    4435  463.42  4458.8  461.07  4548.8  458.13  4808.9   453.8
  4818.9  451.49  4825.9  450.95  4828.7  450.45  4831.9  450.95  4848.9  452.84
  4871.7  453.31    4916   453.5  4922.6  451.43  4931.5  451.79  4937.3   454.3
    4955   457.3  4976.5  457.07  5011.2  455.78    5033  456.43  5038.2  455.15
  5057.8  456.38  5098.3  454.92  5169.1  455.23  5372.3  463.36  5567.8  464.48
#Mann= 8 ,-1 , 0
  4034.8     .05       0  4094.3      .1       0    4435     .05       0
  4825.9     .07       0  4831.9     .05       0  4871.7      .1       0
  4976.5     .16       0  5169.1     .05       0
Bank Sta=4825.9,4831.9
XS Rating Curve= 0 ,0
Exp/Cntr=0.3,0.1

Type RM Length L Ch R = 1 ,713     ,0,0,0
BEGIN DESCRIPTION:
UNT0663 IN SAND CR 1.2
END DESCRIPTION:
XS GIS Cut Line= 6
      3574149.65     10552674.66      3574150.73     10551872.76
      3574180.03       10551812.      3574253.81     10551791.38
      3574283.11     10551691.55      3574086.39     10551282.77
#Sta/Elev= 30
    4080  472.12    4123  471.52    4143   467.9    4153  467.25    4343  467.22
    4443  465.91    4453   465.7    4493  461.36    4583  458.22    4693  456.12
    4813   455.2    4843   453.4    4850  450.26  4852.8  449.76    4873  454.13
  4937.9  453.43  4946.8  454.48  4971.5   454.8  4990.9   453.9    4996  454.94
  5003.3  453.11  5039.6  454.43    5079  454.32  5116.3  452.85  5133.9  454.34
  5186.4   454.1  5223.3   455.4    5299  457.54  5429.6  463.07  5595.2  463.72
#Mann= 3 ,-1 , 0
    4080     .05       0    4850     .03       0  5223.3     .05       0
Bank Sta=4813,5223.3
XS Rating Curve= 0 ,0
Exp/Cntr=0.3,0.1

Chan Stop Cuts=-1
Use User Specified Reach Order=0
Composite Channel Slope=5