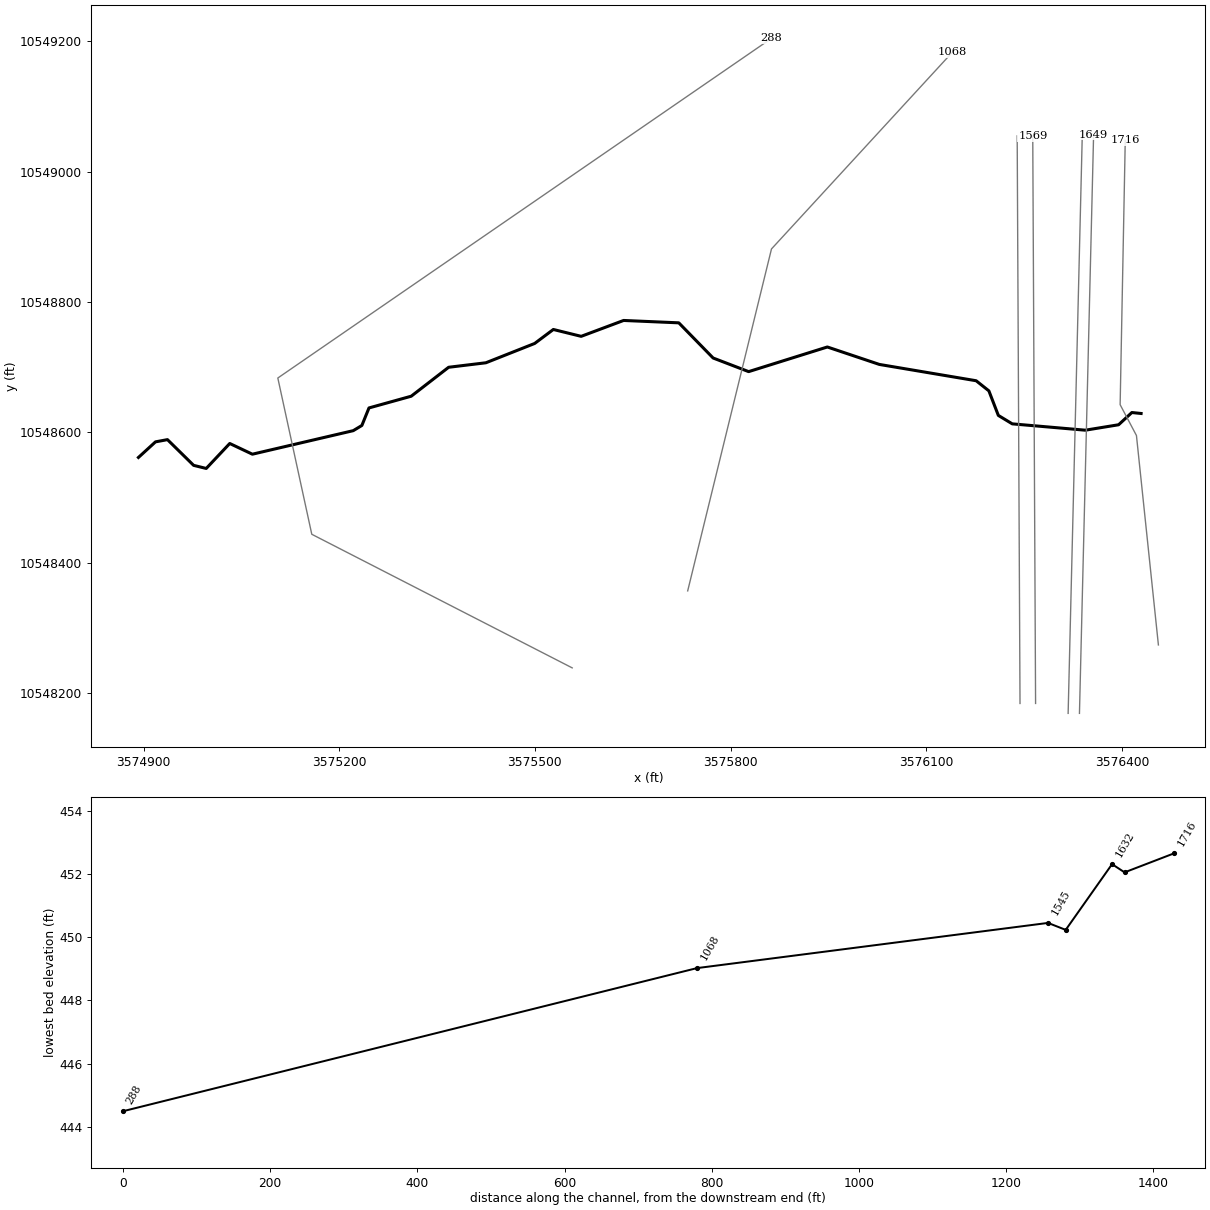
--- UNT0665 IN SAND CR.prj (project) ---

Proj Title=UNT0665 IN SAND CR Base Level Engineering
Current Plan=p01
Default Exp/Contr=0.3,0.1
English Units
Geom File=g01
Flow File=f01
Plan File=p01
Y Axis Title=Elevation
X Axis Title(PF)=Main Channel Distance
X Axis Title(XS)=Station
BEGIN DESCRIPTION:
UNT0665 IN SAND CR
END DESCRIPTION:
DSS Export Rating Curves= 0
DSS Export Rating Curve Sorted= 0
DSS Export Volume Flow Curves= 0
DXF OffsetX= 0
DXF OffsetY= 0
DXF ScaleX= 1
DXF ScaleY= 10

--- UNT0665 IN SAND CR.p01 (plan) ---

Plan Title=Multiple Run
Short Identifier=Multiple
Geom File=g01
Flow File=f01
Subcritical Flow
K Sum by GR= 0
Std Step Tol= 0.01
Critical Tol= 0.01
Num of Std Step Trials= 20
Max Error Tol= 0.3
Flow Tol Ratio= 0.001
Split Flow NTrial= 30
Split Flow Tol= 0.02
Split Flow Ratio= 0.02
Log Output Level= 0
Friction Slope Method= 1
Unsteady Friction Slope Method= 2
Unsteady Bridges Friction Slope Method= 1
Parabolic Critical Depth
Global Vel Dist=  1 , 1 , 1
Global Log Level= 0
CheckData=True
Encroach Param= -1, 0, 0, 0
BEGIN DESCRIPTION:
Multiple Run
END DESCRIPTION:

--- UNT0665 IN SAND CR.f01 (steady flow) ---

Flow Title=Multiple
Number of Profiles=7
Profile Names=10-year,25-year,50-year,1pct_min,100-year,1pct_plu,500-year
River Rch & RM= UNT0665 IN SAND ,Reach-1,1716
     473     617     730     631     854    1155    1163
Boundary for River Rch & Prof#=UNT0665 IN SAND ,Reach-1,1
Up Type=0
Dn Type=3
Dn Slope=0.005
Boundary for River Rch & Prof#=UNT0665 IN SAND ,Reach-1,2
Up Type=0
Dn Type=3
Dn Slope=0.005
Boundary for River Rch & Prof#=UNT0665 IN SAND ,Reach-1,3
Up Type=0
Dn Type=3
Dn Slope=0.005
Boundary for River Rch & Prof#=UNT0665 IN SAND ,Reach-1,4
Up Type=0
Dn Type=3
Dn Slope=0.005
Boundary for River Rch & Prof#=UNT0665 IN SAND ,Reach-1,5
Up Type=0
Dn Type=3
Dn Slope=0.005
Boundary for River Rch & Prof#=UNT0665 IN SAND ,Reach-1,6
Up Type=0
Dn Type=3
Dn Slope=0.005
Boundary for River Rch & Prof#=UNT0665 IN SAND ,Reach-1,7
Up Type=0
Dn Type=3
Dn Slope=0.005

--- UNT0665 IN SAND CR.g01 (geometry) ---

Geom Title=Existing Conditions
Program Version=4.10

River Reach=UNT0665 IN SAND ,Reach-1
Reach XY= 30
      3576429.53     10548629.07      3576415.35     10548630.54
      3576395.03     10548611.79      3576343.99     10548603.45
      3576231.96     10548613.17      3576210.63      10548626.1
      3576196.11     10548663.76      3576176.59     10548679.27
      3576028.18     10548704.28      3575948.43     10548731.03
      3575827.76     10548693.25      3575773.29     10548714.13
      3575720.66     10548768.06      3575636.03     10548771.71
      3575570.97     10548747.36       3575528.3     10548757.88
      3575499.67     10548736.44      3575424.88     10548706.83
      3575367.75     10548699.92      3575310.38     10548655.55
      3575245.62     10548637.57      3575234.71     10548610.69
      3575221.51     10548602.74      3575066.82     10548566.64
      3575032.12     10548583.06      3574996.07     10548544.78
      3574976.75     10548549.54      3574936.63     10548588.97
      3574918.28     10548585.57      3574892.11     10548561.64

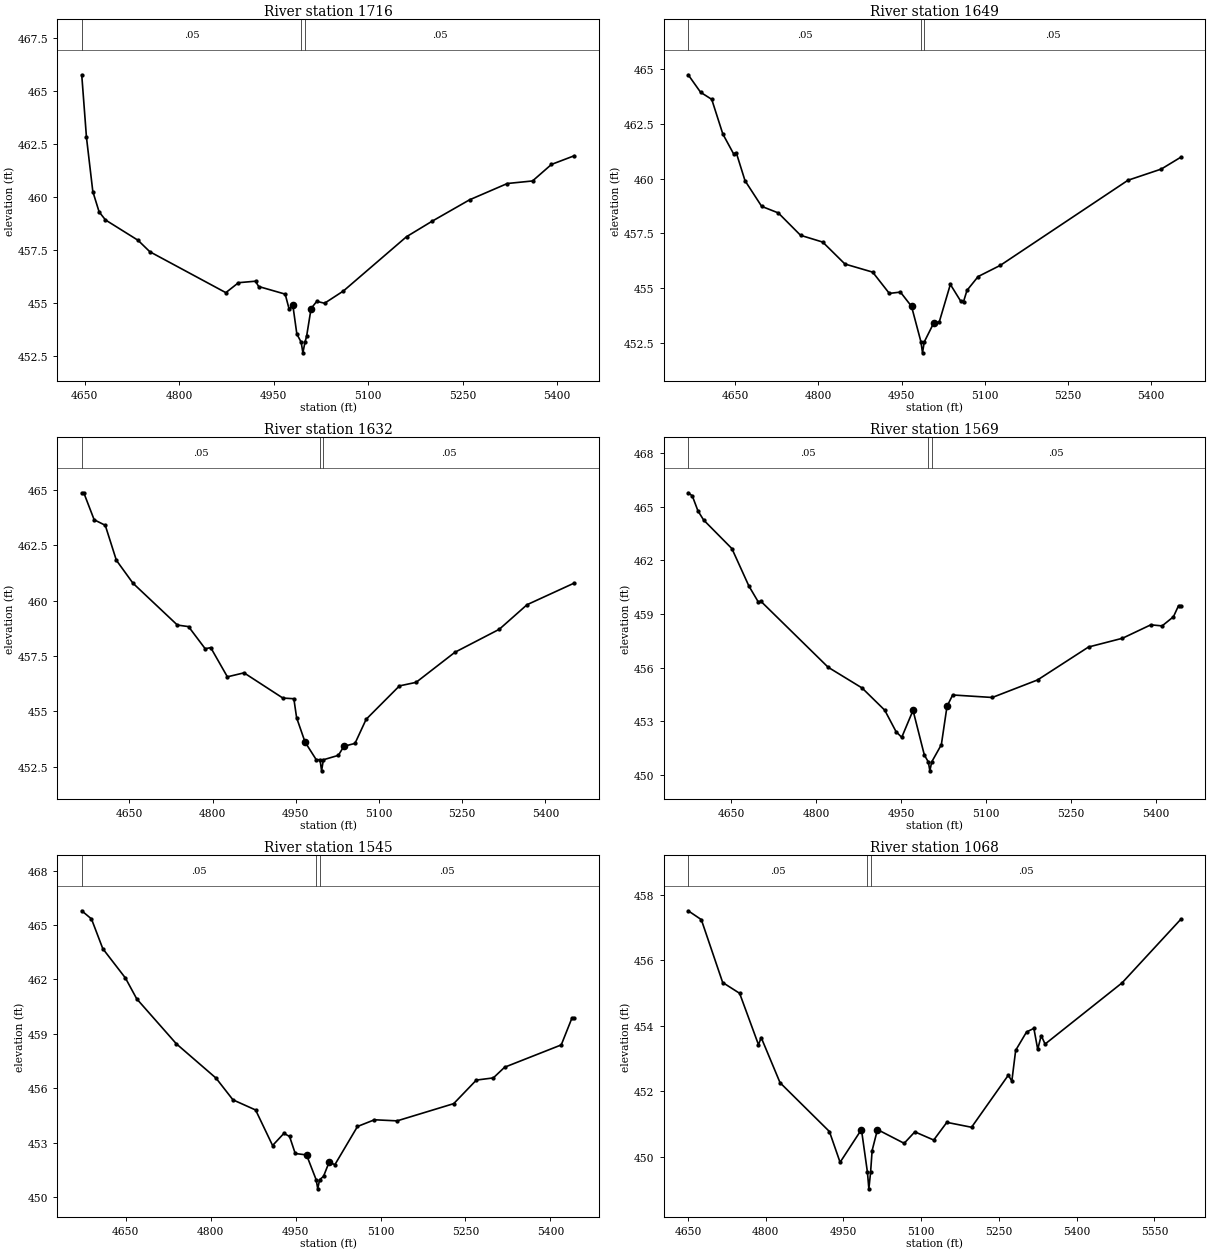
Type RM Length L Ch R = 1 ,1716    ,67,67,67
BEGIN DESCRIPTION:
UNT0665 IN SAND CR 2.3
END DESCRIPTION:
XS GIS Cut Line= 4
      3576456.05     10548274.18      3576422.38     10548595.32
      3576397.38     10548642.54      3576405.22     10549047.93
#Sta/Elev= 30
  4645.4  465.77  4652.9  462.82    4663  460.26    4673   459.3  4683.1  458.92
  4734.8  457.96  4753.5  457.42  4874.1  455.49  4894.2  455.96  4921.2  456.03
  4926.2  455.78  4968.3  455.42  4974.7   454.7  4980.3  454.93  4986.8  453.54
  4993.7  453.15  4996.4  452.65  4999.7  453.15  5002.3  453.43  5009.4  454.74
  5018.4  455.08  5030.8  454.99  5060.8  455.57  5160.9  458.13  5200.9  458.85
  5260.9  459.87  5320.9  460.64  5360.9  460.76  5390.9  461.54  5427.2  461.95
#Mann= 3 ,-1 , 0
  4645.4     .05       0  4993.7     .04       0  4999.7     .05       0
Bank Sta=4980.3,5009.4
XS Rating Curve= 0 ,0
Exp/Cntr=0.3,0.1

Type RM Length L Ch R = 1 ,1649    ,17,17,17
BEGIN DESCRIPTION:
UNT0665 IN SAND CR 2.2
END DESCRIPTION:
XS GIS Cut Line= 2
        3576335.     10548169.25       3576356.7     10549056.78
#Sta/Elev= 30
  4565.4  464.73  4587.8  463.93  4607.8  463.61  4627.8  462.03  4647.1  461.13
  4652.1  461.17  4667.8   459.9  4697.8  458.73  4727.8  458.43  4767.9  457.41
  4807.9   457.1  4847.9   456.1  4897.9  455.73  4927.9  454.76  4947.9  454.82
  4967.9  454.17  4984.9  452.55  4987.7  452.05  4990.9  452.55  5007.9  453.41
  5017.9  453.46  5037.9  455.17  5056.7   454.4  5061.7  454.39  5067.9   454.9
    5088  455.53    5128  456.04    5358  459.92    5418  460.43  5453.2  460.97
#Mann= 3 ,-1 , 0
  4565.4     .05       0  4984.9     .03       0  4990.9     .05       0
Bank Sta=4967.9,5007.9
XS Rating Curve= 0 ,0
Exp/Cntr=0.3,0.1

Type RM Length L Ch R = 1 ,1632    ,63,63,63
BEGIN DESCRIPTION:
UNT0665 IN SAND CR 2.1
END DESCRIPTION:
XS GIS Cut Line= 2
      3576317.64     10548169.24      3576339.34     10549056.78
#Sta/Elev= 30
  4564.3  464.88    4568  464.88  4586.7  463.66  4606.7  463.41  4626.7  461.83
  4656.7  460.79  4736.7   458.9  4756.8  458.83  4786.8  457.83  4796.8  457.88
  4826.8  456.56  4856.8  456.74  4926.8   455.6  4946.6  455.57  4951.6  454.71
  4966.8  453.61  4986.8  452.82  4993.8  452.81  4996.6  452.31  4999.8  452.81
  5026.8  453.01  5036.8  453.42  5056.8  453.55  5076.9  454.64  5136.9  456.15
  5166.9  456.31  5236.9  457.67  5316.9  458.71  5366.9  459.82  5452.1   460.8
#Mann= 3 ,-1 , 0
  4564.3     .05       0  4993.8     .03       0  4999.8     .05       0
Bank Sta=4966.8,5036.8
XS Rating Curve= 0 ,0
Exp/Cntr=0.3,0.1

Type RM Length L Ch R = 1 ,1569    ,24,24,24
BEGIN DESCRIPTION:
UNT0665 IN SAND CR 2.0
END DESCRIPTION:
XS GIS Cut Line= 2
      3576267.73     10548184.46      3576263.39     10549054.65
#Sta/Elev= 30
  4574.2  465.77  4581.4   465.6  4591.4  464.76  4601.4  464.25  4651.4  462.65
  4681.4  460.56  4697.8  459.68  4702.8   459.7  4821.4  456.02  4881.4  454.86
  4921.4  453.62  4941.4  452.42  4951.4   452.1  4971.4  453.61  4991.4  451.11
  4998.4  450.73  5001.1  450.23  5004.4  450.73  5021.4  451.69  5031.4  453.83
  5041.4  454.47  5111.4  454.33  5191.4  455.31  5281.4  457.15  5341.4  457.64
  5391.4  458.39  5411.4  458.33  5431.4  458.84  5440.4  459.46  5444.4  459.46
#Mann= 3 ,-1 , 0
  4574.2     .05       0  4998.4     .03       0  5004.4     .05       0
Bank Sta=4971.4,5031.4
XS Rating Curve= 0 ,0
Exp/Cntr=0.3,0.1

Type RM Length L Ch R = 1 ,1545    ,477,477,477
BEGIN DESCRIPTION:
UNT0665 IN SAND CR 2.4
END DESCRIPTION:
XS GIS Cut Line= 2
      3576243.86     10548184.43      3576239.52     10549054.72
#Sta/Elev= 30
  4572.1  465.79  4589.3  465.34  4609.3   463.7  4649.3  462.08  4669.3  460.93
  4739.3  458.45  4809.3  456.56  4839.3  455.36  4879.3   454.8  4909.3  452.84
  4929.3  453.51  4939.3  453.34  4949.3   452.4  4969.3  452.32  4986.3  450.95
  4989.1  450.45  4992.3  450.95  4999.3  451.14  5009.3  451.93  5019.3  451.78
  5059.3  453.89  5089.3  454.26  5129.3   454.2  5229.3  455.15  5269.3  456.45
  5299.3  456.57  5319.3  457.16  5419.3  458.39  5438.3  459.88  5442.4  459.88
#Mann= 3 ,-1 , 0
  4572.1     .05       0  4986.3     .03       0  4992.3     .05       0
Bank Sta=4969.3,5009.3
XS Rating Curve= 0 ,0
Exp/Cntr=0.3,0.1

Type RM Length L Ch R = 1 ,1068    ,780,780,780
BEGIN DESCRIPTION:
UNT0665 IN SAND CR 1.1
END DESCRIPTION:
XS GIS Cut Line= 3
       3575734.3     10548357.04      3575862.78     10548881.36
      3576140.54     10549183.43
#Sta/Elev= 30
  4650.6  457.51  4675.9  457.24  4717.1  455.32  4749.8  454.99  4786.2  453.42
  4791.4  453.64  4827.8  452.26    4923  450.77  4943.6  449.83  4984.8  450.83
  4996.4  449.52  4999.1  449.02  5002.4  449.52  5005.4  450.19  5015.7  450.83
  5067.2  450.41  5087.8  450.76  5124.2  450.51  5149.5  451.05  5197.2   450.9
  5268.1  452.49  5274.9  452.31  5282.3  453.25  5303.3  453.81  5317.4  453.92
  5324.8  453.28  5331.6   453.7    5339  453.44  5487.6  455.31  5600.8  457.25
#Mann= 3 ,-1 , 0
  4650.6     .05       0  4996.4     .03       0  5002.4     .05       0
Bank Sta=4984.8,5015.7
XS Rating Curve= 0 ,0
Exp/Cntr=0.3,0.1

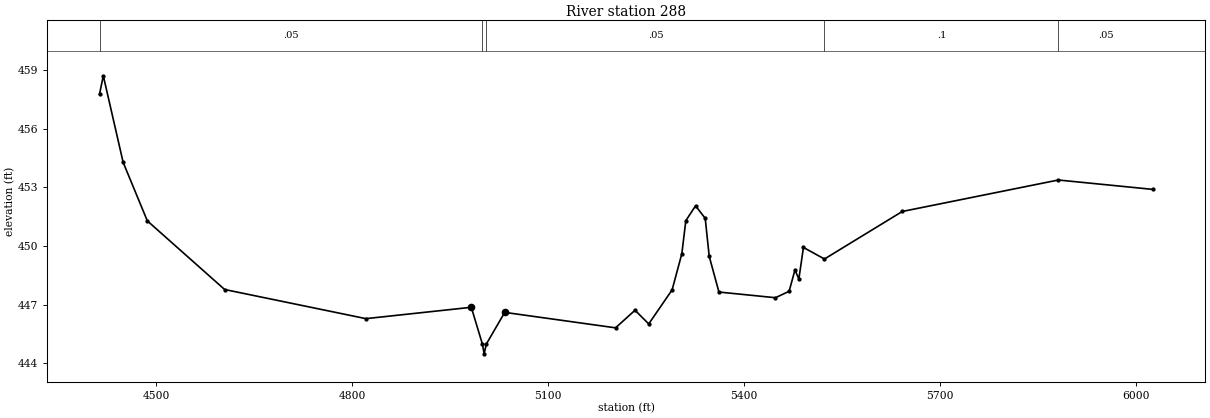
Type RM Length L Ch R = 1 ,288     ,0,0,0
BEGIN DESCRIPTION:
UNT0665 IN SAND CR 1.0
END DESCRIPTION:
XS GIS Cut Line= 4
      3575557.22       10548239.      3575157.92     10548443.86
      3575105.84     10548683.45      3575862.79     10549204.29
#Sta/Elev= 30
  4413.1  457.77  4418.9  458.71  4449.3  454.28  4486.3  451.29  4604.7  447.78
    4821  446.29  4982.4  446.87  4999.4  444.99  5002.1  444.49  5005.4  444.99
  5033.6  446.61  5203.3  445.82  5233.1  446.72  5254.1  446.02  5289.9  447.76
  5304.8  449.61  5310.9   451.3  5325.8  452.06  5340.6  451.42  5346.7  449.48
  5361.6  447.65  5448.2  447.36  5469.1  447.69    5478  448.78    5484  448.32
    5491  449.93  5523.2  449.34  5642.3  451.77  5881.3  453.38  6025.9   452.9
#Mann= 5 ,-1 , 0
  4413.1     .05       0  4999.4     .03       0  5005.4     .05       0
  5523.2      .1       0  5881.3     .05       0
Bank Sta=4982.4,5033.6
XS Rating Curve= 0 ,0
Exp/Cntr=0.3,0.1

Chan Stop Cuts=-1
Use User Specified Reach Order=0
Composite Channel Slope=5