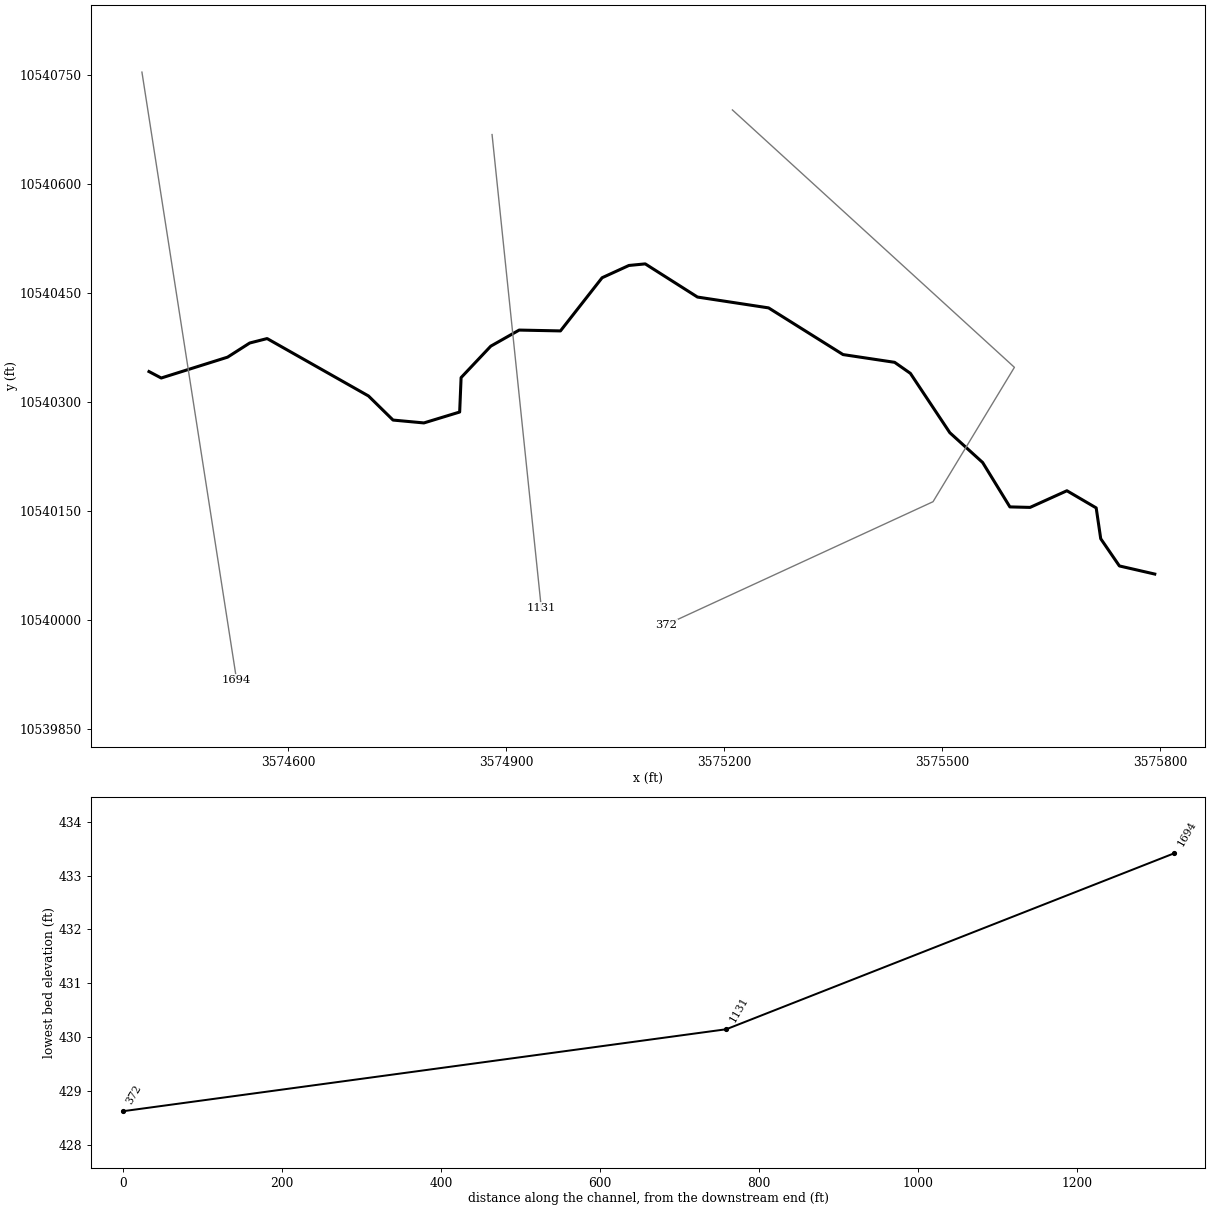
--- UNT0667 IN SAND CR.prj (project) ---

Proj Title=UNT0667 IN SAND CR Base Level Engineering
Current Plan=p01
Default Exp/Contr=0.3,0.1
English Units
Geom File=g01
Flow File=f01
Plan File=p01
BEGIN DESCRIPTION:
UNT0667 IN SAND CR
END DESCRIPTION:

--- UNT0667 IN SAND CR.p01 (plan) ---

Plan Title=Multiple Run
Short Identifier=Multiple
Geom File=g01
Flow File=f01
Subcritical Flow
K Sum by GR= 0
Std Step Tol= 0.01
Critical Tol= 0.01
Num of Std Step Trials= 20
Max Error Tol= 0.3
Flow Tol Ratio= 0.001
Split Flow NTrial= 30
Split Flow Tol= 0.02
Split Flow Ratio= 0.02
Log Output Level= 0
Friction Slope Method= 1
Unsteady Friction Slope Method= 2
Unsteady Bridges Friction Slope Method= 1
Parabolic Critical Depth
Global Vel Dist=  1 , 1 , 1
Global Log Level= 0
CheckData=True
Encroach Param= -1, 0, 0, 0
BEGIN DESCRIPTION:
Multiple Run
END DESCRIPTION:

--- UNT0667 IN SAND CR.f01 (steady flow) ---

Flow Title=Multiple
Number of Profiles=7
Profile Names=10-year,25-year,50-year,1pct_min,100-year,1pct_plu,500-year
River Rch & RM= UNT0667 IN SAND ,Reach-1,1694
     566     747     891     777    1051    1421    1454
Boundary for River Rch & Prof#=UNT0667 IN SAND ,Reach-1,1
Up Type=0
Dn Type=3
Dn Slope=0.005
Boundary for River Rch & Prof#=UNT0667 IN SAND ,Reach-1,2
Up Type=0
Dn Type=3
Dn Slope=0.005
Boundary for River Rch & Prof#=UNT0667 IN SAND ,Reach-1,3
Up Type=0
Dn Type=3
Dn Slope=0.005
Boundary for River Rch & Prof#=UNT0667 IN SAND ,Reach-1,4
Up Type=0
Dn Type=3
Dn Slope=0.005
Boundary for River Rch & Prof#=UNT0667 IN SAND ,Reach-1,5
Up Type=0
Dn Type=3
Dn Slope=0.005
Boundary for River Rch & Prof#=UNT0667 IN SAND ,Reach-1,6
Up Type=0
Dn Type=3
Dn Slope=0.005
Boundary for River Rch & Prof#=UNT0667 IN SAND ,Reach-1,7
Up Type=0
Dn Type=3
Dn Slope=0.005

--- UNT0667 IN SAND CR.g01 (geometry) ---

Geom Title=Existing Conditions

River Reach=UNT0667 IN SAND ,Reach-1
Reach XY= 30
      3574408.73     10540342.21      3574425.60     10540333.33
      3574516.86     10540362.01      3574547.34     10540381.49
      3574571.30     10540387.60      3574710.79     10540308.61
      3574744.54     10540275.46      3574787.03     10540271.52
      3574836.24     10540286.52      3574838.20     10540333.88
      3574879.03     10540377.14      3574918.11     10540399.28
      3574974.92     10540398.13      3575032.23     10540471.30
      3575069.10     10540488.18      3575091.58     10540490.37
      3575163.45     10540444.72      3575261.32     10540429.81
      3575363.77     10540365.57      3575434.73     10540354.91
      3575456.41     10540339.74      3575510.69     10540258.06
      3575555.83     10540217.09      3575593.33     10540155.97
      3575621.11     10540155.28      3575671.80     10540178.20
      3575712.08     10540154.59      3575718.33     10540112.22
      3575744.02     10540074.72      3575792.70     10540063.55

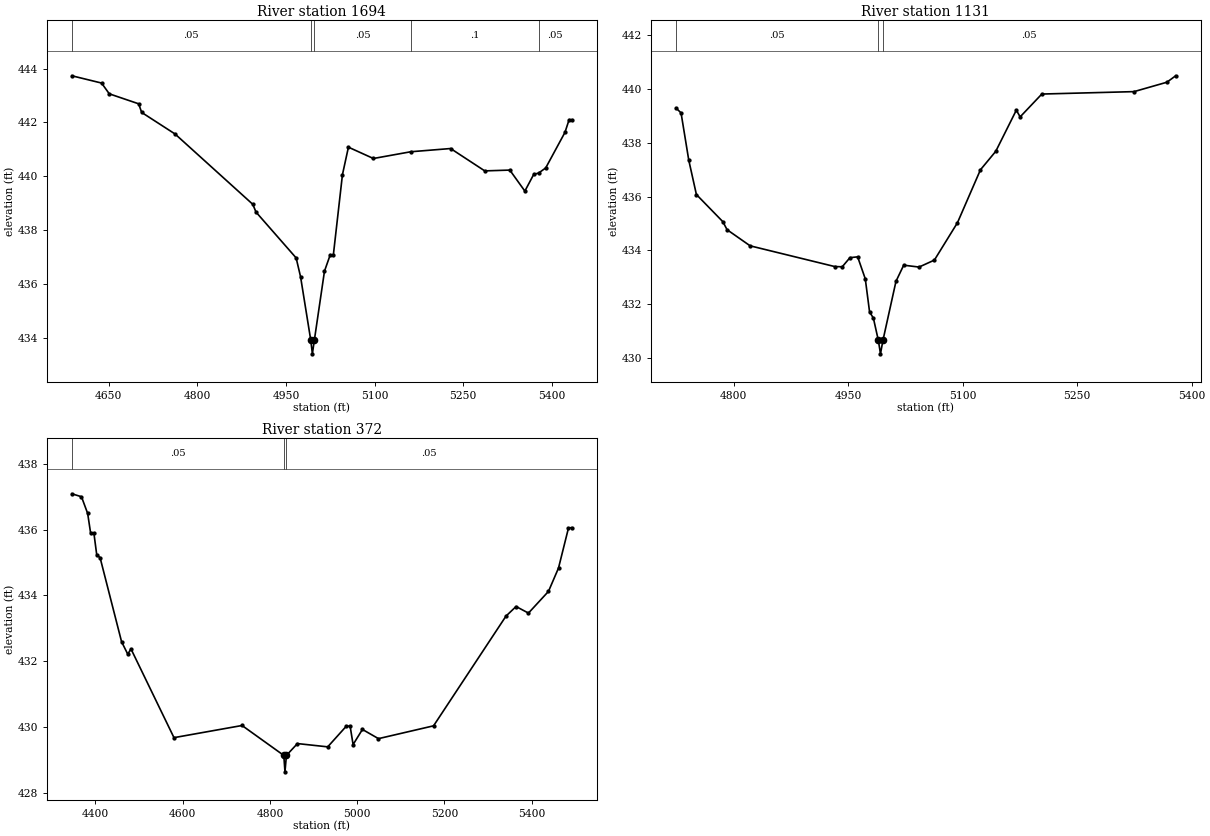
Type RM Length L Ch R = 1,1694,563,563,563
BEGIN DESCRIPTION:
UNT0667 IN SAND CR 2.0
END DESCRIPTION:
XS GIS Cut Line= 2
      3574399.04     10540754.25      3574529.24     10539918.33
#Sta/Elev= 30
  4587.6  443.73  4637.9  443.46  4651.0  443.06  4700.7  442.69  4705.8  442.37
  4762.3  441.57  4893.9  438.96  4899.4  438.67  4967.3  436.97  4974.8  436.27
  4992.1  433.91  4994.8  433.41  4998.1  433.91  5015.3  436.48  5025.1  437.09
  5030.2  437.06  5045.7  440.06  5055.8  441.08  5098.1  440.66  5161.3  440.91
  5228.8  441.03  5286.6  440.20  5329.0  440.23  5354.5  439.45  5369.5  440.07
  5377.8  440.12  5389.8  440.31  5422.4  441.63  5429.4  442.10  5433.6  442.10
#Mann=5,-1,0
  4587.6    0.05       0  4992.1    0.03       0  4998.1    0.05       0
  5161.3     0.1       0  5377.8    0.05       0
Bank Sta=4992.1,4998.1
Exp/Cntr=0.3,0.1

Type RM Length L Ch R = 1,1131,759,759,759
BEGIN DESCRIPTION:
UNT0667 IN SAND CR 1.0
END DESCRIPTION:
XS GIS Cut Line= 2
      3574880.81     10540668.32      3574948.51     10540017.33
#Sta/Elev= 30
  4724.5  439.30  4731.2  439.12  4741.3  437.36  4751.3  436.08  4785.9  435.07
  4791.5  434.77  4821.7  434.17  4932.3  433.40  4942.3  433.39  4952.4  433.73
  4962.5  433.76  4972.5  432.94  4978.1  431.71  4983.1  431.48  4989.6  430.65
  4992.4  430.15  4995.6  430.65  5012.7  432.85  5022.8  433.45  5042.9  433.38
  5063.0  433.64  5093.2  435.03  5123.3  437.00  5143.4  437.69  5170.3  439.22
  5175.3  438.97  5203.7  439.82  5324.4  439.91  5367.5  440.26  5379.0  440.50
#Mann=3,-1,0
  4724.5    0.05       0  4989.6    0.03       0  4995.6    0.05       0
Bank Sta=4989.6,4995.6
Exp/Cntr=0.3,0.1

Type RM Length L Ch R = 1,372,0,0,0
BEGIN DESCRIPTION:
UNT0667 IN SAND CR 1.1
END DESCRIPTION:
XS GIS Cut Line= 4
      3575211.51     10540702.20      3575599.56     10540348.02
      3575487.58     10540163.12      3575120.37     10539993.84
#Sta/Elev= 30
  4345.9  437.09  4368.0  437.00  4382.2  436.49  4389.0  435.89  4396.4  435.90
  4403.1  435.22  4410.6  435.15  4459.9  432.59  4474.1  432.21  4481.5  432.37
  4580.1  429.67  4736.2  430.04  4831.9  429.13  4834.6  428.63  4837.9  429.13
  4863.2  429.49  4932.6  429.39  4975.3  430.02  4984.0  430.02  4990.8  429.46
  5012.2  429.92  5049.0  429.64  5175.3  430.03  5341.5  433.37  5364.5  433.66
  5392.9  433.46  5438.8  434.12  5461.8  434.83  5484.7  436.05  5491.8  436.06
#Mann=3,-1,0
  4345.9    0.05       0  4831.9    0.03       0  4837.9    0.05       0
Bank Sta=4831.9,4837.9
Exp/Cntr=0.3,0.1

Chan Stop Cuts=-1