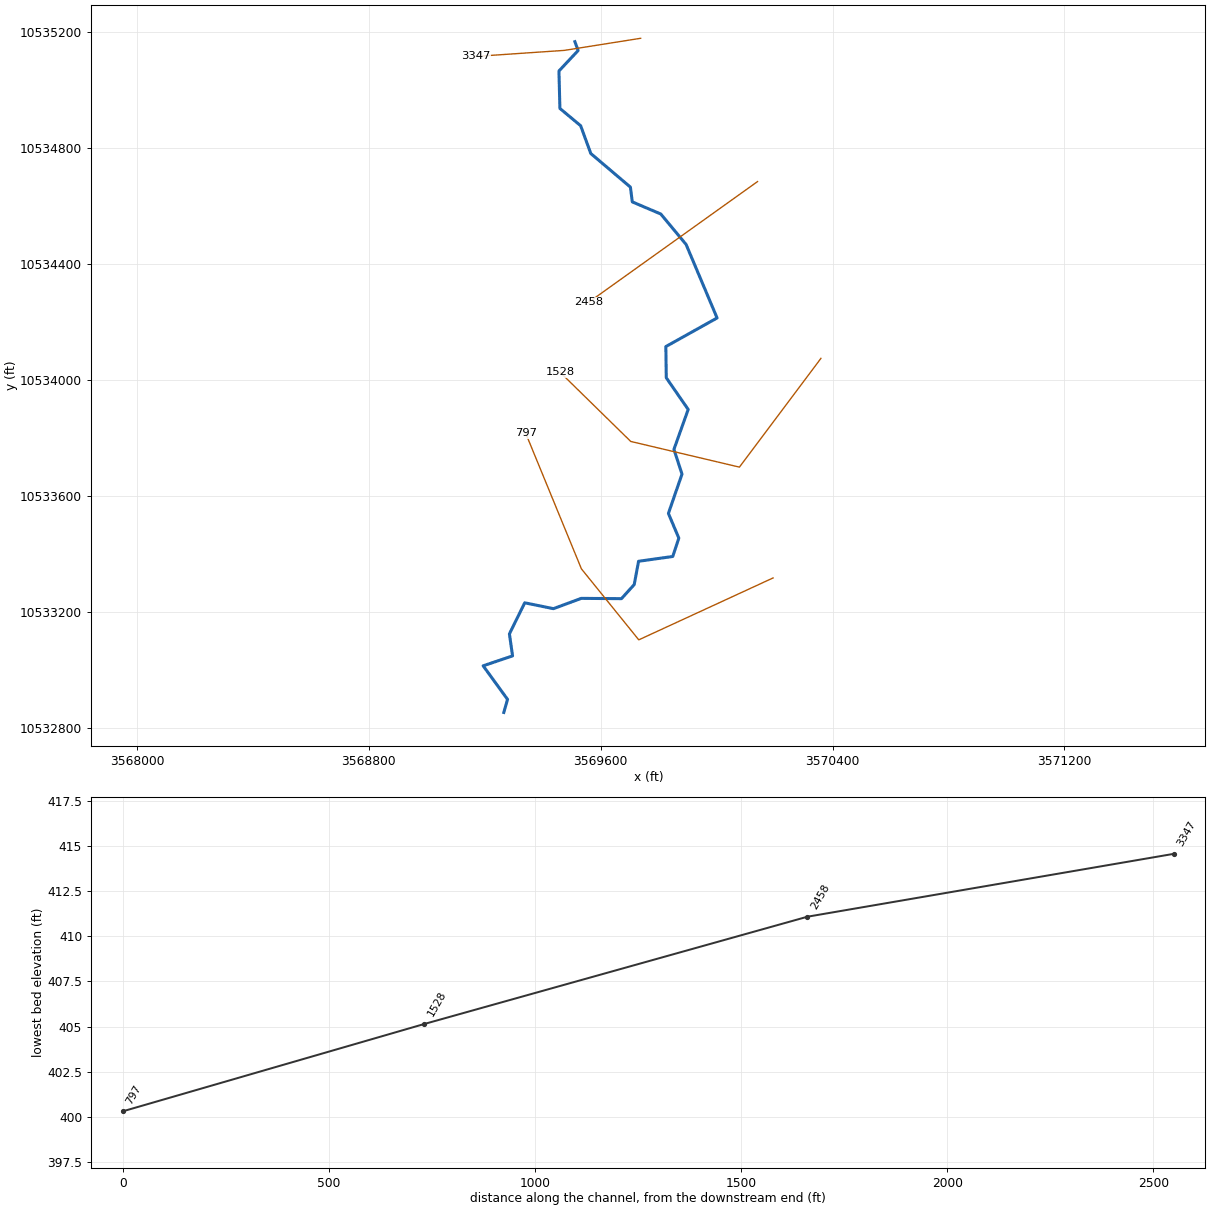
--- UNT0669 IN SAND CR.prj (project) ---

Proj Title=UNT0669 IN SAND CR Base Level Engineering
Current Plan=p01
Default Exp/Contr=0.3,0.1
English Units
Geom File=g01
Flow File=f01
Plan File=p01
BEGIN DESCRIPTION:
UNT0669 IN SAND CR
END DESCRIPTION:

--- UNT0669 IN SAND CR.p01 (plan) ---

Plan Title=Multiple Run
Short Identifier=Multiple
Geom File=g01
Flow File=f01
Subcritical Flow
K Sum by GR= 0
Std Step Tol= 0.01
Critical Tol= 0.01
Num of Std Step Trials= 20
Max Error Tol= 0.3
Flow Tol Ratio= 0.001
Split Flow NTrial= 30
Split Flow Tol= 0.02
Split Flow Ratio= 0.02
Log Output Level= 0
Friction Slope Method= 1
Unsteady Friction Slope Method= 2
Unsteady Bridges Friction Slope Method= 1
Parabolic Critical Depth
Global Vel Dist=  1 , 1 , 1
Global Log Level= 0
CheckData=True
Encroach Param= -1, 0, 0, 0
BEGIN DESCRIPTION:
Multiple Run
END DESCRIPTION:

--- UNT0669 IN SAND CR.f01 (steady flow) ---

Flow Title=Multiple
Number of Profiles=7
Profile Names=10-year,25-year,50-year,1pct_min,100-year,1pct_plu,500-year
River Rch & RM= UNT0669 IN SAND ,Reach-1,3347
     803    1080    1303    1148    1552    2099    2194
Boundary for River Rch & Prof#=UNT0669 IN SAND ,Reach-1,1
Up Type=0
Dn Type=3
Dn Slope=0.005
Boundary for River Rch & Prof#=UNT0669 IN SAND ,Reach-1,2
Up Type=0
Dn Type=3
Dn Slope=0.005
Boundary for River Rch & Prof#=UNT0669 IN SAND ,Reach-1,3
Up Type=0
Dn Type=3
Dn Slope=0.005
Boundary for River Rch & Prof#=UNT0669 IN SAND ,Reach-1,4
Up Type=0
Dn Type=3
Dn Slope=0.005
Boundary for River Rch & Prof#=UNT0669 IN SAND ,Reach-1,5
Up Type=0
Dn Type=3
Dn Slope=0.005
Boundary for River Rch & Prof#=UNT0669 IN SAND ,Reach-1,6
Up Type=0
Dn Type=3
Dn Slope=0.005
Boundary for River Rch & Prof#=UNT0669 IN SAND ,Reach-1,7
Up Type=0
Dn Type=3
Dn Slope=0.005

--- UNT0669 IN SAND CR.g01 (geometry) ---

Geom Title=Existing Conditions

River Reach=UNT0669 IN SAND ,Reach-1
Reach XY= 30
      3569511.11     10535167.51      3569522.35     10535137.00
      3569456.16     10535066.47      3569459.42     10534937.35
      3569531.03     10534877.67      3569565.96     10534782.00
      3569702.65     10534666.07      3569709.22     10534615.15
      3569807.65     10534573.26      3569894.93     10534468.14
      3570001.72     10534214.96      3569824.92     10534116.33
      3569826.44     10534008.78      3569902.02     10533899.59
      3569852.87     10533761.97      3569880.69     10533676.61
      3569833.72     10533541.15      3569869.74     10533456.14
      3569848.70     10533392.70      3569730.82     10533376.23
      3569715.86     10533296.03      3569671.90     10533247.35
      3569533.11     10533248.34      3569437.08     10533212.82
      3569338.11     10533233.05      3569285.25     10533125.85
      3569296.10     10533049.94      3569194.67     10533015.85
      3569278.85     10532899.97      3569265.87     10532855.11

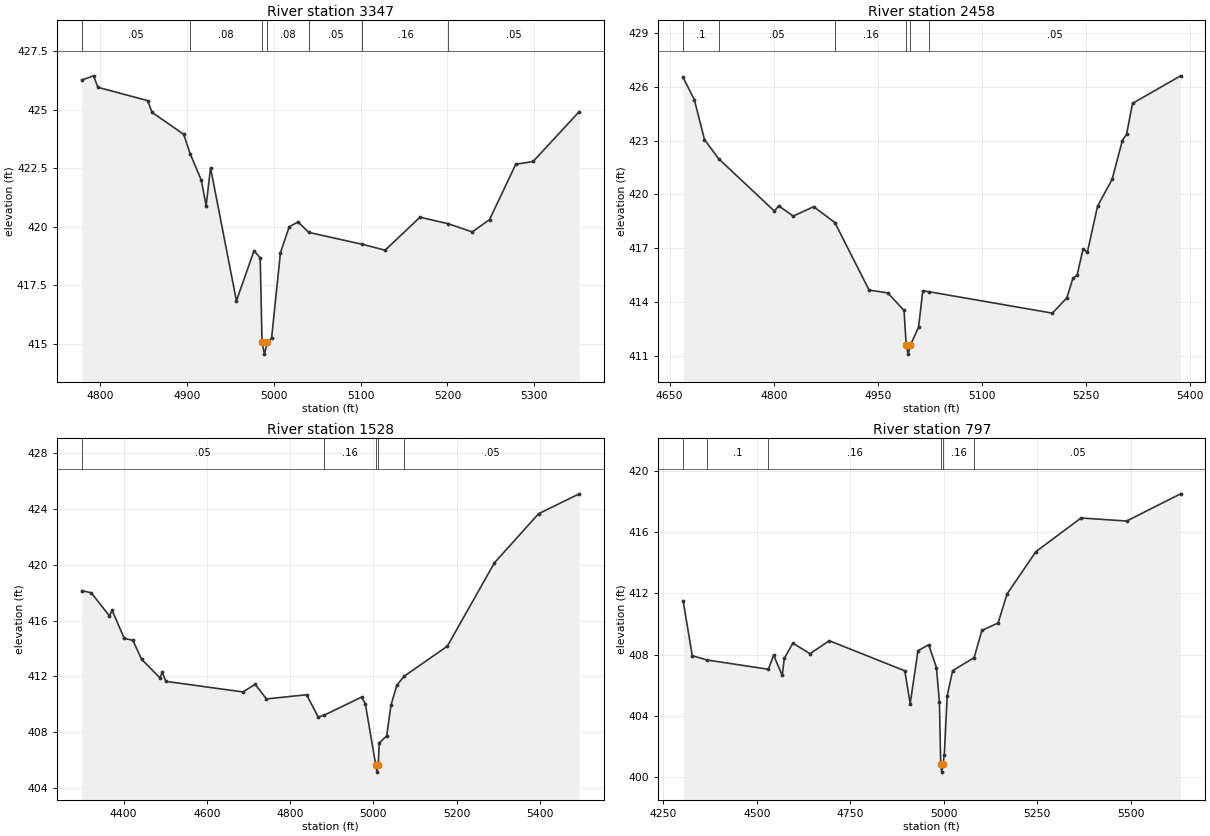
Type RM Length L Ch R = 1,3347,889,889,889
BEGIN DESCRIPTION:
UNT0669 IN SAND CR 4.0
END DESCRIPTION:
XS GIS Cut Line= 3
      3569738.06     10535179.13      3569475.08     10535137.47
      3569169.14     10535116.64
#Sta/Elev= 30
  4778.8  426.27  4792.3  426.45  4797.4  425.96  4854.6  425.39  4859.7  424.89
  4896.2  423.95  4903.5  423.13  4916.4  422.00  4922.0  420.90  4927.1  422.52
  4956.9  416.84  4977.2  418.98  4984.3  418.67  4986.4  415.06  4989.2  414.56
  4992.4  415.06  4997.4  415.24  5007.6  418.89  5017.7  420.00  5027.8  420.21
  5040.3  419.76  5102.1  419.25  5128.2  419.00  5168.3  420.41  5200.9  420.13
  5228.5  419.78  5248.5  420.31  5278.6  422.67  5298.6  422.79  5351.7  424.92
#Mann=7,-1,0
  4778.8    0.05       0  4903.5    0.08       0  4986.4    0.07       0
  4992.4    0.08       0  5040.3    0.05       0  5102.1    0.16       0
  5200.9    0.05       0
Bank Sta=4986.4,4992.4
Exp/Cntr=0.3,0.1

Type RM Length L Ch R = 1,2458,930,930,930
BEGIN DESCRIPTION:
UNT0669 IN SAND CR 3.0
END DESCRIPTION:
XS GIS Cut Line= 2
      3570141.28     10534685.19      3569557.92     10534268.50
#Sta/Elev= 30
  4669.4  426.54  4685.5  425.30  4700.2  423.07  4720.5  422.00  4801.0  419.07
  4807.1  419.37  4828.1  418.79  4857.5  419.32  4888.1  418.43  4937.4  414.66
  4964.4  414.50  4987.8  413.52  4990.9  411.58  4993.7  411.08  4996.9  411.58
  5008.7  412.58  5014.8  414.62  5023.3  414.57  5201.6  413.37  5222.5  414.23
  5231.1  415.31  5237.2  415.49  5245.8  416.96  5252.0  416.77  5266.7  419.35
  5287.6  420.84  5302.4  423.01  5308.5  423.37  5317.1  425.09  5386.3  426.63
#Mann=6,-1,0
  4669.4     0.1       0  4720.5    0.05       0  4888.1    0.16       0
  4990.9    0.07       0  4996.9    0.16       0  5023.3    0.05       0
Bank Sta=4990.9,4996.9
Exp/Cntr=0.3,0.1

Type RM Length L Ch R = 1,1528,731,731,731
BEGIN DESCRIPTION:
UNT0669 IN SAND CR 2.0
END DESCRIPTION:
XS GIS Cut Line= 4
      3570360.05     10534075.84      3570078.77     10533700.80
      3569703.77     10533789.34      3569460.14     10534027.78
#Sta/Elev= 30
  4299.5  418.16  4322.3  418.00  4366.0  416.34  4372.3  416.75  4401.4  414.74
  4422.3  414.59  4443.1  413.24  4486.9  411.91  4493.1  412.29  4501.4  411.65
  4686.9  410.89  4716.0  411.44  4743.1  410.39  4839.6  410.69  4867.6  409.09
  4882.1  409.23  4971.6  410.52  4980.6  410.06  5005.8  405.64  5008.6  405.14
  5011.8  405.64  5014.0  407.23  5032.0  407.74  5042.3  409.94  5056.3  411.37
  5074.0  412.02  5177.6  414.17  5290.8  420.15  5396.8  423.67  5494.5  425.10
#Mann=5,-1,0
  4299.5    0.05       0  4882.1    0.16       0  5005.8    0.07       0
  5011.8    0.16       0  5074.0    0.05       0
Bank Sta=5005.8,5011.8
Exp/Cntr=0.3,0.1

Type RM Length L Ch R = 1,797,0,0,0
BEGIN DESCRIPTION:
UNT0669 IN SAND CR 1.0
END DESCRIPTION:
XS GIS Cut Line= 4
      3570195.07     10533318.85      3569731.55     10533105.32
      3569533.63     10533350.11      3569341.36     10533817.79
#Sta/Elev= 30
  4302.9  411.52  4327.4  407.93  4366.2  407.65  4531.1  407.04  4545.0  407.97
  4568.0  406.64  4573.5  407.75  4596.5  408.75  4642.4  408.06  4693.8  408.91
  4896.0  406.94  4910.4  404.79  4931.2  408.25  4959.9  408.65  4980.7  407.14
  4988.6  404.87  4992.1  400.81  4994.9  400.31  4998.1  400.81  5001.6  401.44
  5009.5  405.32  5023.9  406.95  5081.4  407.80  5102.2  409.58  5145.6  410.07
  5169.5  411.97  5246.8  414.74  5367.6  416.94  5489.5  416.74  5633.7  418.52
#Mann=6,-1,0
  4302.9    0.05       0  4366.2     0.1       0  4531.1    0.16       0
  4992.1    0.07       0  4998.1    0.16       0  5081.4    0.05       0
Bank Sta=4992.1,4998.1
Exp/Cntr=0.3,0.1

Chan Stop Cuts=-1