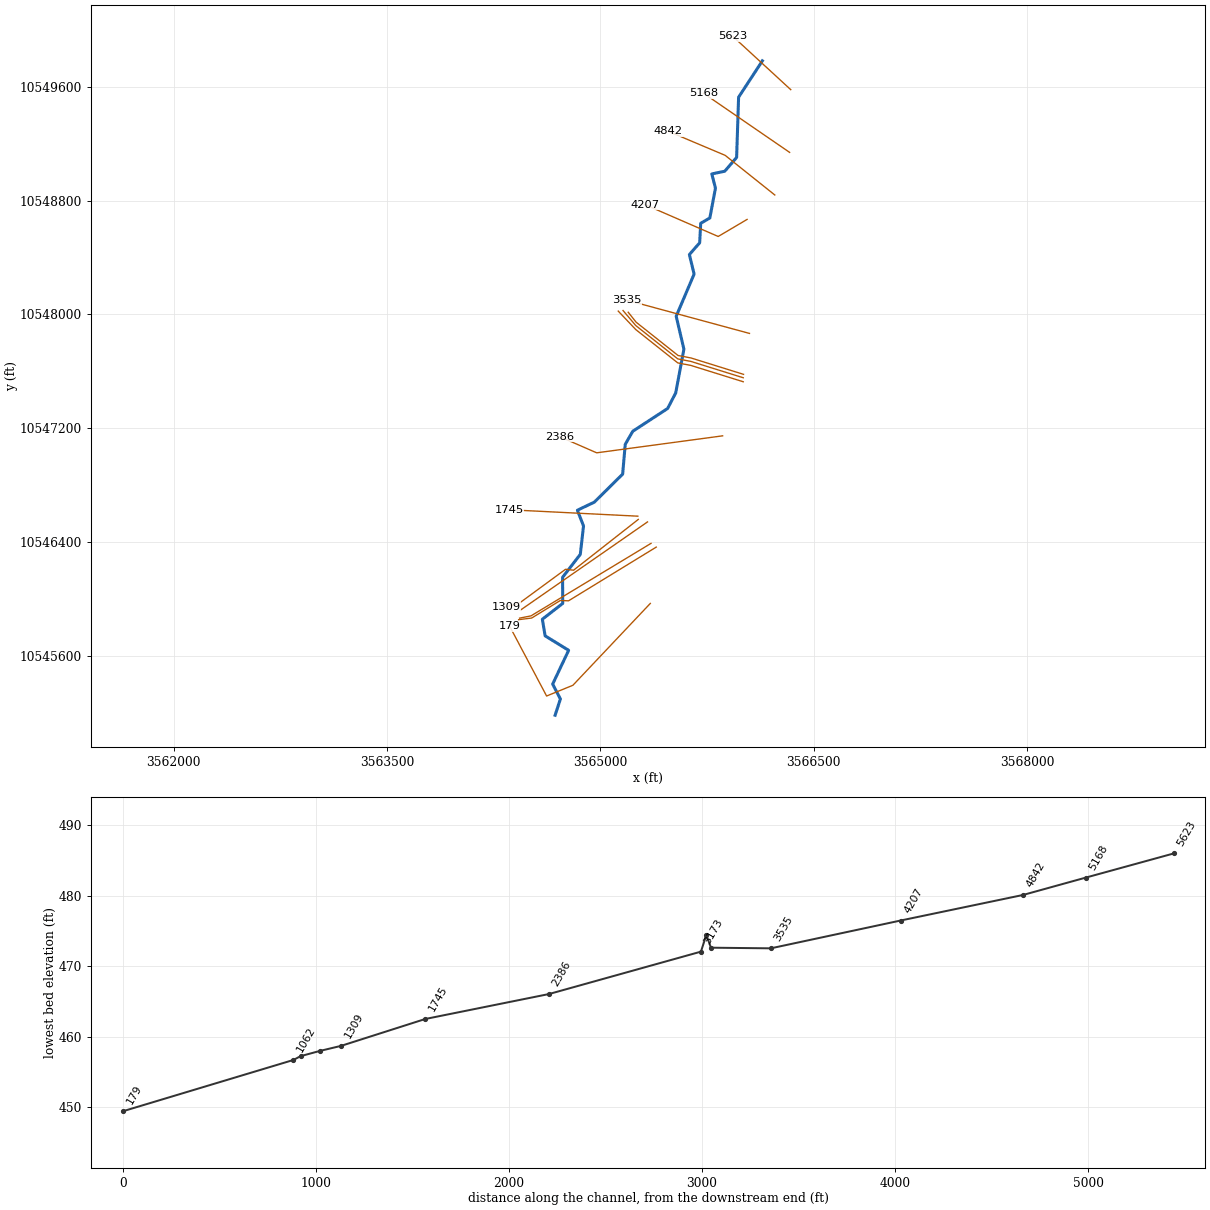
--- UNT0673 IN SAND CR.prj (project) ---

Proj Title=UNT0673 IN SAND CR Base Level Engineering
Current Plan=p01
Default Exp/Contr=0.3,0.1
English Units
Geom File=g01
Flow File=f01
Plan File=p01
BEGIN DESCRIPTION:
UNT0673 IN SAND CR
END DESCRIPTION:

--- UNT0673 IN SAND CR.p01 (plan) ---

Plan Title=Multiple Run
Short Identifier=Multiple
Geom File=g01
Flow File=f01
Subcritical Flow
K Sum by GR= 0
Std Step Tol= 0.01
Critical Tol= 0.01
Num of Std Step Trials= 20
Max Error Tol= 0.3
Flow Tol Ratio= 0.001
Split Flow NTrial= 30
Split Flow Tol= 0.02
Split Flow Ratio= 0.02
Log Output Level= 0
Friction Slope Method= 1
Unsteady Friction Slope Method= 2
Unsteady Bridges Friction Slope Method= 1
Parabolic Critical Depth
Global Vel Dist=  1 , 1 , 1
Global Log Level= 0
CheckData=True
Encroach Param= -1, 0, 0, 0
BEGIN DESCRIPTION:
Multiple Run
END DESCRIPTION:

--- UNT0673 IN SAND CR.f01 (steady flow) ---

Flow Title=Multiple
Number of Profiles=7
Profile Names=10-year,25-year,50-year,1pct_min,100-year,1pct_plu,500-year
River Rch & RM= UNT0673 IN SAND ,Reach-1,5623
     630     837    1003     879    1189    1607    1661
Boundary for River Rch & Prof#=UNT0673 IN SAND ,Reach-1,1
Up Type=0
Dn Type=3
Dn Slope=0.005
Boundary for River Rch & Prof#=UNT0673 IN SAND ,Reach-1,2
Up Type=0
Dn Type=3
Dn Slope=0.005
Boundary for River Rch & Prof#=UNT0673 IN SAND ,Reach-1,3
Up Type=0
Dn Type=3
Dn Slope=0.005
Boundary for River Rch & Prof#=UNT0673 IN SAND ,Reach-1,4
Up Type=0
Dn Type=3
Dn Slope=0.005
Boundary for River Rch & Prof#=UNT0673 IN SAND ,Reach-1,5
Up Type=0
Dn Type=3
Dn Slope=0.005
Boundary for River Rch & Prof#=UNT0673 IN SAND ,Reach-1,6
Up Type=0
Dn Type=3
Dn Slope=0.005
Boundary for River Rch & Prof#=UNT0673 IN SAND ,Reach-1,7
Up Type=0
Dn Type=3
Dn Slope=0.005

--- UNT0673 IN SAND CR.g01 (geometry) ---

Geom Title=Existing Conditions

River Reach=UNT0673 IN SAND ,Reach-1
Reach XY= 30
      3566139.31     10549782.13      3565972.11     10549526.64
      3565958.14     10549102.93      3565874.88     10549006.19
      3565783.78     10548986.98      3565809.38     10548887.25
      3565769.93     10548677.23      3565705.64     10548640.25
      3565698.50     10548503.00      3565626.08     10548420.30
      3565659.35     10548282.79      3565533.33     10547986.44
      3565587.58     10547755.32      3565530.03     10547447.56
      3565473.06     10547338.05      3565228.24     10547178.19
      3565175.20     10547085.99      3565156.93     10546876.73
      3564957.93     10546679.77      3564838.76     10546622.81
      3564881.90     10546512.36      3564859.26     10546312.64
      3564734.85     10546151.59      3564735.54     10545967.56
      3564592.49     10545856.45      3564611.93     10545739.79
      3564777.28     10545637.92      3564664.91     10545400.58
      3564719.36     10545296.01      3564682.11     10545181.64

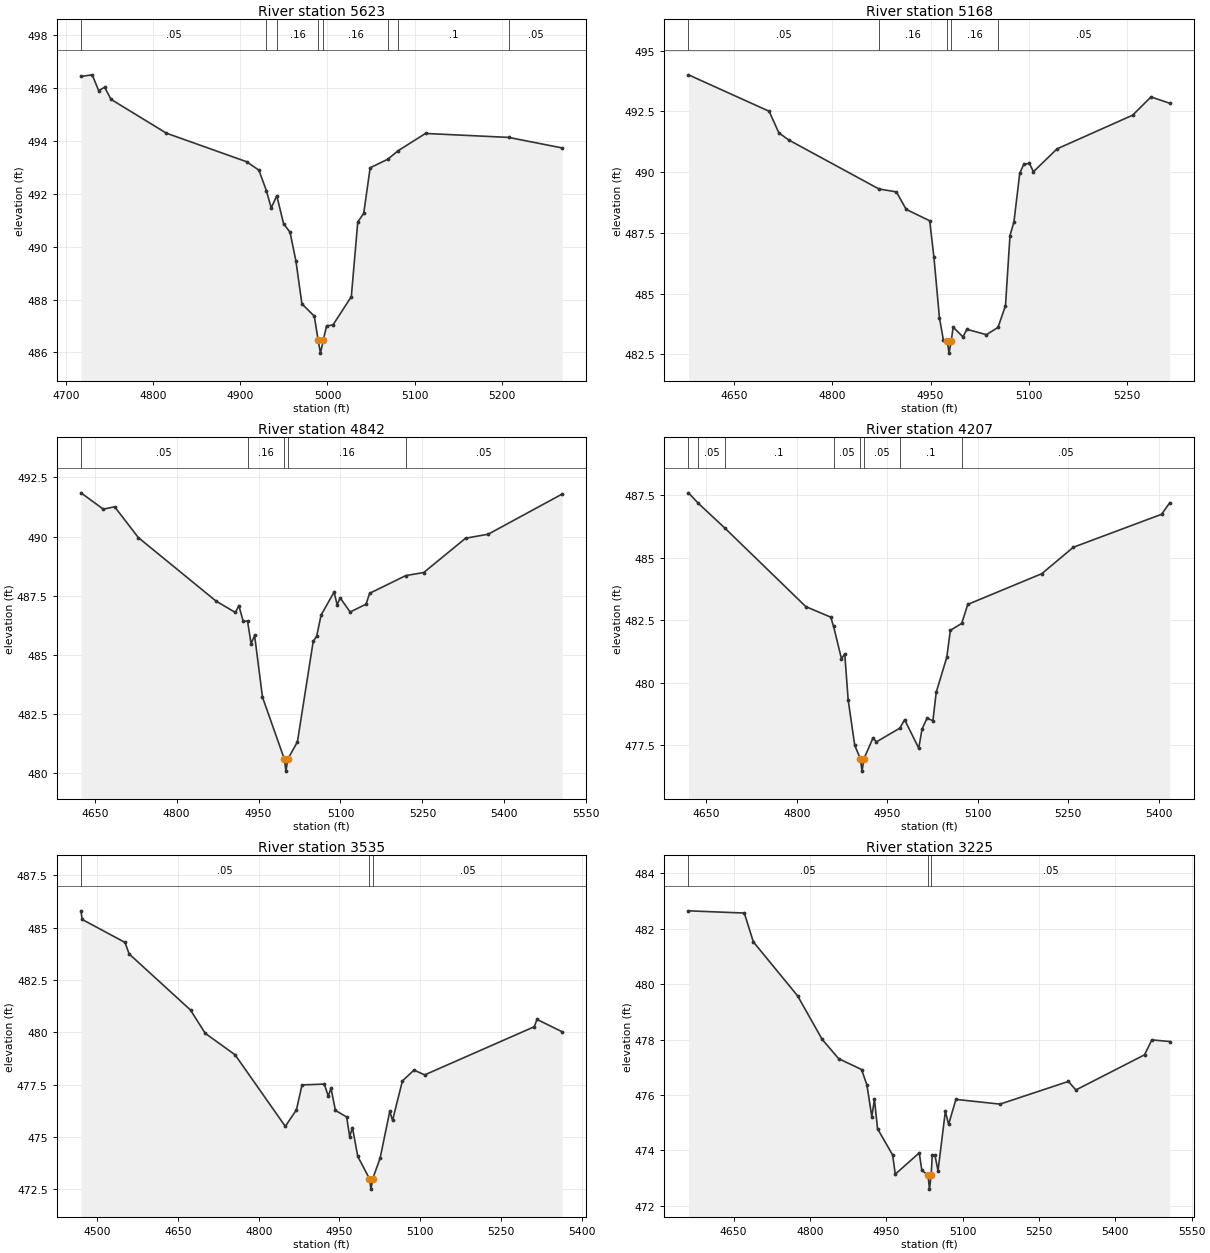
Type RM Length L Ch R = 1,5623,455,455,455
BEGIN DESCRIPTION:
UNT0673 IN SAND CR 10.5
END DESCRIPTION:
XS GIS Cut Line= 2
      3566338.59     10549579.69      3565932.33     10549953.40
#Sta/Elev= 30
  4717.3  496.45  4730.2  496.51  4737.6  495.91  4744.4  496.04  4751.8  495.58
  4815.3  494.30  4907.2  493.22  4921.4  492.90  4930.0  492.12  4935.5  491.47
  4941.9  491.93  4949.7  490.87  4957.1  490.55  4963.9  489.45  4970.7  487.84
  4984.9  487.37  4989.3  486.47  4992.0  485.97  4995.3  486.47  4999.0  487.00
  5006.4  487.04  5027.4  488.11  5034.8  490.94  5041.6  491.26  5049.0  492.99
  5069.0  493.31  5081.3  493.64  5112.5  494.29  5207.9  494.14  5269.3  493.74
#Mann=8,-1,0
  4717.3    0.05       0  4930.0     0.1       0  4941.9    0.16       0
  4989.3    0.07       0  4995.3    0.16       0  5069.0    0.05       0
  5081.3     0.1       0  5207.9    0.05       0
Bank Sta=4989.3,4995.3
Exp/Cntr=0.3,0.1

Type RM Length L Ch R = 1,5168,326,326,326
BEGIN DESCRIPTION:
UNT0673 IN SAND CR 9.0
END DESCRIPTION:
XS GIS Cut Line= 2
      3566330.77     10549138.55      3565725.54     10549554.17
#Sta/Elev= 30
  4580.7  494.01  4703.7  492.51  4718.6  491.62  4733.5  491.33  4871.2  489.31
  4897.9  489.19  4912.8  488.47  4948.7  488.00  4955.1  486.51  4963.6  484.00
  4969.6  483.09  4975.5  483.05  4978.2  482.55  4981.5  483.05  4984.5  483.62
  4999.4  483.22  5005.5  483.53  5035.3  483.31  5052.9  483.61  5064.3  484.50
  5071.2  487.39  5077.2  487.95  5086.1  489.96  5092.1  490.32  5100.7  490.37
  5107.0  490.02  5142.9  490.96  5258.4  492.35  5286.3  493.10  5314.9  492.84
#Mann=5,-1,0
  4580.7    0.05       0  4871.2    0.16       0  4975.5    0.07       0
  4981.5    0.16       0  5052.9    0.05       0
Bank Sta=4975.5,4981.5
Exp/Cntr=0.3,0.1

Type RM Length L Ch R = 1,4842,635,635,635
BEGIN DESCRIPTION:
UNT0673 IN SAND CR 8.1
END DESCRIPTION:
XS GIS Cut Line= 3
      3566226.54     10548839.12      3565877.62     10549117.74
      3565477.24     10549286.73
#Sta/Elev= 30
  4624.9  491.85  4665.8  491.16  4686.6  491.26  4729.8  489.96  4872.3  487.27
  4907.6  486.79  4914.0  487.08  4922.0  486.41  4929.8  486.43  4936.4  485.47
  4942.8  485.82  4957.2  483.21  4997.4  480.58  5000.2  480.08  5003.4  480.58
  5021.2  481.32  5050.1  485.57  5056.5  485.79  5064.5  486.68  5088.3  487.65
  5094.0  487.11  5099.4  487.41  5117.7  486.81  5146.8  487.14  5153.4  487.60
  5219.6  488.35  5252.5  488.48  5329.1  489.93  5370.5  490.10  5506.0  491.80
#Mann=5,-1,0
  4624.9    0.05       0  4929.8    0.16       0  4997.4    0.07       0
  5003.4    0.16       0  5219.6    0.05       0
Bank Sta=4997.4,5003.4
Exp/Cntr=0.3,0.1

Type RM Length L Ch R = 1,4207,672,672,672
BEGIN DESCRIPTION:
UNT0673 IN SAND CR 8.0
END DESCRIPTION:
XS GIS Cut Line= 3
      3566031.79     10548667.22      3565828.66     10548547.43
      3565313.02     10548771.40
#Sta/Elev= 30
  4620.4  487.60  4636.7  487.18  4680.6  486.19  4815.0  483.04  4856.2  482.62
  4861.0  482.25  4874.1  480.95  4879.5  481.15  4885.2  479.30  4896.1  477.48
  4905.4  476.95  4908.2  476.45  4911.4  476.95  4926.4  477.78  4931.9  477.62
  4970.7  478.17  4978.8  478.51  5002.2  477.37  5007.7  478.14  5016.0  478.57
  5025.7  478.47  5031.2  479.61  5048.7  481.01  5054.6  482.09  5073.5  482.37
  5083.5  483.13  5206.2  484.36  5258.6  485.42  5404.8  486.74  5418.4  487.20
#Mann=8,-1,0
  4620.4     0.1       0  4636.7    0.05       0  4680.6     0.1       0
  4861.0    0.05       0  4905.4    0.07       0  4911.4    0.05       0
  4970.7     0.1       0  5073.5    0.05       0
Bank Sta=4905.4,4911.4
Exp/Cntr=0.3,0.1

Type RM Length L Ch R = 1,3535,310,310,310
BEGIN DESCRIPTION:
UNT0673 IN SAND CR 6.0
END DESCRIPTION:
XS GIS Cut Line= 2
      3566048.47     10547865.91      3565185.52     10548099.85
#Sta/Elev= 30
  4469.7  485.81  4471.8  485.40  4551.5  484.30  4559.2  483.75  4673.2  481.07
  4700.4  479.96  4756.0  478.93  4849.3  475.51  4870.0  476.30  4880.4  477.49
  4921.8  477.53  4929.1  476.96  4934.2  477.33  4942.5  476.27  4963.3  475.96
  4968.9  475.02  4974.1  475.45  4984.0  474.07  5005.7  473.01  5008.5  472.51
  5011.7  473.01  5025.4  473.98  5043.4  476.23  5048.6  475.80  5066.9  477.68
  5088.4  478.20  5108.3  477.97  5311.8  480.27  5317.0  480.62  5363.8  480.03
#Mann=3,-1,0
  4469.7    0.05       0  5005.7    0.03       0  5011.7    0.05       0
Bank Sta=5005.7,5011.7
Exp/Cntr=0.3,0.1

Type RM Length L Ch R = 1,3225,24,24,24
BEGIN DESCRIPTION:
UNT0673 IN SAND CR 4.3
END DESCRIPTION:
XS GIS Cut Line= 5
      3566006.81     10547578.15      3565637.86     10547693.18
      3565546.72     10547710.54      3565251.58     10547944.91
      3565195.92     10548014.96
#Sta/Elev= 30
  4561.3  482.65  4671.0  482.57  4688.7  481.53  4775.7  479.58  4823.9  478.01
  4856.4  477.31  4901.4  476.92  4911.9  476.36  4921.5  475.22  4926.7  475.84
  4932.8  474.78  4962.5  473.83  4967.6  473.14  5014.7  473.91  5019.8  473.28
  5032.1  473.10  5034.8  472.60  5038.1  473.10  5040.3  473.83  5045.5  473.83
  5051.6  473.26  5066.0  475.41  5072.4  474.94  5086.8  475.84  5173.4  475.67
  5307.9  476.49  5322.4  476.18  5457.4  477.45  5471.8  477.99  5506.9  477.93
#Mann=3,-1,0
  4561.3    0.05       0  5032.1    0.03       0  5038.1    0.05       0
Bank Sta=5032.1,5038.1
Exp/Cntr=0.3,0.1

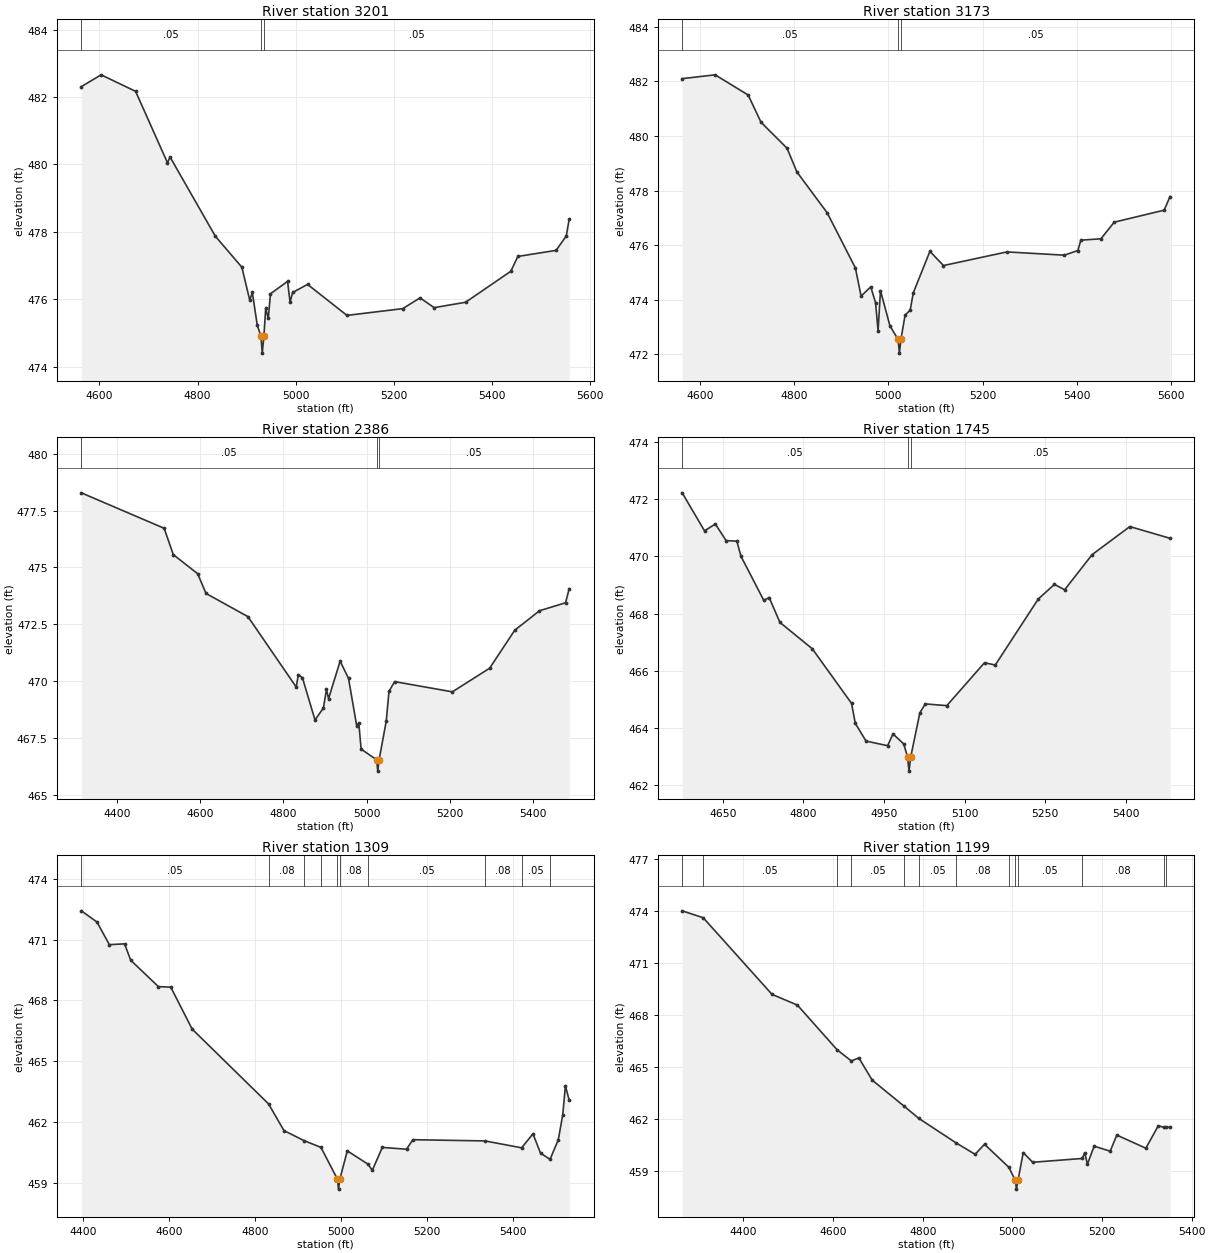
Type RM Length L Ch R = 1,3201,28,28,28
BEGIN DESCRIPTION:
UNT0673 IN SAND CR 4.1
END DESCRIPTION:
XS GIS Cut Line= 5
      3566004.66     10547554.27      3565635.69     10547669.31
      3565544.55     10547686.67      3565249.41     10547921.04
      3565159.62     10548026.82
#Sta/Elev= 30
  4563.0  482.31  4603.4  482.66  4673.7  482.17  4738.7  480.05  4744.0  480.22
  4836.3  477.87  4890.4  476.95  4906.5  475.97  4911.8  476.20  4921.8  475.23
  4929.3  474.90  4932.0  474.40  4935.3  474.90  4939.0  475.73  4944.3  475.43
  4948.7  476.16  4983.6  476.53  4988.7  475.91  4993.9  476.20  5024.4  476.44
  5104.7  475.52  5218.4  475.72  5253.7  476.04  5282.5  475.75  5346.6  475.91
  5438.9  476.83  5453.2  477.27  5531.2  477.45  5552.0  477.88  5557.9  478.38
#Mann=3,-1,0
  4563.0    0.05       0  4929.3    0.03       0  4935.3    0.05       0
Bank Sta=4929.3,4935.3
Exp/Cntr=0.3,0.1

Type RM Length L Ch R = 1,3173,787,787,787
BEGIN DESCRIPTION:
UNT0673 IN SAND CR 4.2
END DESCRIPTION:
XS GIS Cut Line= 5
      3566004.60     10547526.08      3565635.69     10547641.09
      3565544.55     10547658.45      3565249.41     10547892.83
      3565125.77     10548022.85
#Sta/Elev= 30
  4562.5  482.10  4632.4  482.24  4702.6  481.50  4729.9  480.50  4785.1  479.55
  4806.0  478.68  4870.4  477.18  4930.2  475.16  4942.2  474.13  4962.7  474.47
  4972.9  473.89  4978.3  472.86  4983.4  474.33  5003.5  473.04  5020.8  472.54
  5023.6  472.04  5026.8  472.54  5035.6  473.43  5046.5  473.62  5053.0  474.25
  5088.3  475.77  5117.1  475.25  5251.7  475.75  5373.5  475.63  5402.3  475.80
  5408.7  476.18  5451.2  476.23  5479.5  476.84  5585.5  477.28  5598.0  477.78
#Mann=3,-1,0
  4562.5    0.05       0  5020.8    0.03       0  5026.8    0.05       0
Bank Sta=5020.8,5026.8
Exp/Cntr=0.3,0.1

Type RM Length L Ch R = 1,2386,641,641,641
BEGIN DESCRIPTION:
UNT0673 IN SAND CR 4.0
END DESCRIPTION:
XS GIS Cut Line= 3
      3565859.73     10547145.82      3564974.30     10547026.46
      3564716.57     10547139.08
#Sta/Elev= 30
  4313.2  478.28  4512.6  476.72  4534.7  475.56  4593.3  474.72  4613.5  473.85
  4714.4  472.83  4830.7  469.73  4835.8  470.28  4845.6  470.14  4875.9  468.28
  4896.1  468.81  4903.5  469.63  4908.5  469.22  4936.4  470.87  4956.6  470.11
  4976.2  468.03  4981.3  468.15  4986.9  467.00  5024.2  466.53  5027.0  466.03
  5030.2  466.53  5047.4  468.23  5054.0  469.54  5067.6  469.97  5206.6  469.52
  5296.3  470.56  5356.7  472.23  5416.4  473.09  5479.1  473.44  5487.9  474.06
#Mann=3,-1,0
  4313.2    0.05       0  5024.2    0.03       0  5030.2    0.05       0
Bank Sta=5024.2,5030.2
Exp/Cntr=0.3,0.1

Type RM Length L Ch R = 1,1745,436,436,436
BEGIN DESCRIPTION:
UNT0673 IN SAND CR 4.01
END DESCRIPTION:
XS GIS Cut Line= 2
      3565263.69     10546581.07      3564357.41     10546626.21
#Sta/Elev= 30
  4574.6  472.22  4616.2  470.89  4636.3  471.13  4656.3  470.55  4676.3  470.53
  4684.0  470.00  4726.4  468.46  4736.4  468.56  4756.4  467.69  4816.5  466.77
  4889.6  464.86  4896.6  464.16  4916.6  463.54  4956.7  463.38  4966.7  463.79
  4986.7  463.44  4993.7  462.99  4996.5  462.49  4999.7  462.99  5016.7  464.53
  5026.7  464.84  5066.8  464.78  5136.9  466.28  5156.9  466.20  5237.0  468.51
  5267.0  469.02  5285.9  468.83  5337.1  470.06  5407.2  471.04  5482.0  470.63
#Mann=3,-1,0
  4574.6    0.05       0  4993.7    0.03       0  4999.7    0.05       0
Bank Sta=4993.7,4999.7
Exp/Cntr=0.3,0.1

Type RM Length L Ch R = 1,1309,110,110,110
BEGIN DESCRIPTION:
UNT0673 IN SAND CR 3.1
END DESCRIPTION:
XS GIS Cut Line= 5
      3565266.77     10546558.20      3564811.94     10546201.21
      3564755.52     10546207.72      3564430.00     10545969.00
      3564337.61     10545944.66
#Sta/Elev= 30
  4396.2  472.42  4432.5  471.87  4461.4  470.75  4496.7  470.79  4511.1  469.98
  4575.3  468.68  4604.2  468.65  4653.9  466.58  4831.4  462.89  4867.3  461.57
  4914.5  461.07  4953.3  460.74  4991.4  459.18  4994.1  458.68  4997.4  459.18
  5014.5  460.57  5062.1  459.92  5072.8  459.61  5095.9  460.74  5152.3  460.65
  5167.0  461.12  5334.7  461.06  5419.7  460.72  5446.2  461.41  5463.7  460.46
  5485.9  460.15  5505.1  461.12  5515.4  462.35  5521.6  463.78  5530.4  463.07
#Mann=10,-1,0
  4396.2    0.05       0  4831.4    0.08       0  4914.5    0.05       0
  4953.3    0.08       0  4991.4    0.07       0  4997.4    0.08       0
  5062.1    0.05       0  5334.7    0.08       0  5419.7    0.05       0
  5485.9    0.08       0
Bank Sta=4991.4,4997.4
Exp/Cntr=0.3,0.1

Type RM Length L Ch R = 1,1199,100,100,100
BEGIN DESCRIPTION:
UNT0673 IN SAND CR 3.0
END DESCRIPTION:
XS GIS Cut Line= 2
      3565331.84     10546540.81      3564437.74     10545920.15
#Sta/Elev= 30
  4263.4  474.02  4310.4  473.62  4463.8  469.20  4520.5  468.58  4609.1  466.00
  4640.7  465.36  4657.6  465.53  4687.3  464.25  4757.9  462.76  4791.4  462.04
  4875.0  460.62  4916.9  459.97  4937.9  460.55  4992.2  459.22  5006.5  458.46
  5009.2  457.96  5012.5  458.46  5024.3  460.07  5045.3  459.51  5156.2  459.73
  5161.4  460.06  5167.5  459.40  5182.4  460.44  5218.2  460.15  5233.0  461.08
  5297.8  460.32  5325.6  461.62  5338.5  461.52  5343.7  461.52  5351.8  461.53
#Mann=13,-1,0
  4263.4    0.08       0  4310.4    0.05       0  4609.1    0.08       0
  4640.7    0.05       0  4757.9    0.08       0  4791.4    0.05       0
  4875.0    0.08       0  4992.2    0.05       0  5006.5    0.04       0
  5012.5    0.05       0  5156.2    0.08       0  5338.5    0.05       0
  5343.7    0.08       0
Bank Sta=5006.5,5012.5
Exp/Cntr=0.3,0.1

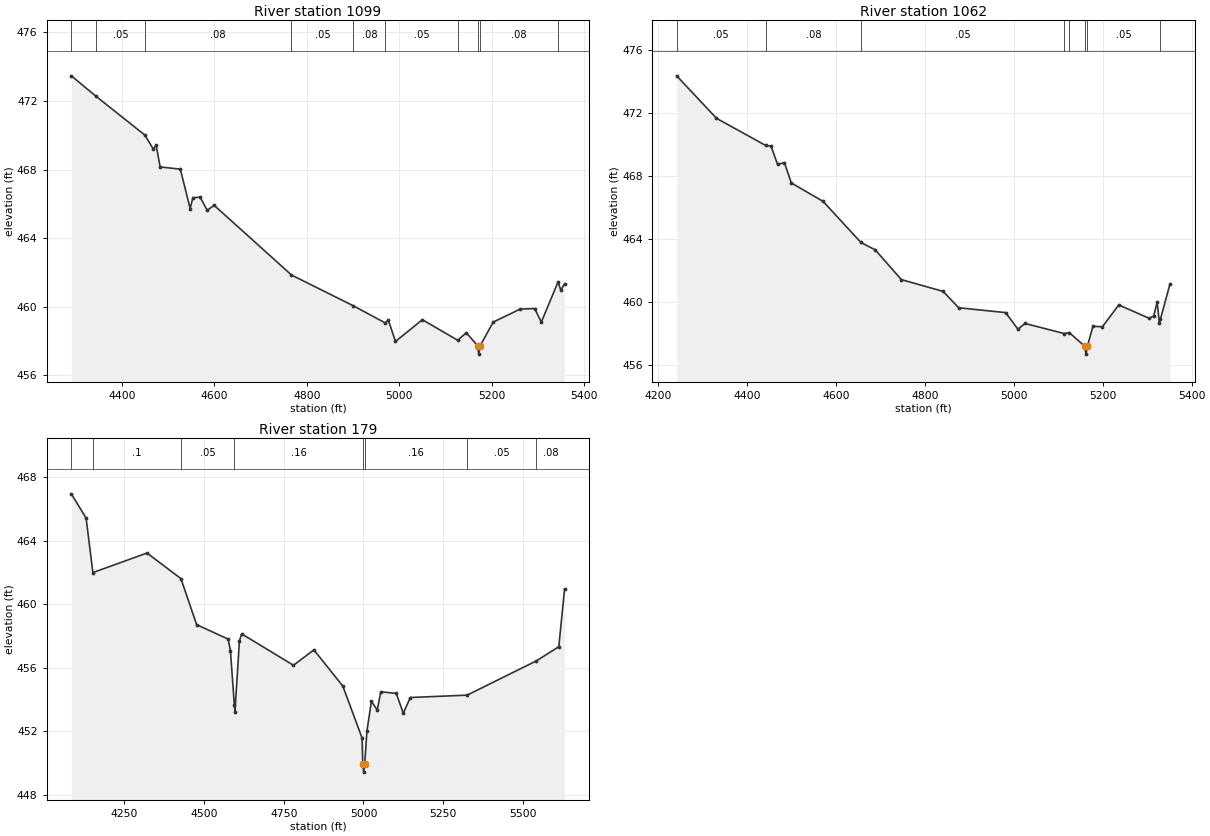
Type RM Length L Ch R = 1,1099,37,37,37
BEGIN DESCRIPTION:
UNT0673 IN SAND CR 2.0
END DESCRIPTION:
XS GIS Cut Line= 3
      3565356.65     10546390.01      3564512.46     10545880.03
      3564432.66     10545864.37
#Sta/Elev= 30
  4290.3  473.47  4343.5  472.28  4449.5  470.01  4467.9  469.18  4473.8  469.43
  4482.5  468.15  4526.2  468.02  4547.5  465.72  4553.3  466.35  4568.9  466.39
  4584.4  465.62  4599.4  465.91  4766.8  461.84  4900.9  460.04  4969.8  459.04
  4976.4  459.21  4991.9  457.96  5050.1  459.23  5126.6  458.03  5145.2  458.47
  5169.4  457.72  5172.1  457.22  5175.4  457.72  5203.4  459.09  5261.6  459.85
  5293.2  459.88  5307.5  459.09  5343.7  461.43  5349.7  460.96  5357.9  461.33
#Mann=10,-1,0
  4290.3    0.08       0  4343.5    0.05       0  4449.5    0.08       0
  4766.8    0.05       0  4900.9    0.08       0  4969.8    0.05       0
  5126.6    0.08       0  5169.4    0.03       0  5175.4    0.08       0
  5343.7    0.08       0
Bank Sta=5169.4,5175.4
Exp/Cntr=0.3,0.1

Type RM Length L Ch R = 1,1062,883,883,883
BEGIN DESCRIPTION:
UNT0673 IN SAND CR 2.1
END DESCRIPTION:
XS GIS Cut Line= 5
      3565393.16     10546363.61      3564776.47     10545985.99
      3564719.18     10545988.59      3564517.35     10545864.89
      3564425.75     10545853.44
#Sta/Elev= 30
  4241.6  474.38  4331.2  471.68  4441.9  469.95  4453.9  469.91  4468.5  468.75
  4484.0  468.86  4499.4  467.57  4571.2  466.39  4656.1  463.78  4688.4  463.31
  4747.0  461.42  4840.9  460.67  4876.0  459.63  4981.6  459.32  5009.1  458.27
  5025.2  458.63  5113.2  457.99  5124.8  458.05  5159.5  457.18  5162.3  456.68
  5165.5  457.18  5177.9  458.45  5199.2  458.42  5236.0  459.81  5304.4  458.96
  5314.5  459.10  5322.4  459.98  5327.4  458.68  5329.6  458.89  5351.1  461.13
#Mann=8,-1,0
  4241.6    0.05       0  4441.9    0.08       0  4656.1    0.05       0
  5113.2    0.08       0  5124.8    0.05       0  5159.5    0.03       0
  5165.5    0.05       0  5329.6    0.08       0
Bank Sta=5159.5,5165.5
Exp/Cntr=0.3,0.1

Type RM Length L Ch R = 1,179,0,0,0
BEGIN DESCRIPTION:
UNT0673 IN SAND CR 1.0
END DESCRIPTION:
XS GIS Cut Line= 4
      3565351.48     10545967.77      3564807.20     10545392.24
      3564622.30     10545316.72      3564362.49     10545807.75
#Sta/Elev= 30
  4083.5  466.94  4129.9  465.41  4151.1  461.98  4320.9  463.21  4427.3  461.60
  4476.6  458.70  4575.3  457.79  4582.6  457.07  4594.8  453.66  4596.8  453.22
  4610.9  457.69  4617.8  458.12  4780.4  456.14  4844.4  457.11  4935.2  454.83
  4995.4  451.57  4997.8  449.91  5000.5  449.41  5003.8  449.91  5010.8  451.99
  5024.8  453.87  5043.2  453.32  5054.2  454.47  5102.9  454.37  5124.9  453.12
  5146.9  454.11  5325.2  454.26  5542.6  456.42  5612.7  457.31  5630.9  460.95
#Mann=8,-1,0
  4083.5    0.05       0  4151.1     0.1       0  4427.3    0.05       0
  4594.8    0.16       0  4997.8    0.07       0  5003.8    0.16       0
  5325.2    0.05       0  5542.6    0.08       0
Bank Sta=4997.8,5003.8
Exp/Cntr=0.3,0.1

Chan Stop Cuts=-1