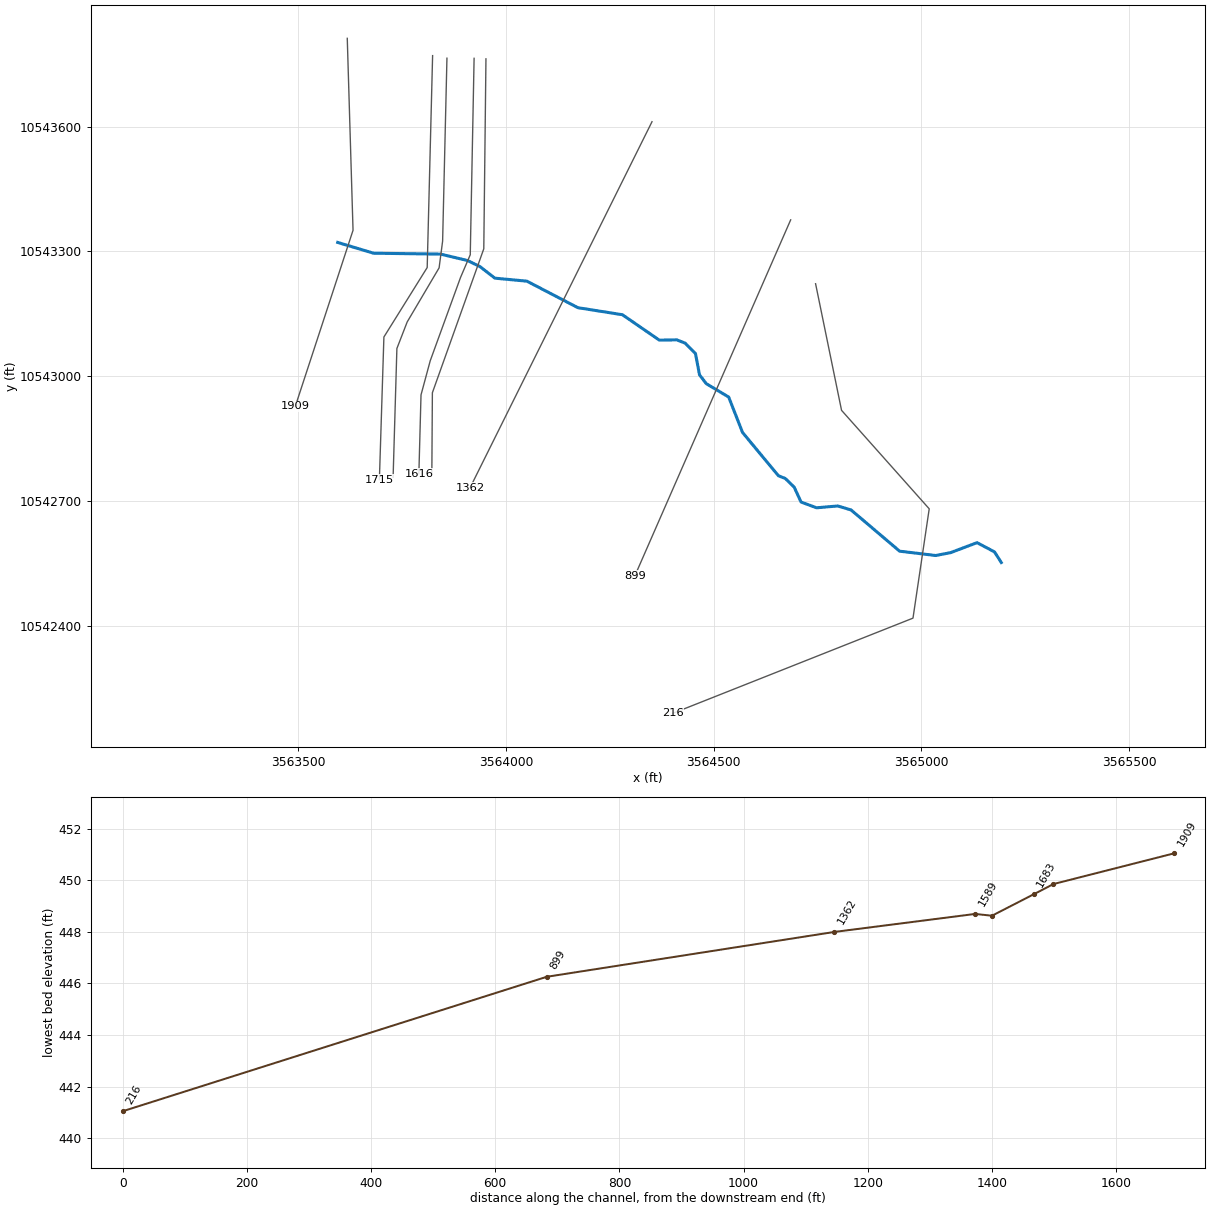
--- UNT0675 IN SAND CR.prj (project) ---

Proj Title=UNT0675 IN SAND CR Base Level Engineering
Current Plan=p01
Default Exp/Contr=0.3,0.1
English Units
Geom File=g01
Flow File=f01
Plan File=p01
BEGIN DESCRIPTION:
UNT0675 IN SAND CR
END DESCRIPTION:

--- UNT0675 IN SAND CR.p01 (plan) ---

Plan Title=Multiple Run
Short Identifier=Multiple
Geom File=g01
Flow File=f01
Subcritical Flow
K Sum by GR= 0
Std Step Tol= 0.01
Critical Tol= 0.01
Num of Std Step Trials= 20
Max Error Tol= 0.3
Flow Tol Ratio= 0.001
Split Flow NTrial= 30
Split Flow Tol= 0.02
Split Flow Ratio= 0.02
Log Output Level= 0
Friction Slope Method= 1
Unsteady Friction Slope Method= 2
Unsteady Bridges Friction Slope Method= 1
Parabolic Critical Depth
Global Vel Dist=  1 , 1 , 1
Global Log Level= 0
CheckData=True
Encroach Param= -1, 0, 0, 0
BEGIN DESCRIPTION:
Multiple Run
END DESCRIPTION:

--- UNT0675 IN SAND CR.f01 (steady flow) ---

Flow Title=Multiple
Number of Profiles=7
Profile Names=10-year,25-year,50-year,1pct_min,100-year,1pct_plu,500-year
River Rch & RM= UNT0675 IN SAND ,Reach-1,1909
     475     620     734     636     860    1163    1175
Boundary for River Rch & Prof#=UNT0675 IN SAND ,Reach-1,1
Up Type=0
Dn Type=3
Dn Slope=0.005
Boundary for River Rch & Prof#=UNT0675 IN SAND ,Reach-1,2
Up Type=0
Dn Type=3
Dn Slope=0.005
Boundary for River Rch & Prof#=UNT0675 IN SAND ,Reach-1,3
Up Type=0
Dn Type=3
Dn Slope=0.005
Boundary for River Rch & Prof#=UNT0675 IN SAND ,Reach-1,4
Up Type=0
Dn Type=3
Dn Slope=0.005
Boundary for River Rch & Prof#=UNT0675 IN SAND ,Reach-1,5
Up Type=0
Dn Type=3
Dn Slope=0.005
Boundary for River Rch & Prof#=UNT0675 IN SAND ,Reach-1,6
Up Type=0
Dn Type=3
Dn Slope=0.005
Boundary for River Rch & Prof#=UNT0675 IN SAND ,Reach-1,7
Up Type=0
Dn Type=3
Dn Slope=0.005

--- UNT0675 IN SAND CR.g01 (geometry) ---

Geom Title=Existing Conditions

River Reach=UNT0675 IN SAND ,Reach-1
Reach XY= 30
      3563595.48     10543321.74      3563681.85     10543295.77
      3563842.79     10543293.69      3563908.42     10543278.06
      3563937.94     10543263.43      3563973.73     10543235.75
      3564050.80     10543228.51      3564173.39     10543164.74
      3564280.51     10543147.78      3564369.33     10543086.68
      3564411.58     10543087.28      3564431.47     10543079.40
      3564456.33     10543054.30      3564466.08     10543003.13
      3564482.22     10542982.01      3564536.25     10542949.71
      3564569.58     10542864.48      3564655.95     10542760.31
      3564672.44     10542753.80      3564693.87     10542732.89
      3564710.36     10542697.16      3564747.57     10542683.24
      3564798.59     10542687.66      3564830.66     10542678.07
      3564947.52     10542578.87      3565034.33     10542568.45
      3565070.26     10542575.35      3565133.79     10542599.38
      3565175.74     10542577.15      3565192.11     10542551.64

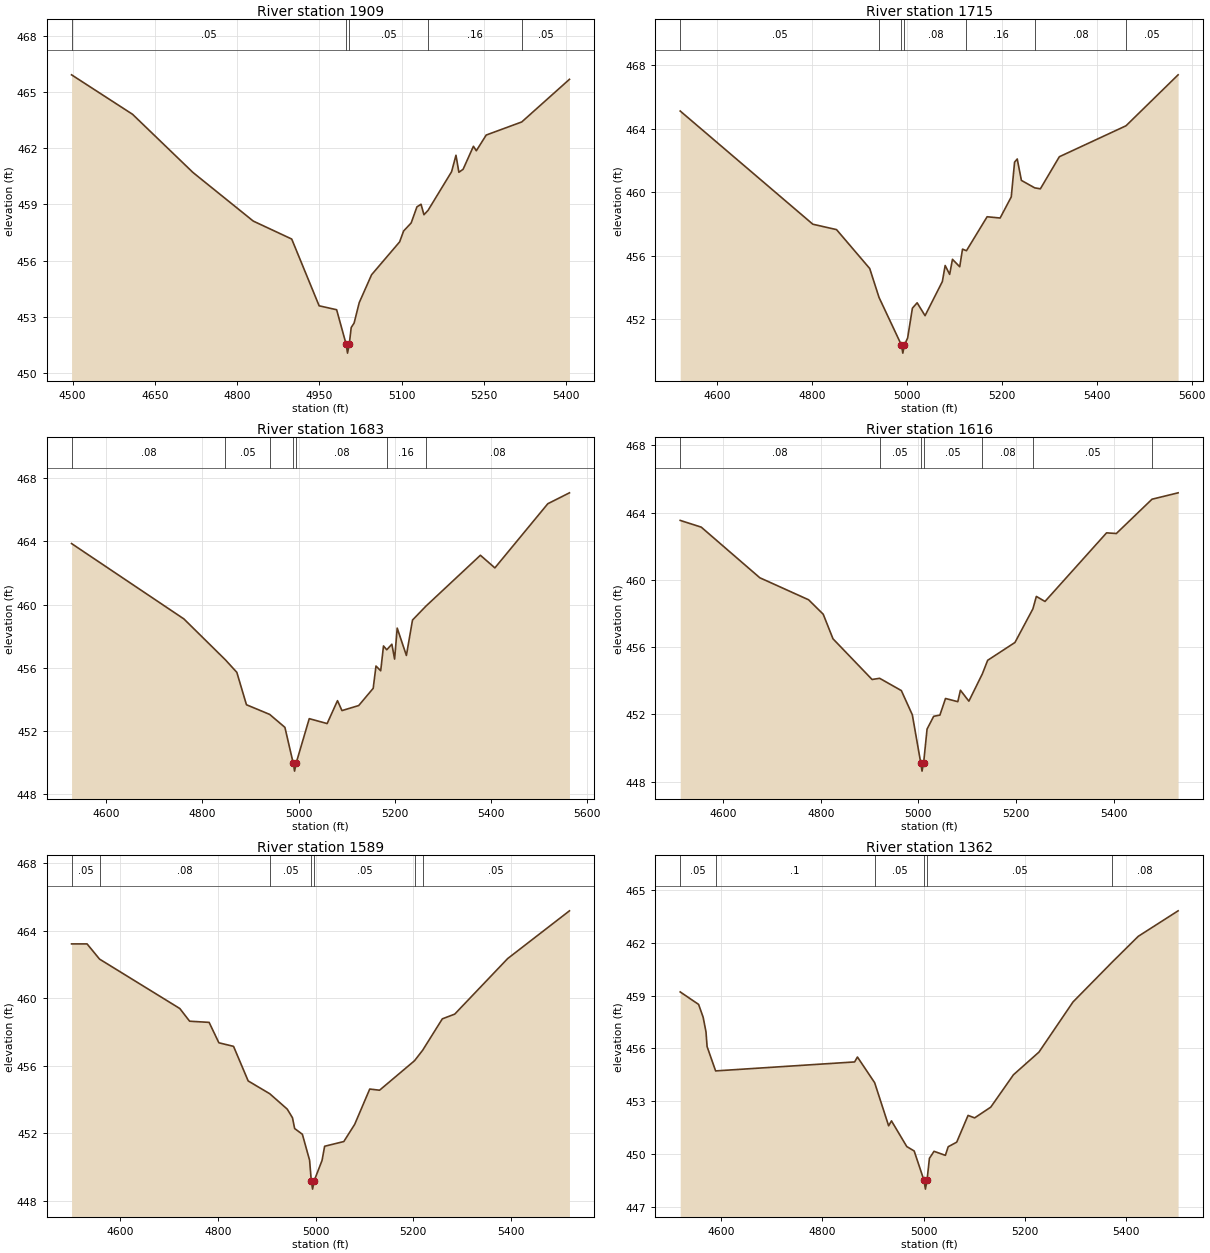
Type RM Length L Ch R = 1,1909,194,194,194
BEGIN DESCRIPTION:
UNT0675 IN SAND CR 1.5
END DESCRIPTION:
XS GIS Cut Line= 3
      3563618.51     10543812.81      3563632.40     10543351.02
      3563493.51     10542927.41
#Sta/Elev= 30
  4498.0  465.93  4609.2  463.82  4719.3  460.71  4829.3  458.11  4899.4  457.15
  4949.4  453.58  4981.3  453.37  4998.4  451.55  5001.2  451.05  5004.4  451.55
  5007.9  452.42  5013.2  452.66  5022.5  453.75  5045.0  455.24  5096.2  457.00
  5103.4  457.58  5117.2  458.01  5127.7  458.87  5135.2  459.01  5140.5  458.45
  5147.9  458.68  5190.9  460.75  5198.9  461.63  5204.2  460.72  5211.9  460.88
  5230.7  462.11  5236.0  461.87  5254.0  462.71  5318.8  463.41  5405.8  465.69
#Mann=5,-1,0
  4498.0    0.05       0  4998.4    0.03       0  5004.4    0.05       0
  5147.9    0.16       0  5318.8    0.05       0
Bank Sta=4998.4,5004.4
Exp/Cntr=0.3,0.1

Type RM Length L Ch R = 1,1715,32,32,32
BEGIN DESCRIPTION:
UNT0675 IN SAND CR 2.1
END DESCRIPTION:
XS GIS Cut Line= 4
      3563823.85     10543771.23      3563810.83     10543261.28
      3563706.66     10543094.18      3563695.81     10542751.28
#Sta/Elev= 30
  4521.4  465.11  4801.1  457.98  4851.1  457.64  4921.1  455.19  4940.7  453.37
  4988.1  450.36  4990.9  449.86  4994.1  450.36  5001.1  450.82  5011.1  452.69
  5021.1  453.03  5037.8  452.22  5074.3  454.37  5080.2  455.38  5089.7  454.82
  5095.6  455.77  5110.9  455.30  5116.8  456.41  5125.1  456.31  5168.7  458.45
  5196.1  458.37  5219.6  459.70  5226.6  461.89  5232.2  462.09  5241.0  460.74
  5269.1  460.27  5281.0  460.21  5321.0  462.23  5461.6  464.18  5571.5  467.39
#Mann=7,-1,0
  4521.4    0.05       0  4940.7    0.08       0  4988.1    0.07       0
  4994.1    0.08       0  5125.1    0.16       0  5269.1    0.08       0
  5461.6    0.05       0
Bank Sta=4988.1,4994.1
Exp/Cntr=0.3,0.1

Type RM Length L Ch R = 1,1683,67,67,67
BEGIN DESCRIPTION:
UNT0675 IN SAND CR 2.0
END DESCRIPTION:
XS GIS Cut Line= 6
      3563858.35     10543765.04      3563847.94     10543324.98
      3563839.47     10543260.52      3563762.65     10543130.32
      3563737.91     10543066.51      3563728.80     10542756.67
#Sta/Elev= 30
  4528.0  463.86  4761.5  459.09  4847.8  456.50  4871.5  455.71  4891.5  453.66
  4939.7  453.05  4971.4  452.23  4988.7  449.96  4991.5  449.46  4994.7  449.96
  5022.0  452.78  5059.2  452.47  5080.7  453.92  5090.0  453.29  5124.8  453.61
  5154.9  454.70  5160.7  456.11  5170.5  455.81  5176.3  457.38  5183.1  457.14
  5193.7  457.49  5199.4  456.55  5204.8  458.51  5223.9  456.78  5236.6  459.02
  5264.5  459.90  5377.7  463.12  5407.8  462.32  5517.8  466.38  5562.8  467.07
#Mann=7,-1,0
  4528.0    0.08       0  4847.8    0.05       0  4939.7    0.08       0
  4988.7    0.07       0  4994.7    0.08       0  5183.1    0.16       0
  5264.5    0.08       0
Bank Sta=4988.7,4994.7
Exp/Cntr=0.3,0.1

Type RM Length L Ch R = 1,1616,27,27,27
BEGIN DESCRIPTION:
UNT0675 IN SAND CR 1.0
END DESCRIPTION:
XS GIS Cut Line= 6
      3563923.68     10543764.73      3563914.45     10543292.10
      3563891.02     10543237.41      3563818.10     10543036.89
      3563795.96     10542954.86      3563790.80     10542765.08
#Sta/Elev= 30
  4512.0  463.54  4555.1  463.14  4675.1  460.13  4775.1  458.82  4805.1  457.96
  4825.1  456.50  4905.2  454.08  4920.7  454.15  4965.2  453.42  4987.7  451.98
  5004.9  449.13  5007.6  448.63  5010.9  449.13  5017.9  451.13  5031.5  451.89
  5044.2  451.96  5055.7  452.95  5080.9  452.76  5086.3  453.44  5103.6  452.79
  5131.3  454.42  5142.1  455.22  5198.0  456.28  5234.8  458.28  5241.9  459.02
  5259.6  458.72  5385.8  462.80  5405.8  462.76  5478.9  464.80  5532.4  465.18
#Mann=7,-1,0
  4512.0    0.08       0  4920.7    0.05       0  5004.9   0.035       0
  5010.9    0.05       0  5131.3    0.08       0  5234.8    0.05       0
  5478.9    0.08       0
Bank Sta=5004.9,5010.9
Exp/Cntr=0.3,0.1

Type RM Length L Ch R = 1,1589,227,227,227
BEGIN DESCRIPTION:
UNT0675 IN SAND CR 1.1
END DESCRIPTION:
XS GIS Cut Line= 4
      3563952.21     10543763.46      3563947.00     10543306.42
      3563823.31     10542960.07      3563822.01     10542765.02
#Sta/Elev= 30
  4500.1  463.23  4531.9  463.23  4557.4  462.33  4721.9  459.40  4741.9  458.65
  4781.9  458.58  4801.9  457.37  4831.9  457.16  4861.9  455.11  4906.2  454.35
  4941.9  453.44  4952.6  452.93  4957.1  452.29  4972.9  451.95  4987.7  450.41
  4991.1  449.20  4993.8  448.70  4997.1  449.20  5013.2  450.40  5018.5  451.24
  5057.8  451.52  5080.1  452.54  5110.9  454.63  5131.0  454.56  5202.7  456.31
  5219.3  456.93  5259.6  458.79  5285.0  459.07  5393.4  462.36  5520.0  465.19
#Mann=7,-1,0
  4500.1    0.05       0  4557.4    0.08       0  4906.2    0.05       0
  4991.1   0.035       0  4997.1    0.05       0  5202.7    0.08       0
  5219.3    0.05       0
Bank Sta=4991.1,4997.1
Exp/Cntr=0.3,0.1

Type RM Length L Ch R = 1,1362,463,463,463
BEGIN DESCRIPTION:
UNT0675 IN SAND CR 1.4
END DESCRIPTION:
XS GIS Cut Line= 2
      3564351.74     10543612.19      3563914.22     10542731.93
#Sta/Elev= 30
  4519.4  459.21  4555.7  458.50  4564.7  457.77  4570.3  456.94  4572.5  456.10
  4589.3  454.72  4863.7  455.23  4869.3  455.51  4903.3  454.05  4930.9  451.60
  4936.5  451.88  4966.7  450.42  4981.3  450.17  5000.7  448.50  5003.5  448.00
  5006.7  448.50  5011.4  449.75  5020.5  450.15  5042.9  449.92  5048.5  450.41
  5065.3  450.67  5087.7  452.19  5100.7  452.05  5132.5  452.66  5177.3  454.50
  5227.7  455.79  5294.9  458.64  5372.1  460.90  5423.7  462.37  5502.4  463.82
#Mann=6,-1,0
  4519.4    0.05       0  4589.3     0.1       0  4903.3    0.05       0
  5000.7    0.03       0  5006.7    0.05       0  5372.1    0.08       0
Bank Sta=5000.7,5006.7
Exp/Cntr=0.3,0.1

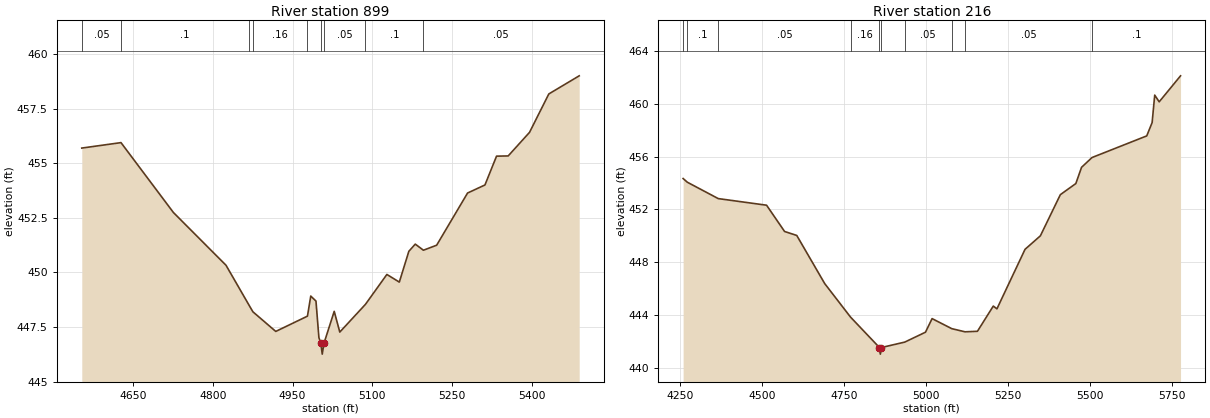
Type RM Length L Ch R = 1,899,683,683,683
BEGIN DESCRIPTION:
UNT0675 IN SAND CR 1.3
END DESCRIPTION:
XS GIS Cut Line= 2
      3564685.40     10543376.04      3564310.42     10542519.31
#Sta/Elev= 30
  4553.8  455.70  4627.5  455.95  4726.0  452.75  4825.0  450.33  4868.8  448.48
  4875.5  448.20  4918.5  447.30  4978.1  448.00  4984.3  448.92  4994.1  448.69
  4999.6  447.02  5003.2  446.76  5005.9  446.26  5009.2  446.76  5028.4  448.22
  5038.9  447.27  5087.1  448.54  5127.4  449.91  5150.8  449.56  5168.7  450.97
  5180.8  451.30  5196.1  451.02  5221.0  451.25  5279.1  453.64  5311.8  454.01
  5333.6  455.33  5355.5  455.34  5395.6  456.42  5431.9  458.18  5489.0  459.01
#Mann=9,-1,0
  4553.8    0.05       0  4627.5     0.1       0  4868.8    0.05       0
  4875.5    0.16       0  4978.1    0.05       0  5003.2    0.03       0
  5009.2    0.05       0  5087.1     0.1       0  5196.1    0.05       0
Bank Sta=5003.2,5009.2
Exp/Cntr=0.3,0.1

Type RM Length L Ch R = 1,216,0,0,0
BEGIN DESCRIPTION:
UNT0675 IN SAND CR 1.2
END DESCRIPTION:
XS GIS Cut Line= 5
      3564745.32     10543222.39      3564807.81     10542917.75
      3565018.75     10542680.77      3564979.69     10542417.75
      3564401.60     10542188.60
#Sta/Elev= 30
  4259.7  454.34  4272.6  454.06  4366.8  452.82  4514.0  452.32  4568.9  450.33
  4606.0  450.03  4691.3  446.38  4770.1  443.84  4858.0  441.54  4860.8  441.04
  4864.0  441.54  4935.1  441.95  4998.3  442.70  5018.5  443.73  5078.4  442.97
  5119.0  442.73  5156.7  442.77  5205.0  444.68  5216.1  444.47  5301.8  448.98
  5348.5  450.00  5409.4  453.12  5456.6  453.96  5474.0  455.19  5505.8  455.93
  5672.7  457.57  5689.1  458.58  5697.0  460.66  5710.6  460.15  5775.7  462.12
#Mann=10,-1,0
  4259.7    0.05       0  4272.6     0.1       0  4366.8    0.05       0
  4770.1    0.16       0  4858.0    0.03       0  4864.0    0.16       0
  4935.1    0.05       0  5078.4    0.16       0  5119.0    0.05       0
  5505.8     0.1       0
Bank Sta=4858,4864
Exp/Cntr=0.3,0.1

Chan Stop Cuts=-1