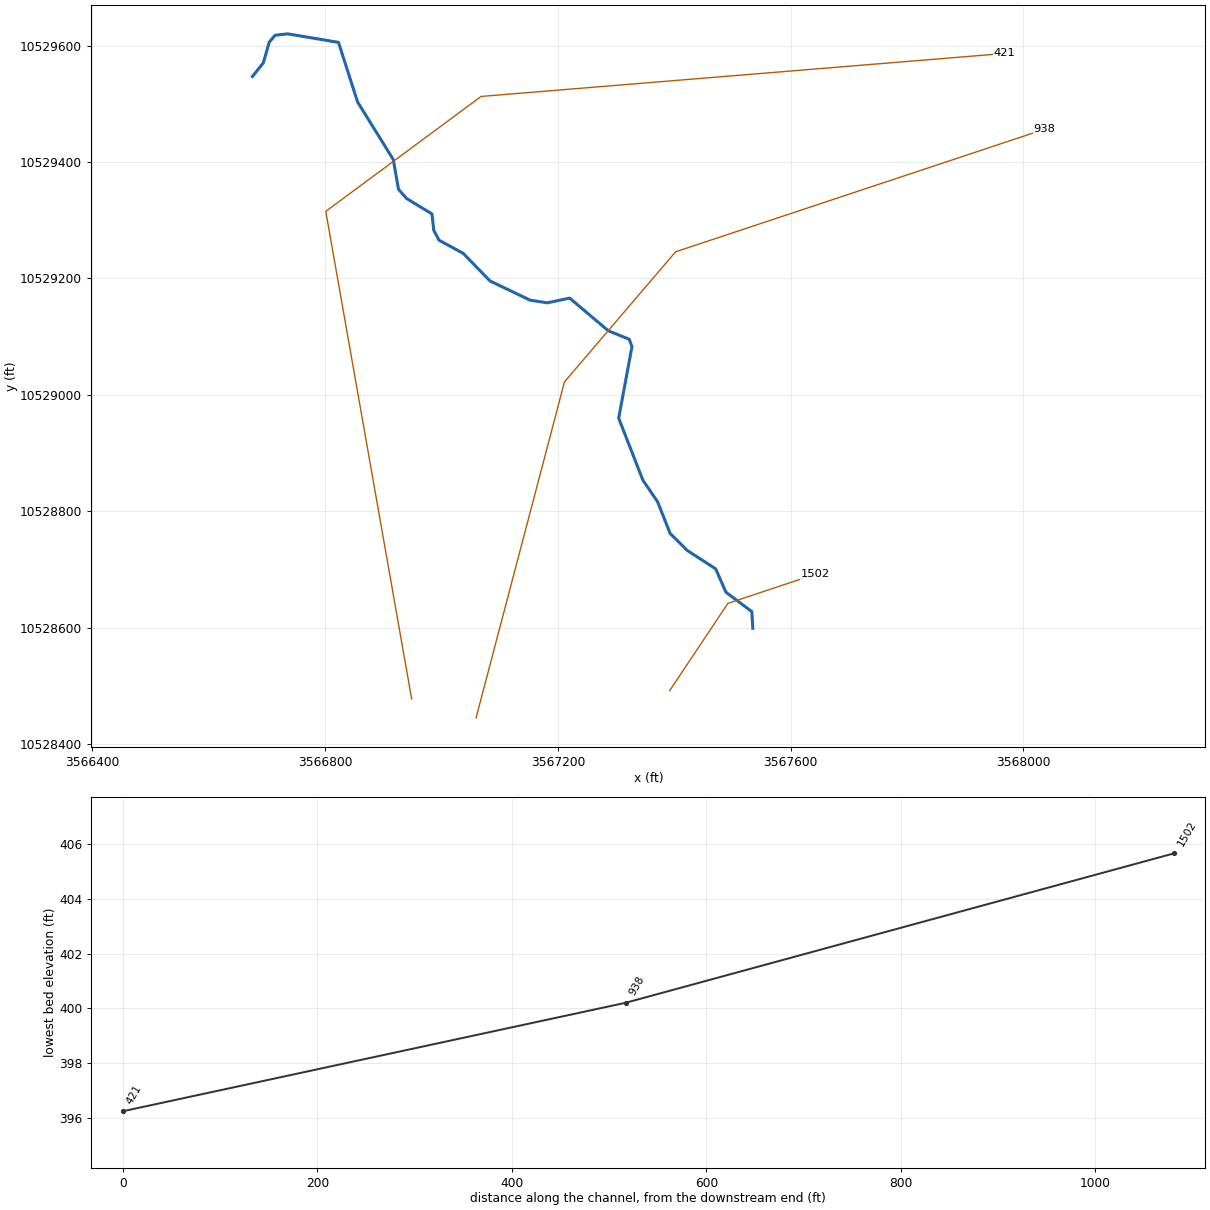
--- UNT0678 IN SAND CR.prj (project) ---

Proj Title=UNT0678 IN SAND CR Base Level Engineering
Current Plan=p01
Default Exp/Contr=0.3,0.1
English Units
Geom File=g01
Flow File=f01
Plan File=p01
BEGIN DESCRIPTION:
UNT0678 IN SAND CR
END DESCRIPTION:

--- UNT0678 IN SAND CR.p01 (plan) ---

Plan Title=Multiple Run
Short Identifier=Multiple
Geom File=g01
Flow File=f01
Subcritical Flow
K Sum by GR= 0
Std Step Tol= 0.01
Critical Tol= 0.01
Num of Std Step Trials= 20
Max Error Tol= 0.3
Flow Tol Ratio= 0.001
Split Flow NTrial= 30
Split Flow Tol= 0.02
Split Flow Ratio= 0.02
Log Output Level= 0
Friction Slope Method= 1
Unsteady Friction Slope Method= 2
Unsteady Bridges Friction Slope Method= 1
Parabolic Critical Depth
Global Vel Dist=  1 , 1 , 1
Global Log Level= 0
CheckData=True
Encroach Param= -1, 0, 0, 0
BEGIN DESCRIPTION:
Multiple Run
END DESCRIPTION:

--- UNT0678 IN SAND CR.f01 (steady flow) ---

Flow Title=Multiple
Number of Profiles=7
Profile Names=10-year,25-year,50-year,1pct_min,100-year,1pct_plu,500-year
River Rch & RM= UNT0678 IN SAND ,Reach-1,1502
     645     867    1048     926    1253    1694    1782
Boundary for River Rch & Prof#=UNT0678 IN SAND ,Reach-1,1
Up Type=0
Dn Type=3
Dn Slope=0.005
Boundary for River Rch & Prof#=UNT0678 IN SAND ,Reach-1,2
Up Type=0
Dn Type=3
Dn Slope=0.005
Boundary for River Rch & Prof#=UNT0678 IN SAND ,Reach-1,3
Up Type=0
Dn Type=3
Dn Slope=0.005
Boundary for River Rch & Prof#=UNT0678 IN SAND ,Reach-1,4
Up Type=0
Dn Type=3
Dn Slope=0.005
Boundary for River Rch & Prof#=UNT0678 IN SAND ,Reach-1,5
Up Type=0
Dn Type=3
Dn Slope=0.005
Boundary for River Rch & Prof#=UNT0678 IN SAND ,Reach-1,6
Up Type=0
Dn Type=3
Dn Slope=0.005
Boundary for River Rch & Prof#=UNT0678 IN SAND ,Reach-1,7
Up Type=0
Dn Type=3
Dn Slope=0.005

--- UNT0678 IN SAND CR.g01 (geometry) ---

Geom Title=Existing Conditions

River Reach=UNT0678 IN SAND ,Reach-1
Reach XY= 30
      3567534.90     10528598.85      3567533.25     10528627.49
      3567488.86     10528660.71      3567471.07     10528701.04
      3567422.37     10528732.53      3567392.88     10528761.81
      3567371.30     10528816.29      3567346.09     10528853.30
      3567304.43     10528959.83      3567327.31     10529082.71
      3567322.71     10529095.39      3567286.63     10529110.10
      3567220.29     10529166.15      3567182.11     10529158.08
      3567152.62     10529162.51      3567083.63     10529195.47
      3567037.35     10529243.07      3566995.90     10529265.59
      3566986.76     10529282.61      3566983.67     10529310.80
      3566939.99     10529337.31      3566926.12     10529353.26
      3566917.21     10529404.25      3566855.83     10529503.21
      3566823.09     10529605.55      3566735.92     10529620.19
      3566714.30     10529617.84      3566704.10     10529606.03
      3566693.90     10529570.27      3566675.15     10529546.84

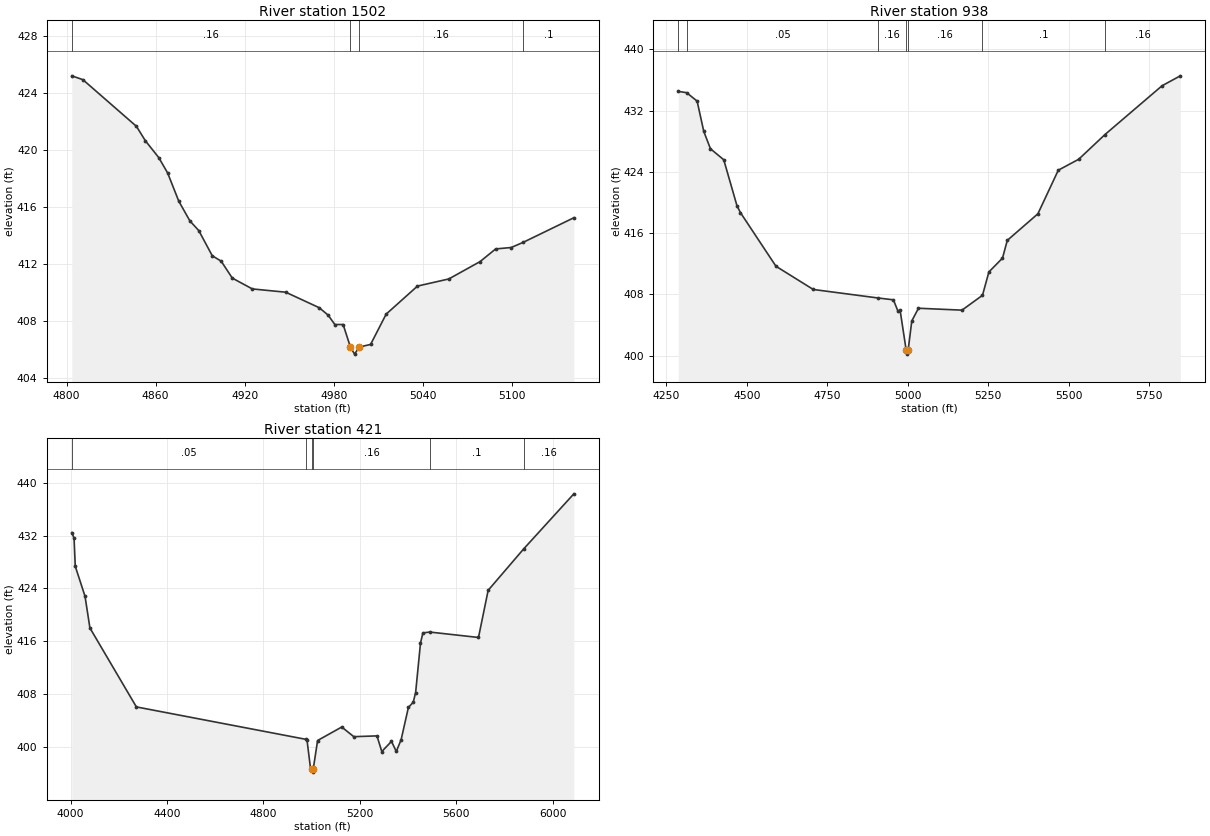
Type RM Length L Ch R = 1,1502,564,564,564
BEGIN DESCRIPTION:
UNT0678 IN SAND CR 3.0
END DESCRIPTION:
XS GIS Cut Line= 3
      3567392.10     10528491.64      3567492.11     10528641.64
      3567642.11     10528691.64
#Sta/Elev= 30
  4803.5  425.22  4811.0  424.95  4847.1  421.67  4853.1  420.66  4862.1  419.48
  4868.1  418.40  4875.6  416.42  4883.1  415.03  4889.1  414.35  4898.2  412.58
  4904.2  412.20  4911.7  411.01  4925.2  410.25  4947.7  410.02  4970.3  408.93
  4976.3  408.41  4980.8  407.75  4986.4  407.75  4991.3  406.17  4994.1  405.67
  4997.3  406.17  5004.9  406.35  5015.4  408.48  5036.5  410.45  5057.6  410.95
  5078.7  412.17  5089.2  413.06  5099.7  413.16  5107.7  413.52  5141.9  415.25
#Mann=4,-1,0
  4803.5    0.16       0  4991.3    0.07       0  4997.3    0.16       0
  5107.7     0.1       0
Bank Sta=4991.3,4997.3
Exp/Cntr=0.3,0.1

Type RM Length L Ch R = 1,938,517,517,517
BEGIN DESCRIPTION:
UNT0678 IN SAND CR 2.0
END DESCRIPTION:
XS GIS Cut Line= 4
      3567059.46     10528444.97      3567211.36     10529022.21
      3567402.34     10529245.74      3568035.99     10529456.23
#Sta/Elev= 30
  4287.4  434.50  4313.5  434.33  4346.0  433.23  4366.7  429.27  4387.4  427.01
  4428.7  425.57  4469.8  419.56  4480.4  418.68  4590.8  411.67  4706.6  408.64
  4907.5  407.53  4955.3  407.29  4969.6  405.80  4976.2  405.92  4995.1  400.70
  4997.9  400.20  5001.1  400.70  5012.4  404.53  5033.2  406.19  5168.3  405.94
  5231.9  407.88  5251.8  410.93  5294.0  412.73  5308.9  415.05  5403.9  418.52
  5467.2  424.21  5530.6  425.64  5612.3  428.87  5789.2  435.23  5846.0  436.53
#Mann=7,-1,0
  4287.4     0.1       0  4313.5    0.05       0  4907.5    0.16       0
  4995.1    0.07       0  5001.1    0.16       0  5231.9     0.1       0
  5612.3    0.16       0
Bank Sta=4995.1,5001.1
Exp/Cntr=0.3,0.1

Type RM Length L Ch R = 1,421,0,0,0
BEGIN DESCRIPTION:
UNT0678 IN SAND CR 1.0
END DESCRIPTION:
XS GIS Cut Line= 4
      3566948.78     10528477.51      3566801.21     10529315.18
      3567068.13     10529512.67      3567966.60     10529586.45
#Sta/Elev= 30
  4004.5  432.45  4014.0  431.60  4019.0  427.36  4059.5  422.82  4079.8  418.03
  4272.7  406.09  4977.7  401.18  4981.0  401.07  4995.6  396.78  5001.0  396.73
  5003.8  396.23  5007.0  396.73  5024.9  401.01  5125.1  403.05  5175.2  401.59
  5271.4  401.71  5291.4  399.34  5331.6  400.88  5351.6  399.35  5371.7  401.14
  5401.8  406.01  5421.9  406.80  5431.9  408.27  5452.0  415.73  5462.0  417.28
  5490.4  417.41  5692.8  416.59  5732.9  423.72  5879.8  429.96  6088.6  438.31
#Mann=6,-1,0
  4004.5    0.05       0  4977.7    0.16       0  5001.0    0.07       0
  5007.0    0.16       0  5490.4     0.1       0  5879.8    0.16       0
Bank Sta=5001,5007
Exp/Cntr=0.3,0.1

Chan Stop Cuts=-1