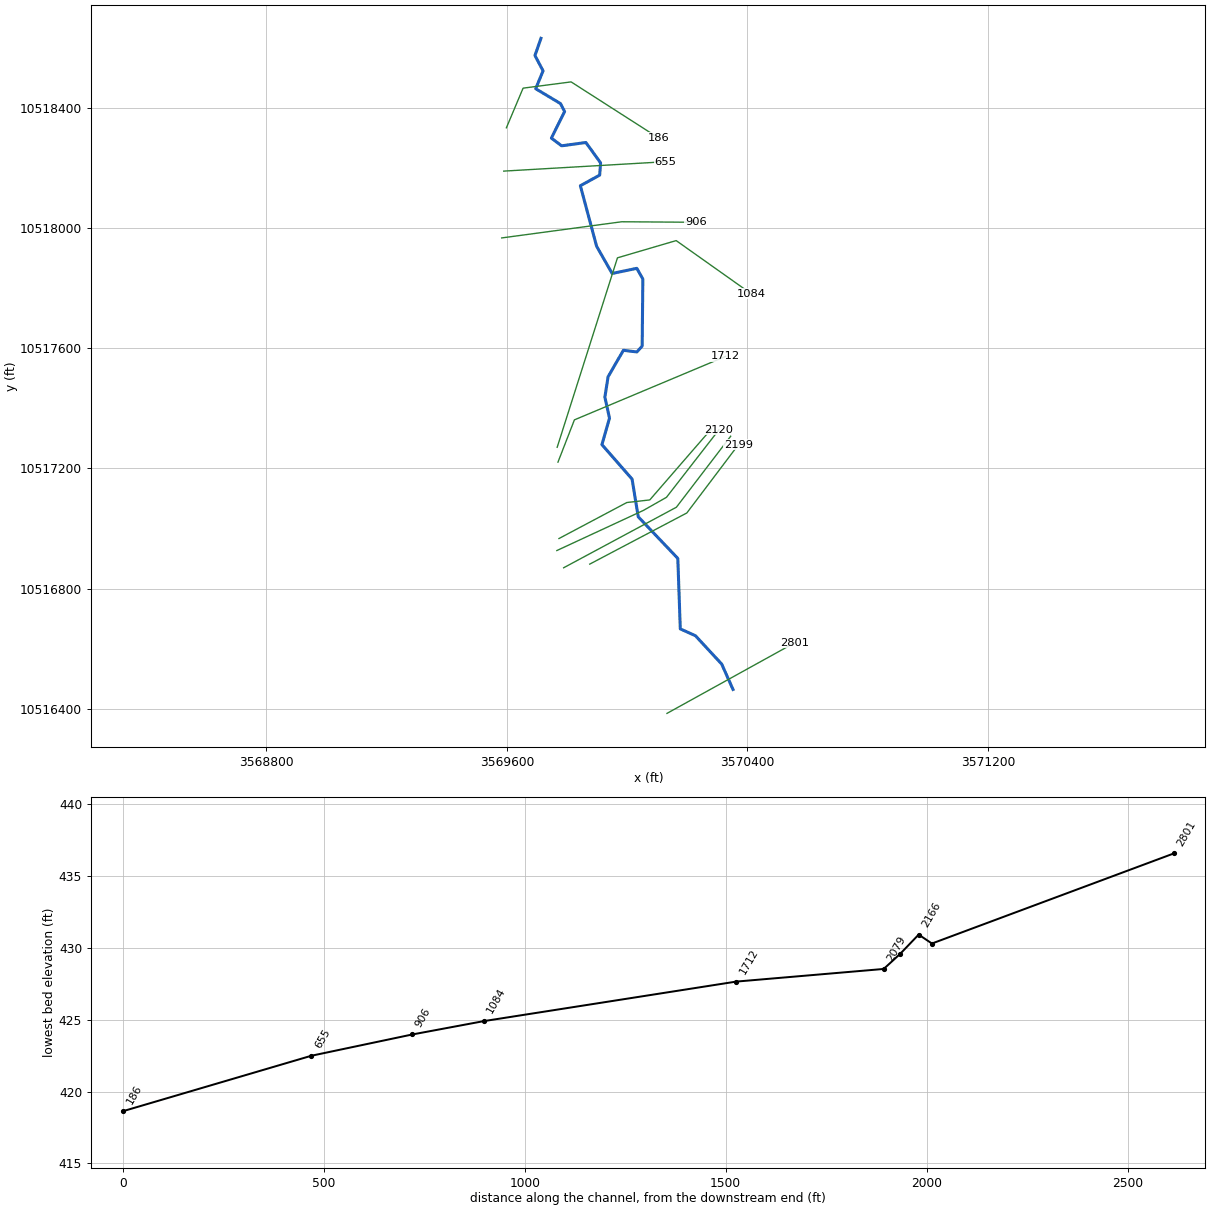
--- UNT0681 IN SAND CR.prj (project) ---

Proj Title=UNT0681 IN SAND CR Base Level Engineering
Current Plan=p01
Default Exp/Contr=0.3,0.1
English Units
Geom File=g01
Flow File=f01
Plan File=p01
BEGIN DESCRIPTION:
UNT0681 IN SAND CR
END DESCRIPTION:

--- UNT0681 IN SAND CR.p01 (plan) ---

Plan Title=Multiple Run
Short Identifier=Multiple
Geom File=g01
Flow File=f01
Subcritical Flow
K Sum by GR= 0
Std Step Tol= 0.01
Critical Tol= 0.01
Num of Std Step Trials= 20
Max Error Tol= 0.3
Flow Tol Ratio= 0.001
Split Flow NTrial= 30
Split Flow Tol= 0.02
Split Flow Ratio= 0.02
Log Output Level= 0
Friction Slope Method= 1
Unsteady Friction Slope Method= 2
Unsteady Bridges Friction Slope Method= 1
Parabolic Critical Depth
Global Vel Dist=  1 , 1 , 1
Global Log Level= 0
CheckData=True
Encroach Param= -1, 0, 0, 0
BEGIN DESCRIPTION:
Multiple Run
END DESCRIPTION:

--- UNT0681 IN SAND CR.f01 (steady flow) ---

Flow Title=Multiple
Number of Profiles=7
Profile Names=10-year,25-year,50-year,1pct_min,100-year,1pct_plu,500-year
River Rch & RM= UNT0681 IN SAND ,Reach-1,2801
     509     678     814     716     968    1310    1364
River Rch & RM= UNT0681 IN SAND ,Reach-1,906
     728     988    1201    1068    1444    1953    2079
Boundary for River Rch & Prof#=UNT0681 IN SAND ,Reach-1,1
Up Type=0
Dn Type=3
Dn Slope=0.005
Boundary for River Rch & Prof#=UNT0681 IN SAND ,Reach-1,2
Up Type=0
Dn Type=3
Dn Slope=0.005
Boundary for River Rch & Prof#=UNT0681 IN SAND ,Reach-1,3
Up Type=0
Dn Type=3
Dn Slope=0.005
Boundary for River Rch & Prof#=UNT0681 IN SAND ,Reach-1,4
Up Type=0
Dn Type=3
Dn Slope=0.005
Boundary for River Rch & Prof#=UNT0681 IN SAND ,Reach-1,5
Up Type=0
Dn Type=3
Dn Slope=0.005
Boundary for River Rch & Prof#=UNT0681 IN SAND ,Reach-1,6
Up Type=0
Dn Type=3
Dn Slope=0.005
Boundary for River Rch & Prof#=UNT0681 IN SAND ,Reach-1,7
Up Type=0
Dn Type=3
Dn Slope=0.005

--- UNT0681 IN SAND CR.g01 (geometry) ---

Geom Title=Existing Conditions

River Reach=UNT0681 IN SAND ,Reach-1
Reach XY= 30
      3570352.18     10516464.25      3570314.61     10516548.67
      3570227.25     10516642.99      3570176.82     10516665.76
      3570168.57     10516900.18      3570036.89     10517038.68
      3570016.43     10517164.07      3569916.15     10517278.69
      3569941.31     10517366.84      3569925.99     10517436.65
      3569936.57     10517504.47      3569987.55     10517592.50
      3570032.40     10517587.09      3570050.01     10517606.59
      3570052.26     10517829.68      3570032.26     10517865.21
      3569950.12     10517848.07      3569898.35     10517938.89
      3569844.40     10518140.03      3569908.63     10518175.18
      3569911.64     10518216.01      3569862.83     10518283.72
      3569781.93     10518272.76      3569748.02     10518298.42
      3569792.00     10518386.67      3569778.26     10518413.28
      3569695.77     10518462.64      3569720.32     10518522.07
      3569693.38     10518573.23      3569713.32     10518630.28

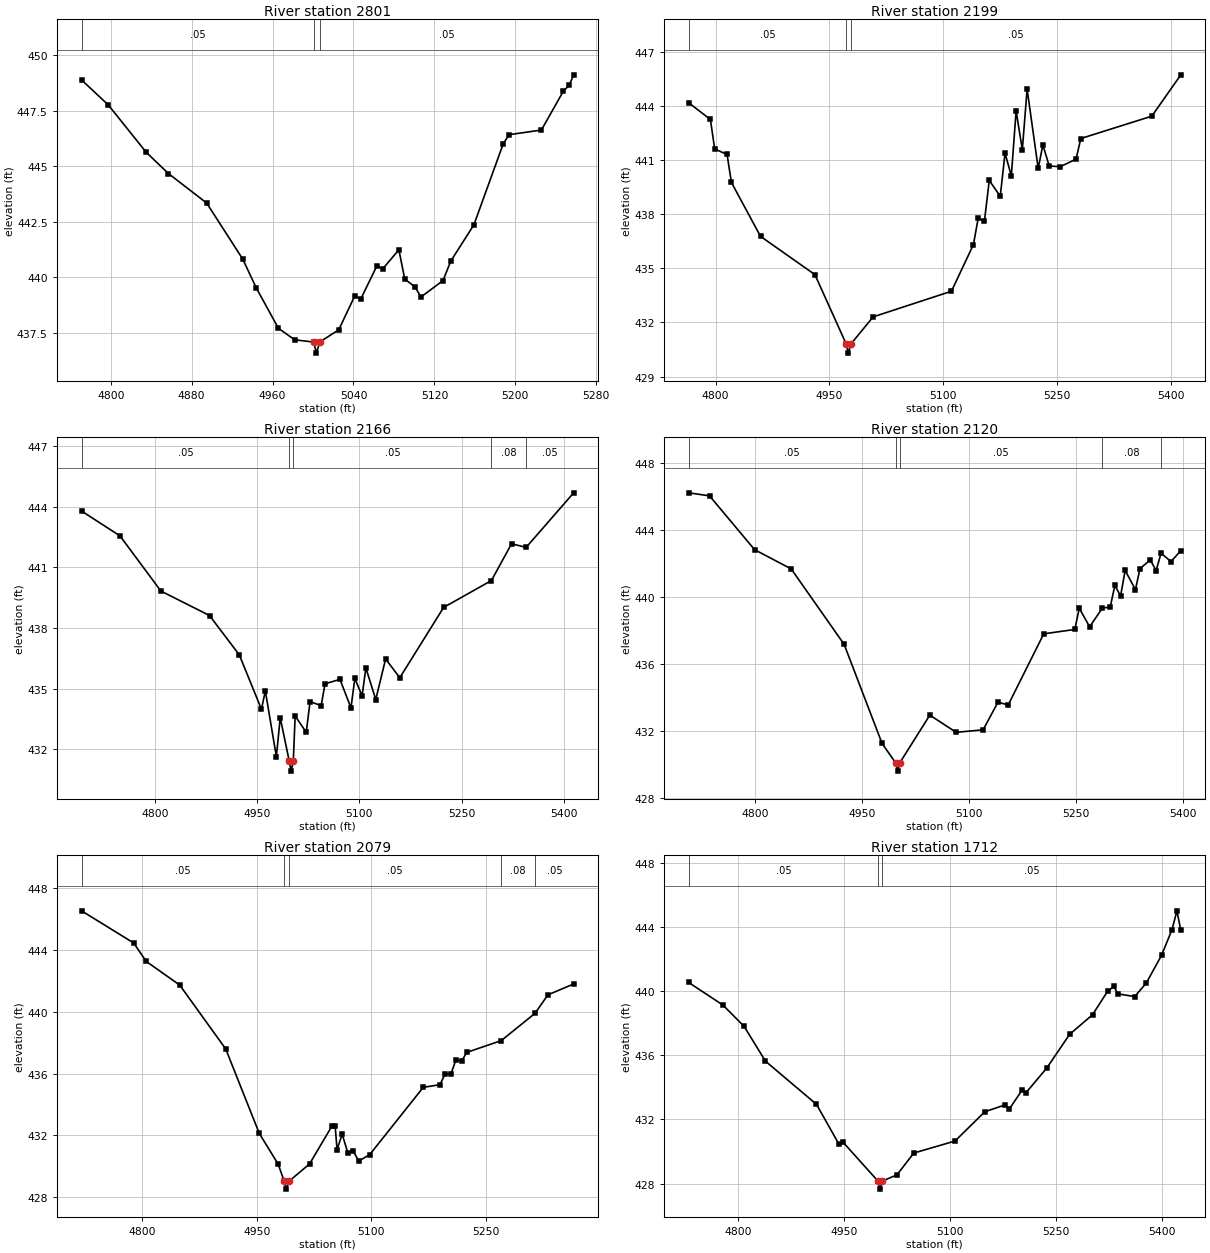
Type RM Length L Ch R = 1,2801,602,602,602
BEGIN DESCRIPTION:
UNT01852 IN SAND CR 3.0
END DESCRIPTION:
XS GIS Cut Line= 2
      3570132.58     10516384.71      3570558.44     10516620.14
#Sta/Elev= 30
  4771.1  448.89  4797.4  447.77  4835.2  445.62  4857.0  444.67  4894.8  443.34
  4930.5  440.81  4944.0  439.50  4965.8  437.69  4981.9  437.17  5000.6  437.07
  5003.4  436.57  5006.6  437.07  5025.4  437.62  5041.4  439.16  5047.1  439.00
  5063.2  440.51  5068.9  440.37  5084.9  441.23  5090.7  439.91  5101.0  439.55
  5106.7  439.10  5128.5  439.84  5136.2  440.72  5159.1  442.36  5188.0  446.00
  5193.8  446.42  5225.8  446.63  5247.6  448.39  5253.3  448.65  5257.7  449.12
#Mann=3,-1,0
  4771.1    0.05       0  5000.6    0.03       0  5006.6    0.05       0
Bank Sta=5000.6,5006.6
Exp/Cntr=0.3,0.1

Type RM Length L Ch R = 1,2199,33,33,33
BEGIN DESCRIPTION:
UNT01852 IN SAND CR 3.2
END DESCRIPTION:
XS GIS Cut Line= 3
      3569875.68     10516881.26      3570198.59     10517051.40
      3570369.64     10517277.74
#Sta/Elev= 30
  4764.5  444.17  4793.1  443.25  4798.8  441.61  4815.1  441.31  4820.8  439.76
  4859.2  436.77  4930.9  434.65  4972.2  430.80  4975.0  430.30  4978.2  430.80
  5007.7  432.31  5110.9  433.73  5139.8  436.31  5146.1  437.76  5154.4  437.63
  5160.7  439.87  5175.2  438.99  5181.5  441.38  5189.8  440.12  5196.1  443.72
  5204.3  441.57  5210.6  444.93  5225.2  440.54  5231.4  441.84  5239.7  440.67
  5254.3  440.63  5275.1  441.05  5281.4  442.19  5375.0  443.43  5413.2  445.72
#Mann=3,-1,0
  4764.5    0.05       0  4972.2    0.03       0  4978.2    0.05       0
Bank Sta=4972.2,4978.2
Exp/Cntr=0.3,0.1

Type RM Length L Ch R = 1,2166,46,46,46
BEGIN DESCRIPTION:
UNT01852 IN SAND CR 3.1
END DESCRIPTION:
XS GIS Cut Line= 3
      3569788.87     10516869.11      3570163.87     10517070.50
      3570344.43     10517306.62
#Sta/Elev= 30
  4691.8  443.79  4748.3  442.56  4808.4  439.83  4879.8  438.62  4923.6  436.67
  4956.1  433.98  4961.8  434.89  4978.0  431.64  4983.7  433.56  4996.9  431.42
  4999.7  430.92  5002.9  431.42  5005.6  433.65  5021.9  432.84  5027.5  434.36
  5043.8  434.16  5049.5  435.24  5071.4  435.46  5087.6  434.05  5093.3  435.51
  5103.9  434.64  5109.5  436.03  5124.0  434.46  5138.5  436.47  5159.3  435.54
  5223.7  439.02  5293.9  440.35  5323.5  442.17  5344.9  441.99  5414.7  444.69
#Mann=5,-1,0
  4691.8    0.05       0  4996.9    0.03       0  5002.9    0.05       0
  5293.9    0.08       0  5344.9    0.05       0
Bank Sta=4996.9,5002.9
Exp/Cntr=0.3,0.1

Type RM Length L Ch R = 1,2120,41,41,41
BEGIN DESCRIPTION:
UNT01852 IN SAND CR 2.0
END DESCRIPTION:
XS GIS Cut Line= 4
      3569766.27     10516926.39      3570054.49     10517060.08
      3570130.88     10517103.48      3570305.26     10517327.93
#Sta/Elev= 30
  4706.8  446.22  4736.0  446.04  4799.2  442.82  4850.5  441.67  4924.7  437.16
  4977.8  431.24  4996.8  430.08  4999.6  429.58  5002.8  430.08  5044.8  432.93
  5081.7  431.90  5119.5  432.05  5140.3  433.70  5154.7  433.54  5204.5  437.79
  5248.0  438.05  5254.3  439.32  5268.8  438.21  5286.7  439.33  5297.7  439.39
  5304.1  440.68  5312.2  440.06  5318.6  441.58  5333.0  440.43  5339.4  441.69
  5353.8  442.21  5362.0  441.57  5368.9  442.61  5382.8  442.11  5396.6  442.76
#Mann=5,-1,0
  4706.8    0.05       0  4996.8    0.03       0  5002.8    0.05       0
  5286.7    0.08       0  5368.9    0.05       0
Bank Sta=4996.8,5002.8
Exp/Cntr=0.3,0.1

Type RM Length L Ch R = 1,2079,367,367,367
BEGIN DESCRIPTION:
UNT01852 IN SAND CR 2.1
END DESCRIPTION:
XS GIS Cut Line= 4
      3569773.27     10516966.34      3569998.94     10517086.12
      3570075.33     10517094.80      3570280.21     10517330.94
#Sta/Elev= 30
  4720.5  446.52  4788.9  444.44  4805.3  443.25  4849.2  441.72  4909.5  437.59
  4953.5  432.13  4978.3  430.14  4986.2  429.03  4989.0  428.53  4992.2  429.03
  5019.4  430.16  5048.7  432.61  5052.9  432.61  5055.4  431.09  5062.1  432.08
  5069.7  430.85  5076.3  431.00  5083.9  430.35  5098.2  430.76  5168.4  435.11
  5190.3  435.28  5196.9  435.97  5204.6  435.97  5211.2  436.88  5218.8  436.82
  5225.4  437.37  5270.6  438.13  5315.0  439.90  5331.8  441.09  5365.5  441.79
#Mann=5,-1,0
  4720.5    0.05       0  4986.2    0.03       0  4992.2    0.05       0
  5270.6    0.08       0  5315.0    0.05       0
Bank Sta=4986.2,4992.2
Exp/Cntr=0.3,0.1

Type RM Length L Ch R = 1,1712,628,628,628
BEGIN DESCRIPTION:
UNT01852 IN SAND CR 3.3
END DESCRIPTION:
XS GIS Cut Line= 3
      3569769.92     10517220.47      3569824.60     10517361.08
      3570327.17     10517572.00
#Sta/Elev= 30
  4730.2  440.54  4778.7  439.13  4808.6  437.80  4838.8  435.63  4910.9  432.94
  4942.6  430.46  4948.0  430.60  4997.9  428.15  5000.7  427.65  5003.9  428.15
  5024.7  428.54  5048.5  429.90  5106.8  430.65  5149.0  432.48  5178.1  432.91
  5183.6  432.65  5201.9  433.84  5207.3  433.67  5236.5  435.20  5268.8  437.30
  5301.3  438.53  5323.0  440.02  5331.6  440.29  5337.0  439.83  5360.8  439.66
  5377.2  440.50  5398.9  442.24  5413.7  443.84  5420.6  445.01  5426.1  443.79
#Mann=3,-1,0
  4730.2    0.05       0  4997.9    0.03       0  5003.9    0.05       0
Bank Sta=4997.9,5003.9
Exp/Cntr=0.3,0.1

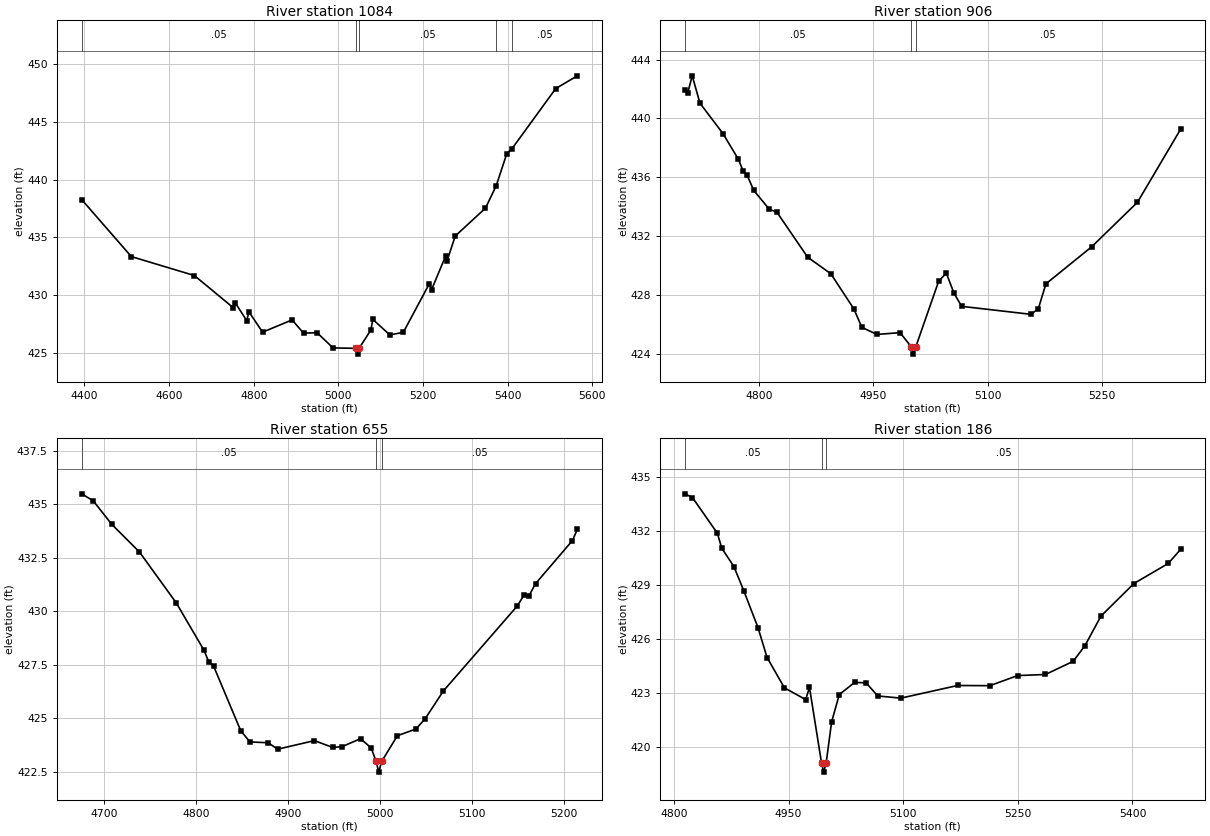
Type RM Length L Ch R = 1,1084,178,178,178
BEGIN DESCRIPTION:
UNT01852 IN SAND CR 3.4
END DESCRIPTION:
XS GIS Cut Line= 4
      3569767.30     10517269.91      3569967.83     10517900.14
      3570163.14     10517957.43      3570413.17     10517780.33
#Sta/Elev= 30
  4393.4  438.27  4510.7  433.34  4659.7  431.70  4751.2  428.93  4756.4  429.33
  4783.4  427.80  4788.6  428.56  4820.9  426.80  4890.6  427.86  4917.6  426.72
  4949.8  426.75  4987.3  425.44  5042.8  425.40  5045.6  424.90  5048.8  425.40
  5076.4  426.96  5081.6  427.90  5121.7  426.56  5153.6  426.79  5215.1  431.00
  5220.4  430.49  5253.8  433.42  5256.9  432.98  5276.2  435.12  5347.6  437.53
  5373.0  439.47  5398.0  442.25  5409.4  442.63  5513.7  447.88  5564.7  448.98
#Mann=5,-1,0
  4393.4    0.05       0  5042.8    0.03       0  5048.8    0.05       0
  5373.0    0.16       0  5409.4    0.05       0
Bank Sta=5042.8,5048.8
Exp/Cntr=0.3,0.1

Type RM Length L Ch R = 1,906,251,251,251
BEGIN DESCRIPTION:
UNT0681 IN SAND CR 1.1
END DESCRIPTION:
XS GIS Cut Line= 3
      3569582.72     10517966.30      3569982.01     10518020.12
      3570228.71     10518018.39
#Sta/Elev= 30
  4703.2  441.96  4706.7  441.74  4712.7  442.90  4722.8  441.04  4753.0  438.97
  4773.2  437.22  4779.4  436.42  4784.5  436.15  4793.4  435.10  4813.6  433.83
  4823.7  433.62  4864.0  430.56  4894.3  429.44  4924.6  427.04  4935.0  425.79
  4954.8  425.31  4985.1  425.43  4999.7  424.47  5002.5  423.97  5005.7  424.47
  5035.6  428.92  5045.6  429.49  5055.7  428.12  5065.8  427.22  5156.2  426.68
  5166.2  427.04  5176.2  428.75  5236.2  431.27  5296.2  434.30  5352.8  439.27
#Mann=3,-1,0
  4703.2    0.05       0  4999.7    0.03       0  5005.7    0.05       0
Bank Sta=4999.7,5005.7
Exp/Cntr=0.3,0.1

Type RM Length L Ch R = 1,655,469,469,469
BEGIN DESCRIPTION:
UNT0681 IN SAND CR 1.2
END DESCRIPTION:
XS GIS Cut Line= 2
      3569589.52     10518188.59      3570127.42     10518219.83
#Sta/Elev= 30
  4675.6  435.48  4688.2  435.15  4708.2  434.06  4738.3  432.77  4778.4  430.39
  4808.4  428.19  4813.9  427.62  4818.9  427.45  4848.5  424.42  4858.5  423.90
  4878.5  423.86  4888.5  423.56  4928.6  423.96  4948.6  423.64  4958.7  423.68
  4978.7  424.05  4990.3  423.62  4995.7  422.99  4998.5  422.49  5001.7  422.99
  5018.8  424.19  5038.8  424.50  5048.8  424.97  5068.8  426.28  5149.0  430.24
  5156.7  430.77  5161.7  430.71  5169.0  431.29  5209.1  433.30  5214.4  433.82
#Mann=3,-1,0
  4675.6    0.05       0  4995.7    0.03       0  5001.7    0.05       0
Bank Sta=4995.7,5001.7
Exp/Cntr=0.3,0.1

Type RM Length L Ch R = 1,186,0,0,0
BEGIN DESCRIPTION:
UNT0681 IN SAND CR 1.0
END DESCRIPTION:
XS GIS Cut Line= 4
      3569598.34     10518332.63      3569653.89     10518464.56
      3569813.61     10518485.39      3570103.57     10518299.61
#Sta/Elev= 30
  4814.4  434.05  4824.2  433.84  4856.7  431.87  4862.5  431.04  4878.4  430.02
  4891.6  428.65  4909.9  426.64  4921.8  424.98  4944.5  423.30  4972.3  422.65
  4977.3  423.32  4993.1  419.13  4995.8  418.63  4999.1  419.13  5006.2  421.40
  5016.3  422.93  5036.4  423.60  5051.3  423.58  5066.7  422.85  5096.9  422.73
  5171.1  423.43  5213.4  423.42  5249.7  423.98  5286.1  424.04  5322.4  424.77
  5337.7  425.63  5358.8  427.28  5401.9  429.08  5446.7  430.19  5463.0  430.97
#Mann=3,-1,0
  4814.4    0.05       0  4993.1    0.03       0  4999.1    0.05       0
Bank Sta=4993.1,4999.1
Exp/Cntr=0.3,0.1

Chan Stop Cuts=-1