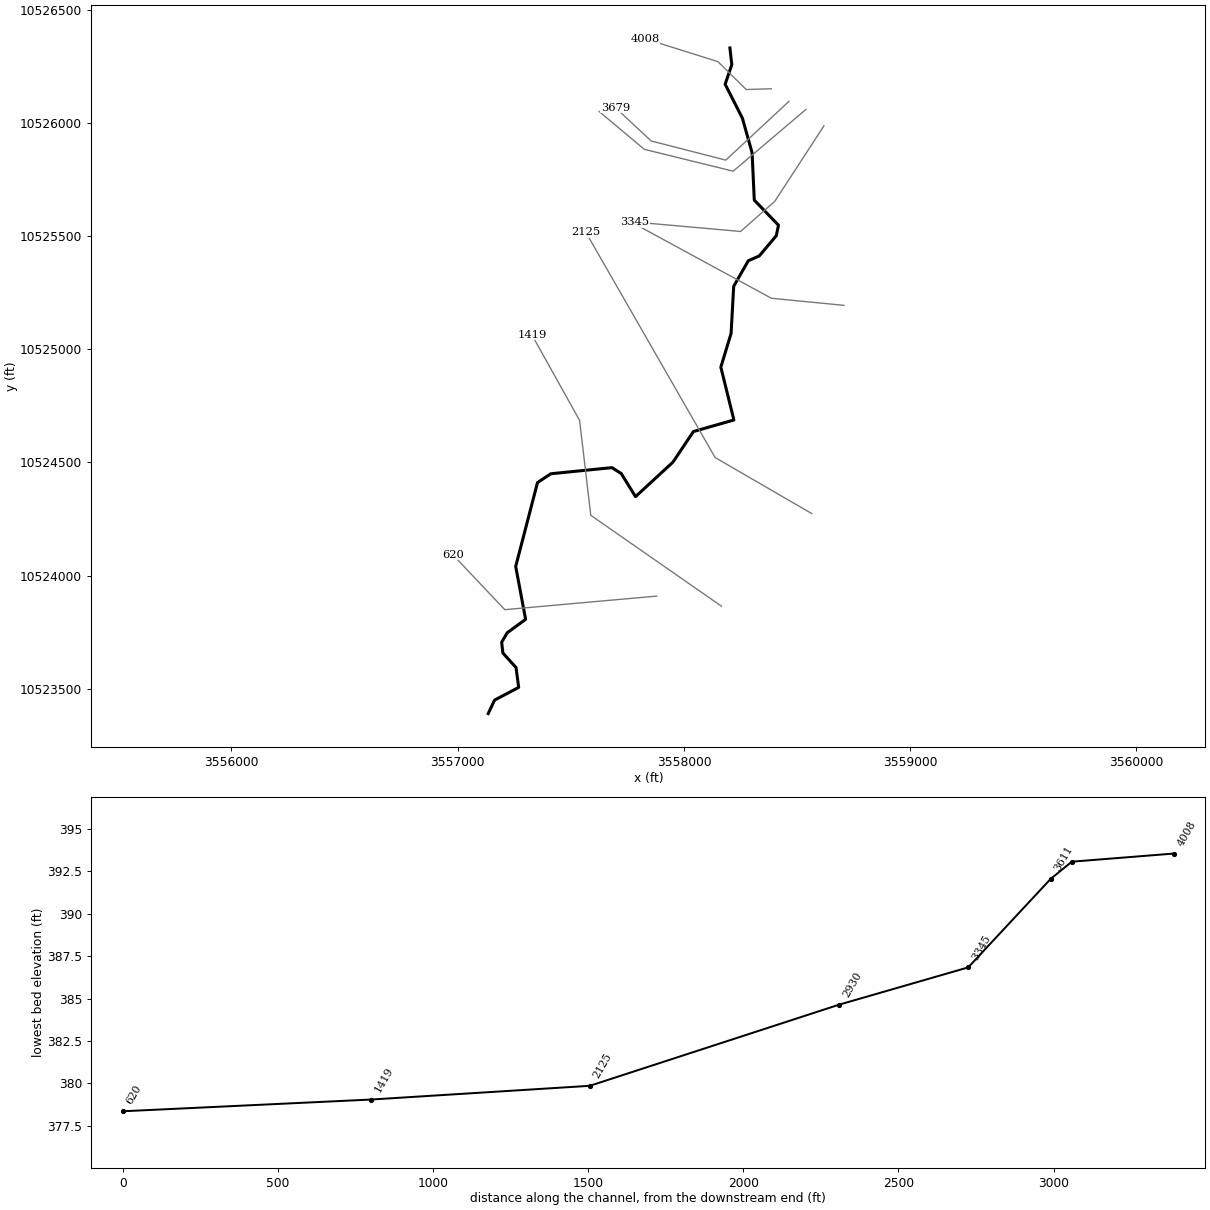
--- UNT0685 IN SAND CR.prj (project) ---

Proj Title=UNT0685 IN SAND CR Base Level Engineering
Current Plan=p01
Default Exp/Contr=0.3,0.1
English Units
Geom File=g01
Flow File=f01
Plan File=p01
Y Axis Title=Elevation
X Axis Title(PF)=Main Channel Distance
X Axis Title(XS)=Station
BEGIN DESCRIPTION:
UNT0685 IN SAND CR
END DESCRIPTION:
DSS Export Rating Curves= 0
DSS Export Rating Curve Sorted= 0
DSS Export Volume Flow Curves= 0
DXF OffsetX= 0
DXF OffsetY= 0
DXF ScaleX= 1
DXF ScaleY= 10

--- UNT0685 IN SAND CR.p01 (plan) ---

Plan Title=Multiple Run
Short Identifier=Multiple
Geom File=g01
Flow File=f01
Subcritical Flow
K Sum by GR= 0
Std Step Tol= 0.01
Critical Tol= 0.01
Num of Std Step Trials= 20
Max Error Tol= 0.3
Flow Tol Ratio= 0.001
Split Flow NTrial= 30
Split Flow Tol= 0.02
Split Flow Ratio= 0.02
Log Output Level= 0
Friction Slope Method= 1
Unsteady Friction Slope Method= 2
Unsteady Bridges Friction Slope Method= 1
Parabolic Critical Depth
Global Vel Dist=  1 , 1 , 1
Global Log Level= 0
CheckData=True
Encroach Param= -1, 0, 0, 0
BEGIN DESCRIPTION:
Multiple Run
END DESCRIPTION:

--- UNT0685 IN SAND CR.f01 (steady flow) ---

Flow Title=Multiple
Number of Profiles=7
Profile Names=10-year,25-year,50-year,1pct_min,100-year,1pct_plu,500-year
River Rch & RM= UNT0685 IN SAND ,Reach-1,4008
     399     515     605     520     703     951     945
Boundary for River Rch & Prof#=UNT0685 IN SAND ,Reach-1,1
Up Type=0
Dn Type=3
Dn Slope=0.005
Boundary for River Rch & Prof#=UNT0685 IN SAND ,Reach-1,2
Up Type=0
Dn Type=3
Dn Slope=0.005
Boundary for River Rch & Prof#=UNT0685 IN SAND ,Reach-1,3
Up Type=0
Dn Type=3
Dn Slope=0.005
Boundary for River Rch & Prof#=UNT0685 IN SAND ,Reach-1,4
Up Type=0
Dn Type=3
Dn Slope=0.005
Boundary for River Rch & Prof#=UNT0685 IN SAND ,Reach-1,5
Up Type=0
Dn Type=3
Dn Slope=0.005
Boundary for River Rch & Prof#=UNT0685 IN SAND ,Reach-1,6
Up Type=0
Dn Type=3
Dn Slope=0.005
Boundary for River Rch & Prof#=UNT0685 IN SAND ,Reach-1,7
Up Type=0
Dn Type=3
Dn Slope=0.005

--- UNT0685 IN SAND CR.g01 (geometry) ---

Geom Title=Existing Conditions
Program Version=4.10

River Reach=UNT0685 IN SAND ,Reach-1
Reach XY= 30
      3558203.08     10526330.41      3558211.43       10526257.
      3558182.05     10526170.37      3558258.43     10526020.07
      3558301.16     10525867.46      3558310.79      10525658.6
      3558417.82     10525547.93      3558407.93     10525501.31
      3558332.67     10525411.99      3558284.23     10525390.89
      3558219.72     10525277.87      3558208.27     10525070.06
      3558162.95      10524921.1      3558220.63     10524687.81
      3558041.66     10524636.63      3557951.55     10524501.81
      3557785.84     10524349.28      3557722.82     10524451.11
      3557681.74     10524477.33      3557411.81     10524450.33
      3557352.66     10524411.55       3557256.2     10524040.95
      3557300.05     10523807.36      3557218.62     10523748.01
      3557194.16     10523706.14      3557199.56     10523658.71
       3557257.7     10523594.54       3557269.4     10523506.85
      3557162.88     10523450.81      3557134.81     10523391.36

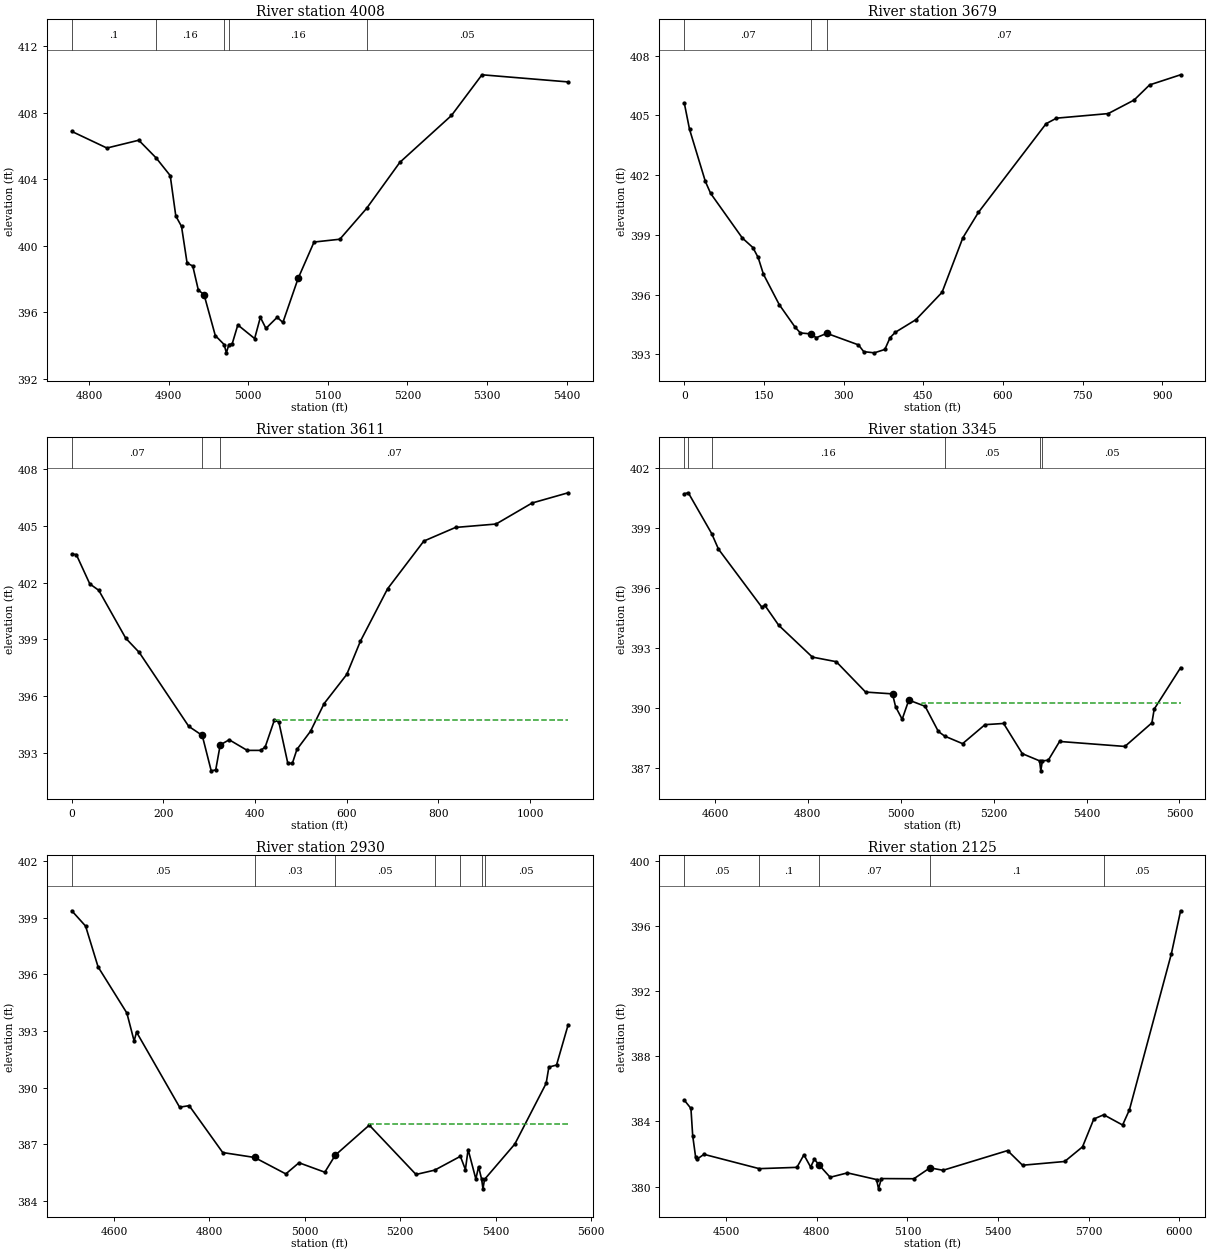
Type RM Length L Ch R = 1 ,4008    ,329,329,329
BEGIN DESCRIPTION:
UNT0685 IN SAND CR 5.0
END DESCRIPTION:
XS GIS Cut Line= 4
      3558386.16     10526150.46      3558275.02     10526146.99
      3558150.02     10526270.25      3557828.88     10526370.94
#Sta/Elev= 30
  4778.5  406.88  4822.6  405.88  4862.6  406.35  4884.5  405.28  4902.1  404.22
  4909.1  401.79  4916.3  401.16  4923.3  398.95  4930.4  398.78  4937.4  397.33
  4944.6  397.05  4958.7  394.59  4969.8  394.05  4972.6  393.55  4975.8  394.05
  4979.9  394.09    4987  395.23  5008.1  394.41  5015.3  395.69  5022.3  395.02
  5036.4  395.69  5043.6  395.38  5062.7  398.03  5082.7  400.22  5115.1  400.39
  5148.6  402.24  5190.5  405.02  5255.3  407.84  5293.6  410.29  5401.8  409.86
#Mann= 5 ,-1 , 0
  4778.5      .1       0  4884.5     .16       0  4969.8     .07       0
  4975.8     .16       0  5148.6     .05       0
Bank Sta=4944.6,5062.7
XS Rating Curve= 0 ,0
Exp/Cntr=0.3,0.1

Type RM Length L Ch R = 1 ,3679    ,68,68,68
XS GIS Cut Line= 4
     3558463.775    10526094.558     3558184.912    10525835.227
     3557855.051    10525919.862     3557697.716    10526066.346
#Sta/Elev= 30
       0  405.63    9.94   404.3   39.75  401.68   49.69  401.08  109.32  398.84
  129.19  398.36  139.13  397.86  149.07  397.02  178.88  395.49   208.7  394.36
  218.64  394.07  238.51  394.02  248.45  393.83  268.33  394.05  327.95  393.47
  337.89  393.13  357.77  393.07  377.64  393.24  387.43  393.83  397.22   394.1
  436.38  394.74  485.33  396.11  524.49  398.85  553.86  400.13  681.13  404.58
  700.71  404.86  798.16  405.09  846.83  405.77  876.03  406.53  934.43  407.04
#Mann= 3 , 0 , 0
       0     .07       0  238.51     .05       0  268.33     .07       0
#XS Ineff= 2 , 0
       0                  272.45       0  393.83
Permanent Ineff=
       F       T
Bank Sta=238.51,268.33
XS Rating Curve= 0 ,0
Exp/Cntr=0.3,0.1

Type RM Length L Ch R = 1 ,3611    ,266,266,266
XS GIS Cut Line= 4
     3558538.645    10526058.751     3558217.464    10525786.399
     3557824.669     10525882.97     3557625.016     10526050.07
#Sta/Elev= 30
       0   403.5    9.82  403.48   39.26  401.93   58.89  401.59  117.79  399.06
  147.23  398.31   255.2  394.41  284.65  393.93  304.28  392.06   314.1  392.11
  323.91  393.43  343.54   393.7  382.81  393.14  412.25  393.14  422.07  393.32
  441.85  394.72  451.74  394.65  471.53  392.45  481.42  392.46  491.31  393.19
  520.98  394.15  550.66  395.61  600.11  397.15  629.79   398.9  689.14  401.67
  768.27  404.19  837.45  404.91  925.94  405.09 1004.59   406.2 1083.25  406.74
#Mann= 3 , 0 , 0
       0     .07       0  284.65     .05       0  323.91     .07       0
#XS Ineff= 2 , 0
                          442.72          394.73
Permanent Ineff=
       F       F
Bank Sta=284.65,323.91
XS Rating Curve= 0 ,0
Exp/Cntr=0.3,0.1

Type RM Length L Ch R = 1 ,3345    ,415,415,415
BEGIN DESCRIPTION:
UNT0685 IN SAND CR 4.01
END DESCRIPTION:
XS GIS Cut Line= 4
      3558618.65     10525986.39      3558401.18     10525653.02
      3558250.14      10525520.2      3557782.65     10525561.87
#Sta/Elev= 30
  4533.9   400.7  4542.6  400.75  4592.9  398.71  4607.6  397.93  4701.1  395.02
  4707.1  395.13  4737.3  394.12  4809.7  392.53  4861.1   392.3  4924.3  390.78
  4982.2  390.69  4988.8  390.05    5003  389.42  5017.3  390.38  5052.4  390.07
  5080.9  388.81  5094.3  388.58  5133.1   388.2  5181.3  389.15  5221.4  389.21
  5261.6   387.7  5298.8  387.34  5301.5  386.84  5304.8  387.34  5317.5  387.37
  5341.9  388.31  5482.5  388.06  5540.6  389.24  5545.6  389.93  5602.4     392
#Mann= 6 ,-1 , 0
  4533.9     .16       0  4542.6     .05       0  4592.9     .16       0
  5094.3     .05       0  5298.8     .07       0  5304.8     .05       0
#XS Ineff= 2 , 0
       0                 5045.63       0  390.21
Permanent Ineff=
       F       T
Bank Sta=4982.2,5017.3
XS Rating Curve= 0 ,0
Exp/Cntr=0.3,0.1

Type RM Length L Ch R = 1 ,2930    ,805,805,805
BEGIN DESCRIPTION:
UNT0685 IN SAND CR 4.0
END DESCRIPTION:
XS GIS Cut Line= 3
      3558706.96     10525193.94      3558386.68     10525225.19
      3557755.49     10525568.06
#Sta/Elev= 30
  4511.6  399.36  4540.5  398.55  4566.7  396.39    4627  393.95  4642.2  392.47
  4647.3  392.94  4737.5  388.97  4757.6  389.05  4827.9  386.57  4894.6  386.31
  4960.1  385.44  4987.7  386.03  5041.8  385.53  5063.7  386.43    5135  388.02
  5232.9  385.41  5272.1  385.64  5325.9  386.37  5336.4  385.67  5342.1  386.73
  5358.3  385.17    5364  385.82  5370.5  385.15  5373.2  384.65  5376.5  385.15
    5440  387.02  5505.6  390.23  5511.3  391.09  5527.4   391.2  5551.7  393.33
#Mann= 7 ,-1 , 0
  4511.6     .05       0  4894.6     .03       0  5063.7     .05       0
  5272.1      .1       0  5325.9     .05       0  5370.5     .03       0
  5376.5     .05       0
#XS Ineff= 2 , 0
                         5135.17          388.06
Permanent Ineff=
       F       F
Bank Sta=4894.6,5063.7
XS Rating Curve= 0 ,0
Exp/Cntr=0.3,0.1

Type RM Length L Ch R = 1 ,2125    ,706,706,706
BEGIN DESCRIPTION:
UNT0685 IN SAND CR 3.0
END DESCRIPTION:
XS GIS Cut Line= 3
      3558564.66     10524274.61      3558137.59       10524522.
      3557565.46     10525518.02
#Sta/Elev= 30
  4361.6  385.31  4383.7   384.8  4389.5  383.13  4399.2  381.81  4405.3   381.7
  4426.8  381.98  4609.6   381.1  4734.4  381.18  4757.5  381.95  4779.7   381.2
  4792.1  381.68    4807  381.34  4844.3  380.57  4901.5  380.84  4997.8  380.43
  5004.4  379.86  5013.6  380.49  5121.4  380.48  5174.6  381.15  5217.8     381
  5431.4  382.21  5480.9  381.31  5620.3  381.54  5679.3  382.44  5716.7  384.15
  5749.5  384.41  5811.9  383.78  5834.6  384.72  5973.4  394.31  6003.8  396.94
#Mann= 5 ,-1 , 0
  4361.6     .05       0  4609.6      .1       0    4807     .07       0
  5174.6      .1       0  5749.5     .05       0
Bank Sta=4807,5174.6
XS Rating Curve= 0 ,0
Exp/Cntr=0.3,0.1

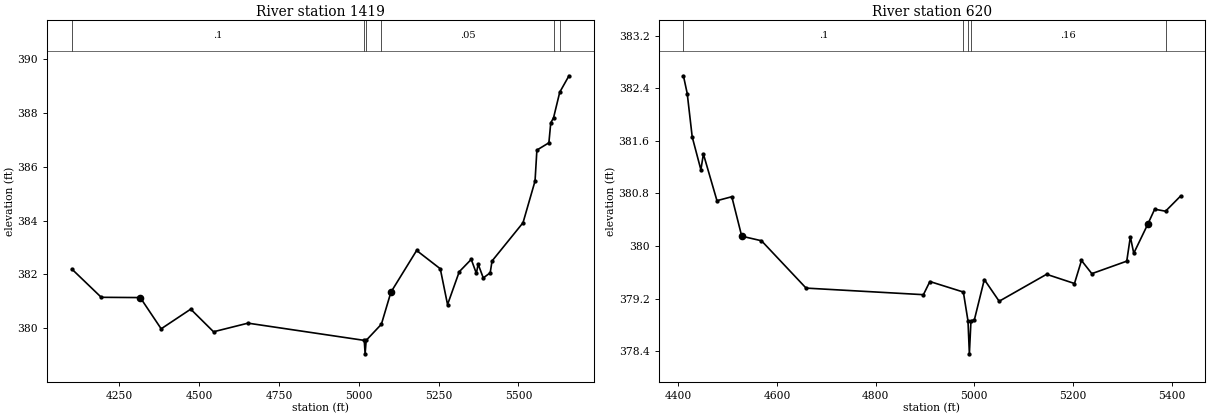
Type RM Length L Ch R = 1 ,1419    ,799,799,799
BEGIN DESCRIPTION:
UNT0685 IN SAND CR 2.0
END DESCRIPTION:
XS GIS Cut Line= 4
      3558165.32     10523865.75      3557588.11     10524266.79
      3557538.63     10524686.06      3557327.67      10525063.7
#Sta/Elev= 30
  4100.8   382.2    4193  381.15  4315.2  381.14  4380.7  379.98  4473.3  380.71
  4544.8  379.87  4652.7  380.19    5017  379.55  5019.7  379.05    5023  379.55
  5070.7  380.15  5100.5  381.34  5181.1  382.89  5255.2  382.21    5278  380.88
  5314.6   382.1  5352.2  382.56  5368.2  382.04  5373.9  382.38  5389.9  381.87
  5411.6  382.06  5417.4   382.5  5514.4  383.92  5552.1  385.47  5557.9  386.62
  5595.5  386.89  5601.3  387.63  5610.1  387.82  5629.5  388.77  5658.4  389.38
#Mann= 6 ,-1 , 0
  4100.8      .1       0    5017     .07       0    5023      .1       0
  5070.7     .05       0  5610.1     .16       0  5629.5     .05       0
Bank Sta=4315.2,5100.5
XS Rating Curve= 0 ,0
Exp/Cntr=0.3,0.1

Type RM Length L Ch R = 1 ,620     ,0,0,0
BEGIN DESCRIPTION:
UNT0685 IN SAND CR 1.0
END DESCRIPTION:
XS GIS Cut Line= 3
      3557879.81     10523910.02       3557207.9     10523850.12
      3556978.74     10524092.31
#Sta/Elev= 30
  4410.1  382.59  4417.8  382.32  4427.9  381.66  4445.5  381.16  4450.6   381.4
  4478.1  380.69  4508.2  380.75  4528.3  380.15  4568.4  380.08  4658.8  379.36
  4896.7  379.26  4909.8  379.46  4977.7   379.3  4987.1  378.86  4989.9  378.36
  4993.1  378.86  5000.1  378.88  5020.2  379.49  5050.3  379.16  5146.4  379.57
    5203  379.43  5217.2  379.78  5238.2  379.58    5309  379.77  5316.3  380.14
  5323.2  379.89  5351.5  380.33  5365.6  380.56  5387.7  380.53  5418.1  380.76
#Mann= 5 ,-1 , 0
  4410.1      .1       0  4977.7     .16       0  4987.1     .07       0
  4993.1     .16       0  5387.7     .05       0
Bank Sta=4528.3,5351.5
XS Rating Curve= 0 ,0
Exp/Cntr=0.3,0.1

Chan Stop Cuts=-1
Use User Specified Reach Order=0
Composite Channel Slope=5