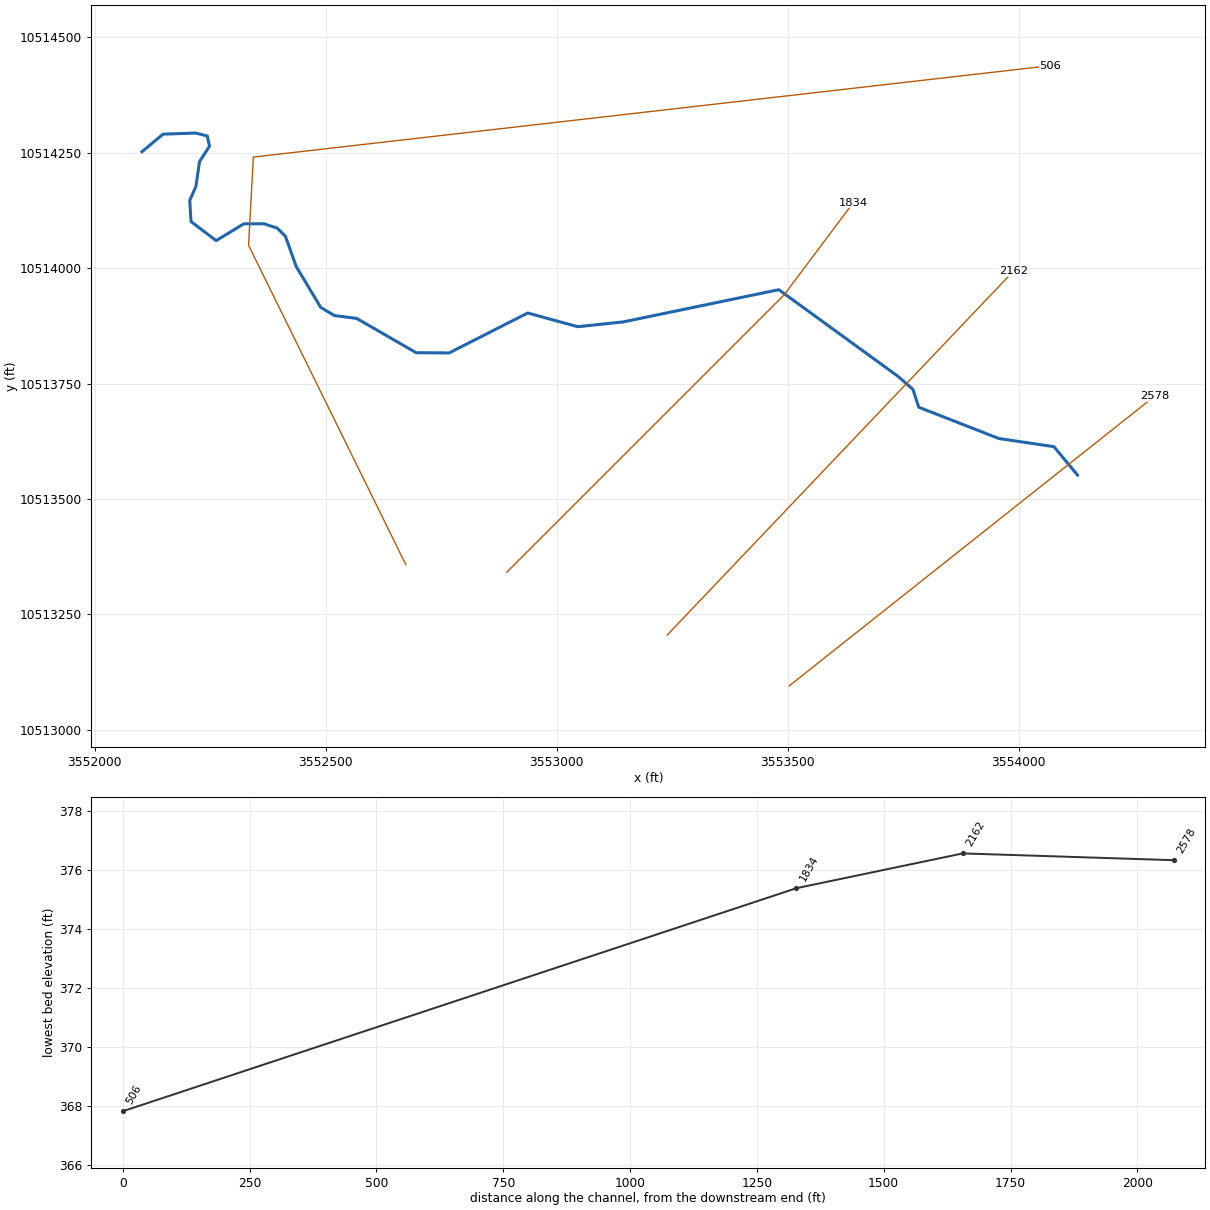
--- UNT0690 IN SAND CR.prj (project) ---

Proj Title=UNT0690 IN SAND CR Base Level Engineering
Current Plan=p01
Default Exp/Contr=0.3,0.1
English Units
Geom File=g01
Flow File=f01
Plan File=p01
BEGIN DESCRIPTION:
UNT0690 IN SAND CR
END DESCRIPTION:

--- UNT0690 IN SAND CR.p01 (plan) ---

Plan Title=Multiple Run
Short Identifier=Multiple
Geom File=g01
Flow File=f01
Subcritical Flow
K Sum by GR= 0
Std Step Tol= 0.01
Critical Tol= 0.01
Num of Std Step Trials= 20
Max Error Tol= 0.3
Flow Tol Ratio= 0.001
Split Flow NTrial= 30
Split Flow Tol= 0.02
Split Flow Ratio= 0.02
Log Output Level= 0
Friction Slope Method= 1
Unsteady Friction Slope Method= 2
Unsteady Bridges Friction Slope Method= 1
Parabolic Critical Depth
Global Vel Dist=  1 , 1 , 1
Global Log Level= 0
CheckData=True
Encroach Param= -1, 0, 0, 0
BEGIN DESCRIPTION:
Multiple Run
END DESCRIPTION:

--- UNT0690 IN SAND CR.f01 (steady flow) ---

Flow Title=Multiple
Number of Profiles=7
Profile Names=10-year,25-year,50-year,1pct_min,100-year,1pct_plu,500-year
River Rch & RM= UNT0690 IN SAND ,Reach-1,2578
     818    1115    1359    1210    1636    2213    2363
Boundary for River Rch & Prof#=UNT0690 IN SAND ,Reach-1,1
Up Type=0
Dn Type=3
Dn Slope=0.005
Boundary for River Rch & Prof#=UNT0690 IN SAND ,Reach-1,2
Up Type=0
Dn Type=3
Dn Slope=0.005
Boundary for River Rch & Prof#=UNT0690 IN SAND ,Reach-1,3
Up Type=0
Dn Type=3
Dn Slope=0.005
Boundary for River Rch & Prof#=UNT0690 IN SAND ,Reach-1,4
Up Type=0
Dn Type=3
Dn Slope=0.005
Boundary for River Rch & Prof#=UNT0690 IN SAND ,Reach-1,5
Up Type=0
Dn Type=3
Dn Slope=0.005
Boundary for River Rch & Prof#=UNT0690 IN SAND ,Reach-1,6
Up Type=0
Dn Type=3
Dn Slope=0.005
Boundary for River Rch & Prof#=UNT0690 IN SAND ,Reach-1,7
Up Type=0
Dn Type=3
Dn Slope=0.005

--- UNT0690 IN SAND CR.g01 (geometry) ---

Geom Title=Existing Conditions

River Reach=UNT0690 IN SAND ,Reach-1
Reach XY= 30
      3554127.40     10513551.75      3554076.42     10513613.25
      3553957.15     10513630.95      3553783.71     10513698.66
      3553771.21     10513737.20      3553738.40     10513765.85
      3553480.79     10513953.09      3553144.13     10513883.39
      3553045.69     10513872.97      3552937.36     10513902.66
      3552767.05     10513816.20      3552695.69     10513816.72
      3552566.89     10513891.02      3552518.77     10513897.05
      3552489.00     10513915.00      3552436.02     10514003.44
      3552412.74     10514068.76      3552394.83     10514086.49
      3552366.09     10514095.87      3552322.40     10514095.59
      3552262.85     10514059.31      3552208.40     10514100.52
      3552205.65     10514146.35      3552219.11     10514177.31
      3552226.72     10514230.19      3552248.37     10514263.80
      3552243.65     10514285.70      3552219.22     10514292.20
      3552147.83     10514289.85      3552102.11     10514251.64

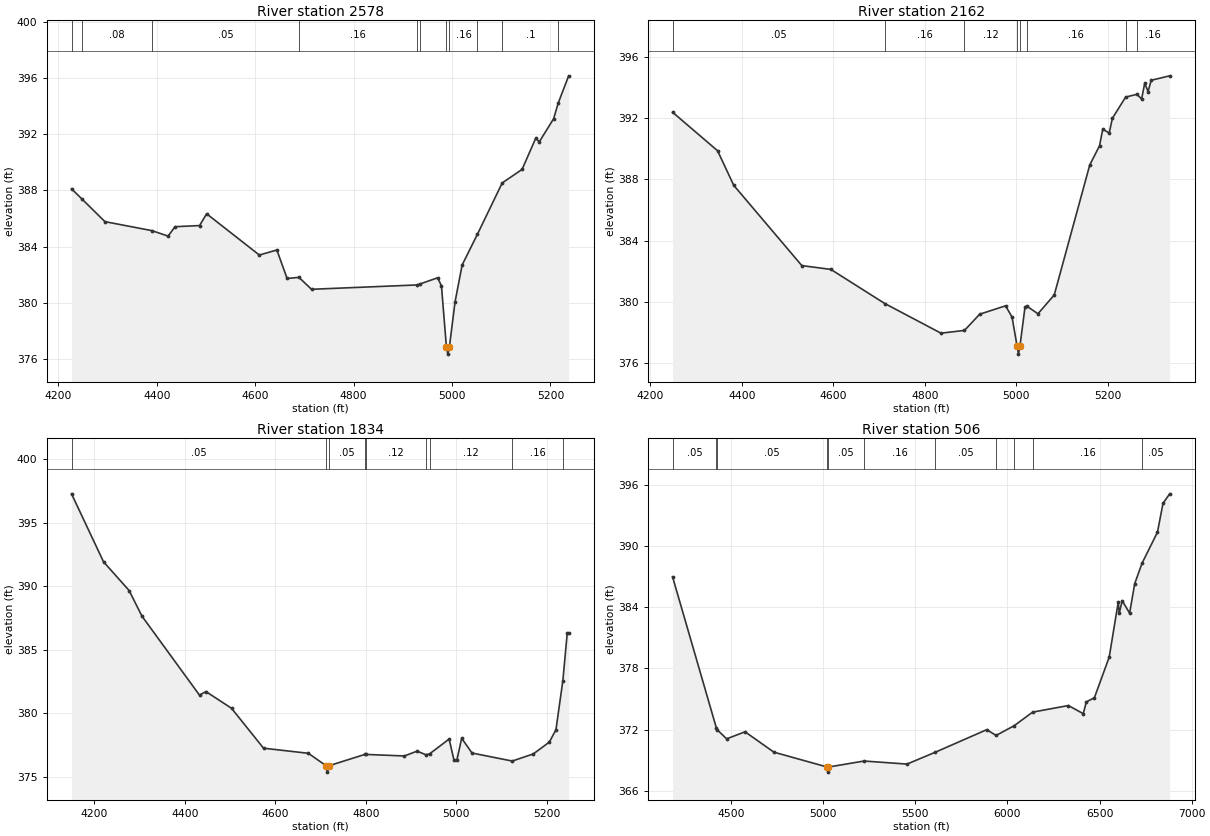
Type RM Length L Ch R = 1,2578,416,416,416
BEGIN DESCRIPTION:
UNT0690 IN SAND CR 2.0
END DESCRIPTION:
XS GIS Cut Line= 2
      3553502.97     10513095.17      3554294.67     10513722.80
#Sta/Elev= 30
  4226.7  388.12  4248.9  387.36  4294.6  385.78  4390.0  385.14  4422.8  384.75
  4437.2  385.42  4486.9  385.50  4501.3  386.34  4608.4  383.40  4644.0  383.76
  4664.8  381.73  4688.9  381.81  4714.4  380.96  4929.4  381.27  4935.8  381.35
  4970.8  381.78  4978.5  381.20  4988.6  376.84  4991.4  376.34  4994.6  376.84
  5006.1  380.06  5020.5  382.69  5051.7  384.89  5102.0  388.54  5142.3  389.50
  5169.9  391.71  5177.5  391.48  5206.4  393.11  5216.0  394.25  5237.0  396.17
#Mann=11,-1,0
  4226.7    0.05       0  4248.9    0.08       0  4390.0    0.05       0
  4688.9    0.16       0  4929.4    0.05       0  4935.8    0.16       0
  4988.6    0.07       0  4994.6    0.16       0  5051.7    0.05       0
  5102.0     0.1       0  5216.0    0.08       0
Bank Sta=4988.6,4994.6
Exp/Cntr=0.3,0.1

Type RM Length L Ch R = 1,2162,328,328,328
BEGIN DESCRIPTION:
UNT0690 IN SAND CR 2.2
END DESCRIPTION:
XS GIS Cut Line= 2
      3553239.14     10513205.43      3553988.11     10513992.54
#Sta/Elev= 30
  4248.8  392.39  4347.2  389.87  4382.5  387.61  4531.3  382.36  4594.8  382.11
  4712.6  379.88  4835.4  377.94  4886.8  378.12  4920.0  379.18  4976.6  379.73
  4990.8  378.99  5001.9  377.07  5004.7  376.57  5007.9  377.07  5019.1  379.65
  5022.8  379.71  5047.4  379.21  5083.0  380.44  5160.6  388.94  5182.0  390.20
  5189.0  391.28  5203.1  391.03  5210.0  391.99  5239.0  393.38  5263.5  393.56
  5273.9  393.26  5280.8  394.29  5288.0  393.74  5294.9  394.48  5335.3  394.77
#Mann=8,-1,0
  4248.8    0.05       0  4712.6    0.16       0  4886.8    0.12       0
  5001.9    0.07       0  5007.9    0.12       0  5022.8    0.16       0
  5239.0    0.05       0  5263.5    0.16       0
Bank Sta=5001.9,5007.9
Exp/Cntr=0.3,0.1

Type RM Length L Ch R = 1,1834,1328,1328,1328
BEGIN DESCRIPTION:
UNT0690 IN SAND CR 1.0
END DESCRIPTION:
XS GIS Cut Line= 3
      3552892.11     10513341.65      3553492.11     10513941.64
      3553642.10     10514141.63
#Sta/Elev= 30
  4149.7  397.26  4220.4  391.92  4277.0  389.66  4305.3  387.65  4432.5  381.44
  4446.7  381.72  4503.2  380.41  4574.0  377.27  4672.9  376.87  4712.4  375.89
  4715.1  375.39  4718.4  375.89  4798.5  376.79  4801.0  376.78  4885.1  376.66
  4913.4  377.04  4933.0  376.75  4941.1  376.83  4984.1  377.99  4994.7  376.35
  5001.3  376.35  5011.8  378.05  5034.7  376.89  5123.6  376.26  5170.1  376.82
  5205.5  377.75  5220.1  378.72  5235.4  382.58  5245.1  386.33  5248.2  386.33
#Mann=9,-1,0
  4149.7    0.05       0  4712.4    0.07       0  4718.4    0.05       0
  4798.5    0.16       0  4801.0    0.12       0  4933.0    0.16       0
  4941.1    0.12       0  5123.6    0.16       0  5235.4     0.1       0
Bank Sta=4712.4,4718.4
Exp/Cntr=0.3,0.1

Type RM Length L Ch R = 1,506,0,0,0
BEGIN DESCRIPTION:
UNT0690 IN SAND CR 2.1
END DESCRIPTION:
XS GIS Cut Line= 4
      3552673.18     10513358.28      3552332.92     10514049.22
      3552343.34     10514240.19      3554068.10     10514438.00
#Sta/Elev= 30
  4183.3  387.00  4421.3  372.14  4424.9  371.99  4476.9  371.09  4576.7  371.78
  4733.2  369.78  5022.6  368.32  5025.4  367.82  5028.6  368.32  5222.8  368.91
  5455.5  368.61  5605.8  369.75  5888.3  371.99  5938.8  371.42  6037.8  372.39
  6136.9  373.71  6331.2  374.36  6411.8  373.56  6428.5  374.72  6472.1  375.12
  6552.7  379.12  6601.8  384.54  6606.8  383.40  6623.1  384.65  6663.4  383.43
  6691.0  386.33  6731.4  388.36  6814.4  391.38  6844.6  394.22  6880.8  395.15
#Mann=11,-1,0
  4183.3    0.05       0  4421.3    0.16       0  4424.9    0.05       0
  5022.6   0.035       0  5028.6    0.05       0  5222.8    0.16       0
  5605.8    0.05       0  5938.8    0.16       0  6037.8    0.05       0
  6136.9    0.16       0  6731.4    0.05       0
Bank Sta=5022.6,5028.6
Exp/Cntr=0.3,0.1

Chan Stop Cuts=-1