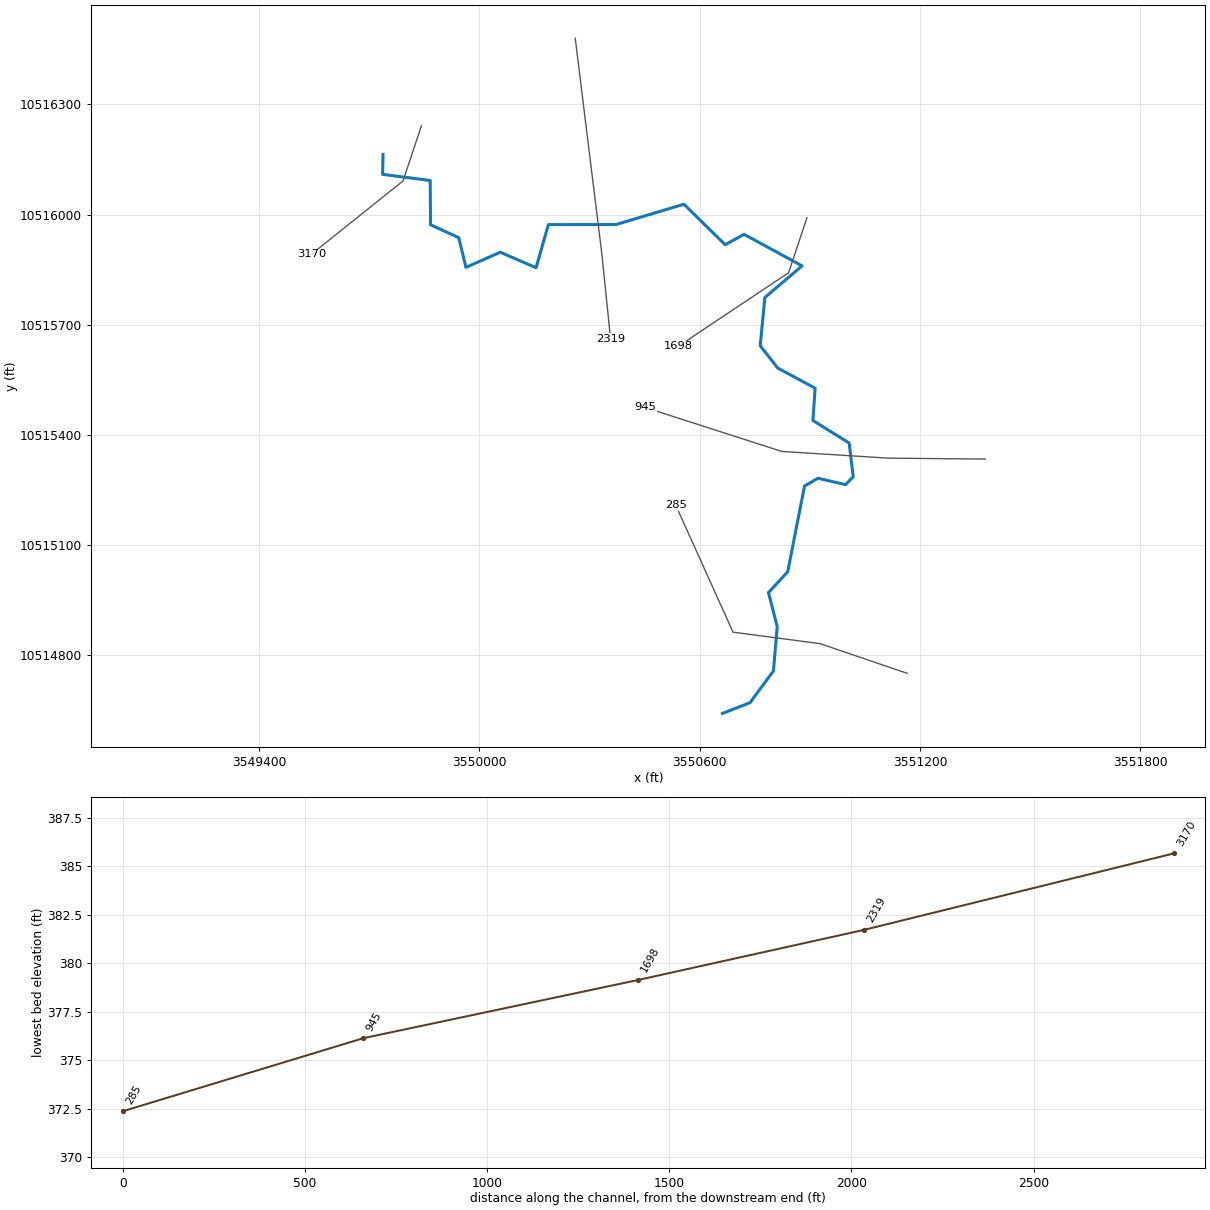
--- UNT0691 IN SAND CR.prj (project) ---

Proj Title=UNT0691 IN SAND CR Base Level Engineering
Current Plan=p01
Default Exp/Contr=0.3,0.1
English Units
Geom File=g01
Flow File=f01
Plan File=p01
BEGIN DESCRIPTION:
UNT0691 IN SAND CR
END DESCRIPTION:

--- UNT0691 IN SAND CR.p01 (plan) ---

Plan Title=Multiple Run
Short Identifier=Multiple
Geom File=g01
Flow File=f01
Subcritical Flow
K Sum by GR= 0
Std Step Tol= 0.01
Critical Tol= 0.01
Num of Std Step Trials= 20
Max Error Tol= 0.3
Flow Tol Ratio= 0.001
Split Flow NTrial= 30
Split Flow Tol= 0.02
Split Flow Ratio= 0.02
Log Output Level= 0
Friction Slope Method= 1
Unsteady Friction Slope Method= 2
Unsteady Bridges Friction Slope Method= 1
Parabolic Critical Depth
Global Vel Dist=  1 , 1 , 1
Global Log Level= 0
CheckData=True
Encroach Param= -1, 0, 0, 0
BEGIN DESCRIPTION:
Multiple Run
END DESCRIPTION:

--- UNT0691 IN SAND CR.f01 (steady flow) ---

Flow Title=Multiple
Number of Profiles=7
Profile Names=10-year,25-year,50-year,1pct_min,100-year,1pct_plu,500-year
River Rch & RM= UNT0691 IN SAND ,Reach-1,3170
     554     731     869     756    1023    1383    1409
Boundary for River Rch & Prof#=UNT0691 IN SAND ,Reach-1,1
Up Type=0
Dn Type=3
Dn Slope=0.005
Boundary for River Rch & Prof#=UNT0691 IN SAND ,Reach-1,2
Up Type=0
Dn Type=3
Dn Slope=0.005
Boundary for River Rch & Prof#=UNT0691 IN SAND ,Reach-1,3
Up Type=0
Dn Type=3
Dn Slope=0.005
Boundary for River Rch & Prof#=UNT0691 IN SAND ,Reach-1,4
Up Type=0
Dn Type=3
Dn Slope=0.005
Boundary for River Rch & Prof#=UNT0691 IN SAND ,Reach-1,5
Up Type=0
Dn Type=3
Dn Slope=0.005
Boundary for River Rch & Prof#=UNT0691 IN SAND ,Reach-1,6
Up Type=0
Dn Type=3
Dn Slope=0.005
Boundary for River Rch & Prof#=UNT0691 IN SAND ,Reach-1,7
Up Type=0
Dn Type=3
Dn Slope=0.005

--- UNT0691 IN SAND CR.g01 (geometry) ---

Geom Title=Existing Conditions

River Reach=UNT0691 IN SAND ,Reach-1
Reach XY= 30
      3549737.51     10516164.00      3549736.55     10516109.57
      3549866.10     10516092.81      3549867.01     10515972.30
      3549943.76     10515937.19      3549963.42     10515856.36
      3550056.92     10515897.48      3550154.39     10515855.25
      3550187.91     10515972.71      3550372.07     10515972.88
      3550557.10     10516028.20      3550669.33     10515918.01
      3550720.83     10515946.21      3550878.85     10515860.31
      3550777.44     10515774.23      3550764.87     10515642.81
      3550812.15     10515582.35      3550914.28     10515527.30
      3550908.37     10515439.34      3551006.99     10515377.95
      3551018.16     10515286.06      3550997.24     10515264.55
      3550921.92     10515281.94      3550885.50     10515260.66
      3550839.69     10515027.25      3550787.33     10514970.61
      3550811.03     10514878.01      3550800.90     10514757.20
      3550736.80     10514670.62      3550662.11     10514641.64

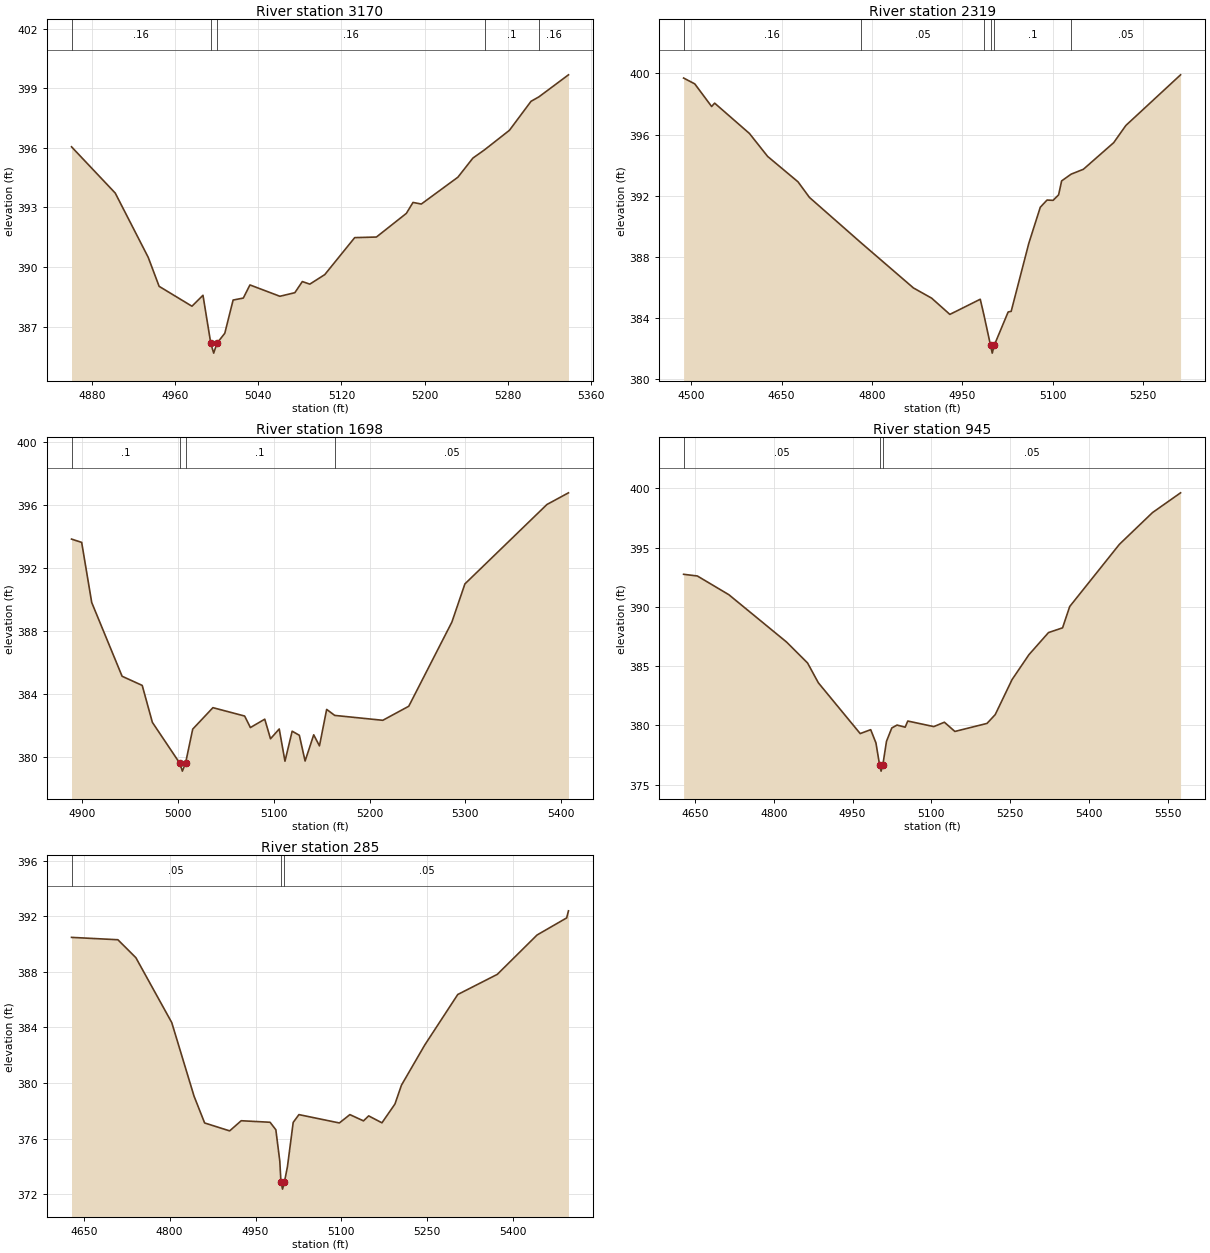
Type RM Length L Ch R = 1,3170,851,851,851
BEGIN DESCRIPTION:
UNT0691 IN SAND CR 6.0
END DESCRIPTION:
XS GIS Cut Line= 3
      3549842.10     10516241.62      3549792.11     10516091.64
      3549542.14     10515891.67
#Sta/Elev= 30
  4860.3  396.05  4902.4  393.72  4934.1  390.49  4944.6  389.03  4976.2  388.03
  4986.8  388.58  4994.3  386.17  4997.1  385.67  5000.3  386.17  5007.8  386.67
  5015.8  388.34  5025.6  388.44  5032.0  389.10  5060.8  388.53  5075.2  388.71
  5082.4  389.27  5089.6  389.14  5104.0  389.62  5132.8  391.48  5153.7  391.51
  5182.5  392.70  5188.9  393.25  5196.9  393.17  5232.1  394.52  5246.5  395.48
  5257.8  395.90  5281.7  396.88  5302.5  398.34  5310.0  398.56  5338.5  399.67
#Mann=5,-1,0
  4860.3    0.16       0  4994.3    0.07       0  5000.3    0.16       0
  5257.8     0.1       0  5310.0    0.16       0
Bank Sta=4994.3,5000.3
Exp/Cntr=0.3,0.1

Type RM Length L Ch R = 1,2319,621,621,621
BEGIN DESCRIPTION:
UNT0691 IN SAND CR 5.0
END DESCRIPTION:
XS GIS Cut Line= 3
      3550261.07     10516480.00      3550333.99     10515888.86
      3550357.26     10515661.27
#Sta/Elev= 30
  4487.6  399.69  4506.1  399.31  4534.1  397.83  4539.1  398.05  4596.8  396.07
  4627.0  394.57  4677.4  392.91  4696.4  391.89  4781.9  388.93  4868.8  385.98
  4899.1  385.31  4929.3  384.25  4979.7  385.24  4985.6  384.25  4996.8  382.22
  4999.6  381.72  5002.8  382.22  5026.0  384.41  5031.0  384.45  5060.3  388.90
  5079.3  391.25  5090.5  391.72  5100.5  391.70  5109.7  392.06  5114.7  392.97
  5130.4  393.41  5150.8  393.73  5201.1  395.47  5221.2  396.59  5312.0  399.90
#Mann=6,-1,0
  4487.6    0.16       0  4781.9    0.05       0  4985.6     0.1       0
  4996.8    0.07       0  5002.8     0.1       0  5130.4    0.05       0
Bank Sta=4996.8,5002.8
Exp/Cntr=0.3,0.1

Type RM Length L Ch R = 1,1698,753,753,753
BEGIN DESCRIPTION:
UNT0691 IN SAND CR 3.0
END DESCRIPTION:
XS GIS Cut Line= 3
      3550892.12     10515991.69      3550842.11     10515841.64
      3550542.12     10515641.65
#Sta/Elev= 30
  4888.9  393.83  4899.5  393.62  4910.0  389.81  4941.7  385.14  4962.7  384.56
  4973.3  382.22  5001.9  379.63  5004.6  379.13  5007.9  379.63  5015.4  381.79
  5036.5  383.15  5069.6  382.62  5075.6  381.89  5090.6  382.42  5096.6  381.18
  5105.7  381.80  5111.7  379.76  5119.2  381.66  5126.7  381.40  5132.7  379.77
  5141.7  381.43  5147.7  380.73  5155.2  383.04  5163.6  382.66  5213.8  382.35
  5240.9  383.24  5285.9  388.57  5299.5  390.99  5385.1  396.02  5407.6  396.76
#Mann=4,-1,0
  4888.9     0.1       0  5001.9    0.07       0  5007.9     0.1       0
  5163.6    0.05       0
Bank Sta=5001.9,5007.9
Exp/Cntr=0.3,0.1

Type RM Length L Ch R = 1,945,660,660,660
BEGIN DESCRIPTION:
UNT0691 IN SAND CR 2.0
END DESCRIPTION:
XS GIS Cut Line= 4
      3551378.21     10515334.17      3551112.63     10515336.78
      3550823.57     10515355.00      3550451.19     10515474.79
#Sta/Elev= 30
  4628.2  392.75  4654.3  392.61  4714.3  391.03  4824.3  387.03  4864.3  385.26
  4884.8  383.59  4964.5  379.30  4984.5  379.63  4994.5  378.51  5001.5  376.63
  5004.3  376.13  5007.5  376.63  5014.6  378.65  5024.6  379.77  5034.6  380.02
  5050.1  379.84  5055.1  380.36  5104.7  379.89  5124.8  380.26  5144.8  379.48
  5206.0  380.16  5221.6  380.90  5253.7  383.86  5285.8  385.96  5323.1  387.83
  5349.9  388.23  5363.5  390.03  5458.1  395.28  5521.1  397.96  5574.6  399.63
#Mann=3,-1,0
  4628.2    0.05       0  5001.5    0.03       0  5007.5    0.05       0
Bank Sta=5001.5,5007.5
Exp/Cntr=0.3,0.1

Type RM Length L Ch R = 1,285,0,0,0
BEGIN DESCRIPTION:
UNT0691 IN SAND CR 1.0
END DESCRIPTION:
XS GIS Cut Line= 4
      3551164.71     10514750.84      3550927.74     10514831.57
      3550690.76     10514862.82      3550535.06     10515207.94
#Sta/Elev= 30
  4628.6  390.47  4709.6  390.30  4741.0  389.01  4803.7  384.34  4842.6  379.05
  4861.1  377.12  4904.8  376.55  4925.0  377.28  4975.4  377.17  4985.5  376.63
  4992.4  374.37  4994.4  372.86  4997.2  372.36  5000.4  372.86  5005.7  373.96
  5015.8  377.16  5025.8  377.72  5096.4  377.12  5114.8  377.72  5138.6  377.27
  5147.6  377.63  5170.8  377.13  5193.5  378.48  5204.9  379.84  5245.6  382.73
  5303.2  386.36  5372.3  387.81  5441.7  390.64  5493.4  391.87  5496.6  392.38
#Mann=3,-1,0
  4628.6    0.05       0  4994.4    0.03       0  5000.4    0.05       0
Bank Sta=4994.4,5000.4
Exp/Cntr=0.3,0.1

Chan Stop Cuts=-1