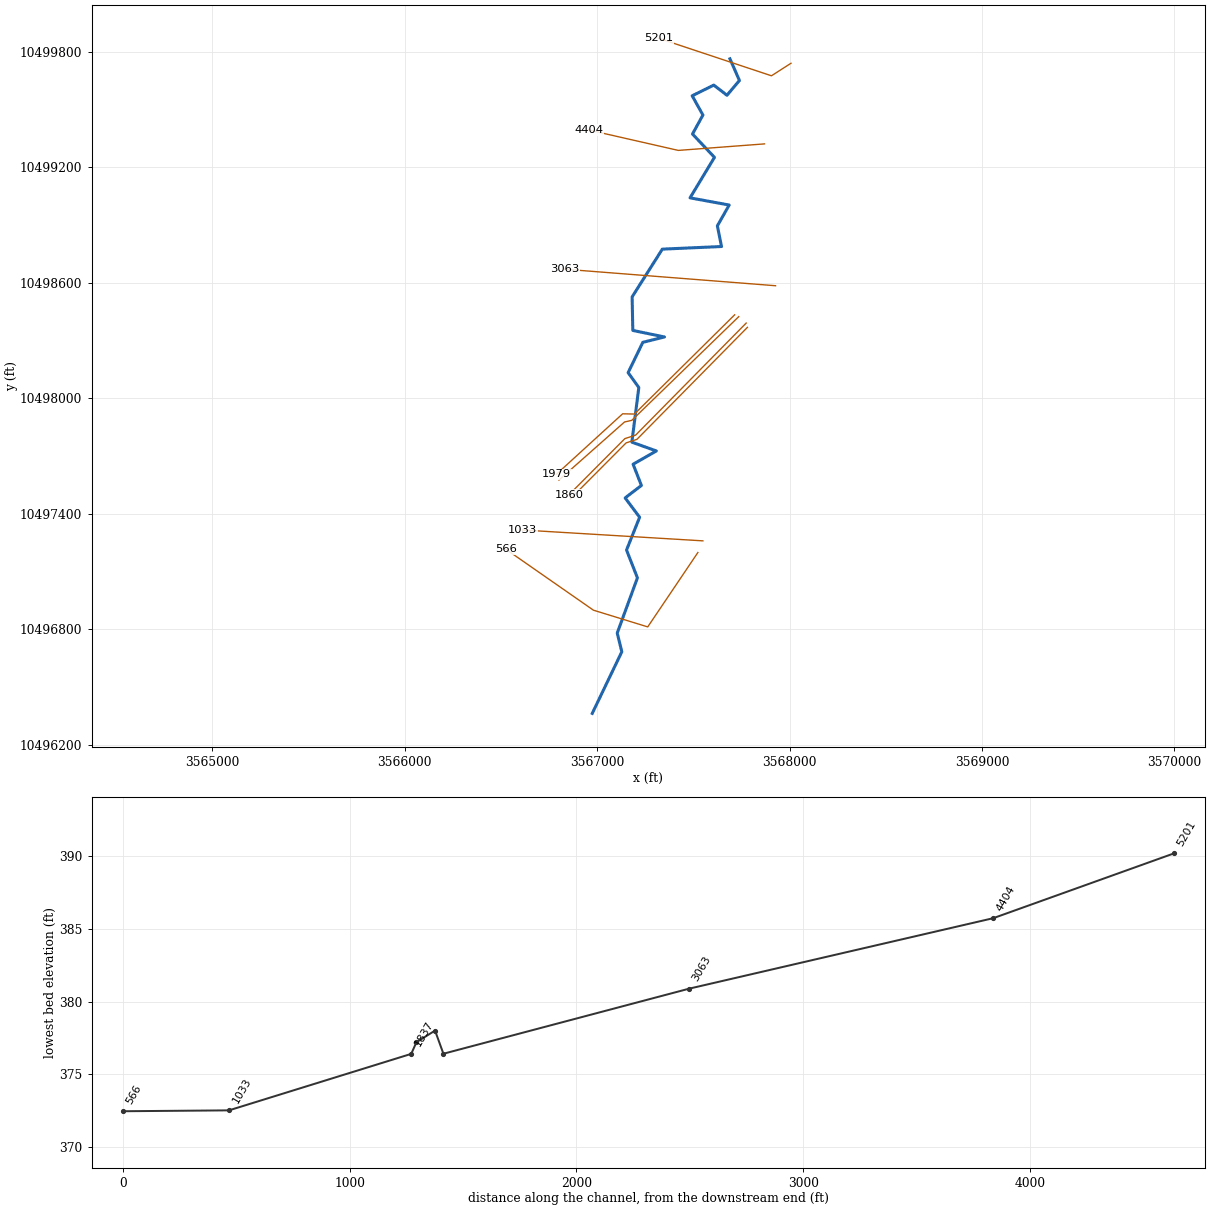
--- UNT0716 IN SAND CR.prj (project) ---

Proj Title=UNT0716 IN SAND CR Base Level Engineering
Current Plan=p01
Default Exp/Contr=0.3,0.1
English Units
Geom File=g01
Flow File=f01
Plan File=p01
BEGIN DESCRIPTION:
UNT0716 IN SAND CR
END DESCRIPTION:

--- UNT0716 IN SAND CR.p01 (plan) ---

Plan Title=Multiple Run
Short Identifier=Multiple
Geom File=g01
Flow File=f01
Subcritical Flow
K Sum by GR= 0
Std Step Tol= 0.01
Critical Tol= 0.01
Num of Std Step Trials= 20
Max Error Tol= 0.3
Flow Tol Ratio= 0.001
Split Flow NTrial= 30
Split Flow Tol= 0.02
Split Flow Ratio= 0.02
Log Output Level= 0
Friction Slope Method= 1
Unsteady Friction Slope Method= 2
Unsteady Bridges Friction Slope Method= 1
Parabolic Critical Depth
Global Vel Dist=  1 , 1 , 1
Global Log Level= 0
CheckData=True
Encroach Param= -1, 0, 0, 0
BEGIN DESCRIPTION:
Multiple Run
END DESCRIPTION:

--- UNT0716 IN SAND CR.f01 (steady flow) ---

Flow Title=Multiple
Number of Profiles=7
Profile Names=10-year,25-year,50-year,1pct_min,100-year,1pct_plu,500-year
River Rch & RM= UNT0716 IN SAND ,Reach-1,5201
     817    1109    1348    1197    1618    2188    2323
Boundary for River Rch & Prof#=UNT0716 IN SAND ,Reach-1,1
Up Type=0
Dn Type=3
Dn Slope=0.005
Boundary for River Rch & Prof#=UNT0716 IN SAND ,Reach-1,2
Up Type=0
Dn Type=3
Dn Slope=0.005
Boundary for River Rch & Prof#=UNT0716 IN SAND ,Reach-1,3
Up Type=0
Dn Type=3
Dn Slope=0.005
Boundary for River Rch & Prof#=UNT0716 IN SAND ,Reach-1,4
Up Type=0
Dn Type=3
Dn Slope=0.005
Boundary for River Rch & Prof#=UNT0716 IN SAND ,Reach-1,5
Up Type=0
Dn Type=3
Dn Slope=0.005
Boundary for River Rch & Prof#=UNT0716 IN SAND ,Reach-1,6
Up Type=0
Dn Type=3
Dn Slope=0.005
Boundary for River Rch & Prof#=UNT0716 IN SAND ,Reach-1,7
Up Type=0
Dn Type=3
Dn Slope=0.005

--- UNT0716 IN SAND CR.g01 (geometry) ---

Geom Title=Existing Conditions

River Reach=UNT0716 IN SAND ,Reach-1
Reach XY= 30
      3567690.28     10499763.95      3567739.75     10499651.33
      3567674.82     10499574.64      3567606.40     10499627.47
      3567494.16     10499571.80      3567549.98     10499471.82
      3567495.84     10499373.17      3567609.98     10499251.99
      3567483.03     10499041.59      3567686.36     10499004.24
      3567624.90     10498896.03      3567646.73     10498788.74
      3567339.15     10498775.13      3567182.19     10498527.11
      3567185.67     10498352.80      3567350.25     10498318.77
      3567237.75     10498291.00      3567161.36     10498133.36
      3567216.92     10498056.28      3567180.80     10497772.25
      3567308.17     10497726.57      3567187.11     10497657.65
      3567230.37     10497547.44      3567145.88     10497482.55
      3567221.10     10497382.17      3567153.07     10497211.91
      3567209.70     10497067.16      3567104.76     10496780.38
      3567128.61     10496683.29      3566975.00     10496363.19

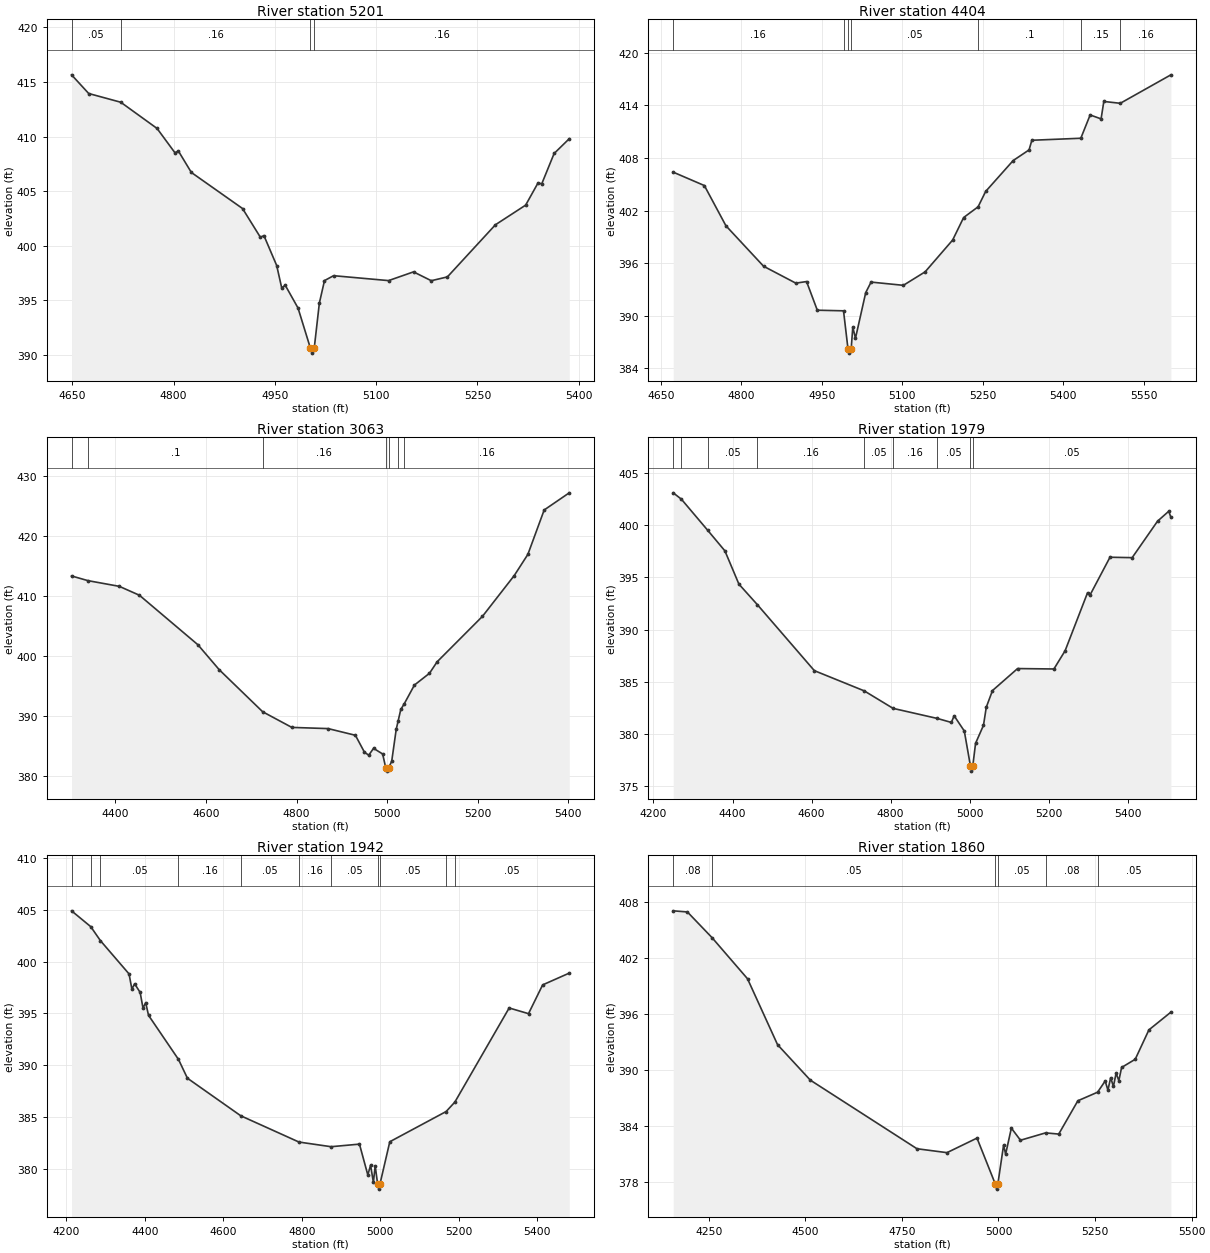
Type RM Length L Ch R = 1,5201,797,797,797
BEGIN DESCRIPTION:
UNT0716 IN SAND CR 9.0
END DESCRIPTION:
XS GIS Cut Line= 3
      3568007.58     10499740.90      3567906.01     10499675.79
      3567320.85     10499870.34
#Sta/Elev= 30
  4648.7  415.66  4674.1  413.95  4721.6  413.15  4775.4  410.75  4801.8  408.53
  4807.0  408.68  4826.2  406.72  4902.0  403.42  4928.4  400.79  4933.7  400.94
  4952.6  398.20  4960.0  396.16  4965.3  396.39  4984.2  394.31  5002.3  390.68
  5005.1  390.18  5008.3  390.68  5015.8  394.76  5023.4  396.82  5036.9  397.27
  5118.3  396.82  5155.3  397.62  5181.6  396.81  5205.5  397.16  5276.6  401.93
  5321.4  403.73  5339.9  405.78  5345.2  405.67  5363.6  408.46  5386.0  409.81
#Mann=4,-1,0
  4648.7    0.05       0  4721.6    0.16       0  5002.3    0.07       0
  5008.3    0.16       0
Bank Sta=5002.3,5008.3
Exp/Cntr=0.3,0.1

Type RM Length L Ch R = 1,4404,1341,1341,1341
BEGIN DESCRIPTION:
UNT0716 IN SAND CR 8.0
END DESCRIPTION:
XS GIS Cut Line= 3
      3567870.09     10499321.95      3567422.17     10499288.10
      3566955.23     10499394.46
#Sta/Elev= 30
  4672.8  406.39  4730.9  404.86  4771.1  400.27  4841.3  395.65  4901.4  393.72
  4921.5  393.90  4941.5  390.63  4990.4  390.56  4998.7  386.23  5001.5  385.73
  5004.7  386.23  5007.7  388.70  5012.7  387.43  5031.8  392.64  5041.8  393.84
  5102.0  393.47  5142.6  395.01  5193.9  398.64  5214.4  401.21  5241.3  402.43
  5255.5  404.19  5306.7  407.71  5336.4  408.93  5341.6  410.03  5432.9  410.26
  5450.3  412.92  5470.7  412.47  5475.8  414.46  5506.5  414.25  5600.9  417.50
#Mann=7,-1,0
  4672.8    0.16       0  4990.4    0.05       0  4998.7   0.035       0
  5004.7    0.05       0  5241.3     0.1       0  5432.9    0.15       0
  5506.5    0.16       0
Bank Sta=4998.7,5004.7
Exp/Cntr=0.3,0.1

Type RM Length L Ch R = 1,3063,1084,1084,1084
BEGIN DESCRIPTION:
UNT0716 IN SAND CR 6.0
END DESCRIPTION:
XS GIS Cut Line= 2
      3567927.36     10498584.97      3566831.02     10498670.91
#Sta/Elev= 30
  4302.9  413.34  4339.1  412.56  4408.5  411.61  4452.9  410.13  4582.1  401.90
  4629.2  397.75  4725.2  390.76  4789.6  388.16  4869.9  387.96  4930.1  386.85
  4950.1  384.03  4959.6  383.54  4970.2  384.68  4990.3  383.74  4997.3  381.39
  5000.0  380.89  5003.3  381.39  5010.3  382.53  5020.3  387.85  5024.4  389.19
  5030.4  391.15  5037.9  392.07  5060.5  395.20  5093.8  397.16  5110.6  399.06
  5210.9  406.63  5281.1  413.41  5311.2  416.93  5347.2  424.31  5402.6  427.16
#Mann=7,-1,0
  4302.9    0.08       0  4339.1     0.1       0  4725.2    0.16       0
  4997.3    0.07       0  5003.3    0.16       0  5024.4     0.1       0
  5037.9    0.16       0
Bank Sta=4997.3,5003.3
Exp/Cntr=0.3,0.1

Type RM Length L Ch R = 1,1979,37,37,37
BEGIN DESCRIPTION:
UNT0716 IN SAND CR 5.1
END DESCRIPTION:
XS GIS Cut Line= 4
      3567714.81     10498433.91      3567193.99     10497918.31
      3567132.80     10497919.61      3566789.51     10497606.23
#Sta/Elev= 30
  4250.0  403.12  4270.7  402.51  4337.6  399.51  4380.8  397.55  4416.2  394.36
  4463.1  392.38  4607.0  386.06  4733.2  384.12  4806.2  382.44  4918.5  381.47
  4953.6  381.09  4960.6  381.73  4986.3  380.27  5001.8  376.92  5004.5  376.42
  5007.8  376.92  5014.8  379.09  5034.8  380.81  5041.9  382.55  5057.6  384.15
  5121.1  386.26  5213.0  386.22  5241.3  387.97  5298.1  393.54  5304.8  393.35
  5354.8  396.94  5410.9  396.90  5475.1  400.40  5503.4  401.35  5508.9  400.77
#Mann=9,-1,0
  4250.0    0.08       0  4270.7    0.16       0  4337.6    0.05       0
  4463.1    0.16       0  4733.2    0.05       0  4806.2    0.16       0
  4918.5    0.05       0  5001.8    0.04       0  5007.8    0.05       0
Bank Sta=5001.8,5007.8
Exp/Cntr=0.3,0.1

Type RM Length L Ch R = 1,1942,82,82,82
BEGIN DESCRIPTION:
UNT0716 IN SAND CR 5.0
END DESCRIPTION:
XS GIS Cut Line= 4
      3567736.36     10498424.67      3567180.54     10497885.75
      3567142.56     10497877.07      3566802.06     10497575.49
#Sta/Elev= 30
  4213.6  404.91  4262.5  403.38  4287.1  402.03  4360.1  398.81  4367.3  397.34
  4374.3  397.86  4388.4  397.02  4395.6  395.51  4402.5  396.03  4409.7  394.81
  4486.0  390.55  4508.8  388.73  4644.7  385.10  4793.0  382.56  4874.8  382.11
  4947.1  382.36  4968.4  379.38  4975.4  380.32  4982.6  378.67  4987.2  380.26
  4993.4  378.51  4996.2  378.01  4999.4  378.51  5024.4  382.59  5167.9  385.51
  5190.1  386.42  5328.5  395.52  5377.8  394.97  5413.8  397.75  5481.6  398.89
#Mann=11,-1,0
  4213.6    0.08       0  4262.5    0.16       0  4287.1    0.05       0
  4486.0    0.16       0  4644.7    0.05       0  4793.0    0.16       0
  4874.8    0.05       0  4993.4    0.04       0  4999.4    0.05       0
  5167.9    0.08       0  5190.1    0.05       0
Bank Sta=4993.4,4999.4
Exp/Cntr=0.3,0.1

Type RM Length L Ch R = 1,1860,23,23,23
BEGIN DESCRIPTION:
UNT0716 IN SAND CR 4.0
END DESCRIPTION:
XS GIS Cut Line= 4
      3567774.72     10498390.96      3567200.50     10497808.93
      3567144.51     10497790.70      3566854.18     10497499.07
#Sta/Elev= 30
  4158.3  407.04  4195.0  406.92  4258.9  404.16  4350.6  399.76  4428.4  392.69
  4513.2  388.89  4789.1  381.54  4866.8  381.12  4944.5  382.68  4992.3  377.71
  4995.0  377.21  4998.3  377.71  5013.3  381.93  5018.6  380.96  5033.4  383.75
  5057.0  382.45  5122.0  383.24  5156.0  383.11  5205.5  386.68  5256.6  387.60
  5276.2  388.80  5283.3  387.82  5290.4  389.15  5297.5  388.22  5304.5  389.63
  5311.6  388.84  5318.7  390.25  5354.0  391.13  5389.4  394.28  5446.3  396.18
#Mann=6,-1,0
  4158.3    0.08       0  4258.9    0.05       0  4992.3    0.04       0
  4998.3    0.05       0  5122.0    0.08       0  5256.6    0.05       0
Bank Sta=4992.3,4998.3
Exp/Cntr=0.3,0.1

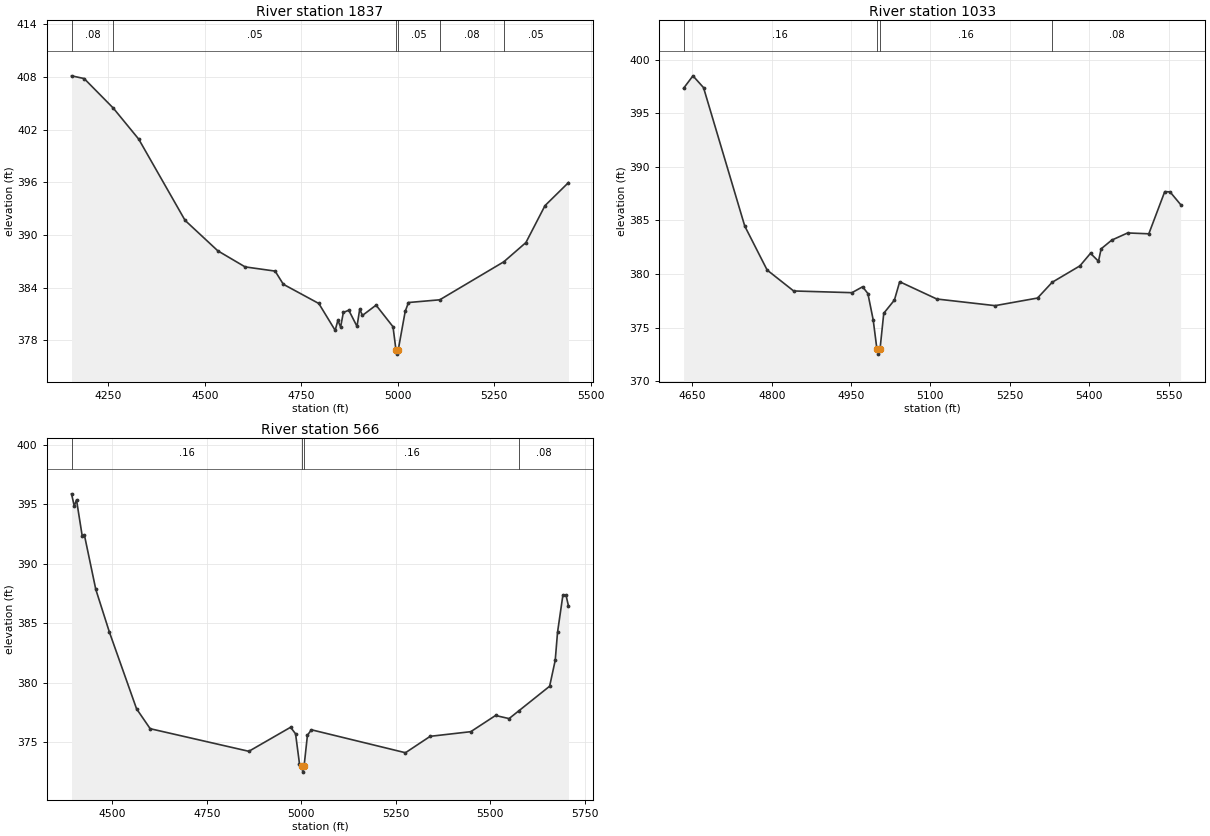
Type RM Length L Ch R = 1,1837,804,804,804
BEGIN DESCRIPTION:
UNT0716 IN SAND CR 4.1
END DESCRIPTION:
XS GIS Cut Line= 4
      3567781.20     10498368.79      3567207.01     10497786.80
      3567151.02     10497768.57      3566860.66     10497476.90
#Sta/Elev= 30
  4154.2  408.12  4186.9  407.81  4262.5  404.44  4328.3  400.91  4448.5  391.65
  4533.4  388.18  4604.1  386.35  4681.9  385.87  4703.1  384.37  4795.1  382.18
  4837.5  379.12  4844.5  380.26  4851.6  379.50  4858.7  381.16  4872.8  381.41
  4894.1  379.57  4901.1  381.53  4908.2  380.82  4943.5  381.99  4987.4  379.53
  4995.0  376.91  4997.7  376.41  5001.0  376.91  5019.0  381.28  5027.5  382.29
  5108.6  382.60  5274.5  386.93  5331.8  389.12  5381.3  393.33  5442.2  395.96
#Mann=6,-1,0
  4154.2    0.08       0  4262.5    0.05       0  4995.0    0.04       0
  5001.0    0.05       0  5108.6    0.08       0  5274.5    0.05       0
Bank Sta=4995,5001
Exp/Cntr=0.3,0.1

Type RM Length L Ch R = 1,1033,467,467,467
BEGIN DESCRIPTION:
UNT0716 IN SAND CR 2.0
END DESCRIPTION:
XS GIS Cut Line= 2
      3567549.76     10497259.54      3566612.26     10497315.96
#Sta/Elev= 30
  4633.5  397.32  4651.2  398.48  4671.2  397.38  4749.1  384.47  4791.4  380.37
  4841.5  378.42  4951.7  378.26  4971.8  378.81  4981.8  378.18  4991.8  375.73
  4998.8  373.03  5001.6  372.53  5004.8  373.03  5011.8  376.34  5031.9  377.57
  5041.9  379.28  5112.0  377.67  5222.2  377.05  5302.4  377.76  5330.1  379.23
  5382.5  380.76  5402.5  381.93  5417.6  381.19  5422.6  382.35  5442.6  383.16
  5472.7  383.83  5512.7  383.75  5542.8  387.68  5552.8  387.66  5572.7  386.48
#Mann=4,-1,0
  4633.5    0.16       0  4998.8    0.07       0  5004.8    0.16       0
  5330.1    0.08       0
Bank Sta=4998.8,5004.8
Exp/Cntr=0.3,0.1

Type RM Length L Ch R = 1,566,0,0,0
BEGIN DESCRIPTION:
UNT0716 IN SAND CR 1.0
END DESCRIPTION:
XS GIS Cut Line= 5
      3567523.70     10497198.80      3567263.26     10496812.49
      3566981.15     10496899.30      3566538.44     10497207.45
      3566526.63     10497215.39
#Sta/Elev= 30
  4391.9  395.86  4399.1  394.84  4405.1  395.35  4420.1  392.34  4426.1  392.38
  4456.1  387.83  4492.1  384.24  4564.0  377.79  4600.0  376.12  4861.0  374.22
  4971.4  376.24  4984.6  375.69  4995.0  373.16  5001.1  372.97  5003.8  372.47
  5007.1  372.97  5016.0  375.57  5026.4  376.03  5275.3  374.10  5340.8  375.48
  5448.1  375.87  5513.6  377.23  5549.4  376.97  5575.1  377.62  5656.7  379.69
  5671.5  381.87  5677.6  384.22  5691.7  387.33  5700.0  387.34  5706.6  386.43
#Mann=4,-1,0
  4391.9    0.16       0  5001.1    0.07       0  5007.1    0.16       0
  5575.1    0.08       0
Bank Sta=5001.1,5007.1
Exp/Cntr=0.3,0.1

Chan Stop Cuts=-1