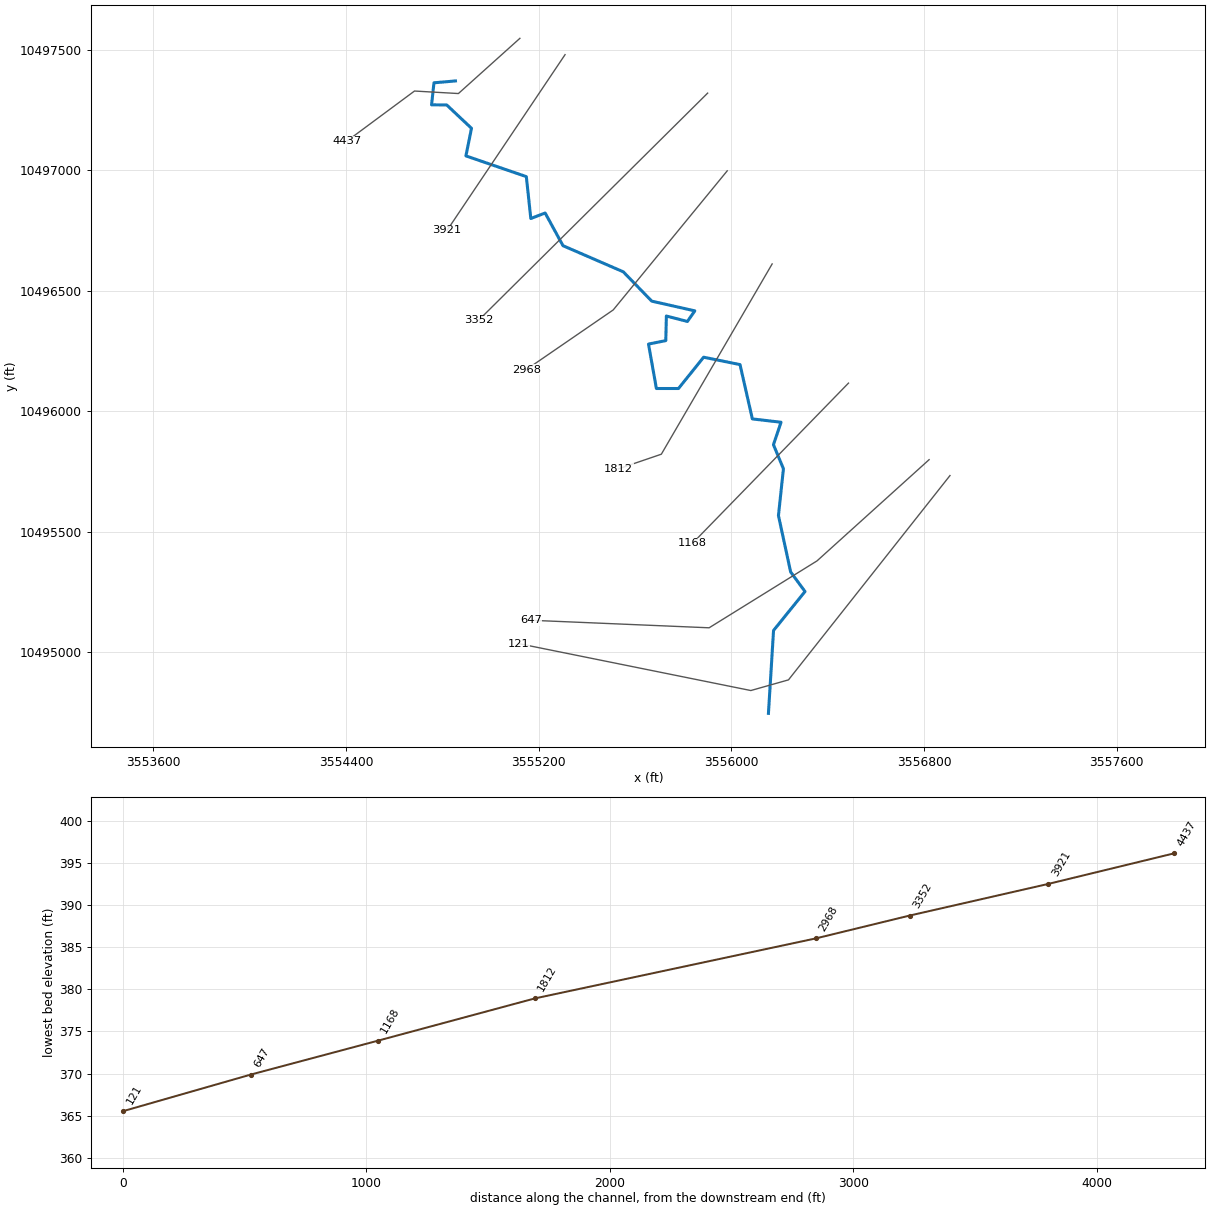
--- UNT0722 IN SAND CR.prj (project) ---

Proj Title=UNT0722 IN SAND CR Base Level Engineering
Current Plan=p01
Default Exp/Contr=0.3,0.1
English Units
Geom File=g01
Flow File=f01
Plan File=p01
BEGIN DESCRIPTION:
UNT0722 IN SAND CR
END DESCRIPTION:

--- UNT0722 IN SAND CR.p01 (plan) ---

Plan Title=Multiple Run
Short Identifier=Multiple
Geom File=g01
Flow File=f01
Subcritical Flow
K Sum by GR= 0
Std Step Tol= 0.01
Critical Tol= 0.01
Num of Std Step Trials= 20
Max Error Tol= 0.3
Flow Tol Ratio= 0.001
Split Flow NTrial= 30
Split Flow Tol= 0.02
Split Flow Ratio= 0.02
Log Output Level= 0
Friction Slope Method= 1
Unsteady Friction Slope Method= 2
Unsteady Bridges Friction Slope Method= 1
Parabolic Critical Depth
Global Vel Dist=  1 , 1 , 1
Global Log Level= 0
CheckData=True
Encroach Param= -1, 0, 0, 0
BEGIN DESCRIPTION:
Multiple Run
END DESCRIPTION:

--- UNT0722 IN SAND CR.f01 (steady flow) ---

Flow Title=Multiple
Number of Profiles=7
Profile Names=10-year,25-year,50-year,1pct_min,100-year,1pct_plu,500-year
River Rch & RM= UNT0722 IN SAND ,Reach-1,4437
     686     924    1118     988    1337    1808    1904
Boundary for River Rch & Prof#=UNT0722 IN SAND ,Reach-1,1
Up Type=0
Dn Type=3
Dn Slope=0.005
Boundary for River Rch & Prof#=UNT0722 IN SAND ,Reach-1,2
Up Type=0
Dn Type=3
Dn Slope=0.005
Boundary for River Rch & Prof#=UNT0722 IN SAND ,Reach-1,3
Up Type=0
Dn Type=3
Dn Slope=0.005
Boundary for River Rch & Prof#=UNT0722 IN SAND ,Reach-1,4
Up Type=0
Dn Type=3
Dn Slope=0.005
Boundary for River Rch & Prof#=UNT0722 IN SAND ,Reach-1,5
Up Type=0
Dn Type=3
Dn Slope=0.005
Boundary for River Rch & Prof#=UNT0722 IN SAND ,Reach-1,6
Up Type=0
Dn Type=3
Dn Slope=0.005
Boundary for River Rch & Prof#=UNT0722 IN SAND ,Reach-1,7
Up Type=0
Dn Type=3
Dn Slope=0.005

--- UNT0722 IN SAND CR.g01 (geometry) ---

Geom Title=Existing Conditions

River Reach=UNT0722 IN SAND ,Reach-1
Reach XY= 30
      3554854.49     10497371.51      3554765.28     10497363.86
      3554755.32     10497272.34      3554818.20     10497271.82
      3554921.12     10497174.88      3554897.92     10497060.40
      3555148.71     10496974.31      3555167.35     10496800.46
      3555226.84     10496823.34      3555300.80     10496687.68
      3555551.14     10496579.19      3555669.30     10496457.44
      3555848.10     10496417.14      3555817.35     10496373.08
      3555730.08     10496395.69      3555727.65     10496293.60
      3555655.86     10496279.21      3555688.66     10496094.74
      3555780.31     10496094.76      3555884.72     10496224.68
      3556035.79     10496194.01      3556086.99     10495968.55
      3556206.06     10495954.71      3556174.51     10495861.52
      3556216.01     10495761.55      3556195.30     10495567.35
      3556245.96     10495333.13      3556305.53     10495252.05
      3556174.96     10495090.44      3556153.74     10494746.20

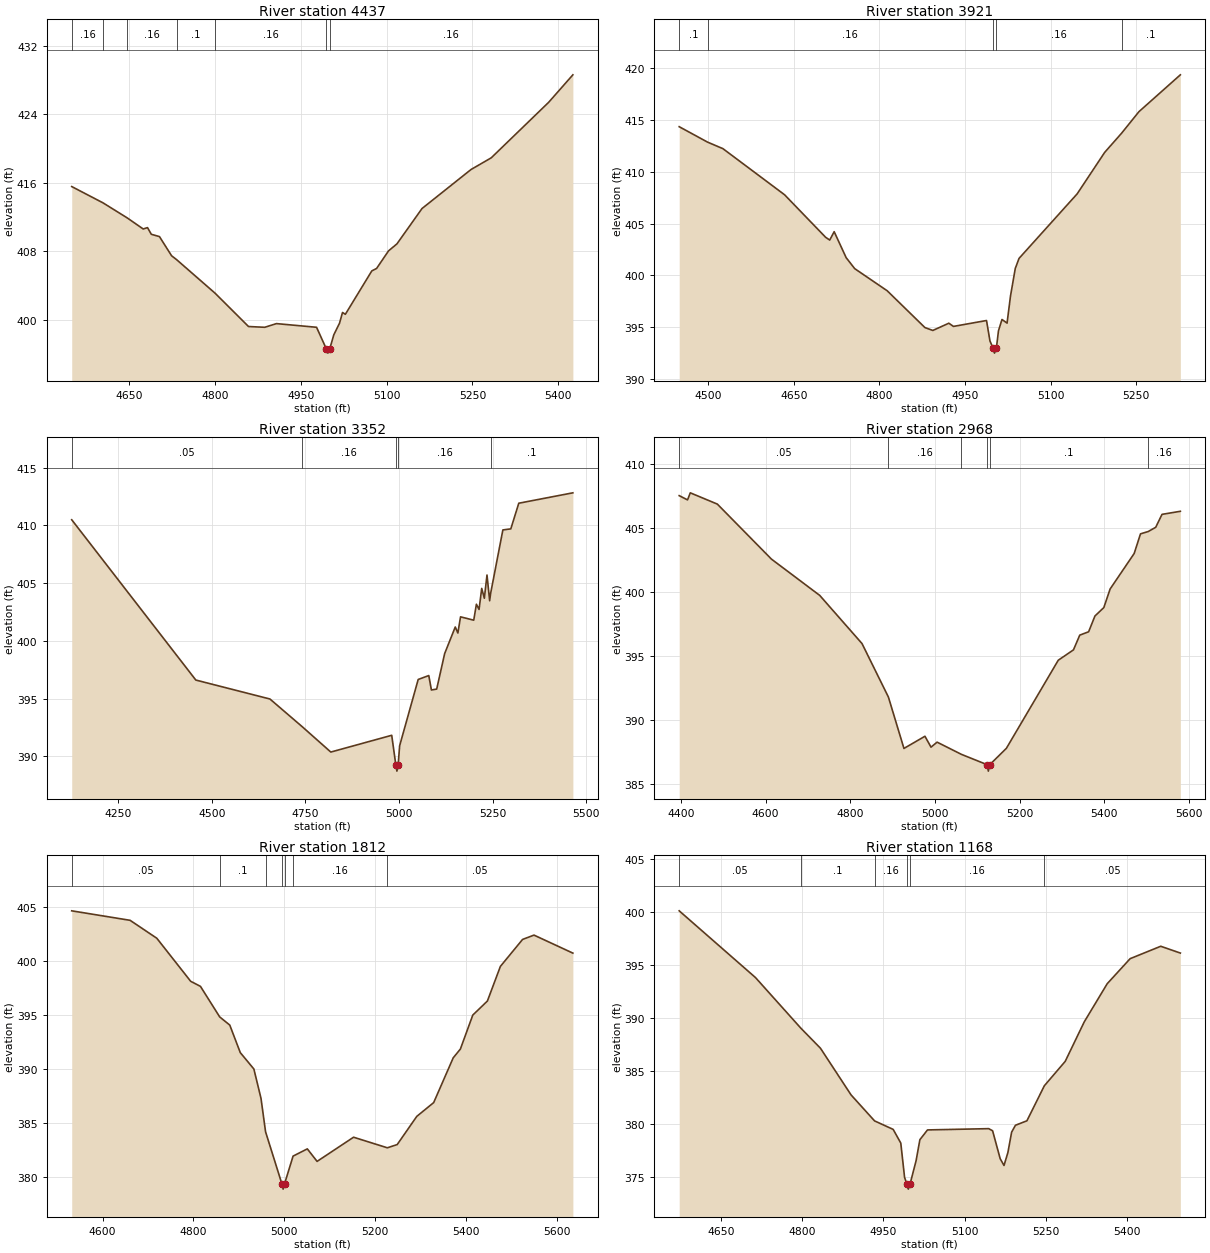
Type RM Length L Ch R = 1,4437,516,516,516
BEGIN DESCRIPTION:
UNT0722 IN SAND CR 8.0
END DESCRIPTION:
XS GIS Cut Line= 4
      3555121.98     10497548.39      3554866.76     10497319.21
      3554684.47     10497329.63      3554403.22     10497121.30
#Sta/Elev= 30
  4549.9  415.57  4604.7  413.66  4647.0  411.90  4674.8  410.61  4682.3  410.77
  4689.0  409.99  4703.2  409.72  4724.4  407.48  4733.1  407.03  4800.6  403.09
  4858.8  399.21  4887.1  399.12  4907.6  399.55  4977.7  399.12  4994.7  396.60
  4997.5  396.10  5000.7  396.60  5007.8  398.24  5017.8  399.60  5023.0  400.85
  5028.0  400.64  5074.2  405.71  5082.6  406.00  5103.4  408.05  5118.1  408.87
  5161.9  413.00  5247.5  417.56  5282.9  418.93  5383.1  425.41  5425.5  428.63
#Mann=7,-1,0
  4549.9    0.16       0  4604.7     0.1       0  4647.0    0.16       0
  4733.1     0.1       0  4800.6    0.16       0  4994.7    0.07       0
  5000.7    0.16       0
Bank Sta=4994.7,5000.7
Exp/Cntr=0.3,0.1

Type RM Length L Ch R = 1,3921,569,569,569
BEGIN DESCRIPTION:
UNT0722 IN SAND CR 8.1
END DESCRIPTION:
XS GIS Cut Line= 2
      3555309.47     10497480.67      3554819.87     10496751.48
#Sta/Elev= 30
  4449.2  414.35  4498.9  412.86  4525.8  412.23  4633.8  407.78  4705.8  403.67
  4713.0  403.40  4720.8  404.21  4741.8  401.70  4756.8  400.64  4813.8  398.50
  4879.8  394.95  4893.7  394.67  4921.8  395.37  4929.8  395.06  4987.8  395.63
  4993.8  393.66  4999.1  392.98  5001.8  392.48  5005.1  392.98  5008.8  394.65
  5014.9  395.73  5023.8  395.38  5029.8  397.99  5038.2  400.66  5044.8  401.63
  5146.6  407.86  5194.9  411.87  5224.5  413.72  5254.9  415.80  5327.5  419.36
#Mann=5,-1,0
  4449.2     0.1       0  4498.9    0.16       0  4999.1    0.07       0
  5005.1    0.16       0  5224.5     0.1       0
Bank Sta=4999.1,5005.1
Exp/Cntr=0.3,0.1

Type RM Length L Ch R = 1,3352,384,384,384
BEGIN DESCRIPTION:
UNT0722 IN SAND CR 7.0
END DESCRIPTION:
XS GIS Cut Line= 2
      3555901.45     10497321.07      3554950.95     10496378.38
#Sta/Elev= 30
  4125.8  410.48  4457.3  396.61  4655.3  394.97  4741.3  392.58  4817.9  390.38
  4980.6  391.83  4991.7  389.23  4994.4  388.73  4997.7  389.23  5001.7  390.92
  5051.3  396.66  5079.6  397.00  5086.6  395.75  5100.7  395.83  5122.0  398.90
  5150.3  401.20  5157.3  400.68  5164.4  402.08  5199.7  401.79  5206.8  403.17
  5213.9  402.72  5221.0  404.54  5228.0  403.69  5235.1  405.70  5242.2  403.47
  5244.8  404.11  5277.5  409.60  5298.7  409.69  5320.0  411.91  5464.5  412.81
#Mann=5,-1,0
  4125.8    0.05       0  4741.3    0.16       0  4991.7    0.07       0
  4997.7    0.16       0  5244.8     0.1       0
Bank Sta=4991.7,4997.7
Exp/Cntr=0.3,0.1

Type RM Length L Ch R = 1,2968,1156,1156,1156
BEGIN DESCRIPTION:
UNT0722 IN SAND CR 6.0
END DESCRIPTION:
XS GIS Cut Line= 3
      3555982.59     10496998.28      3555509.50     10496421.01
      3555149.23     10496173.61
#Sta/Elev= 30
  4396.1  407.52  4415.8  407.19  4422.3  407.74  4486.2  406.86  4613.9  402.57
  4727.9  399.74  4827.8  395.98  4890.1  391.81  4926.8  387.80  4976.4  388.75
  4990.7  387.90  5005.1  388.29  5062.4  387.34  5123.4  386.53  5126.1  386.03
  5129.4  386.53  5168.7  387.81  5291.2  394.68  5327.1  395.49  5342.0  396.64
  5362.9  396.90  5377.8  398.13  5398.8  398.79  5413.7  400.24  5470.5  403.01
  5485.4  404.54  5503.6  404.72  5521.3  405.05  5536.2  406.06  5579.5  406.30
#Mann=6,-1,0
  4396.1    0.05       0  4890.1    0.16       0  5062.4     0.1       0
  5123.4    0.07       0  5129.4     0.1       0  5503.6    0.16       0
Bank Sta=5123.4,5129.4
Exp/Cntr=0.3,0.1

Type RM Length L Ch R = 1,1812,644,644,644
BEGIN DESCRIPTION:
UNT0722 IN SAND CR 4.0
END DESCRIPTION:
XS GIS Cut Line= 3
      3556169.20     10496611.96      3555709.15     10495822.06
      3555531.24     10495761.31
#Sta/Elev= 30
  4532.3  404.69  4660.7  403.81  4719.4  402.15  4793.9  398.16  4815.4  397.69
  4857.7  394.86  4879.9  394.10  4903.0  391.55  4932.9  390.03  4948.6  387.30
  4958.6  384.21  4994.4  379.40  4997.2  378.90  5000.4  379.40  5019.1  381.96
  5050.4  382.63  5071.9  381.47  5152.1  383.71  5226.4  382.73  5248.1  383.03
  5291.1  385.64  5328.3  386.92  5371.3  391.07  5387.0  391.88  5414.3  395.03
  5446.4  396.33  5475.0  399.54  5523.8  402.04  5548.9  402.44  5634.4  400.77
#Mann=7,-1,0
  4532.3    0.05       0  4857.7     0.1       0  4958.6    0.05       0
  4994.4    0.03       0  5000.4    0.05       0  5019.1    0.16       0
  5226.4    0.05       0
Bank Sta=4994.4,5000.4
Exp/Cntr=0.3,0.1

Type RM Length L Ch R = 1,1168,521,521,521
BEGIN DESCRIPTION:
UNT0722 IN SAND CR 3.0
END DESCRIPTION:
XS GIS Cut Line= 2
      3556486.09     10496117.23      3555839.34     10495453.12
#Sta/Elev= 30
  4572.2  400.12  4713.3  393.83  4797.4  389.05  4833.5  387.17  4890.1  382.77
  4933.6  380.32  4968.0  379.52  4982.1  378.23  4989.1  374.99  4993.3  374.39
  4996.0  373.89  4999.3  374.39  5010.4  376.57  5017.4  378.55  5031.5  379.47
  5144.7  379.59  5151.9  379.39  5166.0  376.75  5173.0  376.12  5180.2  377.34
  5187.1  379.26  5194.2  379.91  5215.4  380.33  5247.6  383.63  5286.2  385.93
  5321.4  389.65  5363.9  393.25  5406.3  395.61  5462.9  396.78  5499.2  396.14
#Mann=6,-1,0
  4572.2    0.05       0  4797.4     0.1       0  4933.6    0.16       0
  4993.3    0.07       0  4999.3    0.16       0  5247.6    0.05       0
Bank Sta=4993.3,4999.3
Exp/Cntr=0.3,0.1

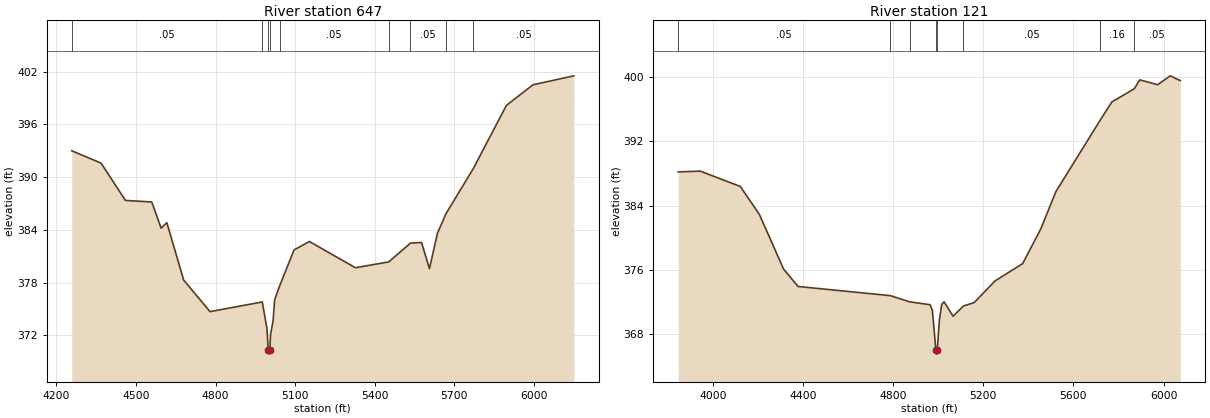
Type RM Length L Ch R = 1,647,526,526,526
BEGIN DESCRIPTION:
UNT0722 IN SAND CR 1.0
END DESCRIPTION:
XS GIS Cut Line= 4
      3556820.71     10495799.36      3556355.45     10495379.23
      3555907.53     10495101.46      3555167.92     10495132.71
#Sta/Elev= 30
  4257.7  392.99  4368.3  391.59  4460.2  387.35  4559.6  387.17  4594.7  384.20
  4616.4  384.82  4679.9  378.30  4779.3  374.71  4976.5  375.81  4994.4  372.73
  4998.8  370.38  5001.6  369.88  5004.8  370.38  5007.7  372.10  5017.2  373.67
  5023.1  376.06  5041.8  377.62  5096.3  381.72  5154.2  382.68  5327.8  379.70
  5453.4  380.36  5535.6  382.50  5577.2  382.57  5607.2  379.59  5637.3  383.62
  5669.6  385.84  5773.0  390.99  5897.5  398.15  5997.6  400.49  6151.9  401.51
#Mann=9,-1,0
  4257.7    0.05       0  4976.5    0.16       0  4998.8    0.07       0
  5004.8    0.16       0  5041.8    0.05       0  5453.4    0.16       0
  5535.6    0.05       0  5669.6    0.16       0  5773.0    0.05       0
Bank Sta=4998.8,5004.8
Exp/Cntr=0.3,0.1

Type RM Length L Ch R = 1,121,0,0,0
BEGIN DESCRIPTION:
UNT0722 IN SAND CR 1.01
END DESCRIPTION:
XS GIS Cut Line= 4
      3556907.30     10495733.39      3556236.93     10494885.28
      3556080.68     10494841.01      3555115.86     10495036.05
#Sta/Elev= 30
  3846.5  388.21  3944.0  388.31  4121.9  386.40  4206.8  382.91  4314.2  376.10
  4378.4  373.95  4787.5  372.81  4873.2  372.04  4964.1  371.68  4974.2  370.98
  4989.8  366.03  4992.6  365.53  4995.8  366.03  5005.3  369.79  5015.7  371.72
  5026.1  372.04  5065.9  370.25  5112.1  371.52  5159.9  371.95  5251.7  374.63
  5375.0  376.80  5455.8  381.15  5522.1  385.75  5719.0  394.66  5770.7  396.92
  5870.1  398.56  5894.5  399.67  5973.7  399.06  6029.5  400.17  6074.3  399.57
#Mann=8,-1,0
  3846.5    0.05       0  4787.5    0.16       0  4873.2    0.12       0
  4989.8    0.07       0  4995.8    0.12       0  5112.1    0.05       0
  5719.0    0.16       0  5870.1    0.05       0
Bank Sta=4989.8,4995.8
Exp/Cntr=0.3,0.1

Chan Stop Cuts=-1