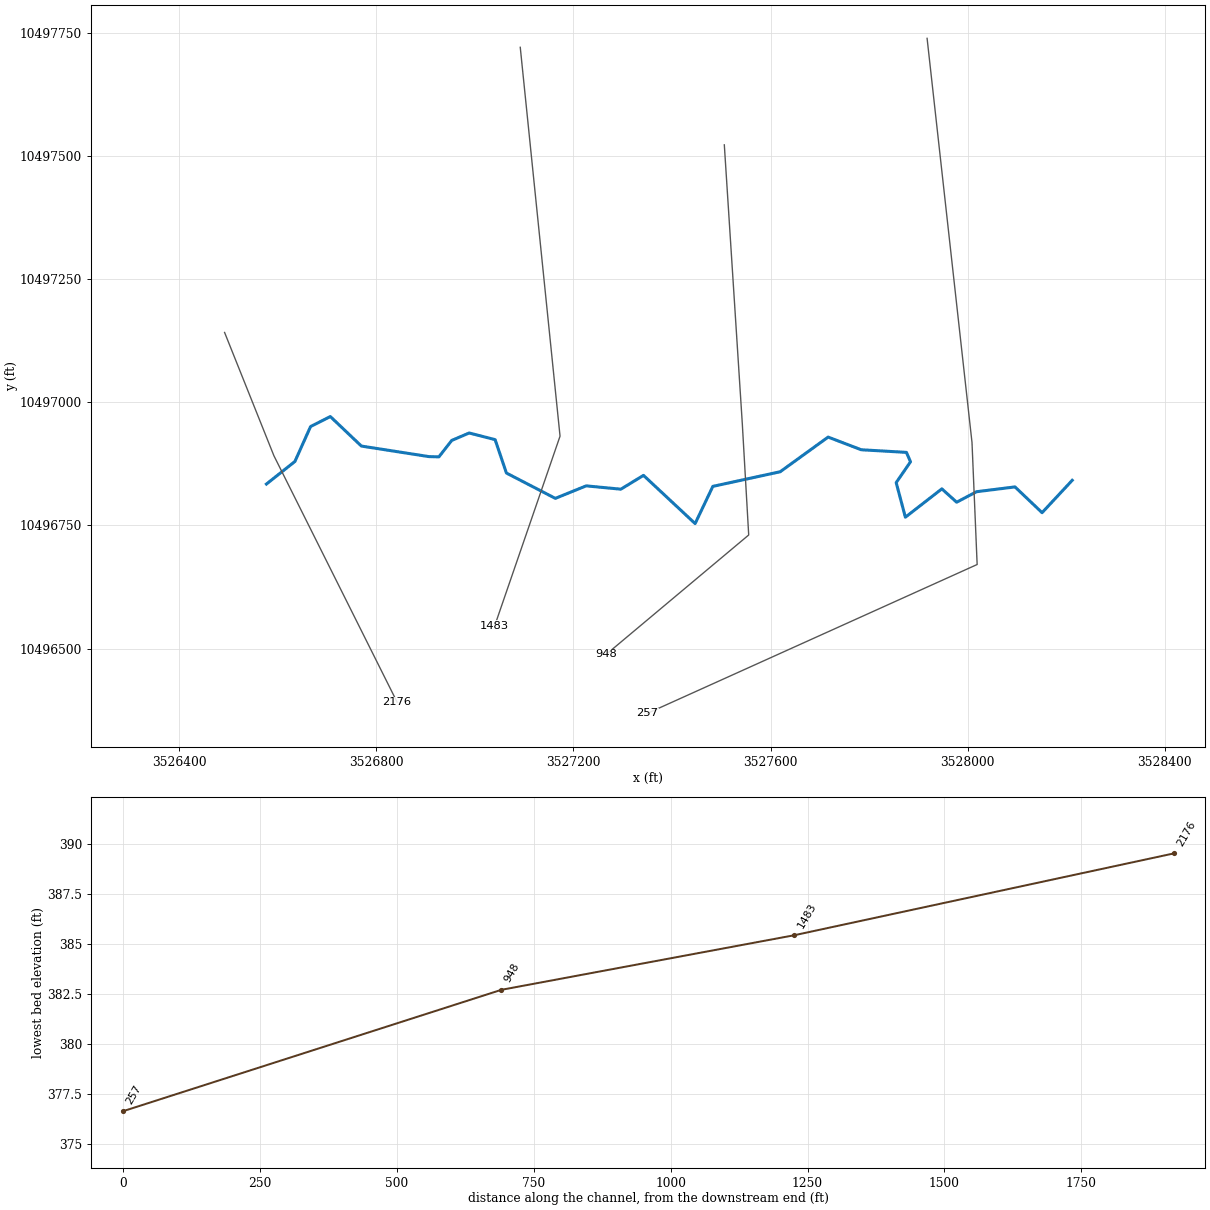
--- UNT0728 IN SAND CR.prj (project) ---

Proj Title=UNT0728 IN SAND CR Base Level Engineering
Current Plan=p01
Default Exp/Contr=0.3,0.1
English Units
Geom File=g01
Flow File=f01
Plan File=p01
BEGIN DESCRIPTION:
UNT0728 IN SAND CR
END DESCRIPTION:

--- UNT0728 IN SAND CR.p01 (plan) ---

Plan Title=Multiple Run
Short Identifier=Multiple
Geom File=g01
Flow File=f01
Subcritical Flow
K Sum by GR= 0
Std Step Tol= 0.01
Critical Tol= 0.01
Num of Std Step Trials= 20
Max Error Tol= 0.3
Flow Tol Ratio= 0.001
Split Flow NTrial= 30
Split Flow Tol= 0.02
Split Flow Ratio= 0.02
Log Output Level= 0
Friction Slope Method= 1
Unsteady Friction Slope Method= 2
Unsteady Bridges Friction Slope Method= 1
Parabolic Critical Depth
Global Vel Dist=  1 , 1 , 1
Global Log Level= 0
CheckData=True
Encroach Param= -1, 0, 0, 0
BEGIN DESCRIPTION:
Multiple Run
END DESCRIPTION:

--- UNT0728 IN SAND CR.f01 (steady flow) ---

Flow Title=Multiple
Number of Profiles=7
Profile Names=10-year,25-year,50-year,1pct_min,100-year,1pct_plu,500-year
River Rch & RM= UNT0728 IN SAND ,Reach-1,2176
     473     621     737     640     866    1171    1190
Boundary for River Rch & Prof#=UNT0728 IN SAND ,Reach-1,1
Up Type=0
Dn Type=3
Dn Slope=0.005
Boundary for River Rch & Prof#=UNT0728 IN SAND ,Reach-1,2
Up Type=0
Dn Type=3
Dn Slope=0.005
Boundary for River Rch & Prof#=UNT0728 IN SAND ,Reach-1,3
Up Type=0
Dn Type=3
Dn Slope=0.005
Boundary for River Rch & Prof#=UNT0728 IN SAND ,Reach-1,4
Up Type=0
Dn Type=3
Dn Slope=0.005
Boundary for River Rch & Prof#=UNT0728 IN SAND ,Reach-1,5
Up Type=0
Dn Type=3
Dn Slope=0.005
Boundary for River Rch & Prof#=UNT0728 IN SAND ,Reach-1,6
Up Type=0
Dn Type=3
Dn Slope=0.005
Boundary for River Rch & Prof#=UNT0728 IN SAND ,Reach-1,7
Up Type=0
Dn Type=3
Dn Slope=0.005

--- UNT0728 IN SAND CR.g01 (geometry) ---

Geom Title=Existing Conditions

River Reach=UNT0728 IN SAND ,Reach-1
Reach XY= 30
      3526576.99     10496833.99      3526634.80     10496879.83
      3526666.57     10496950.66      3526706.67     10496970.97
      3526769.69     10496911.08      3526906.67     10496889.72
      3526926.99     10496889.20      3526953.03     10496922.54
      3526988.44     10496937.64      3527041.05     10496924.10
      3527063.97     10496856.39      3527163.21     10496804.97
      3527225.77     10496830.33      3527296.20     10496823.60
      3527342.11     10496851.64      3527446.88     10496753.82
      3527482.85     10496829.30      3527619.53     10496858.98
      3527716.76     10496929.32      3527783.90     10496903.61
      3527875.62     10496898.29      3527883.97     10496879.24
      3527854.87     10496836.93      3527873.49     10496766.74
      3527947.53     10496824.28      3527977.52     10496797.17
      3528017.96     10496818.45      3528095.99     10496828.19
      3528150.88     10496775.95      3528212.11     10496841.64

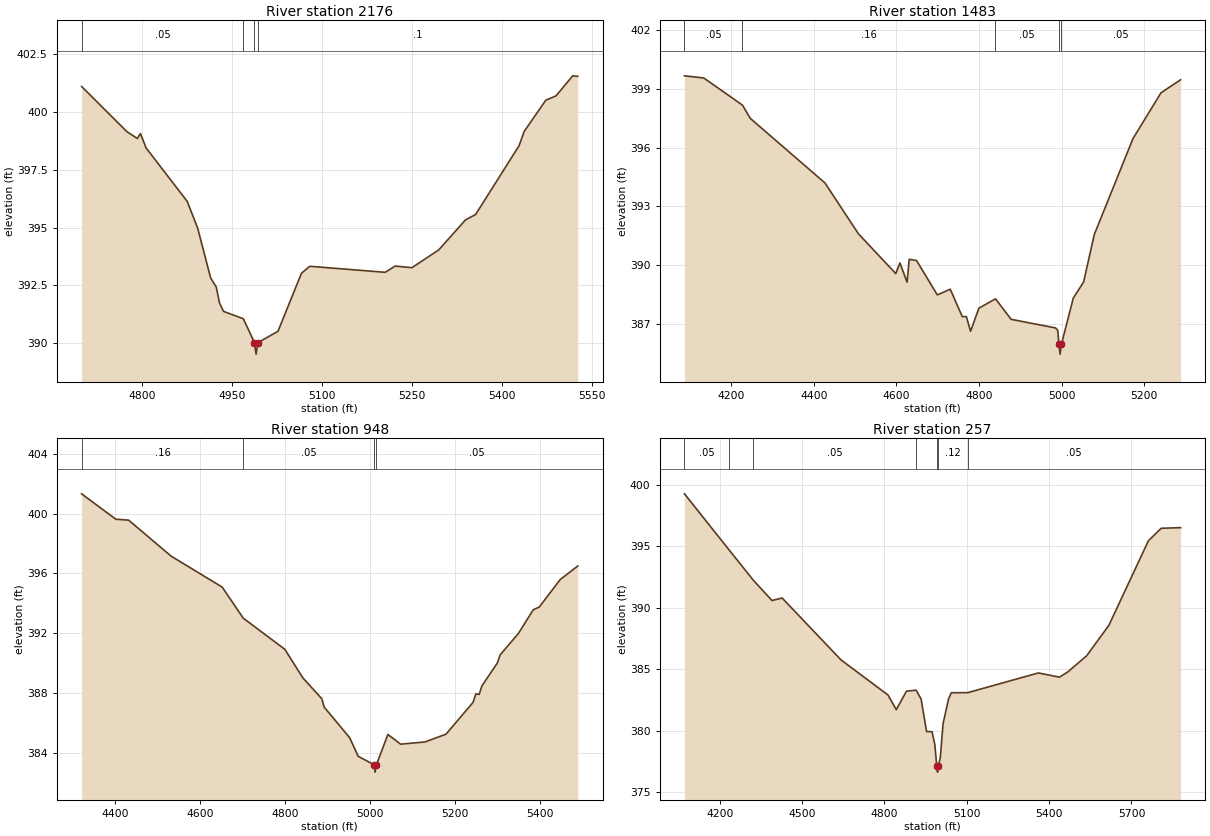
Type RM Length L Ch R = 1,2176,693,693,693
BEGIN DESCRIPTION:
UNT0728 IN SAND CR 4.0
END DESCRIPTION:
XS GIS Cut Line= 3
      3526492.11     10497141.62      3526592.11     10496891.64
      3526842.13     10496391.60
#Sta/Elev= 30
  4698.4  401.11  4773.8  399.16  4791.3  398.86  4796.7  399.07  4806.1  398.45
  4874.7  396.14  4892.2  394.98  4913.8  392.83  4923.2  392.43  4928.6  391.75
  4935.3  391.38  4968.4  391.06  4987.0  390.03  4989.7  389.53  4993.0  390.03
  5026.3  390.52  5065.5  393.03  5079.4  393.33  5205.2  393.07  5222.0  393.34
  5249.9  393.27  5294.7  394.04  5339.4  395.34  5356.2  395.57  5428.8  398.55
  5437.2  399.16  5473.5  400.52  5490.3  400.70  5518.3  401.57  5526.7  401.55
#Mann=4,-1,0
  4698.4    0.05       0  4968.4     0.1       0  4987.0    0.07       0
  4993.0     0.1       0
Bank Sta=4987,4993
Exp/Cntr=0.3,0.1

Type RM Length L Ch R = 1,1483,535,535,535
BEGIN DESCRIPTION:
UNT0728 IN SAND CR 3.0
END DESCRIPTION:
XS GIS Cut Line= 3
      3527092.05     10497720.25      3527172.78     10496931.17
      3527040.12     10496546.18
#Sta/Elev= 30
  4087.3  399.68  4134.0  399.57  4227.7  398.18  4246.7  397.50  4427.2  394.20
  4508.1  391.60  4598.6  389.56  4608.6  390.11  4625.9  389.12  4631.0  390.29
  4648.8  390.23  4699.1  388.47  4730.4  388.76  4759.4  387.36  4769.4  387.36
  4779.5  386.61  4799.6  387.79  4839.8  388.27  4877.7  387.22  4985.2  386.78
  4990.5  386.65  4993.3  385.94  4996.1  385.44  4999.3  385.94  5028.1  388.31
  5053.0  389.13  5078.9  391.56  5172.5  396.47  5240.2  398.81  5287.7  399.48
#Mann=5,-1,0
  4087.3    0.05       0  4227.7    0.16       0  4839.8    0.05       0
  4993.3    0.03       0  4999.3    0.05       0
Bank Sta=4993.3,4999.3
Exp/Cntr=0.3,0.1

Type RM Length L Ch R = 1,948,691,691,691
BEGIN DESCRIPTION:
UNT0728 IN SAND CR 2.0
END DESCRIPTION:
XS GIS Cut Line= 4
      3527506.12     10497522.31      3527542.58     10496957.21
      3527555.60     10496730.65      3527267.09     10496488.93
#Sta/Elev= 30
  4320.4  401.33  4401.2  399.63  4431.3  399.57  4531.5  397.16  4651.8  395.09
  4701.6  393.01  4799.4  390.93  4842.2  389.01  4886.7  387.62  4892.3  387.06
  4952.4  385.01  4972.4  383.77  5009.5  383.21  5012.2  382.71  5015.5  383.21
  5042.5  385.23  5072.6  384.58  5130.1  384.73  5179.5  385.25  5243.3  387.38
  5249.8  387.95  5257.6  387.91  5264.1  388.48  5300.5  390.01  5307.0  390.55
  5349.9  391.98  5385.1  393.57  5399.4  393.76  5448.8  395.60  5490.0  396.50
#Mann=4,-1,0
  4320.4    0.16       0  4701.6    0.05       0  5009.5    0.03       0
  5015.5    0.05       0
Bank Sta=5009.5,5015.5
Exp/Cntr=0.3,0.1

Type RM Length L Ch R = 1,257,0,0,0
BEGIN DESCRIPTION:
UNT0728 IN SAND CR 1.0
END DESCRIPTION:
XS GIS Cut Line= 4
      3527917.58     10497738.43      3528008.72     10496918.15
      3528019.14     10496670.76      3527349.90     10496368.69
#Sta/Elev= 30
  4071.9  399.26  4233.1  394.74  4323.1  392.23  4390.6  390.59  4427.8  390.79
  4642.2  385.76  4813.2  382.91  4843.4  381.72  4880.6  383.22  4915.7  383.30
  4933.8  382.58  4953.8  379.94  4973.8  379.92  4983.8  378.89  4990.8  377.14
  4993.6  376.64  4996.8  377.14  5003.8  377.81  5013.8  380.57  5033.9  382.59
  5043.9  383.09  5103.8  383.10  5361.0  384.70  5437.8  384.36  5468.0  384.78
  5536.6  386.09  5617.8  388.57  5762.0  395.45  5808.3  396.46  5879.1  396.51
#Mann=7,-1,0
  4071.9    0.05       0  4233.1     0.1       0  4323.1    0.05       0
  4915.7    0.12       0  4990.8    0.07       0  4996.8    0.12       0
  5103.8    0.05       0
Bank Sta=4990.8,4996.8
Exp/Cntr=0.3,0.1

Chan Stop Cuts=-1