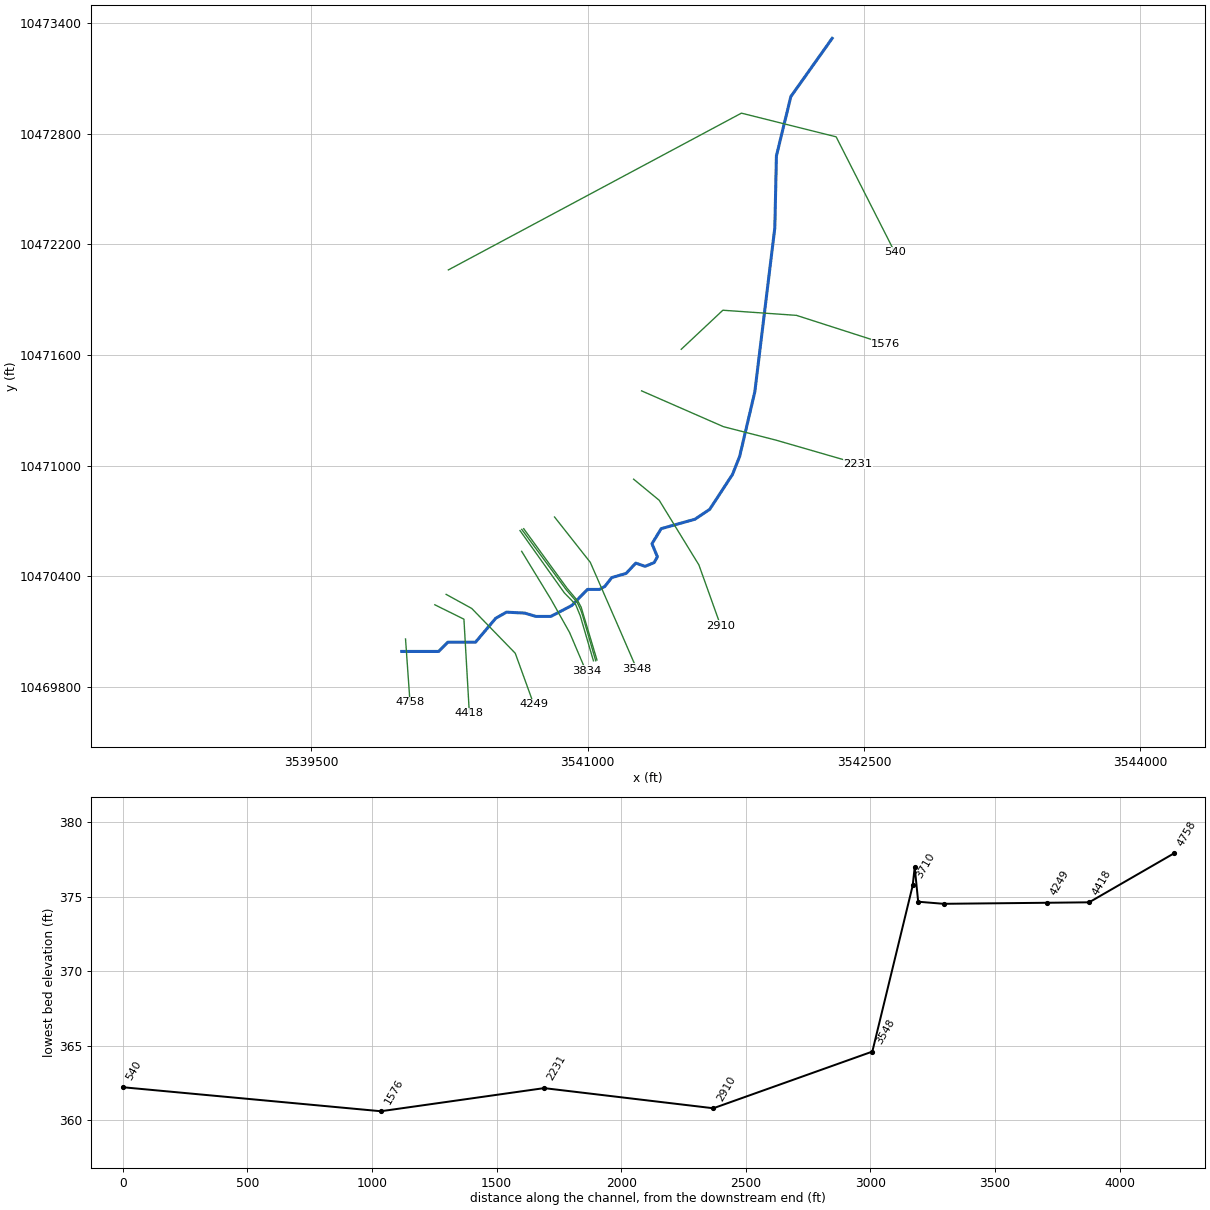
--- UNT0750 IN SAND CR.prj (project) ---

Proj Title=UNT0750 IN SAND CR Base Level Engineering
Current Plan=p01
Default Exp/Contr=0.3,0.1
English Units
Geom File=g01
Flow File=f01
Plan File=p01
Y Axis Title=Elevation
X Axis Title(PF)=Main Channel Distance
X Axis Title(XS)=Station
BEGIN DESCRIPTION:
UNT0750 IN SAND CR
END DESCRIPTION:
DSS Export Rating Curves= 0
DSS Export Rating Curve Sorted= 0
DSS Export Volume Flow Curves= 0
DXF OffsetX= 0
DXF OffsetY= 0
DXF ScaleX= 1
DXF ScaleY= 10

--- UNT0750 IN SAND CR.p01 (plan) ---

Plan Title=Multiple Run
Short Identifier=Multiple
Geom File=g01
Flow File=f01
Subcritical Flow
K Sum by GR= 0
Std Step Tol= 0.01
Critical Tol= 0.01
Num of Std Step Trials= 20
Max Error Tol= 0.3
Flow Tol Ratio= 0.001
Split Flow NTrial= 30
Split Flow Tol= 0.02
Split Flow Ratio= 0.02
Log Output Level= 0
Friction Slope Method= 1
Unsteady Friction Slope Method= 2
Unsteady Bridges Friction Slope Method= 1
Parabolic Critical Depth
Global Vel Dist=  1 , 1 , 1
Global Log Level= 0
CheckData=True
Encroach Param= -1, 0, 0, 0
BEGIN DESCRIPTION:
Multiple Run
END DESCRIPTION:

--- UNT0750 IN SAND CR.f01 (steady flow) ---

Flow Title=Multiple
Number of Profiles=7
Profile Names=10-year,25-year,50-year,1pct_min,100-year,1pct_plu,500-year
River Rch & RM= UNT0750 IN SAND ,Reach-1,4758
     576     766     916     802    1084    1466    1512
Boundary for River Rch & Prof#=UNT0750 IN SAND ,Reach-1,1
Up Type=0
Dn Type=3
Dn Slope=0.005
Boundary for River Rch & Prof#=UNT0750 IN SAND ,Reach-1,2
Up Type=0
Dn Type=3
Dn Slope=0.005
Boundary for River Rch & Prof#=UNT0750 IN SAND ,Reach-1,3
Up Type=0
Dn Type=3
Dn Slope=0.005
Boundary for River Rch & Prof#=UNT0750 IN SAND ,Reach-1,4
Up Type=0
Dn Type=3
Dn Slope=0.005
Boundary for River Rch & Prof#=UNT0750 IN SAND ,Reach-1,5
Up Type=0
Dn Type=3
Dn Slope=0.005
Boundary for River Rch & Prof#=UNT0750 IN SAND ,Reach-1,6
Up Type=0
Dn Type=3
Dn Slope=0.005
Boundary for River Rch & Prof#=UNT0750 IN SAND ,Reach-1,7
Up Type=0
Dn Type=3
Dn Slope=0.005

--- UNT0750 IN SAND CR.g01 (geometry) ---

Geom Title=Existing Conditions
Program Version=4.10

River Reach=UNT0750 IN SAND ,Reach-1
Reach XY= 30
      3539992.11     10469991.64      3540192.11     10469991.64
      3540242.11     10470041.64      3540392.11     10470041.64
      3540502.18     10470171.86      3540560.34     10470204.85
       3540659.3     10470199.64      3540720.05     10470181.67
      3540800.79     10470181.66      3540915.37     10470241.31
      3540999.57     10470328.11      3541064.68     10470328.11
      3541094.19     10470344.61      3541131.52     10470392.35
      3541209.67     10470415.08      3541261.79     10470470.85
      3541312.26     10470453.33      3541361.76     10470473.74
      3541379.24     10470505.48      3541349.75     10470575.96
      3541399.75      10470657.9      3541583.77     10470709.29
      3541663.63     10470763.46      3541786.55     10470951.65
      3541825.44     10471049.57      3541907.91     10471400.61
      3542016.41     10472290.37      3542025.09     10472680.99
      3542103.22     10473002.17      3542327.59     10473318.49

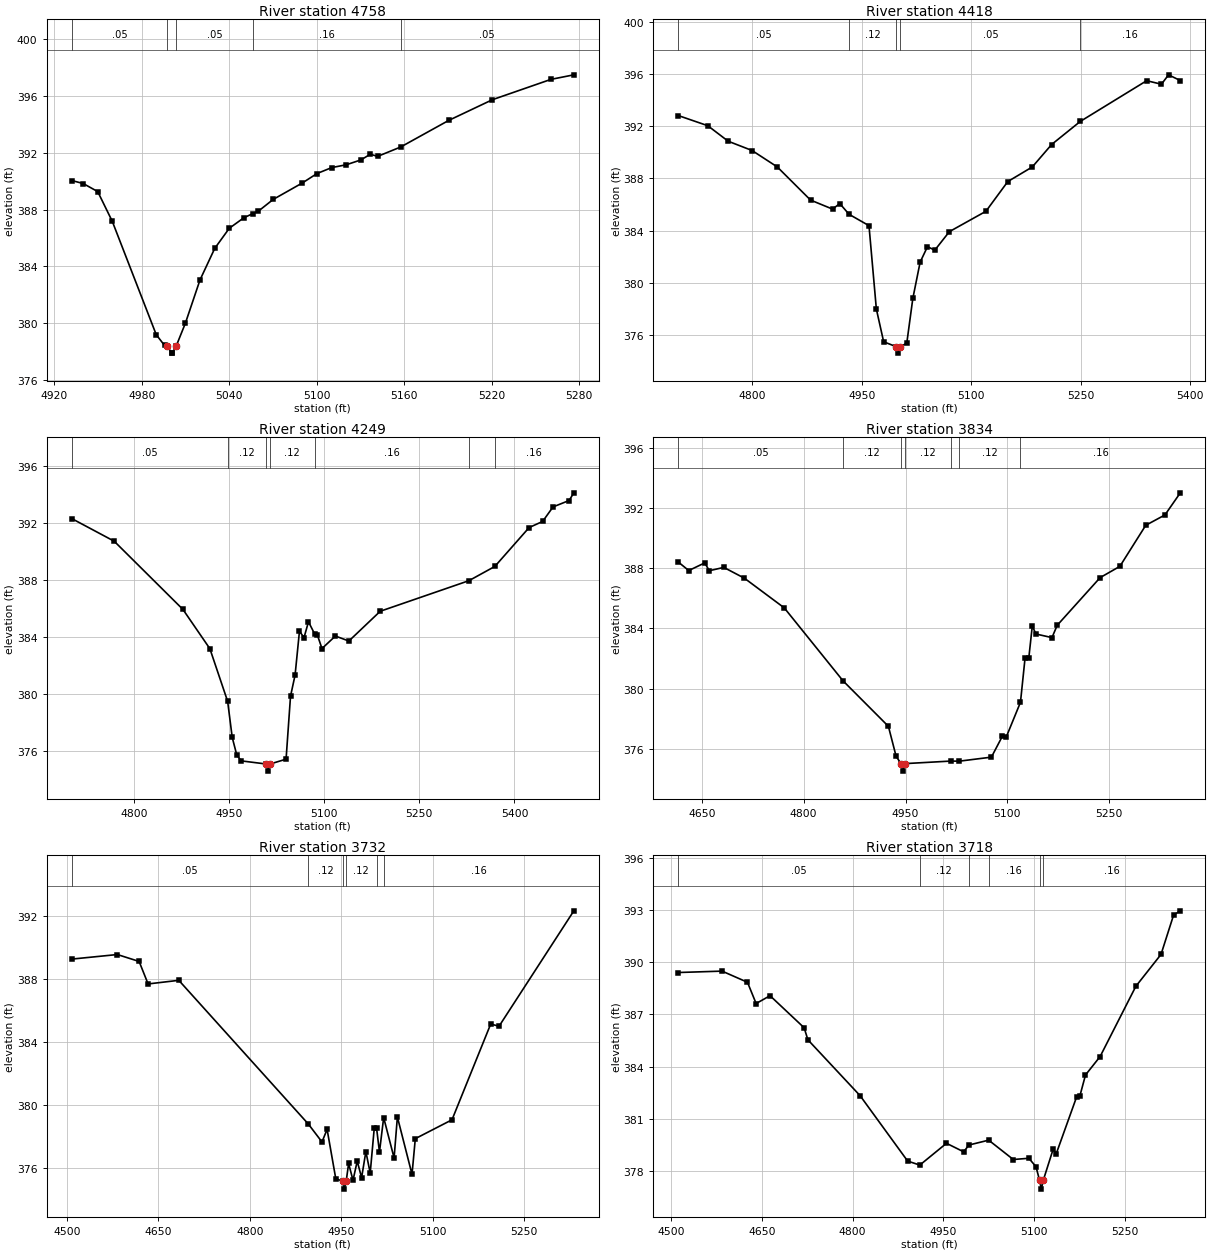
Type RM Length L Ch R = 1 ,4758    ,340,340,340
BEGIN DESCRIPTION:
UNT0750 IN SAND CR 10.0
END DESCRIPTION:
XS GIS Cut Line= 2
      3540012.57     10470059.37      3540036.83     10469716.03
#Sta/Elev= 30
  4932.1  390.04  4939.9  389.83  4949.9  389.26  4959.9  387.16    4990  379.19
  4995.7  378.43  4997.7  378.39  5000.5  377.89    5001  377.89  5003.7  378.39
    5010     380    5020  383.04  5030.1  385.26  5040.1  386.68  5050.1  387.42
    5056   387.7  5060.1  387.89  5070.2  388.71  5090.2  389.87  5100.2  390.53
  5110.3  390.95  5120.3  391.15  5130.3  391.49  5136.8  391.89  5141.8  391.74
  5157.6   392.4  5190.5  394.27  5220.5  395.73  5260.6  397.16  5276.3  397.48
#Mann= 5 ,-1 , 0
  4932.1     .05       0  4997.7     .03       0  5003.7     .05       0
    5056     .16       0  5157.6     .05       0
Bank Sta=4997.7,5003.7
XS Rating Curve= 0 ,0
Exp/Cntr=0.3,0.1

Type RM Length L Ch R = 1 ,4418    ,169,169,169
BEGIN DESCRIPTION:
UNT0750 IN SAND CR 10.1
END DESCRIPTION:
XS GIS Cut Line= 3
      3540171.38     10470244.89      3540329.41     10470166.74
      3540358.87     10469655.58
#Sta/Elev= 30
  4698.4  392.82  4738.9  392.04  4766.9  390.85  4799.6  390.14  4834.2  388.88
  4879.8  386.34  4909.9  385.65  4919.9  386.07  4932.6  385.25  4959.9  384.38
    4970  377.99    4980  375.48    4997  375.11  4999.8  374.61    5003  375.11
  5011.7  375.37    5020   378.8    5030  381.58  5040.1  382.77  5050.1   382.5
  5070.1  383.92  5120.2  385.48  5150.2  387.76  5183.8  388.88  5210.3   390.6
  5249.6  392.37  5340.6  395.49  5360.8  395.22  5370.6  395.94  5386.7   395.5
#Mann= 5 ,-1 , 0
  4698.4     .05       0  4932.6     .12       0    4997     .07       0
    5003     .05       0  5249.6     .16       0
Bank Sta=4997,5003
XS Rating Curve= 0 ,0
Exp/Cntr=0.3,0.1

Type RM Length L Ch R = 1 ,4249    ,415,415,415
BEGIN DESCRIPTION:
UNT0750 IN SAND CR 9.0
END DESCRIPTION:
XS GIS Cut Line= 4
      3540232.95     10470301.29      3540371.81     10470224.92
      3540607.92     10469981.86      3540708.14     10469705.41
#Sta/Elev= 30
  4702.2  392.32  4769.1  390.73  4877.4  385.94  4919.9  383.18  4947.9  379.48
  4955.1  376.95  4962.3  375.71  4969.3   375.3  5008.7  375.08  5011.5  374.58
  5014.7  375.08    5040  375.42    5047  379.84  5054.2  381.33  5061.1  384.41
  5068.3  383.96  5075.3  385.07    5085  384.22  5089.4  384.13  5096.6  383.19
  5117.7  384.07    5139  383.72  5188.4  385.81  5328.3  387.96  5369.1  388.96
  5423.1  391.69  5444.4  392.12  5460.8  393.14  5486.1  393.59  5493.6  394.13
#Mann= 7 ,-1 , 0
  4702.2     .05       0  4947.9     .12       0  5008.7     .07       0
  5014.7     .12       0    5085     .16       0  5328.3     .05       0
  5369.1     .16       0
Bank Sta=5008.7,5014.7
XS Rating Curve= 0 ,0
Exp/Cntr=0.3,0.1

Type RM Length L Ch R = 1 ,3834    ,102,102,102
BEGIN DESCRIPTION:
UNT0750 IN SAND CR 8.1
END DESCRIPTION:
XS GIS Cut Line= 6
      3540642.74     10470534.91      3540801.57     10470274.54
      3540903.13     10470093.55      3540981.25     10469909.95
      3540985.16     10469907.35      3540994.24      10469886.6
#Sta/Elev= 30
  4615.3  388.42  4630.8  387.85  4654.3  388.36  4661.1  387.84  4682.4  388.06
  4712.8  387.34  4771.4  385.37  4857.9  380.52  4924.8  377.49  4936.2  375.49
  4943.4  375.01  4946.2  374.51  4949.4  375.01  5017.3  375.18  5028.8  375.17
  5076.5  375.44  5092.5  376.82  5098.2  376.76  5119.3  379.09  5126.1  382.05
  5131.6  382.05  5136.7  384.16  5142.1  383.63  5165.7  383.39  5173.4  384.21
  5236.6  387.38  5265.7  388.13  5303.8  390.86  5332.1  391.55  5354.7  393.02
#Mann= 7 ,-1 , 0
  4615.3     .05       0  4857.9     .12       0  4943.4     .07       0
  4949.4     .12       0  5017.3     .16       0  5028.8     .12       0
  5119.3     .16       0
Bank Sta=4943.4,4949.4
XS Rating Curve= 0 ,0
Exp/Cntr=0.3,0.1

Type RM Length L Ch R = 1 ,3732    ,14,14,14
BEGIN DESCRIPTION:
UNT0750 IN SAND CR 8.02
END DESCRIPTION:
XS GIS Cut Line= 5
       3540633.7     10470647.53       3540874.3     10470309.54
      3540935.24     10470247.04      3540960.24      10470186.1
      3541032.12     10469940.76
#Sta/Elev= 30
  4508.1  389.28  4582.9  389.57  4618.6  389.13  4633.3   387.7  4683.7  387.93
  4896.2  378.79  4918.6  377.65    4927  378.45  4941.2  375.32  4952.3  375.15
  4955.1  374.65  4958.3  375.15  4962.3  376.28  4969.5  375.21  4976.4  376.43
  4983.6  375.38  4990.6  377.04  4997.7  375.67  5004.4  378.55  5008.1  378.55
  5012.9  377.01  5019.8   379.2  5036.9  376.63  5042.3  379.24  5066.3  375.59
  5071.7  377.86  5131.9  379.06  5195.4  385.15  5209.1  385.01  5331.8  392.35
#Mann= 6 ,-1 , 0
  4508.1     .05       0  4896.2     .12       0  4952.3     .07       0
  4958.3     .12       0  5008.1     .05       0  5019.8     .16       0
Bank Sta=4952.3,4958.3
XS Rating Curve= 0 ,0
Exp/Cntr=0.3,0.1

Type RM Length L Ch R = 1 ,3718    ,8,8,8
BEGIN DESCRIPTION:
UNT0750 IN SAND CR 8.01
END DESCRIPTION:
XS GIS Cut Line= 6
      3540643.29     10470653.83      3540884.27     10470326.75
      3540943.97     10470257.67       3540963.5     10470216.27
      3540973.09     10470187.88      3541044.44       10469941.
#Sta/Elev= 30
  4511.6   389.4  4584.1  389.48  4626.1  388.84  4640.4  387.62  4663.4  388.07
  4719.8  386.23    4726  385.54  4812.4  382.33    4891  378.58  4911.1  378.35
  4955.2   379.6  4983.7  379.11  4992.2   379.5    5025  379.78  5065.7  378.67
  5091.4  378.74  5103.2  378.26  5109.2  377.47    5112  376.97  5115.2  377.47
  5131.6  379.26  5136.8  379.01  5170.4  382.26  5175.6  382.29  5185.1  383.52
  5209.3  384.58  5268.4  388.61    5310  390.44  5330.8   392.7  5341.9  392.94
#Mann= 6 ,-1 , 0
  4511.6     .05       0  4911.1     .12       0  4992.2     .05       0
    5025     .16       0  5109.2     .03       0  5115.2     .16       0
Bank Sta=5109.2,5115.2
XS Rating Curve= 0 ,0
Exp/Cntr=0.3,0.1

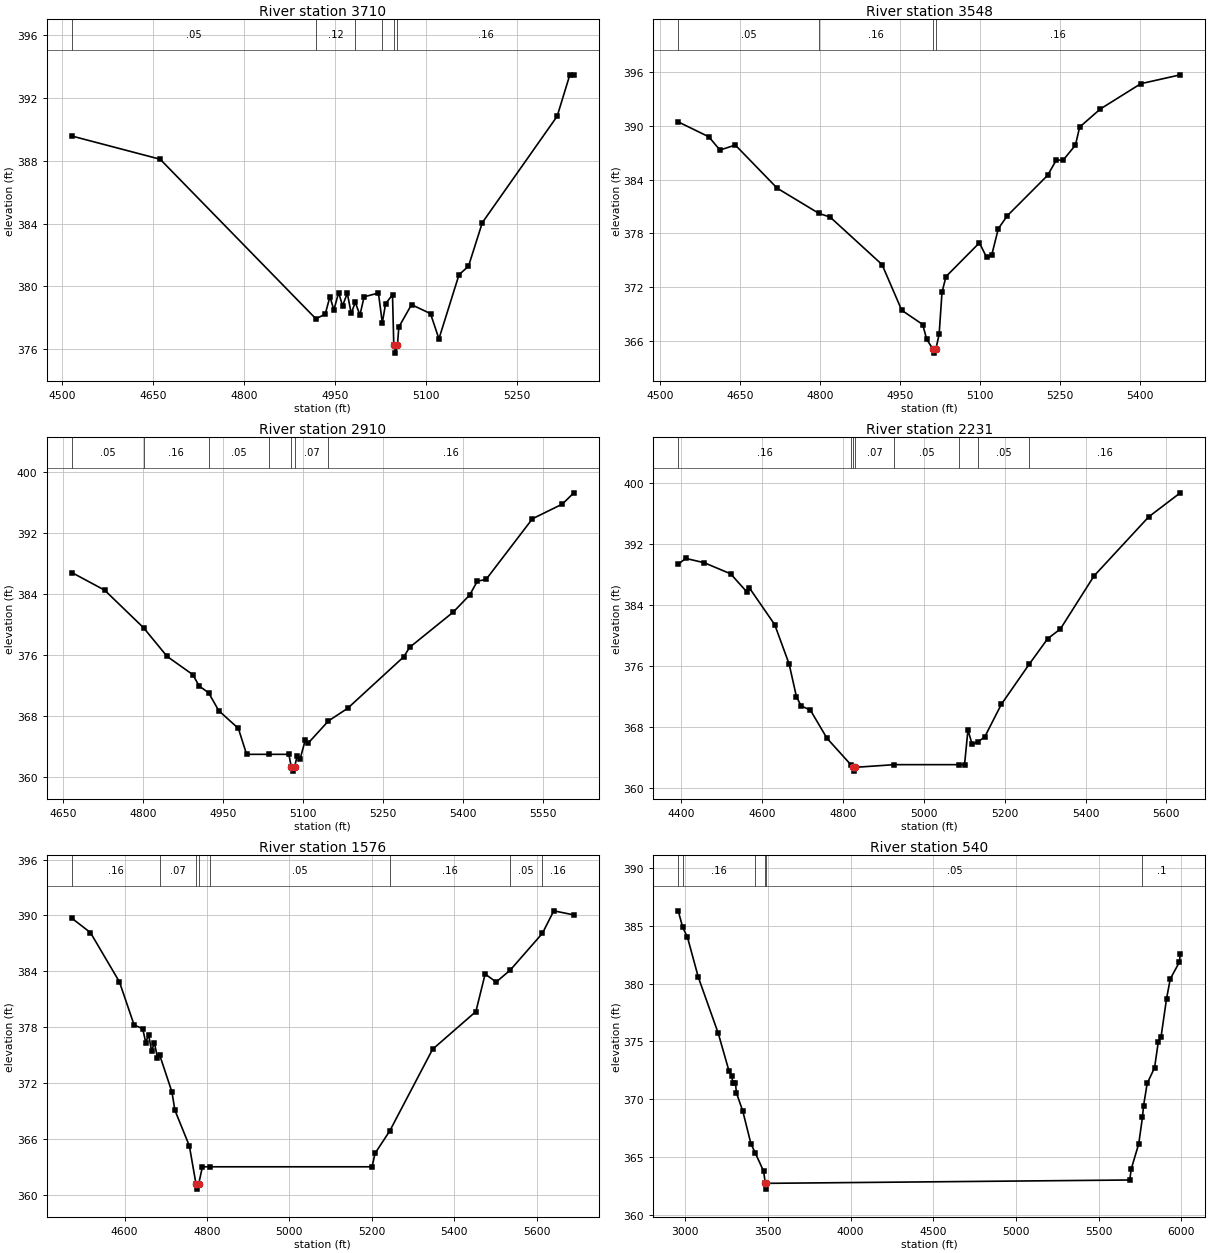
Type RM Length L Ch R = 1 ,3710    ,162,162,162
BEGIN DESCRIPTION:
UNT0750 IN SAND CR 8.0
END DESCRIPTION:
XS GIS Cut Line= 5
      3540653.81     10470657.61      3540888.35      10470335.5
      3540948.25     10470263.88      3540965.69     10470231.59
      3541051.26     10469945.33
#Sta/Elev= 30
  4516.1  389.58  4661.7   388.1  4918.3  377.93  4933.7  378.22  4941.5  379.34
    4948  378.49  4955.8   379.6  4962.3  378.75  4970.1  379.56  4976.6  378.27
  4983.2  378.98  4990.9  378.16  4997.8  379.33  5021.4  379.57  5027.8  377.67
  5033.2  378.89  5044.6  379.46  5046.7  376.24  5049.4  375.74  5052.7  376.24
    5055   377.4  5075.9  378.83  5107.2  378.26  5121.1  376.65  5154.2  380.74
  5169.8  381.28  5192.6  384.06  5315.9  390.84  5336.8  393.48  5343.4  393.44
#Mann= 6 ,-1 , 0
  4516.1     .05       0  4918.3     .12       0  4983.2     .05       0
  5027.8     .16       0  5046.7     .03       0  5052.7     .16       0
Bank Sta=5046.7,5052.7
XS Rating Curve= 0 ,0
Exp/Cntr=0.3,0.1

Type RM Length L Ch R = 1 ,3548    ,638,638,638
BEGIN DESCRIPTION:
UNT0750 IN SAND CR 7.0
END DESCRIPTION:
XS GIS Cut Line= 4
      3540821.07     10470721.19      3541015.11     10470475.06
      3541159.64     10470144.33      3541266.41     10469898.24
#Sta/Elev= 30
  4533.4  390.45  4590.9  388.78  4611.7   387.3  4640.6  387.86  4719.1  383.04
  4797.5  380.22  4818.5  379.81    4916   374.5    4953  369.39  4992.4   367.8
  4999.8  366.14  5011.2   365.1    5014   364.6  5017.2   365.1  5023.2  366.69
  5028.6   371.4  5036.1  373.16  5098.8  376.93  5112.5  375.29  5122.2  375.62
  5134.3  378.51  5151.1  379.95  5226.8  384.47  5243.4   386.2  5255.7  386.15
  5279.1  387.85    5287  389.87  5326.1   391.9  5401.9  394.72    5476  395.71
#Mann= 4 ,-1 , 0
  4533.4     .05       0  4797.5     .16       0  5011.2     .07       0
  5017.2     .16       0
Bank Sta=5011.2,5017.2
XS Rating Curve= 0 ,0
Exp/Cntr=0.3,0.1

Type RM Length L Ch R = 1 ,2910    ,679,679,679
BEGIN DESCRIPTION:
UNT0750 IN SAND CR 6.0
END DESCRIPTION:
XS GIS Cut Line= 4
      3541250.25     10470926.34      3541389.17     10470811.73
      3541604.45     10470461.03      3541722.49     10470131.21
#Sta/Elev= 30
  4665.6  386.82  4727.2  384.51  4800.2  379.59  4844.4  375.83  4892.7  373.44
  4904.7  371.94  4922.3  371.07  4941.4  368.71  4978.1   366.4  4993.6     363
  5034.7     363  5072.9     363  5077.5   361.3  5080.2   360.8  5083.5   361.3
  5088.3  362.76  5094.2  362.45  5103.7  364.88  5109.6   364.5  5147.2  367.38
    5183  369.02  5288.4  375.78  5299.5  377.02  5381.2  381.63    5412  383.87
  5426.5  385.69  5442.8  385.91  5529.8  393.86  5585.8  395.78  5607.5  397.26
#Mann= 7 ,-1 , 0
  4665.6     .05       0  4800.2     .16       0  4922.3     .05       0
  5034.7     .07       0  5077.5     .03       0  5083.5     .07       0
  5147.2     .16       0
Bank Sta=5077.5,5083.5
XS Rating Curve= 0 ,0
Exp/Cntr=0.3,0.1

Type RM Length L Ch R = 1 ,2231    ,655,655,655
BEGIN DESCRIPTION:
UNT0750 IN SAND CR 5.0
END DESCRIPTION:
XS GIS Cut Line= 4
      3541293.48     10471405.62      3541737.94     10471211.17
      3542022.66     10471138.25      3542467.12     10471009.77
#Sta/Elev= 30
  4392.7  389.32  4411.3  390.07  4456.7  389.51  4522.2  388.05  4562.6  385.66
    4568  386.25  4631.3  381.38  4667.1  376.18    4685  371.92  4696.8   370.7
  4719.3  370.18  4760.6  366.46  4820.7  362.93  4824.8  362.65  4827.6  362.15
  4830.8  362.65  4927.3     363  5087.5     363  5100.8     363  5109.2  367.56
  5119.6  365.66  5133.5  365.99  5150.5  366.62    5192  370.94  5261.2  376.22
  5306.5  379.54  5337.7   380.8    5421  387.77  5556.3  395.53  5634.4  398.68
#Mann= 8 ,-1 , 0
  4392.7     .16       0  4820.7     .07       0  4824.8    .033       0
  4830.8     .07       0  4927.3     .05       0  5087.5     .07       0
  5133.5     .05       0  5261.2     .16       0
Bank Sta=4824.8,4830.8
XS Rating Curve= 0 ,0
Exp/Cntr=0.3,0.1

Type RM Length L Ch R = 1 ,1576    ,1036,1036,1036
BEGIN DESCRIPTION:
UNT0750 IN SAND CR 3.0
END DESCRIPTION:
XS GIS Cut Line= 4
      3541508.73     10471631.27      3541734.47     10471843.11
      3542133.77     10471815.33      3542618.51     10471659.52
#Sta/Elev= 30
  4471.6  389.71  4516.9  388.16  4587.3  382.87  4622.9  378.24  4643.9  377.83
  4651.2  376.34  4658.1  377.19  4665.4  375.47  4672.2  376.31  4679.6  374.73
  4684.7  375.05  4714.7  371.05    4722  369.08  4757.2  365.23  4773.4   361.1
  4776.2   360.6  4779.4   361.1  4788.8     363  4807.2     363  5200.7     363
  5207.9  364.44  5243.6  366.85  5347.7  375.63  5452.8  379.68  5475.2  383.71
    5502  382.85  5535.9  384.12  5614.2  388.08  5641.9   390.5  5690.6  390.06
#Mann= 8 ,-1 , 0
  4471.6     .16       0  4684.7     .07       0  4773.4    .033       0
  4779.4     .07       0  4807.2     .05       0  5243.6     .16       0
  5535.9     .05       0  5614.2     .16       0
Bank Sta=4773.4,4779.4
XS Rating Curve= 0 ,0
Exp/Cntr=0.3,0.1

Type RM Length L Ch R = 1 ,540     ,0,0,0
BEGIN DESCRIPTION:
UNT0750 IN SAND CR 1.0
END DESCRIPTION:
XS GIS Cut Line= 4
      3540244.88     10472061.86      3541835.16     10472912.56
      3542349.05     10472784.08      3542667.53      10472157.5
#Sta/Elev= 30
  2957.2  386.29  2983.9  384.87  3013.1     384  3078.9  380.53  3199.2  375.69
    3265  372.39  3281.3  372.01    3287  371.36  3303.2  371.42  3308.9  370.54
  3347.1  368.98  3396.7  366.14  3423.1  365.34  3473.1  363.77  3484.1  362.71
  3486.8  362.21  3490.1  362.71  5687.4     363    5697  363.98  5741.9  366.13
  5764.6  368.45  5770.8   369.4    5793  371.36  5837.5  372.71  5859.8  374.91
  5876.4  375.35  5910.1  378.69  5932.6   380.4  5987.7  381.85  5993.3  382.57
#Mann= 6 ,-1 , 0
  2957.2     .16       0  2983.9     .16       0  3423.1     .05       0
  3484.1    .033       0  3490.1     .05       0  5764.6      .1       0
Bank Sta=3484.1,3490.1
XS Rating Curve= 0 ,0
Exp/Cntr=0.3,0.1

Chan Stop Cuts=-1
Use User Specified Reach Order=0
Composite Channel Slope=5