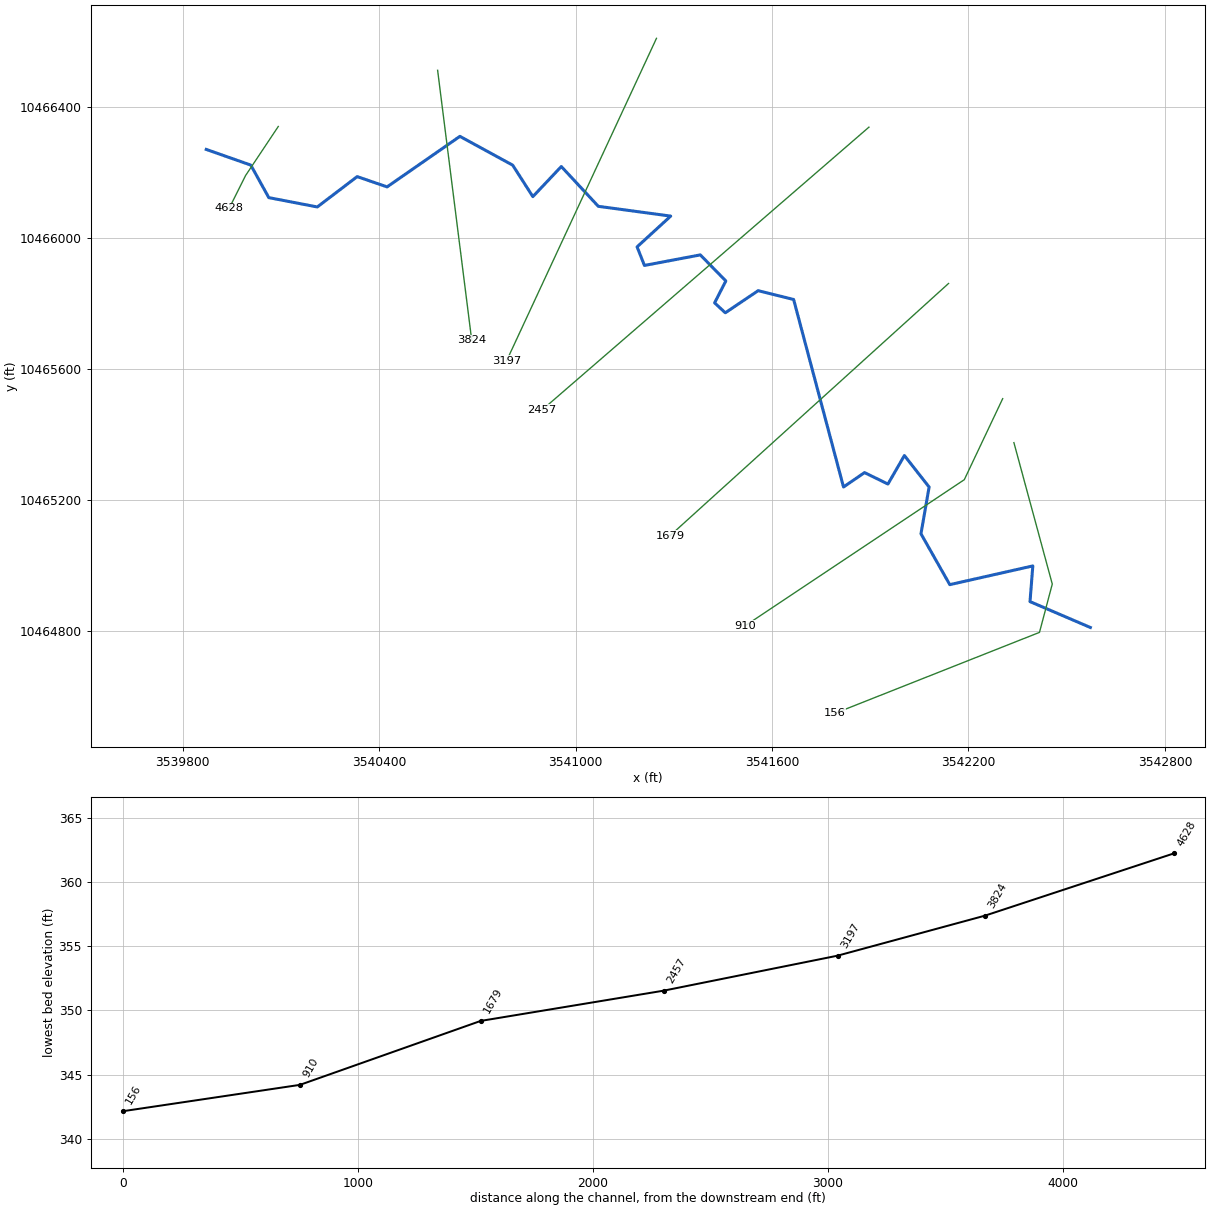
--- UNT0752 IN SAND CR.prj (project) ---

Proj Title=UNT0752 IN SAND CR Base Level Engineering
Current Plan=p01
Default Exp/Contr=0.3,0.1
English Units
Geom File=g01
Flow File=f01
Plan File=p01
BEGIN DESCRIPTION:
UNT0752 IN SAND CR
END DESCRIPTION:

--- UNT0752 IN SAND CR.p01 (plan) ---

Plan Title=Multiple Run
Short Identifier=Multiple
Geom File=g01
Flow File=f01
Subcritical Flow
K Sum by GR= 0
Std Step Tol= 0.01
Critical Tol= 0.01
Num of Std Step Trials= 20
Max Error Tol= 0.3
Flow Tol Ratio= 0.001
Split Flow NTrial= 30
Split Flow Tol= 0.02
Split Flow Ratio= 0.02
Log Output Level= 0
Friction Slope Method= 1
Unsteady Friction Slope Method= 2
Unsteady Bridges Friction Slope Method= 1
Parabolic Critical Depth
Global Vel Dist=  1 , 1 , 1
Global Log Level= 0
CheckData=True
Encroach Param= -1, 0, 0, 0
BEGIN DESCRIPTION:
Multiple Run
END DESCRIPTION:

--- UNT0752 IN SAND CR.f01 (steady flow) ---

Flow Title=Multiple
Number of Profiles=7
Profile Names=10-year,25-year,50-year,1pct_min,100-year,1pct_plu,500-year
River Rch & RM= UNT0752 IN SAND ,Reach-1,4628
     747    1009    1222    1081    1462    1978    2086
Boundary for River Rch & Prof#=UNT0752 IN SAND ,Reach-1,1
Up Type=0
Dn Type=3
Dn Slope=0.005
Boundary for River Rch & Prof#=UNT0752 IN SAND ,Reach-1,2
Up Type=0
Dn Type=3
Dn Slope=0.005
Boundary for River Rch & Prof#=UNT0752 IN SAND ,Reach-1,3
Up Type=0
Dn Type=3
Dn Slope=0.005
Boundary for River Rch & Prof#=UNT0752 IN SAND ,Reach-1,4
Up Type=0
Dn Type=3
Dn Slope=0.005
Boundary for River Rch & Prof#=UNT0752 IN SAND ,Reach-1,5
Up Type=0
Dn Type=3
Dn Slope=0.005
Boundary for River Rch & Prof#=UNT0752 IN SAND ,Reach-1,6
Up Type=0
Dn Type=3
Dn Slope=0.005
Boundary for River Rch & Prof#=UNT0752 IN SAND ,Reach-1,7
Up Type=0
Dn Type=3
Dn Slope=0.005

--- UNT0752 IN SAND CR.g01 (geometry) ---

Geom Title=Existing Conditions

River Reach=UNT0752 IN SAND ,Reach-1
Reach XY= 30
      3539872.11     10466271.64      3540008.11     10466223.77
      3540063.15     10466124.38      3540211.26     10466095.89
      3540333.10     10466188.58      3540424.42     10466157.20
      3540646.76     10466311.53      3540807.98     10466223.51
      3540869.58     10466127.41      3540956.44     10466219.39
      3541069.53     10466097.86      3541290.60     10466067.99
      3541187.94     10465974.03      3541210.31     10465917.28
      3541380.98     10465949.51      3541458.93     10465869.90
      3541424.62     10465803.01      3541457.35     10465772.72
      3541557.63     10465840.20      3541665.95     10465813.38
      3541818.30     10465240.68      3541882.53     10465284.63
      3541953.99     10465249.66      3542004.25     10465336.74
      3542079.75     10465240.54      3542054.85     10465097.80
      3542142.88     10464942.42      3542396.46     10464999.60
      3542387.89     10464890.63      3542572.11     10464811.64

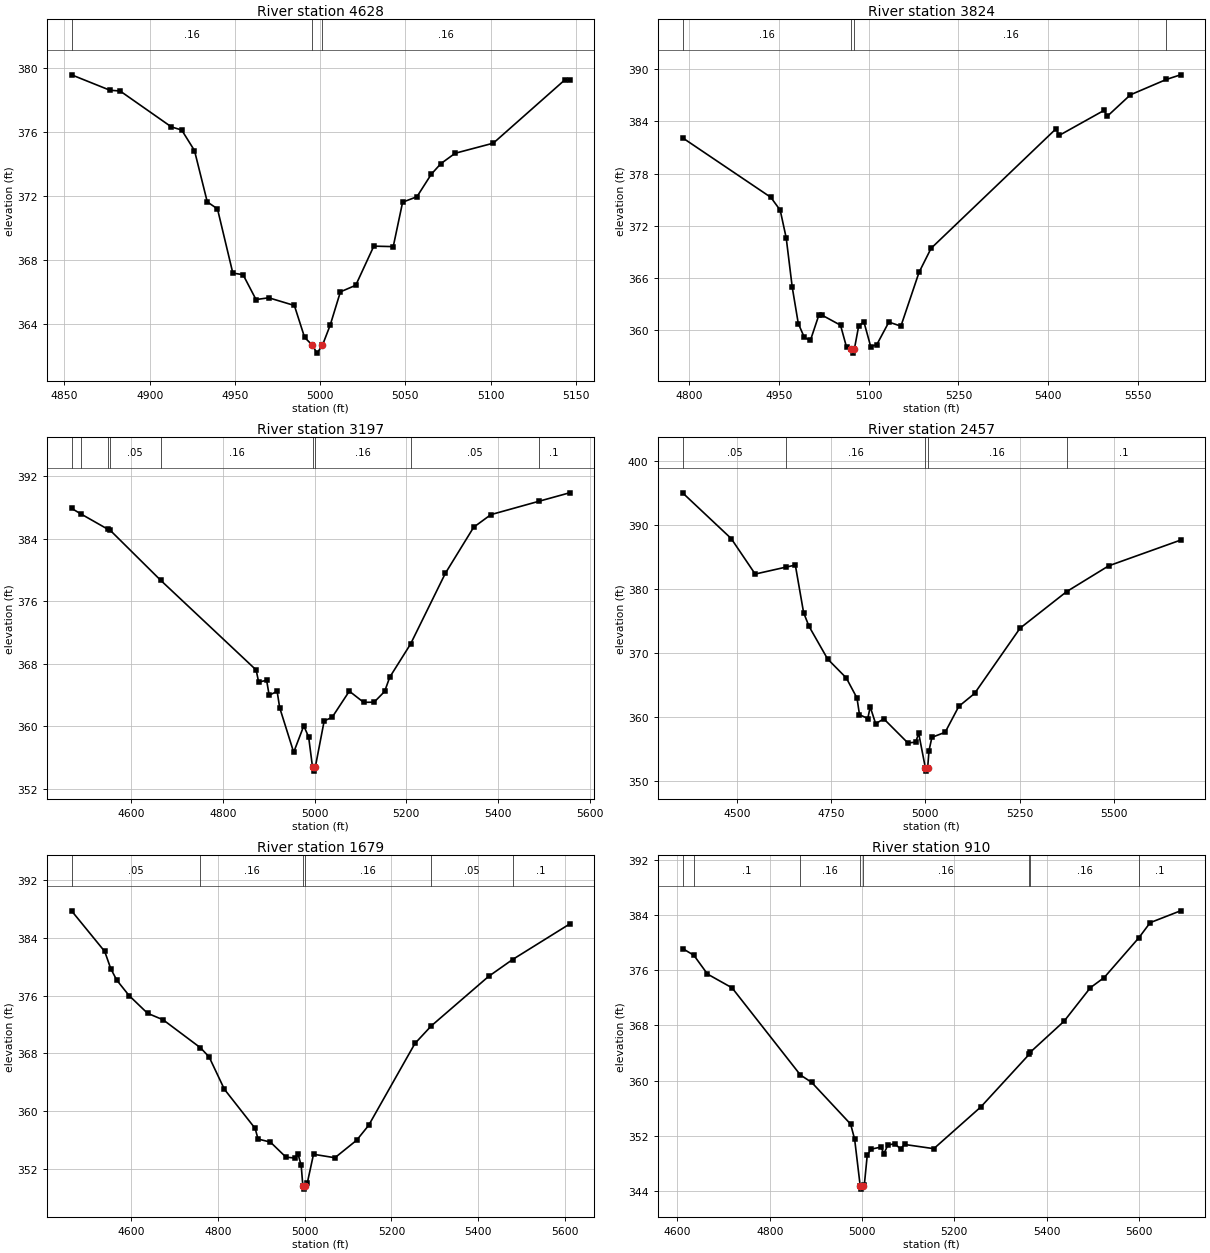
Type RM Length L Ch R = 1,4628,804,804,804
BEGIN DESCRIPTION:
UNT0752 IN SAND CR 9.0
END DESCRIPTION:
XS GIS Cut Line= 3
      3540092.10     10466341.63      3539992.11     10466191.64
      3539942.09     10466091.62
#Sta/Elev= 30
  4854.2  379.56  4876.7  378.60  4882.7  378.55  4912.8  376.31  4918.8  376.12
  4926.3  374.84  4933.8  371.64  4939.8  371.20  4948.8  367.20  4954.8  367.10
  4962.4  365.55  4969.9  365.66  4984.9  365.18  4990.9  363.19  4995.4  362.71
  4998.2  362.21  5001.4  362.71  5005.9  363.95  5011.9  366.03  5020.9  366.44
  5031.5  368.88  5042.9  368.85  5048.4  371.62  5056.8  371.96  5065.2  373.36
  5070.8  374.02  5079.2  374.67  5101.6  375.30  5143.5  379.24  5146.3  379.24
#Mann=3,-1,0
  4854.2    0.16       0  4995.4    0.07       0  5001.4    0.16       0
Bank Sta=4995.4,5001.4
Exp/Cntr=0.3,0.1

Type RM Length L Ch R = 1,3824,627,627,627
BEGIN DESCRIPTION:
UNT0752 IN SAND CR 7.0
END DESCRIPTION:
XS GIS Cut Line= 2
      3540578.71     10466513.31      3540682.89     10465688.57
#Sta/Elev= 30
  4789.5  382.12  4936.8  375.28  4952.5  373.80  4962.5  370.62  4972.6  364.94
  4982.7  360.77  4992.8  359.17  5002.9  358.83  5017.0  361.74  5023.0  361.71
  5053.2  360.58  5063.3  358.04  5070.4  357.87  5073.2  357.37  5076.4  357.87
  5083.5  360.49  5092.2  360.97  5103.6  358.12  5113.7  358.34  5133.9  360.94
  5154.0  360.47  5184.3  366.66  5204.4  369.42  5413.0  383.16  5418.1  382.39
  5493.3  385.28  5498.3  384.58  5537.1  387.06  5597.2  388.83  5620.8  389.36
#Mann=4,-1,0
  4789.5    0.16       0  5070.4    0.07       0  5076.4    0.16       0
  5597.2    0.05       0
Bank Sta=5070.4,5076.4
Exp/Cntr=0.3,0.1

Type RM Length L Ch R = 1,3197,740,740,740
BEGIN DESCRIPTION:
UNT0752 IN SAND CR 6.0
END DESCRIPTION:
XS GIS Cut Line= 2
      3541247.10     10466610.88      3540789.44     10465626.13
#Sta/Elev= 30
  4470.0  387.87  4491.6  387.12  4549.2  385.20  4553.2  385.13  4664.2  378.68
  4872.5  367.20  4878.0  365.65  4895.4  365.88  4900.9  363.96  4918.3  364.47
  4923.8  362.39  4954.4  356.67  4976.4  360.05  4987.0  358.63  4995.5  354.76
  4998.2  354.26  5001.5  354.76  5020.9  360.69  5038.2  361.14  5075.7  364.49
  5106.9  363.06  5129.8  363.08  5152.7  364.45  5163.9  366.28  5209.2  370.51
  5285.2  379.57  5346.9  385.46  5384.4  387.07  5489.2  388.78  5555.9  389.86
#Mann=9,-1,0
  4470.0    0.16       0  4491.6    0.05       0  4549.2    0.16       0
  4553.2    0.05       0  4664.2    0.16       0  4995.5    0.07       0
  5001.5    0.16       0  5209.2    0.05       0  5489.2     0.1       0
Bank Sta=4995.5,5001.5
Exp/Cntr=0.3,0.1

Type RM Length L Ch R = 1,2457,778,778,778
BEGIN DESCRIPTION:
UNT0752 IN SAND CR 4.0
END DESCRIPTION:
XS GIS Cut Line= 2
      3541895.96     10466339.62      3540898.11     10465476.27
#Sta/Elev= 30
  4356.5  395.02  4485.3  387.88  4548.9  382.33  4630.9  383.42  4655.3  383.73
  4677.2  376.31  4691.4  374.18  4740.8  369.06  4790.2  366.11  4818.7  362.96
  4825.3  360.36  4847.2  359.76  4853.8  361.57  4868.1  358.96  4889.9  359.70
  4953.6  355.94  4974.4  356.07  4982.1  357.47  4999.9  352.04  5002.7  351.54
  5005.9  352.04  5009.6  354.76  5017.2  356.82  5052.3  357.61  5088.5  361.66
  5130.2  363.67  5250.8  373.87  5373.9  379.57  5485.5  383.61  5676.0  387.63
#Mann=5,-1,0
  4356.5    0.05       0  4630.9    0.16       0  4999.9    0.07       0
  5005.9    0.16       0  5373.9     0.1       0
Bank Sta=4999.9,5005.9
Exp/Cntr=0.3,0.1

Type RM Length L Ch R = 1,1679,769,769,769
BEGIN DESCRIPTION:
UNT0752 IN SAND CR 3.0
END DESCRIPTION:
XS GIS Cut Line= 2
      3542139.02     10465862.19      3541288.39     10465091.85
#Sta/Elev= 30
  4462.8  387.76  4539.2  382.13  4553.1  379.75  4566.9  378.16  4595.3  376.02
  4637.9  373.56  4673.7  372.66  4759.9  368.78  4779.8  367.51  4814.9  363.04
  4885.9  357.60  4892.6  356.13  4921.0  355.71  4956.9  353.62  4977.8  353.50
  4984.8  354.05  4992.0  352.47  4995.8  349.69  4998.5  349.19  5001.8  349.69
  5006.2  350.07  5020.4  354.02  5069.7  353.54  5119.7  355.96  5147.4  358.02
  5254.2  369.38  5291.8  371.81  5423.9  378.67  5479.2  381.01  5610.4  385.92
#Mann=6,-1,0
  4462.8    0.05       0  4759.9    0.16       0  4995.8    0.07       0
  5001.8    0.16       0  5291.8    0.05       0  5479.2     0.1       0
Bank Sta=4995.8,5001.8
Exp/Cntr=0.3,0.1

Type RM Length L Ch R = 1,910,754,754,754
BEGIN DESCRIPTION:
UNT0752 IN SAND CR 2.0
END DESCRIPTION:
XS GIS Cut Line= 3
      3542304.46     10465510.46      3542187.26     10465263.04
      3541517.35     10464816.44
#Sta/Elev= 30
  4611.2  379.18  4635.7  378.20  4665.2  375.47  4718.4  373.47  4866.6  360.80
  4890.8  359.74  4975.3  353.67  4984.0  351.48  4996.0  344.72  4998.8  344.22
  5002.0  344.72  5005.0  344.83  5011.4  349.20  5020.0  350.03  5041.1  350.33
  5047.4  349.38  5056.1  350.63  5071.1  350.82  5083.5  350.05  5092.1  350.71
  5155.6  350.10  5257.4  356.16  5362.6  363.84  5364.8  364.13  5437.7  368.61
  5494.8  373.49  5524.8  374.97  5599.8  380.74  5624.3  382.94  5690.1  384.66
#Mann=8,-1,0
  4611.2    0.05       0  4635.7     0.1       0  4866.6    0.16       0
  4996.0    0.07       0  5002.0    0.16       0  5362.6     0.1       0
  5364.8    0.16       0  5599.8     0.1       0
Bank Sta=4996,5002
Exp/Cntr=0.3,0.1

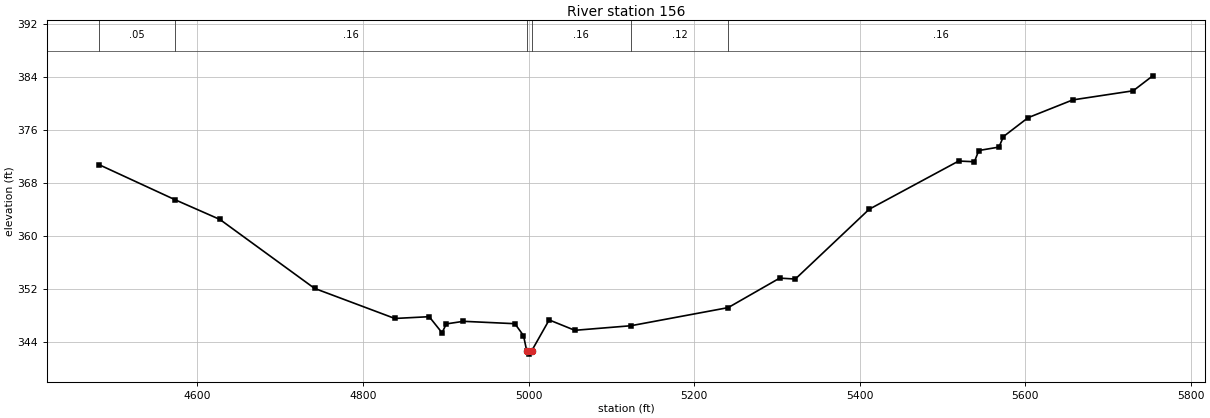
Type RM Length L Ch R = 1,156,0,0,0
BEGIN DESCRIPTION:
UNT0752 IN SAND CR 1.0
END DESCRIPTION:
XS GIS Cut Line= 4
      3542338.70     10465376.13      3542455.89     10464944.25
      3542416.83     10464796.69      3541791.85     10464549.30
#Sta/Elev= 30
  4481.5  370.79  4573.1  365.50  4627.1  362.53  4741.4  352.11  4838.4  347.56
  4879.9  347.83  4895.4  345.40  4900.6  346.74  4921.3  347.13  4983.4  346.77
  4993.8  344.97  4997.7  342.67  5000.4  342.17  5003.7  342.67  5024.8  347.34
  5055.8  345.77  5123.4  346.46  5241.0  349.20  5303.2  353.66  5322.1  353.52
  5411.3  364.07  5519.4  371.36  5538.4  371.25  5543.7  372.95  5568.1  373.47
  5573.4  375.05  5603.2  377.91  5657.2  380.60  5730.2  381.98  5753.8  384.24
#Mann=6,-1,0
  4481.5    0.05       0  4573.1    0.16       0  4997.7    0.07       0
  5003.7    0.16       0  5123.4    0.12       0  5241.0    0.16       0
Bank Sta=4997.7,5003.7
Exp/Cntr=0.3,0.1

Chan Stop Cuts=-1