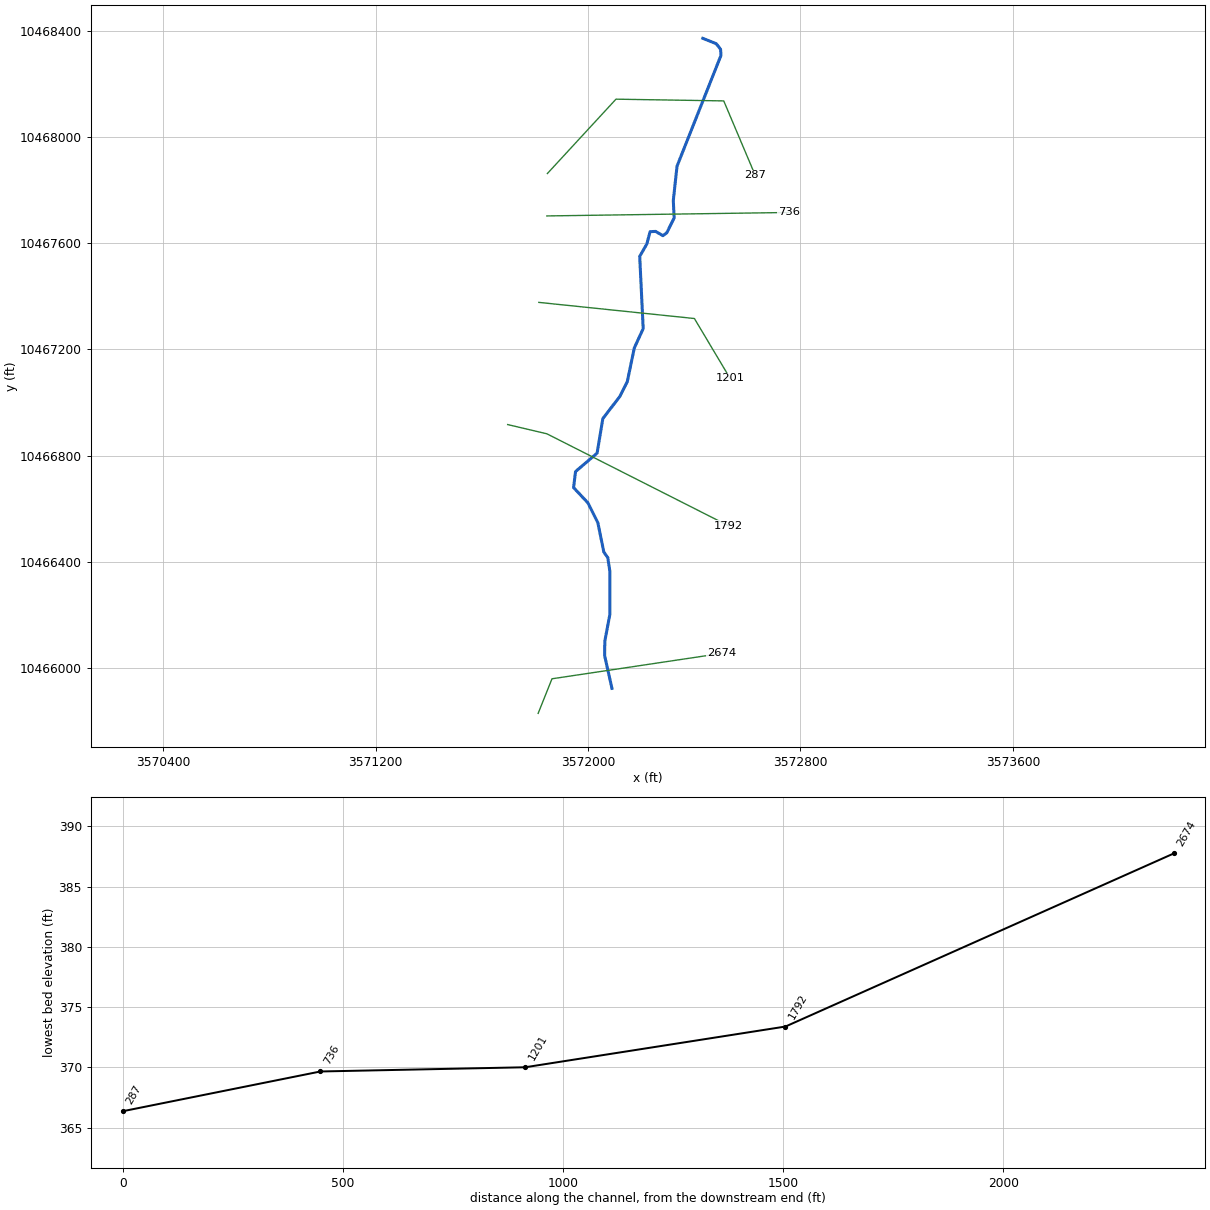
--- UNT0762 IN SAND CR.prj (project) ---

Proj Title=UNT0762 IN SAND CR Base Level Engineering
Current Plan=p01
Default Exp/Contr=0.3,0.1
English Units
Geom File=g01
Flow File=f01
Plan File=p01
BEGIN DESCRIPTION:
UNT0762 IN SAND CR
END DESCRIPTION:

--- UNT0762 IN SAND CR.p01 (plan) ---

Plan Title=Multiple Run
Short Identifier=Multiple
Geom File=g01
Flow File=f01
Subcritical Flow
K Sum by GR= 0
Std Step Tol= 0.01
Critical Tol= 0.01
Num of Std Step Trials= 20
Max Error Tol= 0.3
Flow Tol Ratio= 0.001
Split Flow NTrial= 30
Split Flow Tol= 0.02
Split Flow Ratio= 0.02
Log Output Level= 0
Friction Slope Method= 1
Unsteady Friction Slope Method= 2
Unsteady Bridges Friction Slope Method= 1
Parabolic Critical Depth
Global Vel Dist=  1 , 1 , 1
Global Log Level= 0
CheckData=True
Encroach Param= -1, 0, 0, 0
BEGIN DESCRIPTION:
Multiple Run
END DESCRIPTION:

--- UNT0762 IN SAND CR.f01 (steady flow) ---

Flow Title=Multiple
Number of Profiles=7
Profile Names=10-year,25-year,50-year,1pct_min,100-year,1pct_plu,500-year
River Rch & RM= UNT0762 IN SAND ,Reach-1,2674
     869    1188    1450    1292    1748    2364    2532
Boundary for River Rch & Prof#=UNT0762 IN SAND ,Reach-1,1
Up Type=0
Dn Type=3
Dn Slope=0.005
Boundary for River Rch & Prof#=UNT0762 IN SAND ,Reach-1,2
Up Type=0
Dn Type=3
Dn Slope=0.005
Boundary for River Rch & Prof#=UNT0762 IN SAND ,Reach-1,3
Up Type=0
Dn Type=3
Dn Slope=0.005
Boundary for River Rch & Prof#=UNT0762 IN SAND ,Reach-1,4
Up Type=0
Dn Type=3
Dn Slope=0.005
Boundary for River Rch & Prof#=UNT0762 IN SAND ,Reach-1,5
Up Type=0
Dn Type=3
Dn Slope=0.005
Boundary for River Rch & Prof#=UNT0762 IN SAND ,Reach-1,6
Up Type=0
Dn Type=3
Dn Slope=0.005
Boundary for River Rch & Prof#=UNT0762 IN SAND ,Reach-1,7
Up Type=0
Dn Type=3
Dn Slope=0.005

--- UNT0762 IN SAND CR.g01 (geometry) ---

Geom Title=Existing Conditions

River Reach=UNT0762 IN SAND ,Reach-1
Reach XY= 30
      3572090.14     10465924.10      3572062.64     10466046.97
      3572063.18     10466101.10      3572082.12     10466201.64
      3572082.30     10466364.38      3572074.55     10466415.95
      3572059.45     10466437.82      3572037.05     10466547.72
      3571999.55     10466622.72      3571945.65     10466680.01
      3571953.03     10466740.34      3572034.28     10466809.79
      3572055.92     10466940.06      3572119.52     10467022.71
      3572147.86     10467078.69      3572174.31     10467205.75
      3572207.78     10467278.55      3572194.66     10467550.55
      3572221.71     10467597.79      3572233.69     10467643.63
      3572254.52     10467644.67      3572282.13     10467628.52
      3572296.71     10467639.46      3572324.32     10467695.19
      3572321.15     10467761.16      3572335.21     10467890.35
      3572500.73     10468307.56      3572499.10     10468330.31
      3572483.00     10468351.38      3572432.11     10468371.64

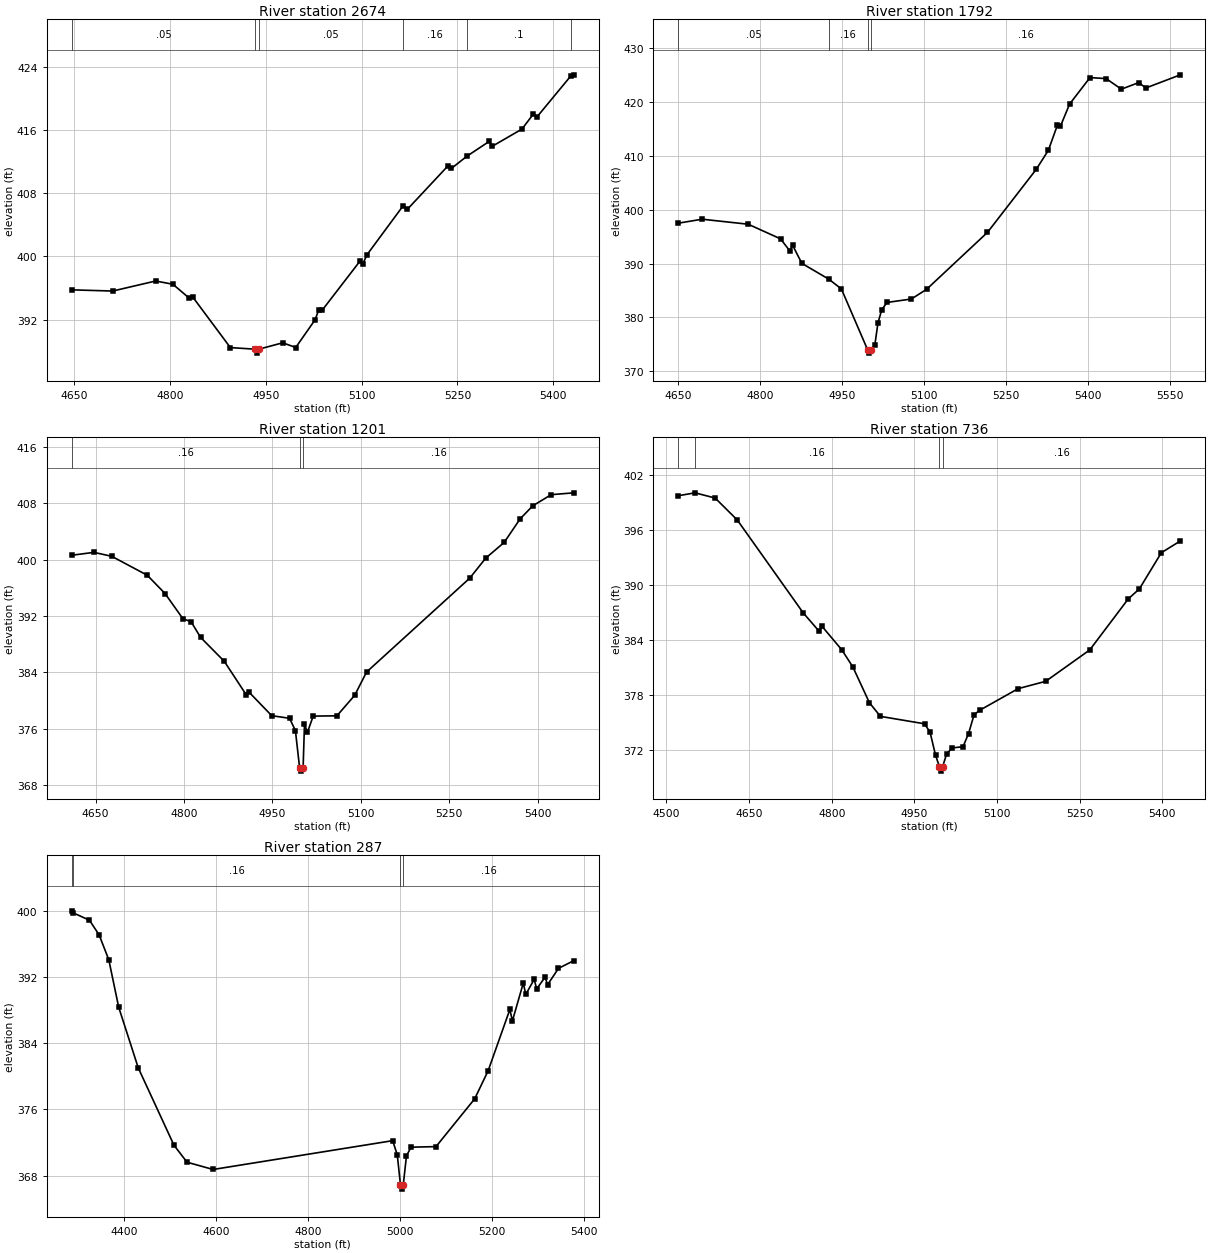
Type RM Length L Ch R = 1,2674,882,882,882
BEGIN DESCRIPTION:
UNT0762 IN SAND CR 5.0
END DESCRIPTION:
XS GIS Cut Line= 3
      3571812.25     10465829.86      3571864.35     10465960.10
      3572502.37     10466055.59
#Sta/Elev= 30
  4646.7  395.76  4710.7  395.61  4777.9  396.88  4804.9  396.47  4830.7  394.69
  4835.7  394.88  4894.8  388.45  4933.4  388.25  4936.1  387.75  4939.4  388.25
  4976.8  389.06  4997.0  388.46  5027.4  391.98  5033.1  393.25  5038.2  393.16
  5097.3  399.37  5102.3  399.09  5108.3  400.18  5165.3  406.43  5171.5  405.94
  5235.6  411.49  5240.7  411.14  5264.7  412.67  5299.7  414.55  5304.8  413.95
  5350.9  416.11  5368.9  418.03  5373.9  417.60  5427.3  422.83  5432.1  422.98
#Mann=6,-1,0
  4646.7    0.05       0  4933.4   0.035       0  4939.4    0.05       0
  5165.3    0.16       0  5264.7     0.1       0  5427.3    0.16       0
Bank Sta=4933.4,4939.4
Exp/Cntr=0.3,0.1

Type RM Length L Ch R = 1,1792,591,591,591
BEGIN DESCRIPTION:
UNT0762 IN SAND CR 3.0
END DESCRIPTION:
XS GIS Cut Line= 3
      3571697.48     10466917.34      3571845.06     10466882.61
      3572529.60     10466536.01
#Sta/Elev= 30
  4650.3  397.48  4694.0  398.22  4778.3  397.29  4837.5  394.58  4854.2  392.38
  4859.8  393.36  4876.5  390.03  4925.7  387.11  4948.9  385.29  4997.4  373.88
  5000.1  373.38  5003.4  373.88  5010.2  374.95  5015.8  378.96  5022.8  381.44
  5032.4  382.78  5077.0  383.42  5104.9  385.22  5216.3  395.78  5305.4  407.45
  5327.7  411.00  5344.3  415.68  5349.9  415.49  5366.6  419.58  5403.9  424.49
  5433.4  424.30  5461.3  422.34  5493.5  423.57  5505.9  422.55  5569.2  425.00
#Mann=4,-1,0
  4650.3    0.05       0  4925.7    0.16       0  4997.4    0.07       0
  5003.4    0.16       0
Bank Sta=4997.4,5003.4
Exp/Cntr=0.3,0.1

Type RM Length L Ch R = 1,1201,465,465,465
BEGIN DESCRIPTION:
UNT0762 IN SAND CR 2.0
END DESCRIPTION:
XS GIS Cut Line= 3
      3571814.71     10467377.40      3572400.62     10467316.64
      3572535.16     10467090.95
#Sta/Elev= 30
  4609.5  400.64  4647.1  401.05  4677.3  400.49  4737.6  397.80  4767.7  395.21
  4797.9  391.65  4811.9  391.20  4828.1  388.98  4868.3  385.58  4905.6  380.82
  4910.6  381.18  4948.7  377.87  4978.9  377.50  4988.9  375.76  4996.0  370.50
  4998.7  370.00  5002.0  370.50  5004.3  376.65  5009.4  375.53  5019.1  377.81
  5059.3  377.85  5089.5  380.76  5109.6  384.06  5284.7  397.39  5311.9  400.24
  5343.1  402.46  5370.3  405.82  5391.7  407.66  5422.9  409.24  5461.3  409.50
#Mann=3,-1,0
  4609.5    0.16       0  4996.0    0.07       0  5002.0    0.16       0
Bank Sta=4996,5002
Exp/Cntr=0.3,0.1

Type RM Length L Ch R = 1,736,449,449,449
BEGIN DESCRIPTION:
UNT0762 IN SAND CR 1.0
END DESCRIPTION:
XS GIS Cut Line= 2
      3571845.07     10467702.93      3572756.47     10467715.95
#Sta/Elev= 30
  4521.4  399.73  4551.9  400.05  4588.4  399.48  4628.5  397.09  4748.5  386.92
  4777.5  384.91  4782.5  385.46  4818.5  382.89  4838.5  381.02  4868.5  377.12
  4888.5  375.63  4968.5  374.82  4978.5  373.92  4988.5  371.39  4995.5  370.15
  4998.2  369.65  5001.5  370.15  5008.5  371.51  5018.5  372.18  5038.5  372.32
  5048.5  373.76  5058.5  375.81  5068.5  376.29  5138.5  378.66  5188.5  379.46
  5268.5  382.89  5338.5  388.47  5358.5  389.55  5398.5  393.51  5432.9  394.79
#Mann=4,-1,0
  4521.4    0.05       0  4551.9    0.16       0  4995.5    0.07       0
  5001.5    0.16       0
Bank Sta=4995.5,5001.5
Exp/Cntr=0.3,0.1

Type RM Length L Ch R = 1,287,0,0,0
BEGIN DESCRIPTION:
UNT0762 IN SAND CR 1.1
END DESCRIPTION:
XS GIS Cut Line= 4
      3571847.04     10467862.61      3572105.30     10468142.56
      3572511.11     10468136.05      3572629.90     10467855.29
#Sta/Elev= 30
  4287.0  400.06  4289.1  399.84  4325.5  398.92  4346.5  397.14  4367.5  394.13
  4389.0  388.39  4431.6  381.03  4509.2  371.67  4537.6  369.61  4594.3  368.73
  4984.7  372.22  4994.7  370.50  5001.7  366.85  5004.5  366.35  5007.7  366.85
  5014.7  370.39  5024.7  371.43  5078.9  371.50  5163.0  377.29  5192.2  380.68
  5239.5  388.11  5245.0  386.73  5268.7  391.31  5274.1  389.94  5292.4  391.76
  5297.8  390.60  5316.0  392.02  5321.5  391.11  5345.2  393.09  5378.6  394.03
#Mann=4,-1,0
  4287.0    0.05       0  4289.1    0.16       0  5001.7    0.07       0
  5007.7    0.16       0
Bank Sta=5001.7,5007.7
Exp/Cntr=0.3,0.1

Chan Stop Cuts=-1