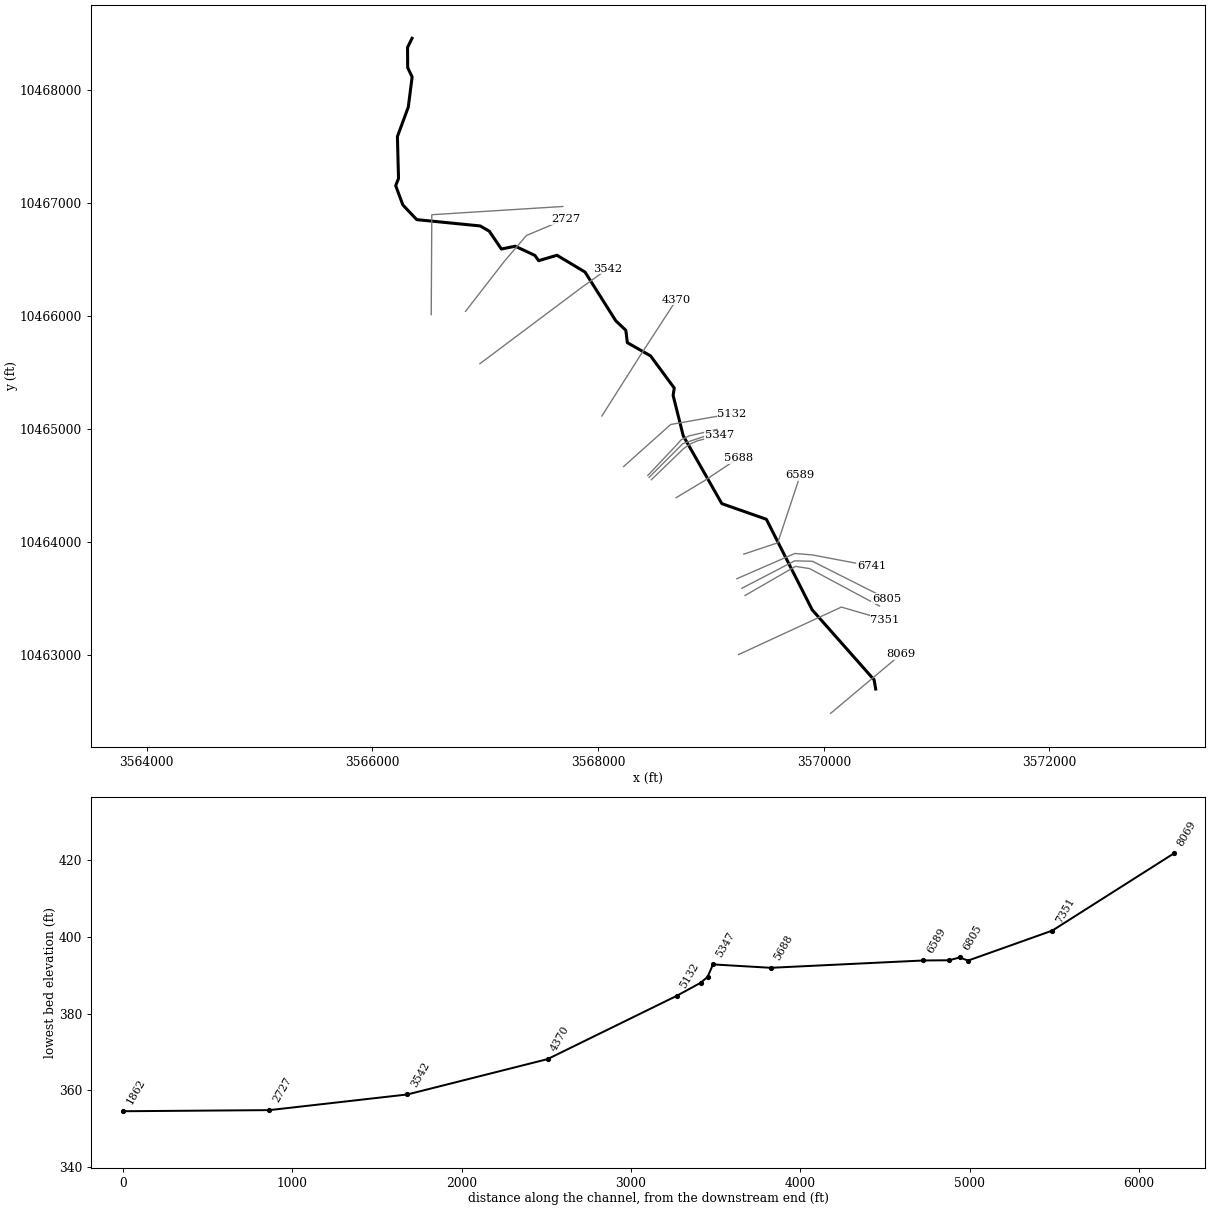
--- UNT0765 IN SAND CR.prj (project) ---

Proj Title=UNT0765 IN SAND CR Base Level Engineering
Current Plan=p01
Default Exp/Contr=0.3,0.1
English Units
Geom File=g01
Flow File=f01
Plan File=p01
Y Axis Title=Elevation
X Axis Title(PF)=Main Channel Distance
X Axis Title(XS)=Station
BEGIN DESCRIPTION:
UNT0765 IN SAND CR
END DESCRIPTION:
DSS Export Rating Curves= 0
DSS Export Rating Curve Sorted= 0
DSS Export Volume Flow Curves= 0
DXF OffsetX= 0
DXF OffsetY= 0
DXF ScaleX= 1
DXF ScaleY= 10

--- UNT0765 IN SAND CR.p01 (plan) ---

Plan Title=Multiple Run
Short Identifier=Multiple
Geom File=g01
Flow File=f01
Subcritical Flow
K Sum by GR= 0
Std Step Tol= 0.01
Critical Tol= 0.01
Num of Std Step Trials= 20
Max Error Tol= 0.3
Flow Tol Ratio= 0.001
Split Flow NTrial= 30
Split Flow Tol= 0.02
Split Flow Ratio= 0.02
Log Output Level= 0
Friction Slope Method= 1
Unsteady Friction Slope Method= 2
Unsteady Bridges Friction Slope Method= 1
Parabolic Critical Depth
Global Vel Dist=  1 , 1 , 1
Global Log Level= 0
CheckData=True
Encroach Param= -1, 0, 0, 0
BEGIN DESCRIPTION:
Multiple Run
END DESCRIPTION:

--- UNT0765 IN SAND CR.f01 (steady flow) ---

Flow Title=Multiple
Number of Profiles=7
Profile Names=10-year,25-year,50-year,1pct_min,100-year,1pct_plu,500-year
River Rch & RM= UNT0765 IN SAND ,Reach-1,8069
    1130    1587    1975    1795    2428    3283    3657
Boundary for River Rch & Prof#=UNT0765 IN SAND ,Reach-1,1
Up Type=0
Dn Type=3
Dn Slope=0.005
Boundary for River Rch & Prof#=UNT0765 IN SAND ,Reach-1,2
Up Type=0
Dn Type=3
Dn Slope=0.005
Boundary for River Rch & Prof#=UNT0765 IN SAND ,Reach-1,3
Up Type=0
Dn Type=3
Dn Slope=0.005
Boundary for River Rch & Prof#=UNT0765 IN SAND ,Reach-1,4
Up Type=0
Dn Type=3
Dn Slope=0.005
Boundary for River Rch & Prof#=UNT0765 IN SAND ,Reach-1,5
Up Type=0
Dn Type=3
Dn Slope=0.005
Boundary for River Rch & Prof#=UNT0765 IN SAND ,Reach-1,6
Up Type=0
Dn Type=3
Dn Slope=0.005
Boundary for River Rch & Prof#=UNT0765 IN SAND ,Reach-1,7
Up Type=0
Dn Type=3
Dn Slope=0.005

--- UNT0765 IN SAND CR.g01 (geometry) ---

Geom Title=Existing Conditions
Program Version=4.10

River Reach=UNT0765 IN SAND ,Reach-1
Reach XY= 30
      3570460.26      10462696.2      3570446.37     10462777.45
       3569897.7     10463397.65      3569491.56     10464200.36
      3569096.92     10464338.77       3568754.9     10464940.33
      3568665.37     10465297.49      3568675.22     10465363.12
      3568465.28     10465647.96      3568259.75     10465765.35
      3568246.55     10465874.11      3568157.08      10465959.2
       3567884.7     10466390.78      3567636.16     10466539.55
      3567473.53     10466491.68      3567440.38     10466538.25
      3567266.65     10466619.71      3567143.56      10466594.9
      3567036.53     10466752.68      3566956.42     10466799.25
      3566393.61     10466855.29      3566270.62     10466985.25
      3566207.07     10467156.61      3566232.22     10467220.13
      3566222.43     10467591.51      3566318.87     10467852.61
      3566352.77     10468119.31      3566313.37     10468202.08
      3566312.19      10468381.6      3566352.11     10468461.64

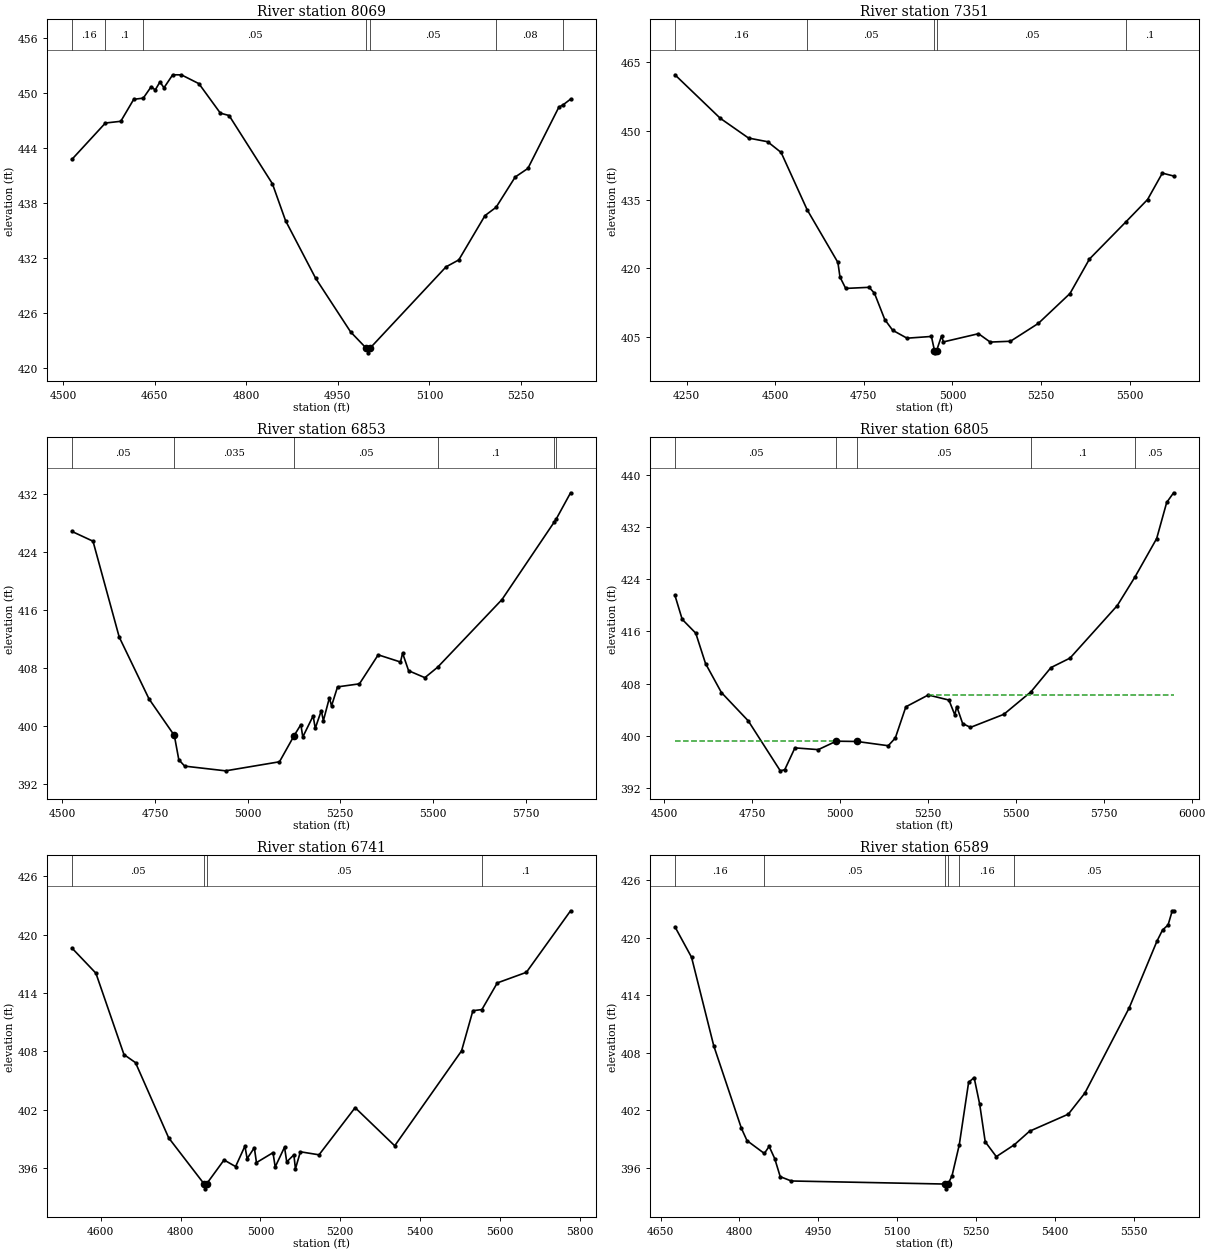
Type RM Length L Ch R = 1 ,8069    ,718,718,718
BEGIN DESCRIPTION:
UNT0765 IN SAND CR 9.5
END DESCRIPTION:
XS GIS Cut Line= 2
      3570060.86     10462480.45      3570685.82     10463005.59
#Sta/Elev= 30
  4514.7  442.75  4569.5  446.72  4594.7  446.91  4615.9  449.31  4631.5  449.44
  4644.5  450.69  4651.1  450.33  4658.8  451.21  4665.4  450.57  4679.7  451.99
    4694  451.98  4722.6  451.02  4757.7   447.8    4772  447.54  4842.9  440.09
  4864.4  436.06  4913.8  429.75    4971   423.9  4996.6  422.12  4999.4  421.62
  5002.6  422.12  5127.1  431.01    5148  431.77  5190.9  436.61  5209.1  437.52
  5240.3  440.82  5261.1  441.76  5311.8  448.45  5319.4  448.74    5331  449.33
#Mann= 7 ,-1 , 0
  4514.7     .16       0  4569.5      .1       0  4631.5     .05       0
  4996.6     .03       0  5002.6     .05       0  5209.1     .08       0
  5319.4     .05       0
Bank Sta=4996.6,5002.6
XS Rating Curve= 0 ,0
Exp/Cntr=0.3,0.1

Type RM Length L Ch R = 1 ,7351    ,498,498,498
BEGIN DESCRIPTION:
UNT0765 IN SAND CR 9.4
END DESCRIPTION:
XS GIS Cut Line= 3
      3569244.89     10463001.28      3570156.33     10463422.28
      3570542.61     10463309.44
#Sta/Elev= 30
  4217.2  462.29    4345  452.79  4424.8  448.47  4478.5  447.67  4516.6  445.33
    4590  432.82  4676.8   421.3  4682.7  418.11  4698.8  415.63  4764.9  415.87
  4779.9  414.58    4809  408.83  4831.3  406.49  4871.7  404.76  4940.5  405.14
  4949.2  402.06  4951.9  401.56  4955.2  402.06    4969  405.23  4974.5  403.95
  5073.3  405.74  5106.4  403.91  5163.5  404.09  5242.1  407.99  5331.4  414.52
  5386.3  422.05  5489.9  430.23  5550.2  435.05  5591.8  440.81  5623.6  440.18
#Mann= 5 ,-1 , 0
  4217.2     .16       0    4590     .05       0  4949.2    .035       0
  4955.2     .05       0  5489.9      .1       0
Bank Sta=4949.2,4955.2
XS Rating Curve= 0 ,0
Exp/Cntr=0.3,0.1

Type RM Length L Ch R = 1 ,6853    ,48,48,48
BEGIN DESCRIPTION:
UNT0765 IN SAND CR 9.2
END DESCRIPTION:
XS GIS Cut Line= 4
      3569302.82     10463525.08      3569749.43     10463782.89
      3569874.43     10463763.36       3570494.2     10463431.34
#Sta/Elev= 30
    4526  426.78  4582.9  425.43  4653.6  412.21    4734  403.68  4802.3  398.64
  4814.4  395.29  4830.2  394.41  4940.6  393.76    5086  395.01  5125.4  398.61
  5143.7  400.14  5148.8  398.43  5176.8  401.34  5182.5  399.62  5198.8  402.07
  5204.4  400.68  5220.7  403.84  5226.4  402.71  5242.6  405.34  5301.7  405.76
  5352.3  409.76  5412.4  408.77  5418.1  409.99  5434.3  407.57  5478.2  406.61
  5512.8  408.06  5686.2  417.38  5826.6  428.03  5833.2  428.55  5871.3  432.11
#Mann= 6 ,-1 , 0
    4526     .05       0  4802.3    .035       0  5125.4     .05       0
  5512.8      .1       0  5826.6     .05       0  5833.2      .1       0
Bank Sta=4802.3,5125.4
XS Rating Curve= 0 ,0
Exp/Cntr=0.3,0.1

Type RM Length L Ch R = 1 ,6805    ,64,64,64
BEGIN DESCRIPTION:
UNT0765 IN SAND CR 9.1
END DESCRIPTION:
XS GIS Cut Line= 4
      3569274.85     10463589.22      3569743.57     10463832.26
      3569899.82     10463827.92       3570555.2     10463498.06
#Sta/Elev= 30
  4530.7  421.55  4551.3  417.87  4589.9  415.74  4617.7  411.07  4662.8  406.62
  4739.2  402.26  4830.3  394.58    4843  394.76  4871.9  398.11  4938.3  397.84
  4989.4  399.14  5048.9  399.09  5137.2  398.44  5157.3  399.62  5187.3  404.42
  5251.1  406.24  5309.8  405.46  5326.5  403.18  5332.1  404.46  5348.8  401.85
  5371.1  401.26    5466  403.27  5543.1  406.73  5599.9  410.45  5654.2  411.91
  5788.5  419.98  5839.5  424.44  5900.5  430.28    5929  435.83  5948.7  437.32
#Mann= 5 ,-1 , 0
  4530.7     .05       0  4989.4    .035       0  5048.9     .05       0
  5543.1      .1       0  5839.5     .05       0
#XS Ineff= 2 , 0
       0 4985.81   399.1 5250.92       0  406.26
Permanent Ineff=
       T       F
Bank Sta=4989.4,5048.9
XS Rating Curve= 0 ,0
Exp/Cntr=0.3,0.1

Type RM Length L Ch R = 1 ,6741    ,152,152,152
BEGIN DESCRIPTION:
UNT0765 IN SAND CR 9.3
END DESCRIPTION:
XS GIS Cut Line= 4
      3569229.91     10463673.52      3569744.22     10463897.47
      3569897.87     10463884.45      3570422.57      10463785.5
#Sta/Elev= 30
  4527.9  418.62    4588  416.03  4658.3  407.66  4687.2  406.83  4770.2   399.1
  4859.1  394.35  4861.9  393.85  4865.1  394.35    4909  396.82  4937.9  396.14
  4961.3  398.25  4966.8  396.95  4984.8  398.08  4990.2  396.55  5031.6  397.57
  5037.1   396.1  5060.5  398.14    5066  396.62  5083.9  397.35  5087.8  395.91
  5100.2  397.66  5146.9  397.35  5237.3   402.2  5336.5  398.28  5503.9  408.04
  5532.3  412.17  5554.9  412.29  5593.4  415.03  5666.3  416.12    5777  422.45
#Mann= 4 ,-1 , 0
  4527.9     .05       0  4859.1    .035       0  4865.1     .05       0
  5554.9      .1       0
Bank Sta=4859.1,4865.1
XS Rating Curve= 0 ,0
Exp/Cntr=0.3,0.1

Type RM Length L Ch R = 1 ,6589    ,901,901,901
BEGIN DESCRIPTION:
UNT0765 IN SAND CR 9.0
END DESCRIPTION:
XS GIS Cut Line= 3
      3569292.09     10463891.64      3569592.11     10463991.64
       3569792.1     10464591.64
#Sta/Elev= 30
  4677.4  421.13    4709  417.95  4751.2  408.72  4803.9   400.1  4814.5  398.82
  4847.5  397.48  4856.6  398.22  4867.2  396.95  4877.7  395.06  4898.8  394.61
  5190.9  394.29  5193.7  393.79  5196.9  394.29  5204.5  395.14  5218.3  398.37
  5236.1   404.9  5246.6   405.4  5257.2  402.61  5267.7   398.7  5288.8  397.15
  5323.1  398.39    5352   399.8  5425.8  401.58  5457.4  403.79  5541.8  412.69
  5594.5  419.64    5605  420.79  5615.6  421.32  5623.5   422.8  5626.1   422.8
#Mann= 6 ,-1 , 0
  4677.4     .16       0  4847.5     .05       0  5190.9    .035       0
  5196.9     .05       0  5218.3     .16       0  5323.1     .05       0
Bank Sta=5190.9,5196.9
XS Rating Curve= 0 ,0
Exp/Cntr=0.3,0.1

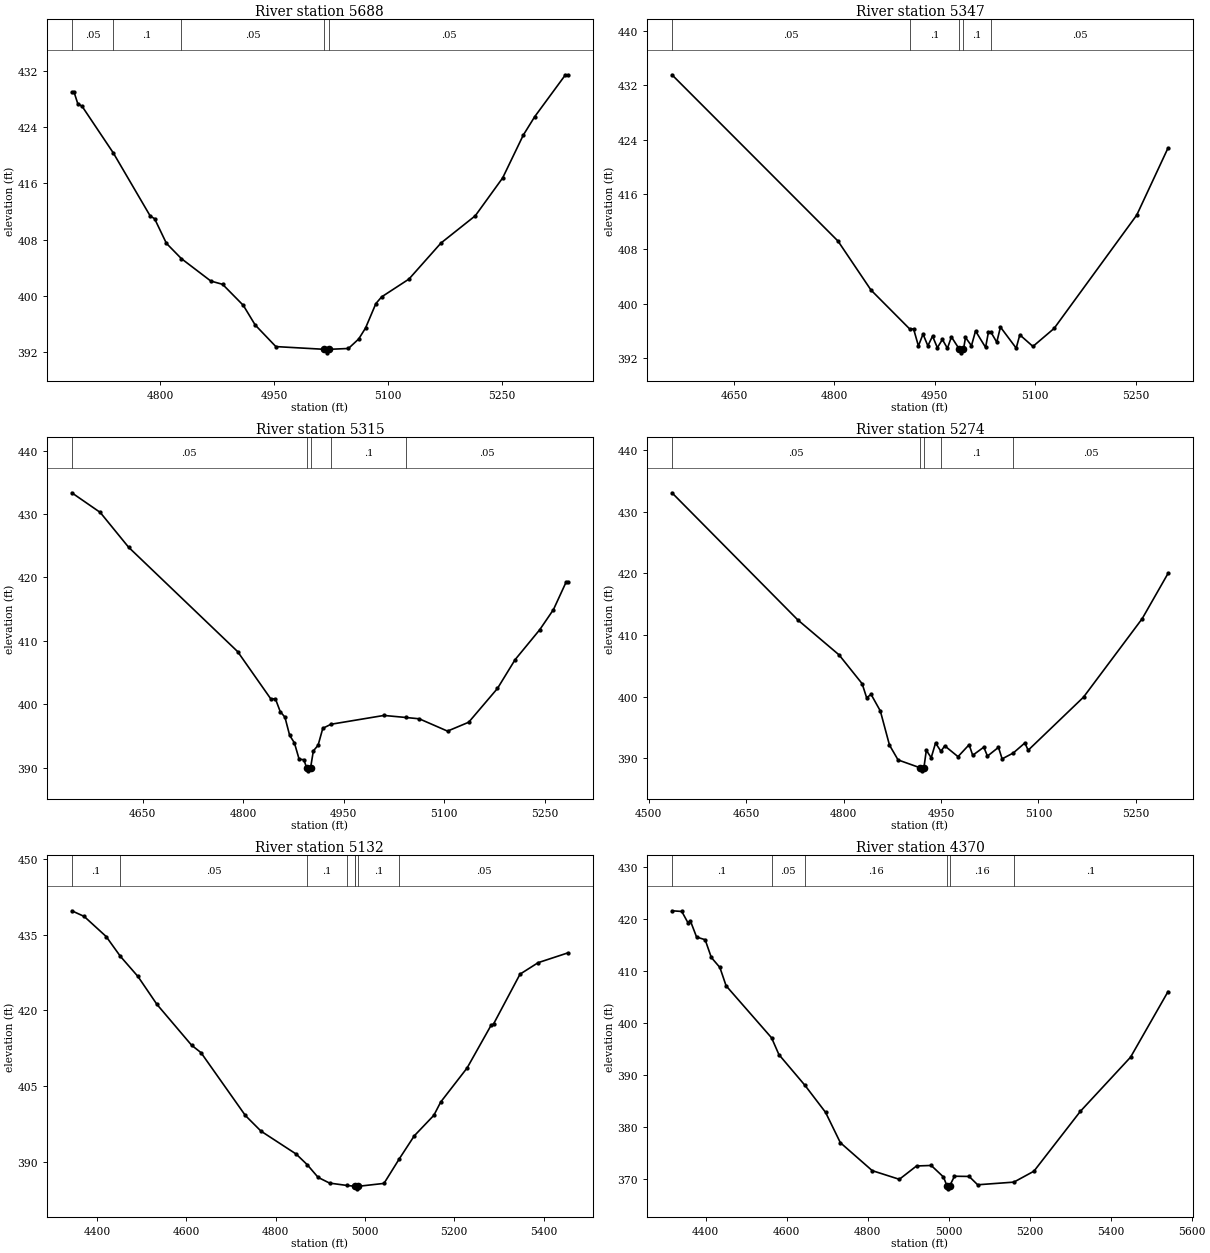
Type RM Length L Ch R = 1 ,5688    ,341,341,341
BEGIN DESCRIPTION:
UNT0765 IN SAND CR 7.0
END DESCRIPTION:
XS GIS Cut Line= 3
      3568692.06     10464391.62      3568942.11     10464541.64
      3569242.15     10464741.67
#Sta/Elev= 30
    4684     429    4687     429  4691.8  427.38  4697.7  426.96  4738.5  420.36
  4787.1  411.37  4792.9  410.98  4808.4  407.48  4828.1   405.3  4866.8  402.11
  4882.3  401.64  4909.5  398.65  4925.1  395.86  4952.3  392.78  5016.2  392.39
  5018.9  391.89  5022.2  392.39  5047.7  392.51  5061.2  393.86  5070.2  395.42
  5083.8   398.9  5091.3  399.85  5127.3  402.39  5169.4  407.52  5214.5   411.4
  5250.5  416.79  5277.6  422.88  5292.6   425.5  5333.1  431.47  5336.2  431.47
#Mann= 5 ,-1 , 0
    4684     .05       0  4738.5      .1       0  4828.1     .05       0
  5016.2    .033       0  5022.2     .05       0
Bank Sta=5016.2,5022.2
XS Rating Curve= 0 ,0
Exp/Cntr=0.3,0.1

Type RM Length L Ch R = 1 ,5347    ,32,32,32
BEGIN DESCRIPTION:
UNT0765 IN SAND CR 6.1
END DESCRIPTION:
XS GIS Cut Line= 5
      3568472.48     10464550.95      3568760.27     10464828.33
      3568824.07      10464871.3      3568881.36     10464896.04
      3569077.54     10464942.81
#Sta/Elev= 30
  4557.5  433.56  4805.4  409.17  4854.7  401.98  4912.3  396.29  4918.3  396.28
  4925.5  393.78  4932.4  395.52  4939.6   393.8  4946.6  395.22  4953.8  393.52
  4961.3  394.73  4968.8  393.43  4974.8  395.11  4986.8  393.27  4989.5  392.77
  4992.8  393.27  4995.8  395.03  5004.7  393.81  5010.8  395.98  5025.8  393.56
    5030  395.78  5033.9  395.78  5042.5  394.33    5048  396.55  5071.5  393.46
  5076.9  395.41  5096.5  393.71  5128.1  396.35  5251.5  412.98  5298.2  422.82
#Mann= 5 ,-1 , 0
  4557.5     .05       0  4912.3      .1       0  4986.8     .07       0
  4992.8      .1       0  5033.9     .05       0
Bank Sta=4986.8,4992.8
XS Rating Curve= 0 ,0
Exp/Cntr=0.3,0.1

Type RM Length L Ch R = 1 ,5315    ,41,41,41
BEGIN DESCRIPTION:
UNT0765 IN SAND CR 6.0
END DESCRIPTION:
XS GIS Cut Line= 3
      3568452.49      10464571.3      3568752.52     10464871.33
      3569052.49     10464971.32
#Sta/Elev= 30
  4544.3  433.35  4586.7  430.26  4629.1  424.77  4791.8  408.33  4841.3  400.88
  4848.3  400.87  4855.4  398.88  4862.5  397.98  4869.5  395.13  4876.6  393.94
  4883.7  391.35  4890.7  391.29  4894.8  390.03  4897.6  389.53  4900.8  390.03
  4904.9  392.67    4912  393.57    4919  396.23  4931.2  396.87  5010.3  398.26
  5042.9  397.94    5063  397.73  5105.2  395.79  5136.8  397.19  5179.7  402.51
    5206  407.04  5242.9  411.78  5263.3  414.94    5282  419.23  5284.8  419.23
#Mann= 5 ,-1 , 0
  4544.3     .05       0  4894.8     .07       0  4900.8     .05       0
  4931.2      .1       0  5042.9     .05       0
Bank Sta=4894.8,4900.8
XS Rating Curve= 0 ,0
Exp/Cntr=0.3,0.1

Type RM Length L Ch R = 1 ,5274    ,142,142,142
BEGIN DESCRIPTION:
UNT0765 IN SAND CR 6.2
END DESCRIPTION:
XS GIS Cut Line= 5
      3568441.27     10464588.76      3568683.45     10464845.26
      3568736.83     10464905.15      3568807.15     10464939.01
      3569053.23      10464996.3
#Sta/Elev= 30
  4535.8  433.08  4729.5  412.47  4793.1  406.79  4828.6  402.12  4835.5  399.85
  4842.4  400.38  4856.6   397.7  4870.7  392.16  4883.9  389.76  4917.7  388.49
  4920.4  387.99  4923.7  388.49  4927.4  391.33  4934.9  390.11  4941.6   392.5
  4949.9  391.16  4955.8  392.04  4976.2  390.29  4993.3  392.23  4998.8  390.51
  5015.9  391.83  5021.5  390.38  5038.5   391.8  5044.1  389.93  5061.2  390.88
  5079.1  392.51  5084.2  391.33  5169.4  399.94  5259.7  412.66  5299.5     420
#Mann= 5 ,-1 , 0
  4535.8     .05       0  4917.7     .07       0  4923.7     .05       0
  4949.9      .1       0  5061.2     .05       0
Bank Sta=4917.7,4923.7
XS Rating Curve= 0 ,0
Exp/Cntr=0.3,0.1

Type RM Length L Ch R = 1 ,5132    ,762,762,762
BEGIN DESCRIPTION:
UNT0765 IN SAND CR 5.0
END DESCRIPTION:
XS GIS Cut Line= 3
      3568227.12     10464667.62      3568643.78       10465040.
       3569187.6     10465136.28
#Sta/Elev= 30
  4343.4  439.79  4371.1  438.67  4420.4  434.68  4452.4  430.73  4491.5  426.76
  4534.1  421.21  4611.8   413.1  4632.8  411.63  4732.2  399.15  4767.3  396.04
  4845.9   391.5  4870.8  389.38  4895.2  386.86  4920.8  385.73  4959.9  385.26
  4977.5   385.1  4978.8  385.09  4981.5  384.59  4984.8  385.09  5042.7  385.67
  5077.2  390.58  5110.5  395.11  5154.4  399.19  5169.7  401.82  5228.8  408.58
  5282.9  417.11    5288   417.3  5347.4  427.21    5388  429.49  5454.5  431.43
#Mann= 8 ,-1 , 0
  4343.4      .1       0  4452.4     .05       0  4870.8      .1       0
  4959.9     .05       0  4977.5      .1       0  4978.8     .07       0
  4984.8      .1       0  5077.2     .05       0
Bank Sta=4978.8,4984.8
XS Rating Curve= 0 ,0
Exp/Cntr=0.3,0.1

Type RM Length L Ch R = 1 ,4370    ,828,828,828
BEGIN DESCRIPTION:
UNT0765 IN SAND CR 4.0
END DESCRIPTION:
XS GIS Cut Line= 3
      3568034.41     10465115.54       3568364.6     10465636.63
      3568695.83     10466146.73
#Sta/Elev= 30
  4316.5  421.55  4340.8  421.42  4356.1  419.24    4362  419.62  4377.3  416.51
  4398.5  415.99  4413.7  412.59  4434.9  410.66  4450.2  407.15  4562.6  397.15
  4580.7  393.93    4645  388.03  4695.9  382.84  4732.4  377.02  4811.2  371.65
  4878.1  369.99  4920.5  372.55  4956.8  372.65  4987.1  370.43    4996  368.66
  4998.8  368.16    5002  368.66  5014.2  370.58  5050.4  370.54  5071.5  368.94
  5160.9  369.45  5210.5  371.55  5325.2  383.05  5449.1  393.44  5541.6  406.03
#Mann= 6 ,-1 , 0
  4316.5      .1       0  4562.6     .05       0    4645     .16       0
    4996     .07       0    5002     .16       0  5160.9      .1       0
Bank Sta=4996,5002
XS Rating Curve= 0 ,0
Exp/Cntr=0.3,0.1

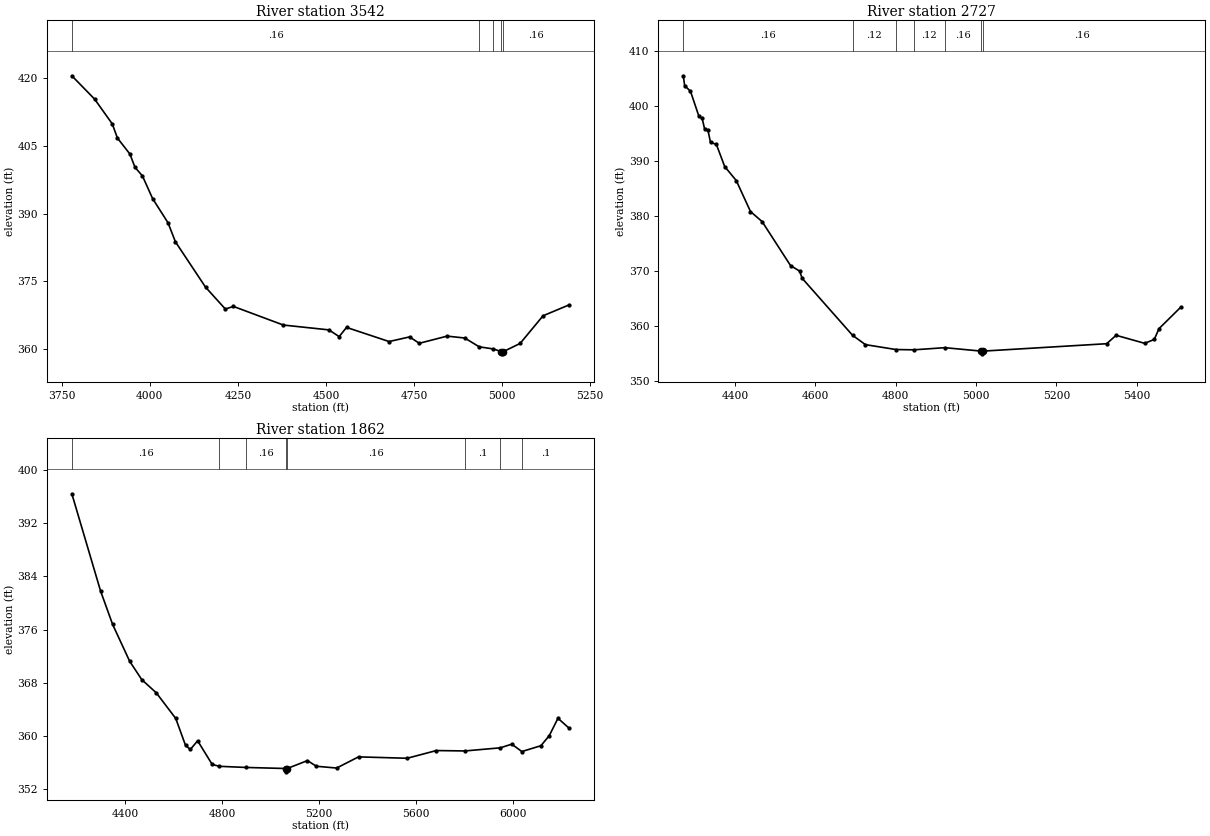
Type RM Length L Ch R = 1 ,3542    ,815,815,815
BEGIN DESCRIPTION:
UNT0765 IN SAND CR 4.1
END DESCRIPTION:
XS GIS Cut Line= 3
      3566953.67     10465579.06      3567857.32     10466256.15
      3568086.48     10466420.21
#Sta/Elev= 30
    3779  420.49  3843.7  415.32  3893.7  409.85  3908.3  406.72  3943.7  403.18
  3958.3  400.22  3979.2  398.35  4008.3   393.3  4051.9  387.97  4072.9  383.76
  4158.3  373.73  4214.6  368.88  4237.5  369.46  4379.2  365.34  4508.4  364.27
  4537.6  362.78  4558.4  364.82  4679.2  361.69  4737.6  362.72  4764.7   361.3
  4843.9  362.89  4893.9  362.47    4935  360.52  4974.5  360.06  4997.6  359.47
  5000.4  358.97  5003.6  359.47    5051  361.27  5116.1  367.39    5190   369.8
#Mann= 5 ,-1 , 0
    3779     .16       0    4935     .12       0  4974.5     .16       0
  4997.6     .07       0  5003.6     .16       0
Bank Sta=4997.6,5003.6
XS Rating Curve= 0 ,0
Exp/Cntr=0.3,0.1

Type RM Length L Ch R = 1 ,2727    ,865,865,865
BEGIN DESCRIPTION:
UNT0765 IN SAND CR 3.0
END DESCRIPTION:
XS GIS Cut Line= 4
      3566826.08     10466042.62      3567167.22     10466482.71
      3567365.13     10466714.48      3567711.48     10466860.31
#Sta/Elev= 30
  4271.7  405.43  4275.1  403.63  4289.6  402.62  4310.4   398.1  4318.6  397.71
  4324.9  395.71    4333  395.54  4339.4  393.32  4353.9  392.98  4374.7  388.94
  4403.6  386.38  4438.9  380.76  4467.9  378.93  4538.5  370.95  4561.2  369.93
  4567.5  368.63    4693  358.26    4725  356.57  4801.2  355.68  4845.6  355.63
  4922.4  356.02  5012.5   355.4  5015.2   354.9  5018.5   355.4  5325.3  356.74
  5348.7  358.27  5419.9  356.81  5443.7  357.52  5455.5  359.48  5509.1  363.34
#Mann= 7 ,-1 , 0
  4271.7     .16       0    4693     .12       0  4801.2     .16       0
  4845.6     .12       0  4922.4     .16       0  5012.5     .07       0
  5018.5     .16       0
Bank Sta=5012.5,5018.5
XS Rating Curve= 0 ,0
Exp/Cntr=0.3,0.1

Type RM Length L Ch R = 1 ,1862    ,0,0,0
BEGIN DESCRIPTION:
UNT0765 IN SAND CR 2.0
END DESCRIPTION:
XS GIS Cut Line= 3
      3566521.99      10466013.5       3566527.2      10466898.9
       3567687.9     10466971.77
#Sta/Elev= 30
  4181.2  396.41  4299.3  381.82  4349.3  376.76  4419.3  371.24  4469.3  368.47
  4529.3  366.48  4609.3  362.63  4649.4   358.6  4669.4  357.97  4699.4  359.28
  4759.4  355.72  4789.3  355.44  4898.6  355.27  5062.5  355.11  5065.2  354.61
  5068.5  355.11  5151.7   356.3  5188.5  355.45  5271.9  355.18  5362.1  356.86
  5562.5  356.65  5682.7  357.81  5800.3  357.75  5946.1  358.22  5993.3  358.77
    6035  357.66  6113.6  358.54  6148.2  360.07  6183.7  362.66  6229.6  361.17
#Mann= 8 ,-1 , 0
  4181.2     .16       0  4789.3     .05       0  4898.6     .16       0
  5062.5     .07       0  5068.5     .16       0  5800.3      .1       0
  5946.1     .16       0    6035      .1       0
Bank Sta=5062.5,5068.5
XS Rating Curve= 0 ,0
Exp/Cntr=0.3,0.1

Chan Stop Cuts=-1
Use User Specified Reach Order=0
Composite Channel Slope=5