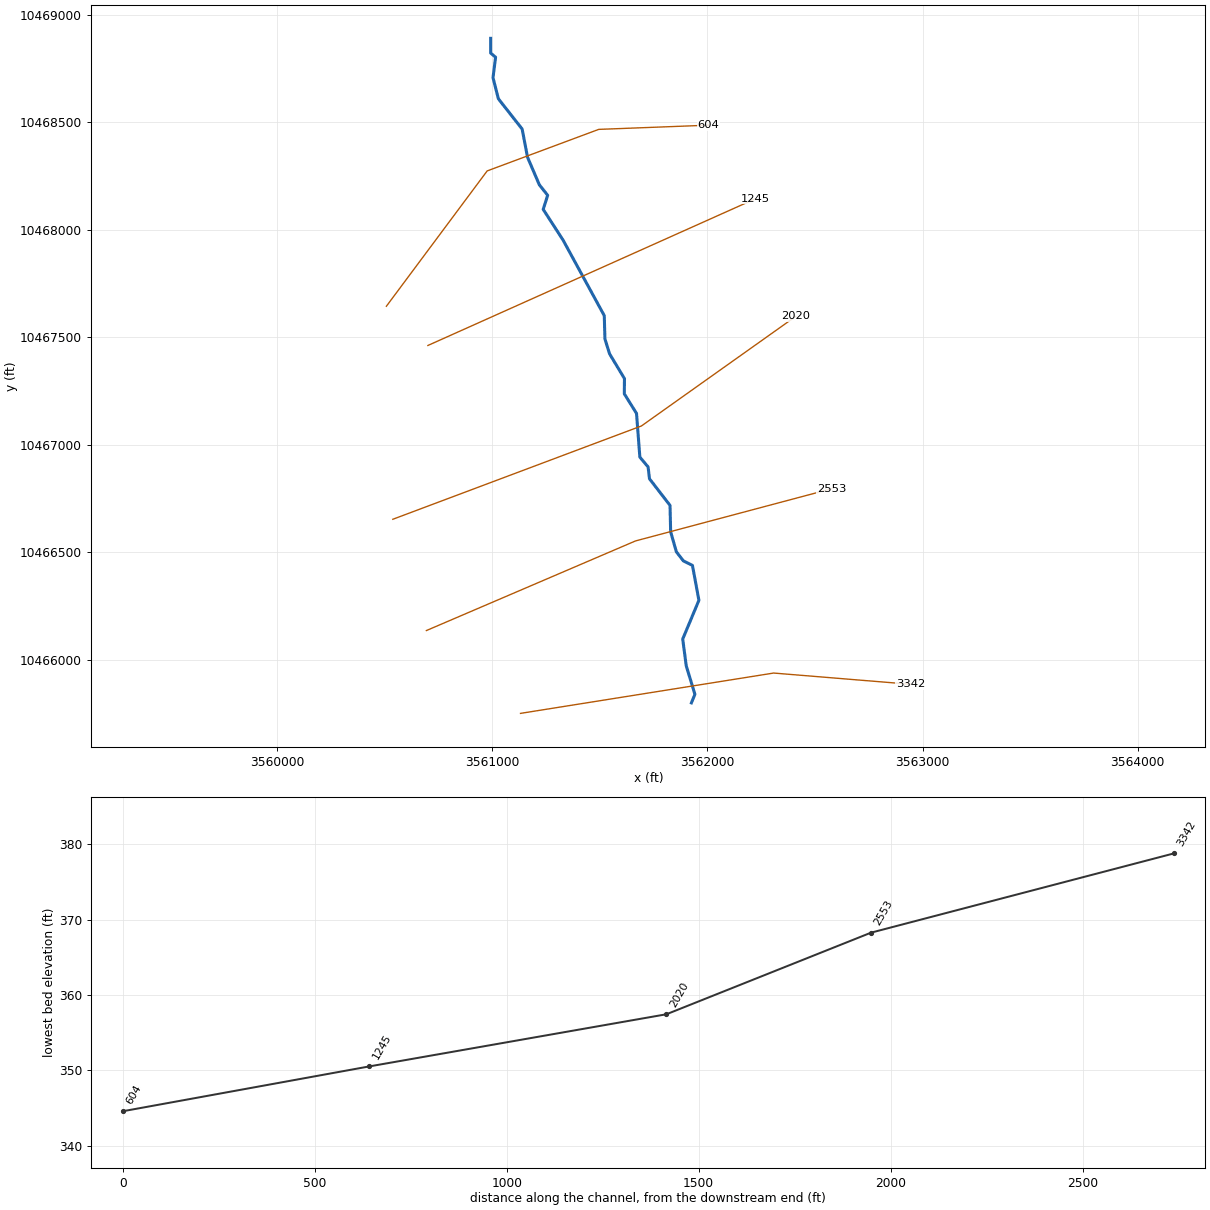
--- UNT0767 IN SAND CR.prj (project) ---

Proj Title=UNT0767 IN SAND CR Base Level Engineering
Current Plan=p01
Default Exp/Contr=0.3,0.1
English Units
Geom File=g01
Flow File=f01
Plan File=p01
BEGIN DESCRIPTION:
UNT0767 IN SAND CR
END DESCRIPTION:

--- UNT0767 IN SAND CR.p01 (plan) ---

Plan Title=Multiple Run
Short Identifier=Multiple
Geom File=g01
Flow File=f01
Subcritical Flow
K Sum by GR= 0
Std Step Tol= 0.01
Critical Tol= 0.01
Num of Std Step Trials= 20
Max Error Tol= 0.3
Flow Tol Ratio= 0.001
Split Flow NTrial= 30
Split Flow Tol= 0.02
Split Flow Ratio= 0.02
Log Output Level= 0
Friction Slope Method= 1
Unsteady Friction Slope Method= 2
Unsteady Bridges Friction Slope Method= 1
Parabolic Critical Depth
Global Vel Dist=  1 , 1 , 1
Global Log Level= 0
CheckData=True
Encroach Param= -1, 0, 0, 0
BEGIN DESCRIPTION:
Multiple Run
END DESCRIPTION:

--- UNT0767 IN SAND CR.f01 (steady flow) ---

Flow Title=Multiple
Number of Profiles=7
Profile Names=10-year,25-year,50-year,1pct_min,100-year,1pct_plu,500-year
River Rch & RM= UNT0767 IN SAND ,Reach-1,3342
     759    1042    1276    1145    1548    2094    2267
Boundary for River Rch & Prof#=UNT0767 IN SAND ,Reach-1,1
Up Type=0
Dn Type=3
Dn Slope=0.005
Boundary for River Rch & Prof#=UNT0767 IN SAND ,Reach-1,2
Up Type=0
Dn Type=3
Dn Slope=0.005
Boundary for River Rch & Prof#=UNT0767 IN SAND ,Reach-1,3
Up Type=0
Dn Type=3
Dn Slope=0.005
Boundary for River Rch & Prof#=UNT0767 IN SAND ,Reach-1,4
Up Type=0
Dn Type=3
Dn Slope=0.005
Boundary for River Rch & Prof#=UNT0767 IN SAND ,Reach-1,5
Up Type=0
Dn Type=3
Dn Slope=0.005
Boundary for River Rch & Prof#=UNT0767 IN SAND ,Reach-1,6
Up Type=0
Dn Type=3
Dn Slope=0.005
Boundary for River Rch & Prof#=UNT0767 IN SAND ,Reach-1,7
Up Type=0
Dn Type=3
Dn Slope=0.005

--- UNT0767 IN SAND CR.g01 (geometry) ---

Geom Title=Existing Conditions

River Reach=UNT0767 IN SAND ,Reach-1
Reach XY= 30
      3561925.36     10465800.26      3561941.64     10465840.24
      3561901.36     10465972.53      3561884.95     10466097.15
      3561960.26     10466277.36      3561930.19     10466439.62
      3561887.95     10466460.67      3561855.41     10466502.84
      3561828.85     10466595.86      3561825.94     10466718.66
      3561730.45     10466842.35      3561723.89     10466897.56
      3561685.67     10466943.18      3561670.18     10467146.18
      3561613.38     10467237.36      3561614.10     10467308.13
      3561545.09     10467422.88      3561523.26     10467492.27
      3561520.17     10467600.93      3561329.57     10467950.59
      3561236.23     10468095.18      3561257.10     10468160.47
      3561218.25     10468209.35      3561163.44     10468337.31
      3561138.25     10468468.69      3561027.83     10468609.31
      3561002.83     10468707.23      3561014.81     10468802.54
      3560991.89     10468821.81      3560991.83     10468890.35

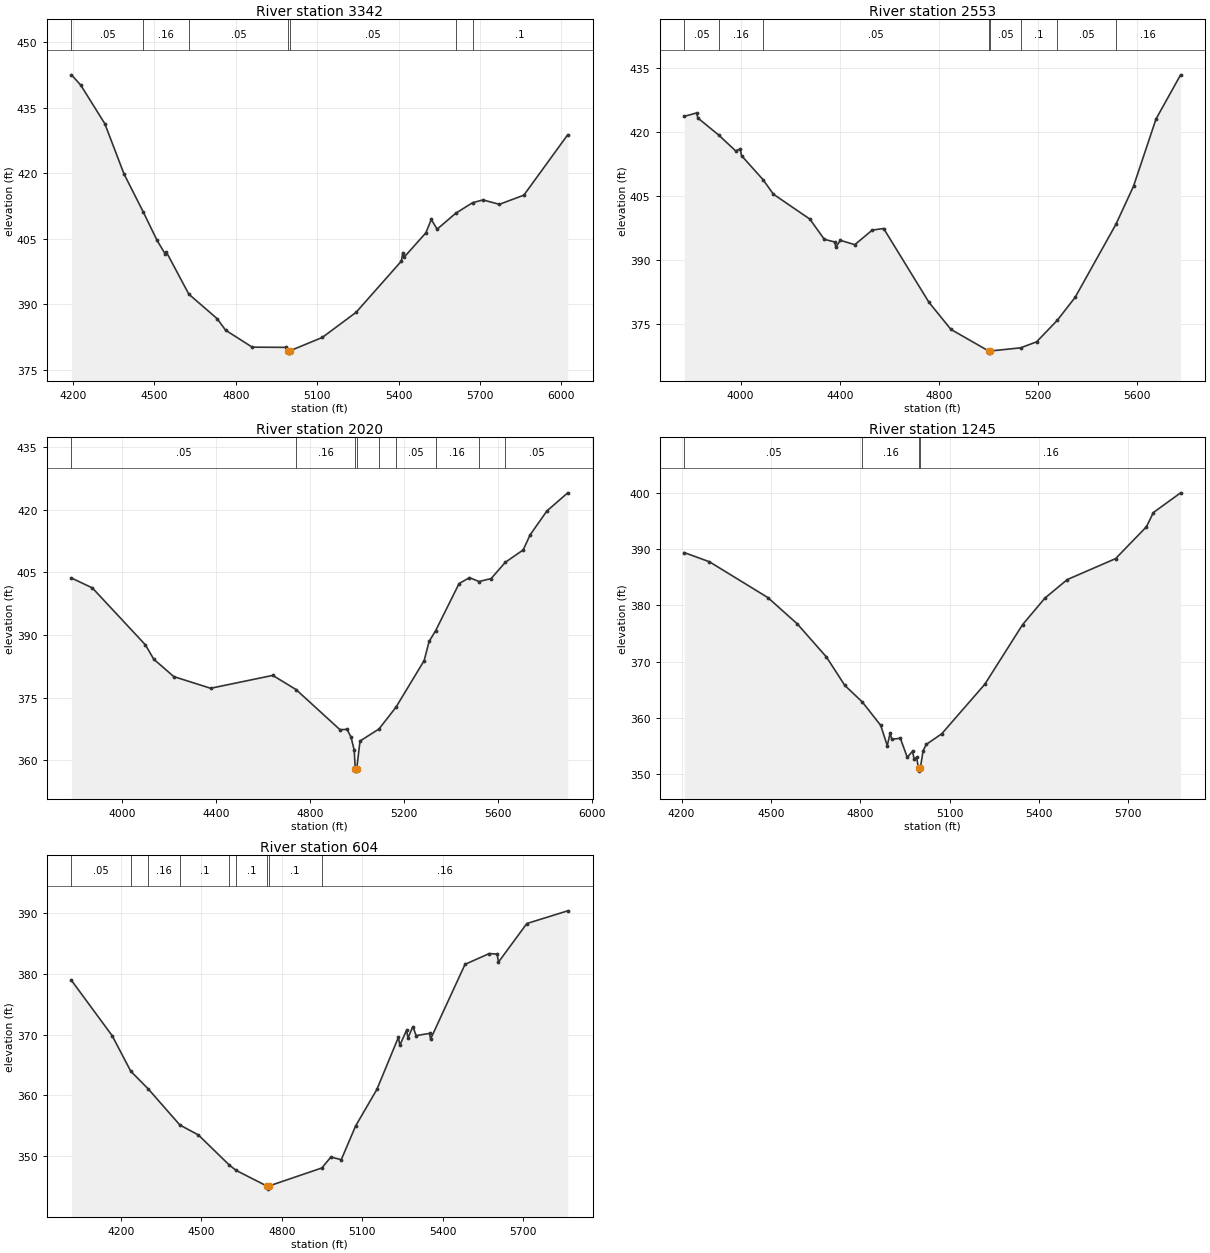
Type RM Length L Ch R = 1,3342,789,789,789
BEGIN DESCRIPTION:
UNT0767 IN SAND CR 7.0
END DESCRIPTION:
XS GIS Cut Line= 3
      3561130.85     10465751.59      3562307.92     10465939.09
      3562943.38     10465887.00
#Sta/Elev= 30
  4194.1  442.56  4228.5  440.18  4316.9  431.38  4387.8  419.85  4458.5  411.17
  4509.3  404.67  4539.3  401.54  4544.4  401.91  4626.6  392.32  4730.9  386.71
  4762.4  384.05  4860.3  380.17  4984.6  380.12  4992.3  379.30  4995.1  378.80
  4998.3  379.30  5119.0  382.40  5243.4  388.15  5410.3  399.88  5415.6  401.82
  5420.6  400.79  5500.6  406.36  5520.6  409.42  5542.1  407.20  5610.2  410.82
  5673.0  413.27  5711.3  413.90  5771.5  412.89  5861.8  414.99  6023.6  428.83
#Mann=7,-1,0
  4194.1    0.05       0  4458.5    0.16       0  4626.6    0.05       0
  4992.3    0.03       0  4998.3    0.05       0  5610.2    0.16       0
  5673.0     0.1       0
Bank Sta=4992.3,4998.3
Exp/Cntr=0.3,0.1

Type RM Length L Ch R = 1,2553,533,533,533
BEGIN DESCRIPTION:
UNT0767 IN SAND CR 6.0
END DESCRIPTION:
XS GIS Cut Line= 3
      3560693.14     10466136.70      3561665.39     10466553.37
      3562577.84     10466796.23
#Sta/Elev= 30
  3773.1  423.78  3822.3  424.57  3827.8  423.38  3911.8  419.39  3980.1  415.68
  3998.2  416.14  4003.7  414.58  4090.8  408.92  4132.4  405.53  4279.3  399.70
  4337.7  394.96  4379.0  394.34  4384.5  393.17  4402.6  394.72  4460.6  393.70
  4531.3  397.12  4577.1  397.49  4759.8  380.20  4848.5  373.84  5000.8  368.78
  5003.6  368.28  5006.8  368.78  5129.6  369.52  5194.2  370.93  5277.2  375.95
  5349.5  381.35  5514.0  398.46  5585.2  407.41  5676.0  423.17  5775.1  433.51
#Mann=8,-1,0
  3773.1    0.05       0  3911.8    0.16       0  4090.8    0.05       0
  5000.8    0.03       0  5006.8    0.05       0  5129.6     0.1       0
  5277.2    0.05       0  5514.0    0.16       0
Bank Sta=5000.8,5006.8
Exp/Cntr=0.3,0.1

Type RM Length L Ch R = 1,2020,775,775,775
BEGIN DESCRIPTION:
UNT0767 IN SAND CR 5.0
END DESCRIPTION:
XS GIS Cut Line= 3
      3560536.96     10466654.08      3561693.16     10467088.10
      3562410.58     10467597.57
#Sta/Elev= 30
  3783.3  403.62  3872.4  401.25  4098.4  387.64  4134.0  384.21  4219.4  380.05
  4376.3  377.26  4641.1  380.34  4740.2  376.96  4927.6  367.36  4957.8  367.44
  4974.4  365.61  4988.1  362.54  4992.8  357.95  4995.5  357.45  4998.8  357.95
  5013.0  364.65  5093.9  367.53  5166.2  372.73  5286.4  383.89  5307.3  388.45
  5335.2  391.02  5435.2  402.30  5479.5  403.71  5520.0  402.78  5571.7  403.49
  5632.2  407.38  5708.3  410.33  5737.8  413.93  5809.2  419.64  5898.2  423.99
#Mann=9,-1,0
  3783.3    0.05       0  4740.2    0.16       0  4992.8    0.07       0
  4998.8    0.16       0  5093.9     0.1       0  5166.2    0.05       0
  5335.2    0.16       0  5520.0     0.1       0  5632.2    0.05       0
Bank Sta=4992.8,4998.8
Exp/Cntr=0.3,0.1

Type RM Length L Ch R = 1,1245,641,641,641
BEGIN DESCRIPTION:
UNT0767 IN SAND CR 3.0
END DESCRIPTION:
XS GIS Cut Line= 2
      3560700.15     10467462.24      3562221.40     10468143.66
#Sta/Elev= 30
  4209.2  389.41  4293.4  387.78  4489.9  381.40  4588.1  376.75  4686.4  370.84
  4748.3  365.77  4807.1  362.82  4868.8  358.66  4890.7  355.06  4900.5  357.28
  4906.0  356.19  4934.7  356.37  4957.9  352.98  4975.6  354.06  4981.1  352.64
  4989.3  352.95  4995.8  351.02  4998.5  350.52  5001.8  351.02  5011.2  354.17
  5022.0  355.28  5073.8  357.17  5218.4  365.98  5345.3  376.59  5420.4  381.32
  5495.4  384.61  5657.7  388.34  5761.4  394.01  5784.6  396.54  5876.1  400.05
#Mann=4,-1,0
  4209.2    0.05       0  4807.1    0.16       0  4995.8    0.07       0
  5001.8    0.16       0
Bank Sta=4995.8,5001.8
Exp/Cntr=0.3,0.1

Type RM Length L Ch R = 1,604,0,0,0
BEGIN DESCRIPTION:
UNT0767 IN SAND CR 1.0
END DESCRIPTION:
XS GIS Cut Line= 4
      3560506.96     10467644.52      3560975.72     10468273.86
      3561494.38     10468467.00      3562004.32     10468486.53
#Sta/Elev= 30
  4016.8  378.91  4168.4  369.81  4237.8  363.96  4303.6  361.02  4420.5  355.13
  4489.5  353.49  4605.0  348.53  4630.5  347.65  4745.1  345.08  4747.9  344.58
  4751.1  345.08  4949.4  348.06  4982.9  349.85  5021.8  349.43  5075.1  354.96
  5154.3  360.97  5234.6  369.55  5239.9  368.24  5264.9  370.71  5270.3  369.45
  5288.5  371.31  5300.6  369.83  5350.6  370.19  5354.5  369.26  5482.8  381.55
  5572.9  383.32  5602.4  383.23  5607.4  381.92  5713.0  388.26  5865.3  390.35
#Mann=9,-1,0
  4016.8    0.05       0  4237.8     0.1       0  4303.6    0.16       0
  4420.5     0.1       0  4605.0    0.16       0  4630.5     0.1       0
  4745.1    0.07       0  4751.1     0.1       0  4949.4    0.16       0
Bank Sta=4745.1,4751.1
Exp/Cntr=0.3,0.1

Chan Stop Cuts=-1