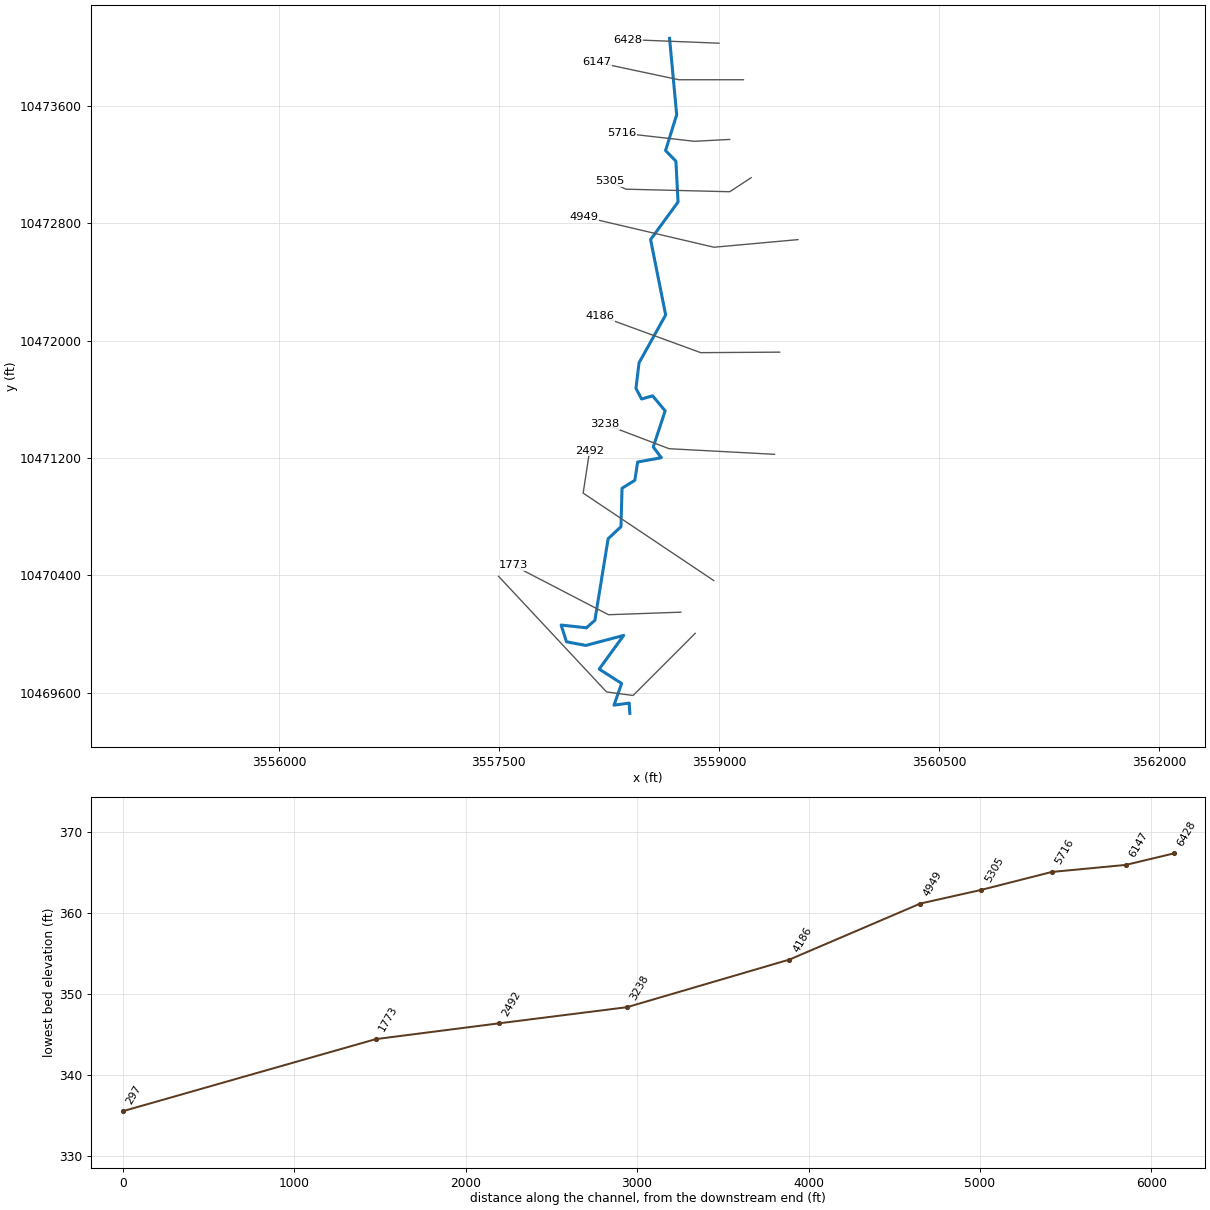
--- UNT0768 IN SAND CR.prj (project) ---

Proj Title=UNT0768 IN SAND CR Base Level Engineering
Current Plan=p01
Default Exp/Contr=0.3,0.1
English Units
Geom File=g01
Flow File=f01
Plan File=p01
BEGIN DESCRIPTION:
UNT0768 IN SAND CR
END DESCRIPTION:

--- UNT0768 IN SAND CR.p01 (plan) ---

Plan Title=Multiple Run
Short Identifier=Multiple
Geom File=g01
Flow File=f01
Subcritical Flow
K Sum by GR= 0
Std Step Tol= 0.01
Critical Tol= 0.01
Num of Std Step Trials= 20
Max Error Tol= 0.3
Flow Tol Ratio= 0.001
Split Flow NTrial= 30
Split Flow Tol= 0.02
Split Flow Ratio= 0.02
Log Output Level= 0
Friction Slope Method= 1
Unsteady Friction Slope Method= 2
Unsteady Bridges Friction Slope Method= 1
Parabolic Critical Depth
Global Vel Dist=  1 , 1 , 1
Global Log Level= 0
CheckData=True
Encroach Param= -1, 0, 0, 0
BEGIN DESCRIPTION:
Multiple Run
END DESCRIPTION:

--- UNT0768 IN SAND CR.f01 (steady flow) ---

Flow Title=Multiple
Number of Profiles=7
Profile Names=10-year,25-year,50-year,1pct_min,100-year,1pct_plu,500-year
River Rch & RM= UNT0768 IN SAND ,Reach-1,6428
    1234    1736    2162    1965    2657    3594    4004
Boundary for River Rch & Prof#=UNT0768 IN SAND ,Reach-1,1
Up Type=0
Dn Type=3
Dn Slope=0.005
Boundary for River Rch & Prof#=UNT0768 IN SAND ,Reach-1,2
Up Type=0
Dn Type=3
Dn Slope=0.005
Boundary for River Rch & Prof#=UNT0768 IN SAND ,Reach-1,3
Up Type=0
Dn Type=3
Dn Slope=0.005
Boundary for River Rch & Prof#=UNT0768 IN SAND ,Reach-1,4
Up Type=0
Dn Type=3
Dn Slope=0.005
Boundary for River Rch & Prof#=UNT0768 IN SAND ,Reach-1,5
Up Type=0
Dn Type=3
Dn Slope=0.005
Boundary for River Rch & Prof#=UNT0768 IN SAND ,Reach-1,6
Up Type=0
Dn Type=3
Dn Slope=0.005
Boundary for River Rch & Prof#=UNT0768 IN SAND ,Reach-1,7
Up Type=0
Dn Type=3
Dn Slope=0.005

--- UNT0768 IN SAND CR.g01 (geometry) ---

Geom Title=Existing Conditions

River Reach=UNT0768 IN SAND ,Reach-1
Reach XY= 30
      3558663.66     10474062.49      3558712.22     10473541.75
      3558636.50     10473297.25      3558706.94     10473224.97
      3558721.58     10472946.42      3558534.36     10472690.43
      3558637.14     10472176.65      3558455.66     10471850.09
      3558434.52     10471675.99      3558472.76     10471603.30
      3558548.33     10471624.99      3558633.54     10471522.64
      3558552.62     10471276.05      3558607.23     10471203.32
      3558446.03     10471173.63      3558426.90     10471048.94
      3558339.63     10470994.76      3558332.35     10470732.67
      3558244.80     10470650.50      3558154.59     10470095.08
      3558097.27     10470043.34      3557924.29     10470062.12
      3557960.98     10469947.95      3558092.62     10469923.02
      3558350.75     10469991.48      3558183.93     10469761.90
      3558336.80     10469663.76      3558284.91     10469515.96
      3558388.21     10469529.85      3558392.81     10469459.83

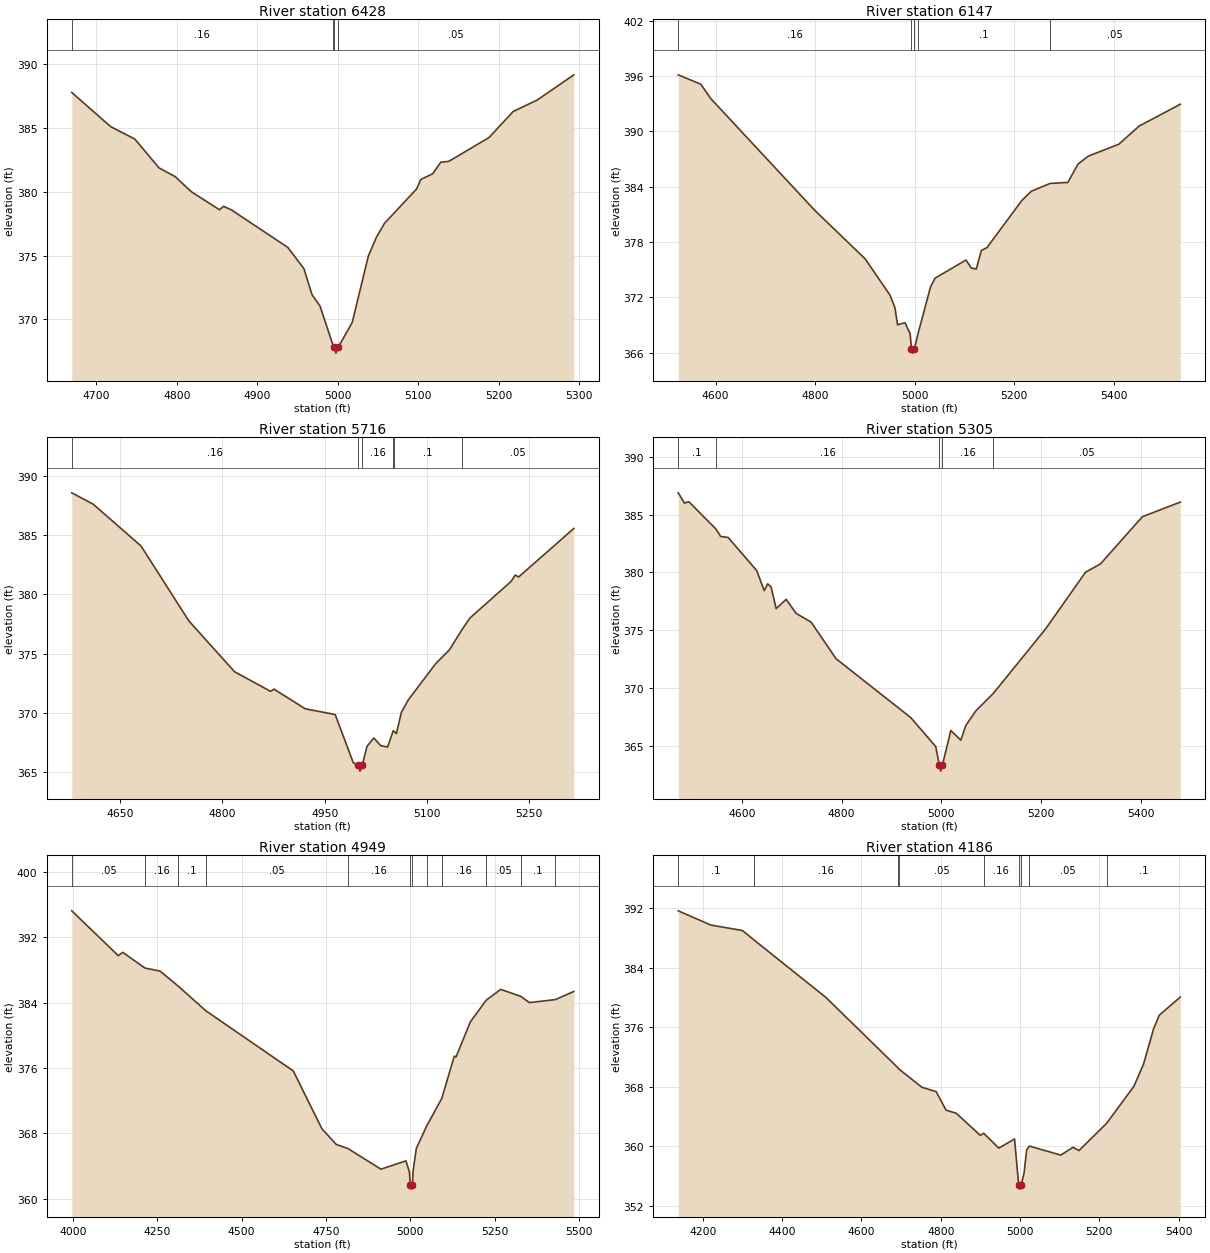
Type RM Length L Ch R = 1,6428,281,281,281
BEGIN DESCRIPTION:
UNT0768 IN SAND CR 11.1
END DESCRIPTION:
XS GIS Cut Line= 2
      3559000.48     10474029.30      3558376.78     10474054.24
#Sta/Elev= 30
  4669.3  387.78  4717.7  385.10  4747.7  384.13  4777.8  381.87  4797.8  381.19
  4817.8  380.01  4853.0  378.59  4858.0  378.86  4867.8  378.58  4937.9  375.64
  4957.9  373.98  4967.9  371.95  4977.9  371.05  4993.8  368.04  4994.9  367.86
  4997.7  367.36  5000.9  367.86  5018.0  369.77  5038.0  374.96  5048.0  376.43
  5058.0  377.52  5098.0  380.22  5103.2  380.96  5118.0  381.41  5128.0  382.31
  5138.0  382.38  5188.1  384.25  5218.1  386.29  5248.1  387.19  5293.5  389.16
#Mann=4,-1,0
  4669.3    0.16       0  4993.8    0.05       0  4994.9    0.03       0
  5000.9    0.05       0
Bank Sta=4994.9,5000.9
Exp/Cntr=0.3,0.1

Type RM Length L Ch R = 1,6147,431,431,431
BEGIN DESCRIPTION:
UNT0768 IN SAND CR 11.0
END DESCRIPTION:
XS GIS Cut Line= 3
      3559167.53     10473780.18      3558726.56     10473780.18
      3558171.04     10473898.23
#Sta/Elev= 30
  4525.1  396.15  4570.5  395.13  4590.5  393.57  4800.5  381.38  4900.5  376.19
  4950.5  372.25  4960.5  370.89  4965.8  369.02  4980.8  369.24  4991.1  368.04
  4993.7  366.44  4996.4  365.94  4999.7  366.44  5007.3  368.12  5032.0  373.12
  5041.2  374.08  5103.5  376.05  5113.8  375.18  5124.0  375.07  5134.2  377.08
  5145.5  377.40  5216.0  382.54  5234.5  383.51  5272.3  384.36  5308.0  384.47
  5328.4  386.46  5348.9  387.32  5410.2  388.61  5451.1  390.58  5534.0  392.96
#Mann=5,-1,0
  4525.1    0.16       0  4993.7    0.07       0  4999.7    0.16       0
  5007.3     0.1       0  5272.3    0.05       0
Bank Sta=4993.7,4999.7
Exp/Cntr=0.3,0.1

Type RM Length L Ch R = 1,5716,411,411,411
BEGIN DESCRIPTION:
UNT0768 IN SAND CR 10.0
END DESCRIPTION:
XS GIS Cut Line= 3
      3559073.42     10473373.17      3558832.92     10473360.43
      3558340.81     10473416.21
#Sta/Elev= 30
  4579.2  388.59  4610.6  387.63  4680.7  384.10  4750.8  377.77  4817.9  373.47
  4870.7  371.81  4875.7  372.00  4921.5  370.34  4965.4  369.85  4991.9  365.78
  4999.0  365.57  5001.8  365.07  5005.0  365.57  5012.1  367.17  5022.1  367.87
  5032.2  367.22  5042.3  367.11  5050.6  368.49  5051.2  368.46  5055.1  368.24
  5062.4  370.03  5072.5  371.08  5112.7  374.15  5132.8  375.31  5151.1  377.01
  5163.0  378.01  5223.4  381.11  5229.4  381.64  5234.4  381.48  5315.3  385.58
#Mann=6,-1,0
  4579.2    0.16       0  4999.0    0.07       0  5005.0    0.16       0
  5050.6    0.05       0  5051.2     0.1       0  5151.1    0.05       0
Bank Sta=4999,5005
Exp/Cntr=0.3,0.1

Type RM Length L Ch R = 1,5305,356,356,356
BEGIN DESCRIPTION:
UNT0768 IN SAND CR 9.0
END DESCRIPTION:
XS GIS Cut Line= 4
      3559219.76     10473112.21      3559074.07     10473016.57
      3558365.73     10473033.93      3558254.51     10473087.77
#Sta/Elev= 30
  4472.6  386.87  4485.2  385.98  4493.7  386.11  4548.1  383.75  4557.6  383.11
  4572.7  383.02  4629.9  380.16  4645.0  378.43  4651.9  379.02  4658.8  378.74
  4668.9  376.88  4688.9  377.68  4708.9  376.47  4738.9  375.72  4788.9  372.56
  4938.9  367.47  4988.9  364.97  4996.0  363.36  4998.7  362.86  5002.0  363.36
  5019.0  366.36  5039.0  365.53  5049.0  366.79  5069.0  368.05  5103.7  369.54
  5209.0  375.13  5289.0  380.02  5319.0  380.74  5403.0  384.81  5479.0  386.07
#Mann=5,-1,0
  4472.6     0.1       0  4548.1    0.16       0  4996.0    0.07       0
  5002.0    0.16       0  5103.7    0.05       0
Bank Sta=4996,5002
Exp/Cntr=0.3,0.1

Type RM Length L Ch R = 1,4949,763,763,763
BEGIN DESCRIPTION:
UNT0768 IN SAND CR 9.1
END DESCRIPTION:
XS GIS Cut Line= 3
      3559539.32     10472690.18      3558966.43     10472638.10
      3558077.57     10472846.42
#Sta/Elev= 30
  3996.4  395.22  4134.2  389.74  4147.6  390.14  4213.2  388.22  4258.0  387.85
  4312.1  386.00  4394.5  382.97  4653.0  375.63  4737.9  368.55  4780.4  366.64
  4815.1  366.13  4912.9  363.61  4986.9  364.63  4997.2  363.27  4999.9  361.67
  5002.7  361.17  5005.9  361.67  5008.1  363.36  5017.7  366.15  5048.6  368.91
  5093.0  372.25  5130.3  377.44  5135.4  377.34  5177.9  381.64  5225.0  384.29
  5267.9  385.61  5327.5  384.75  5352.8  383.99  5430.0  384.36  5484.6  385.36
#Mann=12,-1,0
  3996.4    0.05       0  4213.2    0.16       0  4312.1     0.1       0
  4394.5    0.05       0  4815.1    0.16       0  4999.9    0.07       0
  5005.9    0.16       0  5048.6     0.1       0  5093.0    0.16       0
  5225.0    0.05       0  5327.5     0.1       0  5430.0    0.05       0
Bank Sta=4999.9,5005.9
Exp/Cntr=0.3,0.1

Type RM Length L Ch R = 1,4186,948,948,948
BEGIN DESCRIPTION:
UNT0768 IN SAND CR 7.0
END DESCRIPTION:
XS GIS Cut Line= 3
      3559414.30     10471922.82      3558876.15     10471919.35
      3558192.16     10472169.33
#Sta/Elev= 30
  4137.8  391.64  4220.0  389.73  4300.0  388.99  4329.1  387.72  4510.0  380.02
  4691.2  370.60  4694.7  370.38  4752.5  367.94  4788.3  367.36  4813.5  364.86
  4838.8  364.46  4899.8  361.48  4908.3  361.76  4946.4  359.77  4986.1  361.00
  4996.7  354.76  4999.4  354.26  5002.7  354.76  5010.3  356.49  5016.6  359.52
  5023.5  360.04  5102.9  358.83  5133.5  359.88  5148.7  359.44  5218.8  363.13
  5287.1  368.07  5311.4  371.04  5336.6  375.76  5351.0  377.61  5404.2  380.06
#Mann=9,-1,0
  4137.8     0.1       0  4329.1    0.16       0  4691.2     0.1       0
  4694.7    0.05       0  4908.3    0.16       0  4996.7    0.07       0
  5002.7    0.16       0  5023.5    0.05       0  5218.8     0.1       0
Bank Sta=4996.7,5002.7
Exp/Cntr=0.3,0.1

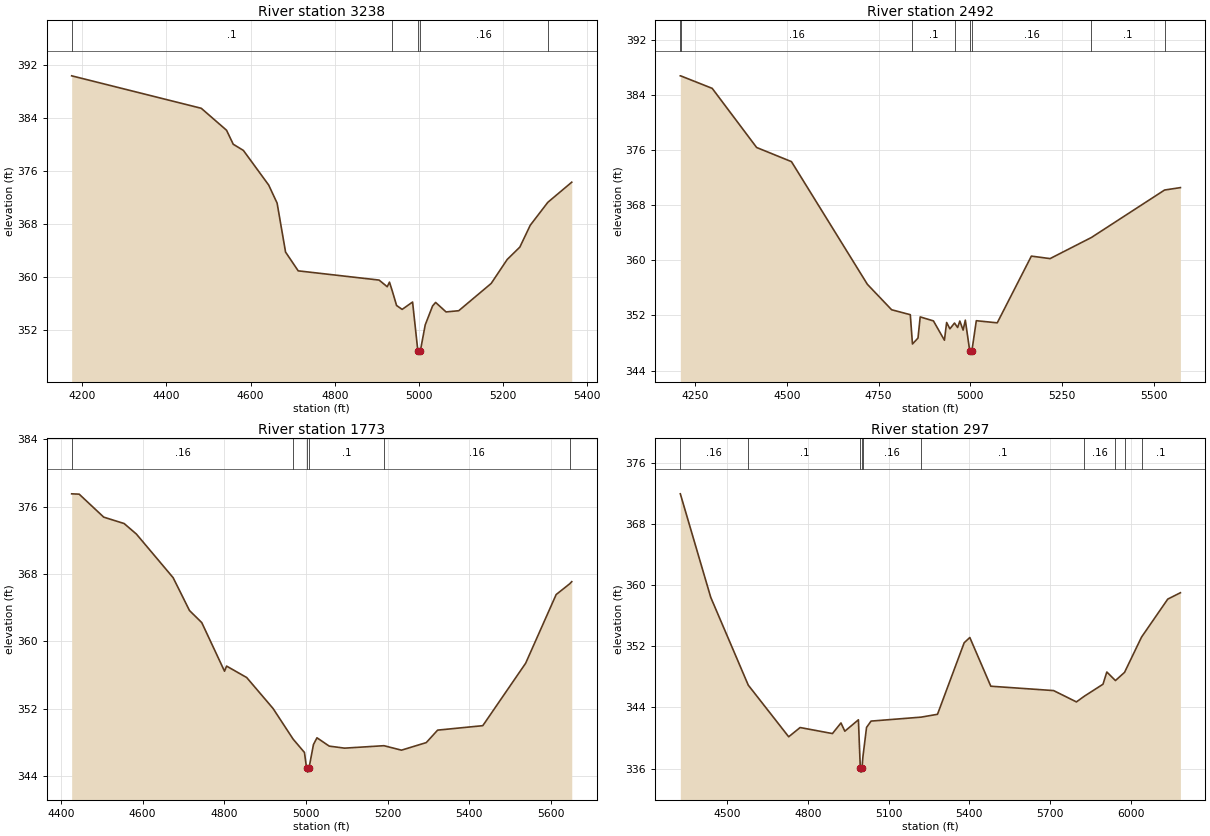
Type RM Length L Ch R = 1,3238,746,746,746
BEGIN DESCRIPTION:
UNT0768 IN SAND CR 5.0
END DESCRIPTION:
XS GIS Cut Line= 3
      3559379.46     10471226.23      3558660.70     10471264.43
      3558223.24     10471431.08
#Sta/Elev= 30
  4175.0  390.32  4482.8  385.43  4542.9  382.12  4558.8  380.01  4582.9  379.08
  4643.0  373.86  4663.0  371.14  4683.1  363.76  4713.1  360.93  4905.2  359.54
  4924.6  358.54  4929.9  359.23  4936.3  357.96  4946.8  355.71  4960.0  355.12
  4984.8  356.23  4997.3  348.88  5000.0  348.38  5003.3  348.88  5014.8  352.78
  5032.4  355.65  5039.6  356.17  5064.3  354.74  5094.4  354.92  5171.5  359.03
  5209.5  362.64  5239.6  364.51  5264.3  367.80  5306.1  371.26  5362.9  374.29
#Mann=5,-1,0
  4175.0     0.1       0  4936.3    0.16       0  4997.3    0.07       0
  5003.3    0.16       0  5306.1     0.1       0
Bank Sta=4997.3,5003.3
Exp/Cntr=0.3,0.1

Type RM Length L Ch R = 1,2492,719,719,719
BEGIN DESCRIPTION:
UNT0768 IN SAND CR 3.0
END DESCRIPTION:
XS GIS Cut Line= 3
      3558965.13     10470365.35      3558074.50     10470961.71
      3558118.78     10471250.79
#Sta/Elev= 30
  4208.9  386.77  4209.6  386.77  4295.9  384.95  4417.1  376.37  4512.1  374.32
  4719.2  356.52  4785.3  352.83  4836.3  352.11  4842.2  347.86  4857.3  348.72
  4863.3  351.79  4899.4  351.21  4929.4  348.41  4935.4  350.98  4944.4  350.06
  4956.9  350.90  4965.4  350.25  4971.4  351.19  4980.4  349.88  4986.4  351.32
  4998.4  346.89  5001.2  346.39  5004.4  346.89  5016.4  351.24  5073.5  350.93
  5166.6  360.61  5217.6  360.25  5330.3  363.31  5530.0  370.20  5573.2  370.55
#Mann=8,-1,0
  4208.9     0.1       0  4209.6    0.16       0  4842.2     0.1       0
  4956.9    0.16       0  4998.4    0.07       0  5004.4    0.16       0
  5330.3     0.1       0  5530.0    0.16       0
Bank Sta=4998.4,5004.4
Exp/Cntr=0.3,0.1

Type RM Length L Ch R = 1,1773,1476,1476,1476
BEGIN DESCRIPTION:
UNT0768 IN SAND CR 1.0
END DESCRIPTION:
XS GIS Cut Line= 3
      3558740.52     10470149.84      3558247.50     10470132.48
      3557598.19     10470469.29
#Sta/Elev= 30
  4426.4  377.51  4444.8  377.47  4504.9  374.74  4554.9  373.98  4584.9  372.73
  4675.0  367.54  4715.0  363.64  4745.0  362.21  4800.8  356.43  4805.8  357.04
  4855.1  355.68  4919.7  352.00  4968.8  348.36  4996.5  346.78  5001.7  344.94
  5004.4  344.44  5007.7  344.94  5018.6  347.72  5027.2  348.52  5057.2  347.53
  5094.8  347.29  5191.2  347.58  5234.2  347.05  5294.9  347.95  5322.7  349.43
  5433.3  349.96  5538.3  357.38  5613.0  365.54  5646.2  366.82  5651.2  367.07
#Mann=6,-1,0
  4426.4    0.16       0  4968.8     0.1       0  5001.7    0.07       0
  5007.7     0.1       0  5191.2    0.16       0  5646.2     0.1       0
Bank Sta=5001.7,5007.7
Exp/Cntr=0.3,0.1

Type RM Length L Ch R = 1,297,0,0,0
BEGIN DESCRIPTION:
UNT0768 IN SAND CR 1.1
END DESCRIPTION:
XS GIS Cut Line= 4
      3558838.34     10470005.38      3558414.69     10469581.74
      3558234.14     10469606.04      3557498.02     10470394.25
#Sta/Elev= 30
  4325.7  371.92  4438.8  358.39  4578.4  346.91  4728.7  340.16  4771.2  341.37
  4891.4  340.58  4923.1  341.97  4937.5  340.89  4988.0  342.38  4995.1  336.04
  4997.8  335.54  5001.1  336.04  5005.0  337.61  5018.2  341.38  5035.0  342.21
  5221.6  342.73  5282.1  343.10  5381.3  352.45  5402.3  353.14  5480.4  346.77
  5713.9  346.20  5798.8  344.72  5828.8  345.48  5897.6  347.03  5911.8  348.63
  5943.9  347.51  5977.7  348.58  6040.9  353.19  6138.5  358.16  6185.5  358.99
#Mann=10,-1,0
  4325.7    0.16       0  4578.4     0.1       0  4995.1    0.07       0
  5001.1     0.1       0  5005.0    0.16       0  5221.6     0.1       0
  5828.8    0.16       0  5943.9     0.1       0  5977.7    0.16       0
  6040.9     0.1       0
Bank Sta=4995.1,5001.1
Exp/Cntr=0.3,0.1

Chan Stop Cuts=-1