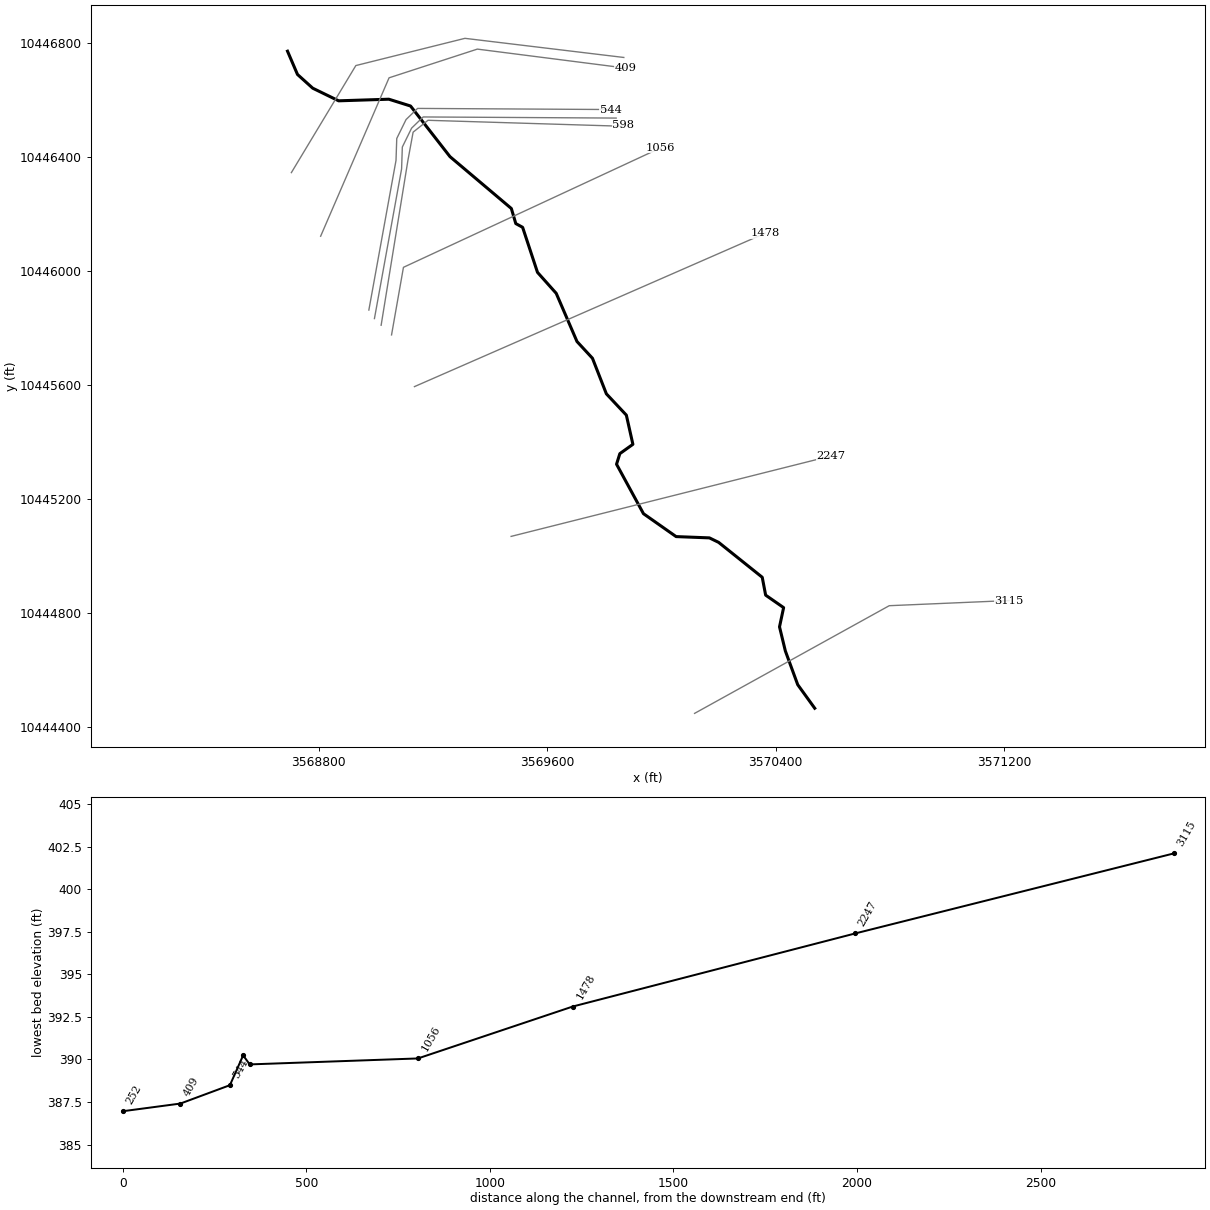
--- UNT0778 IN SAND CR.prj (project) ---

Proj Title=UNT0778 IN SAND CR Base Level Engineering
Current Plan=p01
Default Exp/Contr=0.3,0.1
English Units
Geom File=g01
Flow File=f01
Plan File=p01
BEGIN DESCRIPTION:
UNT0778 IN SAND CR
END DESCRIPTION:

--- UNT0778 IN SAND CR.p01 (plan) ---

Plan Title=Multiple Run
Short Identifier=Multiple
Geom File=g01
Flow File=f01
Subcritical Flow
K Sum by GR= 0
Std Step Tol= 0.01
Critical Tol= 0.01
Num of Std Step Trials= 20
Max Error Tol= 0.3
Flow Tol Ratio= 0.001
Split Flow NTrial= 30
Split Flow Tol= 0.02
Split Flow Ratio= 0.02
Log Output Level= 0
Friction Slope Method= 1
Unsteady Friction Slope Method= 2
Unsteady Bridges Friction Slope Method= 1
Parabolic Critical Depth
Global Vel Dist=  1 , 1 , 1
Global Log Level= 0
CheckData=True
Encroach Param= -1, 0, 0, 0
BEGIN DESCRIPTION:
Multiple Run
END DESCRIPTION:

--- UNT0778 IN SAND CR.f01 (steady flow) ---

Flow Title=Multiple
Number of Profiles=7
Profile Names=10-year,25-year,50-year,1pct_min,100-year,1pct_plu,500-year
River Rch & RM= UNT0778 IN SAND ,Reach-1,3115
     620     825     989     866    1171    1583    1636
Boundary for River Rch & Prof#=UNT0778 IN SAND ,Reach-1,1
Up Type=0
Dn Type=3
Dn Slope=0.005
Boundary for River Rch & Prof#=UNT0778 IN SAND ,Reach-1,2
Up Type=0
Dn Type=3
Dn Slope=0.005
Boundary for River Rch & Prof#=UNT0778 IN SAND ,Reach-1,3
Up Type=0
Dn Type=3
Dn Slope=0.005
Boundary for River Rch & Prof#=UNT0778 IN SAND ,Reach-1,4
Up Type=0
Dn Type=3
Dn Slope=0.005
Boundary for River Rch & Prof#=UNT0778 IN SAND ,Reach-1,5
Up Type=0
Dn Type=3
Dn Slope=0.005
Boundary for River Rch & Prof#=UNT0778 IN SAND ,Reach-1,6
Up Type=0
Dn Type=3
Dn Slope=0.005
Boundary for River Rch & Prof#=UNT0778 IN SAND ,Reach-1,7
Up Type=0
Dn Type=3
Dn Slope=0.005

--- UNT0778 IN SAND CR.g01 (geometry) ---

Geom Title=Existing Conditions

River Reach=UNT0778 IN SAND ,Reach-1
Reach XY= 30
      3570537.11     10444466.64      3570477.58     10444549.20
      3570434.26     10444667.56      3570413.83     10444752.06
      3570428.21     10444819.49      3570365.27     10444863.28
      3570353.34     10444925.94      3570200.76     10445048.31
      3570168.41     10445064.09      3570051.77     10445068.61
      3569937.53     10445148.95      3569843.30     10445322.39
      3569854.82     10445359.50      3569900.51     10445392.17
      3569877.62     10445494.54      3569807.69     10445569.21
      3569758.99     10445693.96      3569704.80     10445752.69
      3569632.11     10445921.64      3569566.53     10445995.26
      3569514.45     10446153.24      3569490.57     10446166.27
      3569474.95     10446219.22      3569260.11     10446401.07
      3569122.09     10446578.59      3569046.13     10446602.46
      3568870.35     10446596.82      3568779.64     10446641.09
      3568726.25     10446689.27      3568691.34     10446770.88

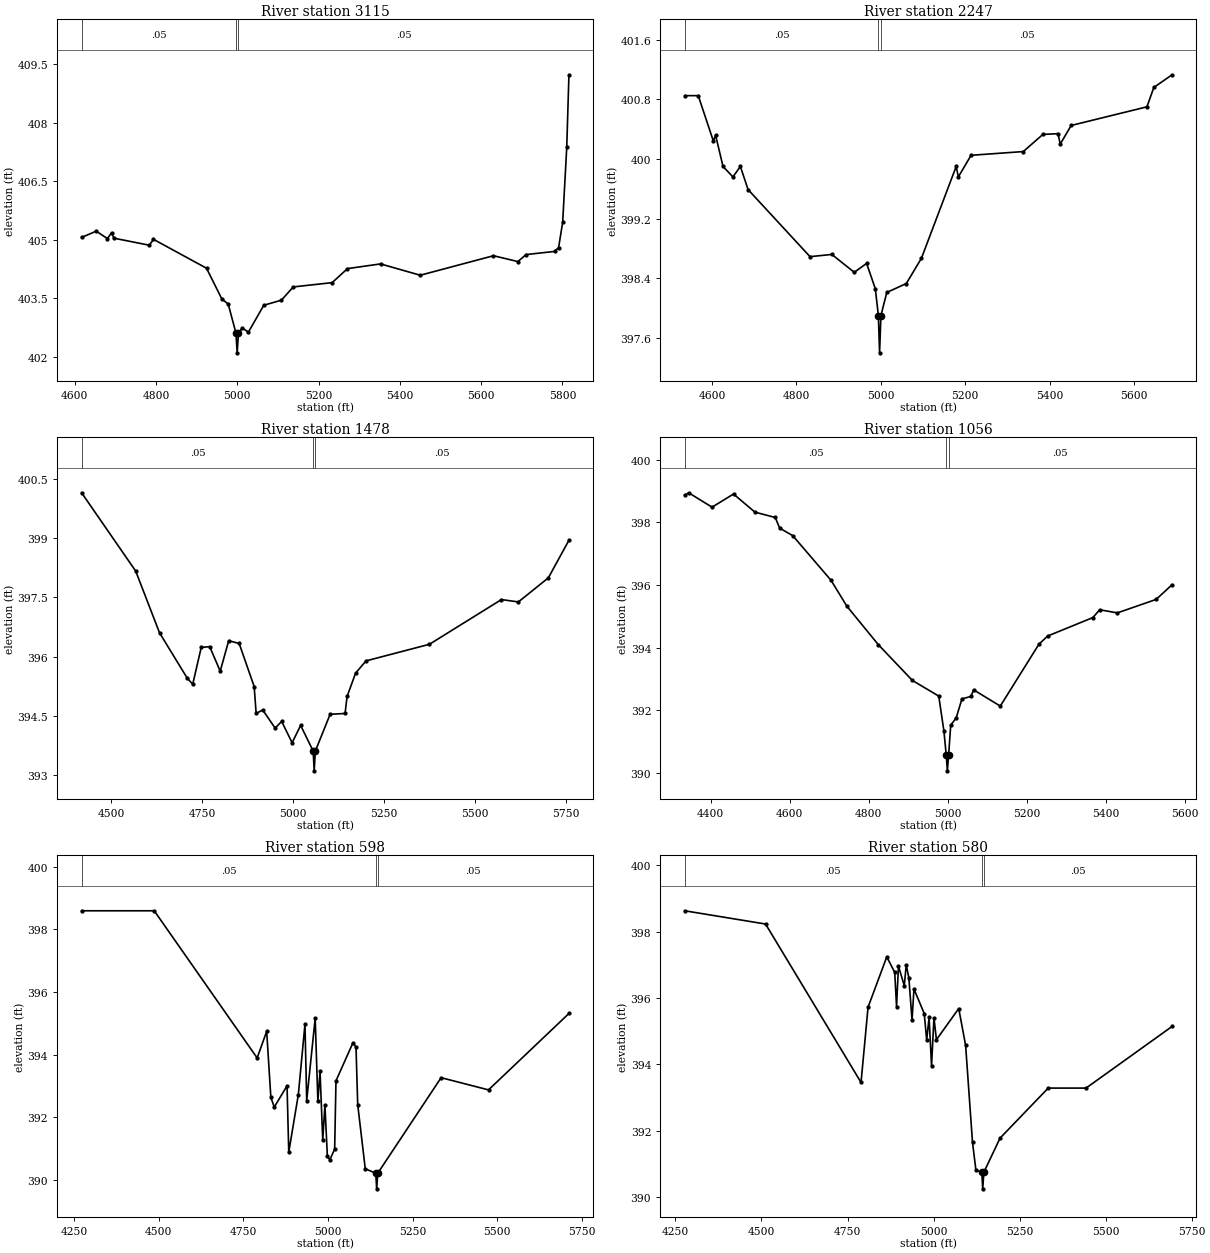
Type RM Length L Ch R = 1,3115,868,868,868
BEGIN DESCRIPTION:
UNT0778 IN SAND CR 3.1
END DESCRIPTION:
XS GIS Cut Line= 3
      3570116.54     10444448.64      3570797.98     10444826.25
      3571217.52     10444844.31
#Sta/Elev= 30
  4616.9  405.06  4652.9  405.22  4680.4  405.03  4690.7  405.18  4696.4  405.04
  4783.4  404.86  4793.8  405.01  4924.2  404.27  4962.0  403.48  4977.7  403.35
  4996.8  402.60  4999.6  402.10  5002.8  402.60  5012.0  402.74  5027.3  402.63
  5065.1  403.32  5108.5  403.45  5137.7  403.79  5233.3  403.90  5271.1  404.26
  5352.4  404.38  5450.1  404.09  5630.3  404.59  5690.4  404.44  5710.4  404.62
  5780.5  404.70  5790.5  404.80  5800.5  405.45  5810.5  407.37  5815.9  409.23
#Mann=3,-1,0
  4616.9    0.05       0  4996.8    0.03       0  5002.8    0.05       0
Bank Sta=4996.8,5002.8
Exp/Cntr=0.3,0.1

Type RM Length L Ch R = 1,2247,769,769,769
BEGIN DESCRIPTION:
UNT0778 IN SAND CR 3.2
END DESCRIPTION:
XS GIS Cut Line= 2
      3569474.19     10445069.30      3570593.99     10445351.43
#Sta/Elev= 30
  4535.6  400.85  4567.6  400.85  4603.5  400.24  4608.7  400.32  4626.3  399.90
  4649.8  399.76  4667.5  399.90  4685.7  399.59  4832.5  398.69  4884.1  398.72
  4937.4  398.48  4966.6  398.60  4987.2  398.26  4994.5  397.90  4997.3  397.40
  5000.5  397.90  5014.4  398.21  5060.7  398.33  5096.6  398.67  5178.8  399.90
  5184.0  399.76  5214.1  400.05  5337.8  400.10  5384.3  400.33  5420.2  400.34
  5425.4  400.20  5451.3  400.45  5630.8  400.70  5647.2  400.96  5690.4  401.13
#Mann=3,-1,0
  4535.6    0.05       0  4994.5    0.03       0  5000.5    0.05       0
Bank Sta=4994.5,5000.5
Exp/Cntr=0.3,0.1

Type RM Length L Ch R = 1,1478,422,422,422
BEGIN DESCRIPTION:
UNT0778 IN SAND CR 3.0
END DESCRIPTION:
XS GIS Cut Line= 2
      3569135.70     10445594.50      3570363.96     10446132.68
#Sta/Elev= 30
  4418.4  400.14  4567.3  398.16  4632.8  396.60  4709.3  395.45  4724.2  395.30
  4747.6  396.23  4770.9  396.25  4799.8  395.63  4823.2  396.40  4852.0  396.33
  4893.3  395.24  4898.7  394.56  4916.7  394.65  4951.0  394.19  4968.9  394.36
  4997.7  393.82  5021.1  394.26  5055.6  393.61  5058.4  393.11  5061.6  393.61
  5102.3  394.54  5143.4  394.56  5148.9  394.99  5172.3  395.58  5201.1  395.89
  5375.7  396.31  5573.6  397.44  5620.3  397.38  5702.8  397.99  5759.4  398.94
#Mann=3,-1,0
  4418.4    0.05       0  5055.6   0.035       0  5061.6    0.05       0
Bank Sta=5055.6,5061.6
Exp/Cntr=0.3,0.1

Type RM Length L Ch R = 1,1056,458,458,458
BEGIN DESCRIPTION:
UNT0778 IN SAND CR 1.3
END DESCRIPTION:
XS GIS Cut Line= 3
      3569055.57     10445775.87      3569097.24     10446012.88
      3569997.68     10446431.87
#Sta/Elev= 30
  4334.0  398.87  4343.9  398.95  4403.2  398.49  4457.5  398.91  4511.8  398.33
  4563.2  398.16  4574.3  397.82  4607.4  397.58  4704.5  396.15  4744.7  395.32
  4824.4  394.09  4910.4  392.95  4977.1  392.45  4990.1  391.34  4996.1  390.56
  4998.9  390.06  5002.1  390.56  5007.4  391.52  5021.2  391.75  5035.8  392.36
  5058.7  392.44  5065.3  392.65  5132.9  392.13  5230.8  394.11  5252.8  394.37
  5367.2  394.96  5384.6  395.21  5429.3  395.11  5527.4  395.54  5567.8  396.01
#Mann=3,-1,0
  4334.0    0.05       0  4996.1    0.03       0  5002.1    0.05       0
Bank Sta=4996.1,5002.1
Exp/Cntr=0.3,0.1

Type RM Length L Ch R = 1,598,18,18,18
BEGIN DESCRIPTION:
UNT0778 IN SAND CR 1.4
END DESCRIPTION:
XS GIS Cut Line= 6
      3569019.12     10445809.77      3569112.86     10446387.88
      3569131.09     10446486.84      3569183.18     10446528.51
      3569862.86     10446507.67      3569867.61     10446512.42
#Sta/Elev= 30
  4272.2  398.59  4486.8  398.59  4790.8  393.89  4819.0  394.74  4831.3  392.63
  4841.4  392.32  4879.1  393.00  4884.2  390.88  4912.5  392.72  4932.1  394.97
  4937.2  392.53  4962.3  395.16  4970.2  392.51  4976.6  393.46  4984.6  391.27
  4991.0  392.38  4998.2  390.77  5005.4  390.63  5019.8  390.98  5023.7  393.16
  5074.1  394.38  5082.9  394.23  5087.9  392.40  5110.2  390.35  5141.2  390.21
  5143.9  389.71  5147.2  390.21  5334.3  393.26  5474.3  392.87  5711.9  395.31
#Mann=3,-1,0
  4272.2    0.05       0  5141.2    0.03       0  5147.2    0.05       0
Bank Sta=5141.2,5147.2
Exp/Cntr=0.3,0.1

Type RM Length L Ch R = 1,580,36,36,36
BEGIN DESCRIPTION:
UNT0778 IN SAND CR 1.2
END DESCRIPTION:
XS GIS Cut Line= 6
      3568995.67     10445833.16      3569090.73     10446357.93
      3569093.33     10446434.76      3569125.89     10446501.16
      3569166.25     10446540.23      3569842.03     10446536.32
#Sta/Elev= 30
  4277.0  398.63  4511.9  398.23  4789.3  393.45  4809.7  395.72  4864.1  397.24
  4887.2  396.77  4892.5  395.74  4898.1  396.96  4915.0  396.37  4920.6  397.00
  4928.3  396.60  4937.5  395.33  4943.1  396.27  4972.9  395.53  4980.1  394.73
  4987.0  395.41  4994.2  393.95  5001.2  395.40  5008.4  394.74  5073.2  395.68
  5093.2  394.57  5113.2  391.64  5123.2  390.80  5140.2  390.74  5142.9  390.24
  5146.2  390.74  5193.2  391.77  5333.2  393.28  5443.2  393.28  5693.1  395.14
#Mann=3,-1,0
  4277.0    0.05       0  5140.2    0.03       0  5146.2    0.05       0
Bank Sta=5140.2,5146.2
Exp/Cntr=0.3,0.1

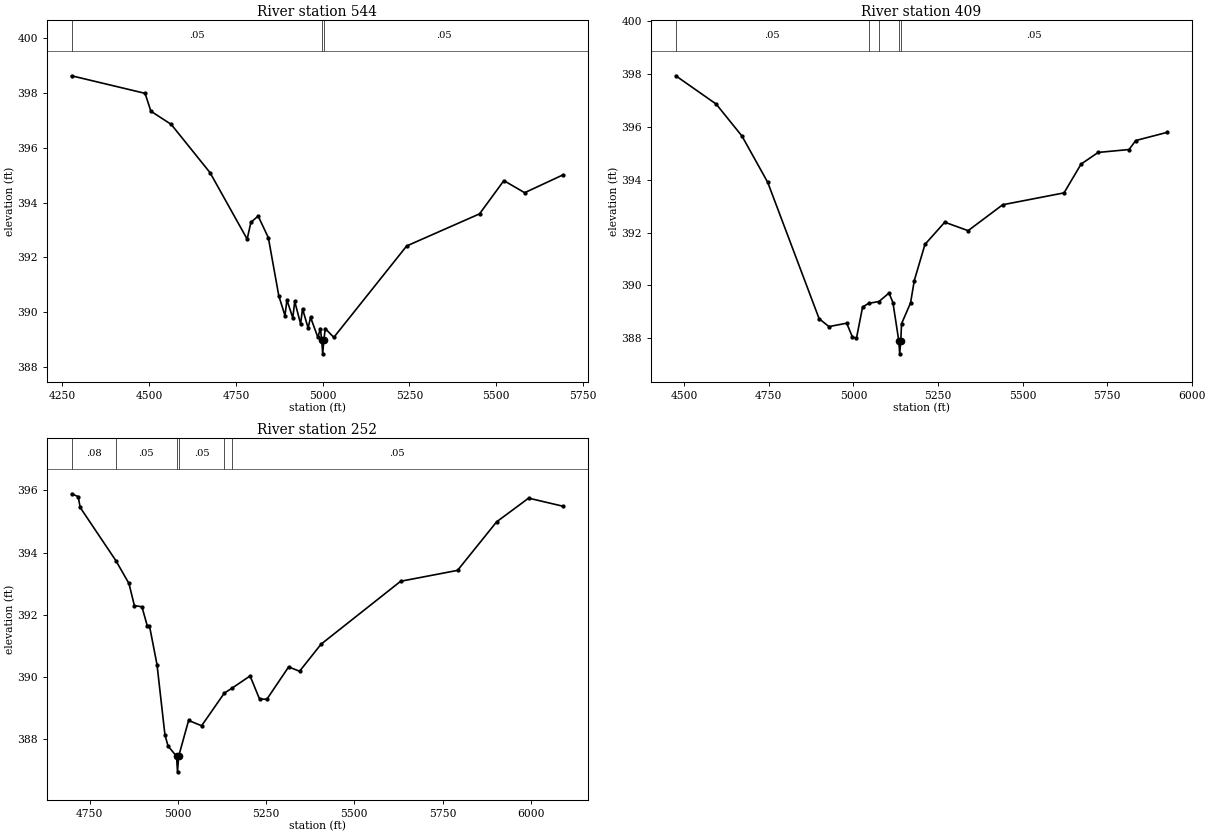
Type RM Length L Ch R = 1,544,135,135,135
BEGIN DESCRIPTION:
UNT0778 IN SAND CR 1.5
END DESCRIPTION:
XS GIS Cut Line= 6
      3568976.14     10445863.09      3569071.20     10446387.88
      3569073.80     10446464.70      3569106.35     10446531.11
      3569146.72     10446570.17      3569822.49     10446566.27
#Sta/Elev= 30
  4276.4  398.62  4488.3  397.98  4504.9  397.33  4563.5  396.85  4675.5  395.09
  4782.4  392.67  4793.2  393.28  4814.1  393.51  4843.5  392.72  4873.5  390.61
  4891.4  389.88  4897.0  390.45  4913.9  389.80  4919.5  390.40  4936.4  389.58
  4942.0  390.13  4958.1  389.43  4965.1  389.82  4986.2  389.09  4993.3  389.41
  4997.3  388.99  5000.1  388.49  5003.3  388.99  5007.5  389.41  5032.1  389.09
  5242.1  392.42  5452.1  393.59  5522.1  394.80  5582.1  394.36  5692.5  395.01
#Mann=3,-1,0
  4276.4    0.05       0  4997.3    0.03       0  5003.3    0.05       0
Bank Sta=4997.3,5003.3
Exp/Cntr=0.3,0.1

Type RM Length L Ch R = 1,409,157,157,157
BEGIN DESCRIPTION:
UNT0778 IN SAND CR 1.1
END DESCRIPTION:
XS GIS Cut Line= 4
      3568807.33     10446121.97      3569046.89     10446677.49
      3569355.92     10446778.18      3569874.60     10446711.77
#Sta/Elev= 30
  4474.8  397.93  4594.2  396.86  4670.5  395.65  4746.6  393.90  4898.6  388.74
  4927.6  388.44  4980.1  388.57  4997.2  388.04  5009.0  388.00  5027.1  389.18
  5045.1  389.32  5075.6  389.39  5105.2  389.71  5116.8  389.35  5134.1  387.91
  5136.8  387.41  5140.1  387.91  5142.3  388.55  5169.0  389.34  5179.9  390.18
  5211.5  391.55  5270.0  392.39  5339.1  392.07  5441.3  393.05  5622.7  393.50
  5673.1  394.59  5723.6  395.03  5815.0  395.14  5834.5  395.48  5927.7  395.79
#Mann=5,-1,0
  4474.8    0.05       0  5045.1     0.1       0  5075.6    0.05       0
  5134.1    0.03       0  5140.1    0.05       0
Bank Sta=5134.1,5140.1
Exp/Cntr=0.3,0.1

Type RM Length L Ch R = 1,252,0,0,0
BEGIN DESCRIPTION:
UNT0778 IN SAND CR 1.0
END DESCRIPTION:
XS GIS Cut Line= 4
      3568704.86     10446344.99      3568930.57     10446720.46
      3569312.52     10446815.94      3569868.70     10446748.85
#Sta/Elev= 30
  4699.1  395.89  4717.8  395.80  4723.6  395.45  4824.8  393.74  4861.6  393.01
  4877.1  392.30  4898.5  392.26  4914.0  391.63  4919.8  391.65  4941.2  390.40
  4963.6  388.15  4972.3  387.79  4996.5  387.46  4999.2  386.96  5002.5  387.46
  5030.6  388.61  5067.5  388.44  5131.9  389.49  5152.8  389.64  5204.8  390.04
  5231.5  389.30  5252.2  389.29  5314.0  390.33  5344.9  390.19  5405.9  391.06
  5631.2  393.08  5792.4  393.43  5903.2  394.99  5993.8  395.75  6091.1  395.49
#Mann=6,-1,0
  4699.1    0.08       0  4824.8    0.05       0  4996.5   0.033       0
  5002.5    0.05       0  5131.9     0.1       0  5152.8    0.05       0
Bank Sta=4996.5,5002.5
Exp/Cntr=0.3,0.1

Chan Stop Cuts=-1