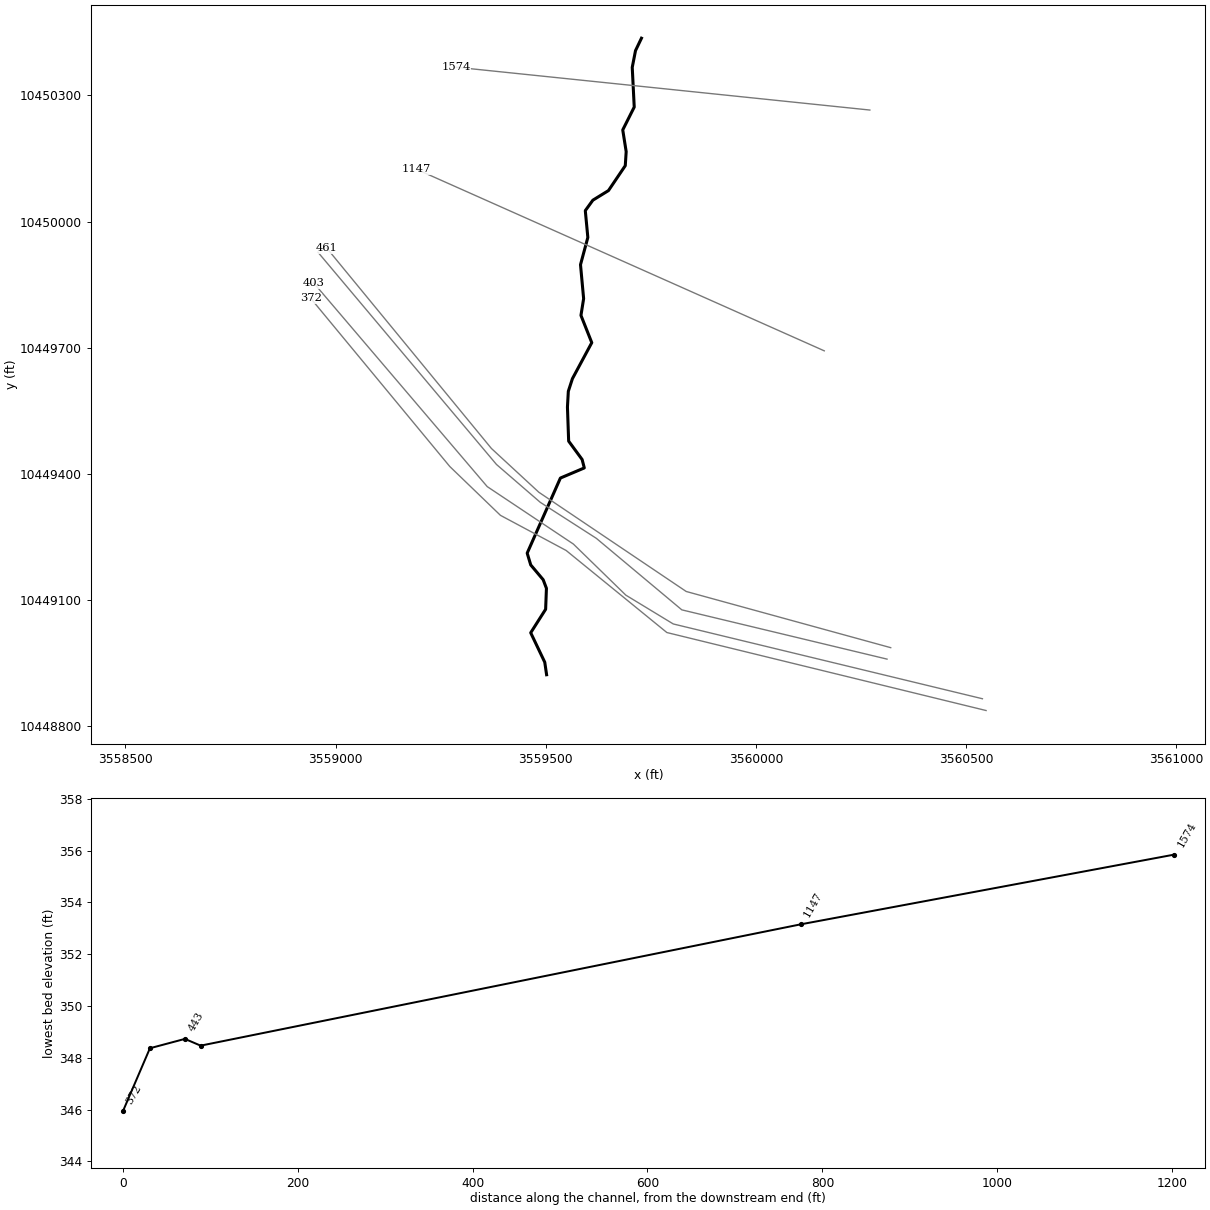
--- UNT0781 IN SAND CR.prj (project) ---

Proj Title=UNT0781 IN SAND CR Base Level Engineering
Current Plan=p01
Default Exp/Contr=0.3,0.1
English Units
Geom File=g01
Flow File=f01
Plan File=p01
BEGIN DESCRIPTION:
UNT0781 IN SAND CR
END DESCRIPTION:

--- UNT0781 IN SAND CR.p01 (plan) ---

Plan Title=Multiple Run
Short Identifier=Multiple
Geom File=g01
Flow File=f01
Subcritical Flow
K Sum by GR= 0
Std Step Tol= 0.01
Critical Tol= 0.01
Num of Std Step Trials= 20
Max Error Tol= 0.3
Flow Tol Ratio= 0.001
Split Flow NTrial= 30
Split Flow Tol= 0.02
Split Flow Ratio= 0.02
Log Output Level= 0
Friction Slope Method= 1
Unsteady Friction Slope Method= 2
Unsteady Bridges Friction Slope Method= 1
Parabolic Critical Depth
Global Vel Dist=  1 , 1 , 1
Global Log Level= 0
CheckData=True
Encroach Param= -1, 0, 0, 0
BEGIN DESCRIPTION:
Multiple Run
END DESCRIPTION:

--- UNT0781 IN SAND CR.f01 (steady flow) ---

Flow Title=Multiple
Number of Profiles=7
Profile Names=10-year,25-year,50-year,1pct_min,100-year,1pct_plu,500-year
River Rch & RM= UNT0781 IN SAND ,Reach-1,1574
     601     810     979     867    1173    1586    1674
Boundary for River Rch & Prof#=UNT0781 IN SAND ,Reach-1,1
Up Type=0
Dn Type=3
Dn Slope=0.005
Boundary for River Rch & Prof#=UNT0781 IN SAND ,Reach-1,2
Up Type=0
Dn Type=3
Dn Slope=0.005
Boundary for River Rch & Prof#=UNT0781 IN SAND ,Reach-1,3
Up Type=0
Dn Type=3
Dn Slope=0.005
Boundary for River Rch & Prof#=UNT0781 IN SAND ,Reach-1,4
Up Type=0
Dn Type=3
Dn Slope=0.005
Boundary for River Rch & Prof#=UNT0781 IN SAND ,Reach-1,5
Up Type=0
Dn Type=3
Dn Slope=0.005
Boundary for River Rch & Prof#=UNT0781 IN SAND ,Reach-1,6
Up Type=0
Dn Type=3
Dn Slope=0.005
Boundary for River Rch & Prof#=UNT0781 IN SAND ,Reach-1,7
Up Type=0
Dn Type=3
Dn Slope=0.005

--- UNT0781 IN SAND CR.g01 (geometry) ---

Geom Title=Existing Conditions

River Reach=UNT0781 IN SAND ,Reach-1
Reach XY= 30
      3559727.86     10450436.15      3559713.68     10450406.59
      3559705.90     10450366.76      3559710.63     10450272.27
      3559683.30     10450217.94      3559691.47     10450166.23
      3559689.32     10450132.85      3559649.31     10450073.59
      3559612.18     10450050.73      3559594.20     10450025.89
      3559600.24     10449962.06      3559582.79     10449897.28
      3559590.22     10449816.55      3559583.87     10449776.62
      3559609.62     10449711.73      3559563.55     10449626.06
      3559553.82     10449596.10      3559551.71     10449558.37
      3559554.59     10449477.44      3559586.65     10449433.74
      3559591.82     10449413.70      3559534.95     10449389.62
      3559455.91     10449210.96      3559464.37     10449182.89
      3559493.99     10449147.69      3559501.72     10449127.24
      3559499.80     10449077.39      3559464.30     10449021.53
      3559497.74     10448951.42      3559502.11     10448921.64

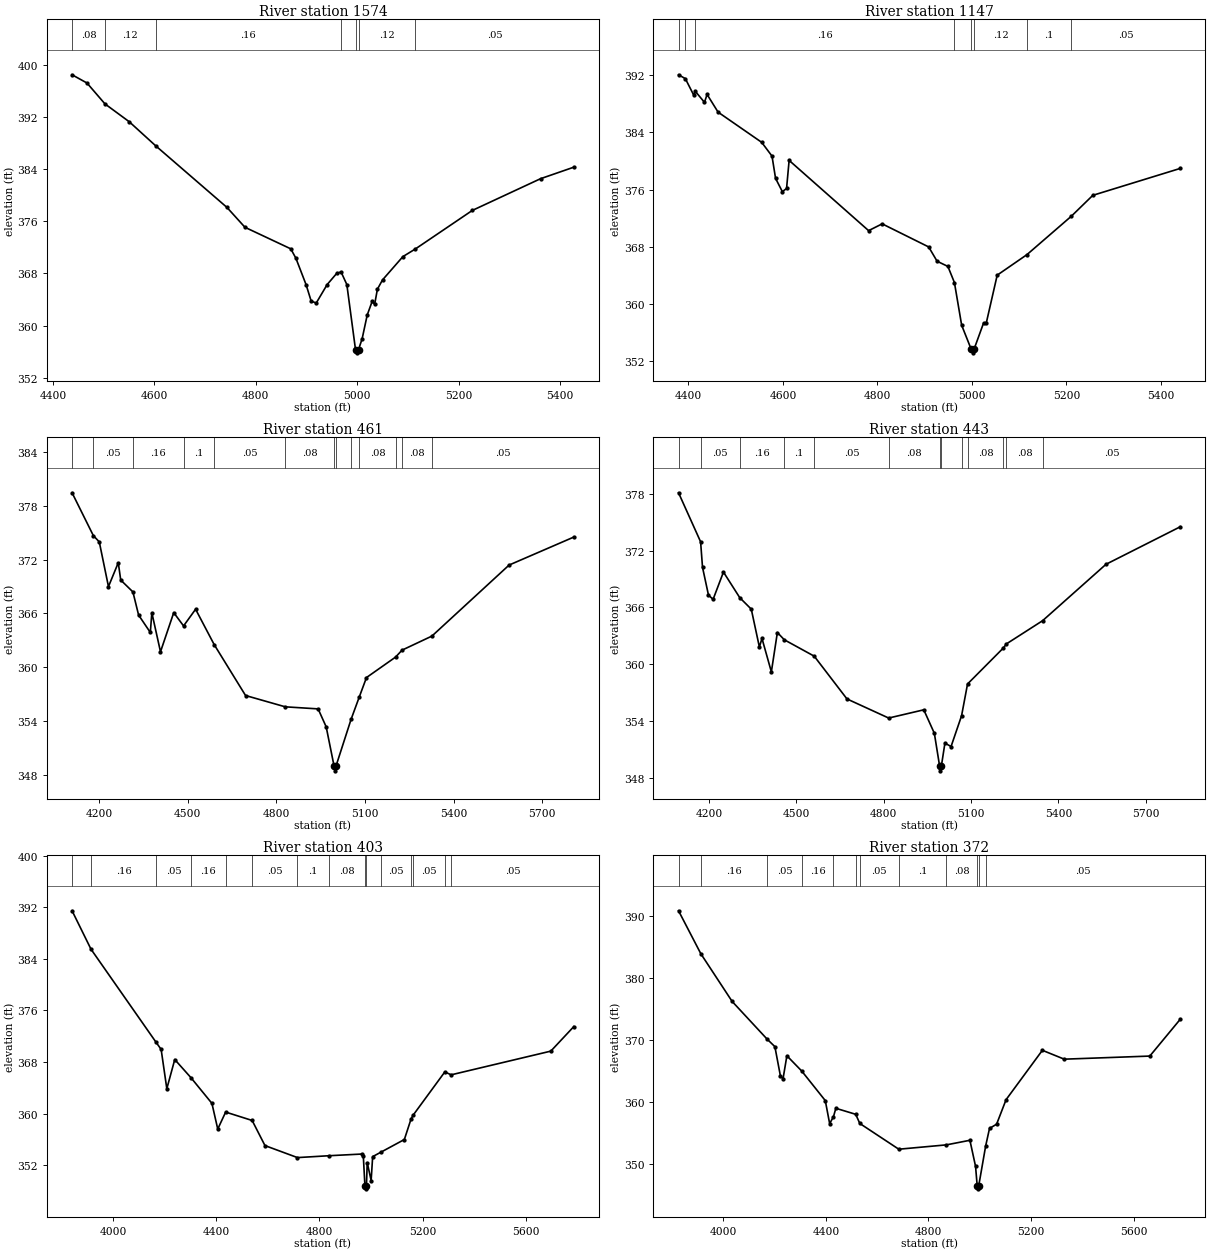
Type RM Length L Ch R = 1,1574,427,427,427
BEGIN DESCRIPTION:
UNT0781 IN SAND CR 3.0
END DESCRIPTION:
XS GIS Cut Line= 2
      3560271.35     10450265.21      3559286.61     10450367.16
#Sta/Elev= 30
  4437.5  398.43  4466.9  397.17  4502.4  393.97  4550.4  391.23  4602.2  387.57
  4743.0  378.12  4778.6  375.07  4869.0  371.77  4879.1  370.33  4899.2  366.28
  4909.3  363.75  4919.3  363.48  4940.7  366.29  4959.5  368.00  4968.2  368.23
  4979.6  366.30  4996.7  356.34  4999.5  355.84  5002.7  356.34  5009.8  358.00
  5019.8  361.63  5029.5  363.71  5034.5  363.28  5039.9  365.59  5050.0  367.01
  5090.2  370.58  5114.8  371.75  5227.1  377.65  5361.7  382.51  5427.5  384.28
#Mann=7,-1,0
  4437.5    0.08       0  4502.4    0.12       0  4602.2    0.16       0
  4968.2    0.12       0  4996.7    0.07       0  5002.7    0.12       0
  5114.8    0.05       0
Bank Sta=4996.7,5002.7
Exp/Cntr=0.3,0.1

Type RM Length L Ch R = 1,1147,686,686,686
BEGIN DESCRIPTION:
UNT0781 IN SAND CR 2.0
END DESCRIPTION:
XS GIS Cut Line= 2
      3560162.83     10449692.30      3559192.81     10450124.15
#Sta/Elev= 30
  4379.1  392.06  4393.5  391.52  4410.8  389.27  4414.8  389.73  4434.0  388.20
  4439.5  389.31  4462.8  386.83  4555.0  382.61  4576.9  380.68  4584.4  377.57
  4598.8  375.70  4607.7  376.15  4613.1  380.08  4781.3  370.25  4810.0  371.20
  4908.4  367.97  4926.2  365.97  4949.1  365.24  4962.9  362.98  4978.2  357.01
  4998.4  353.65  5001.2  353.15  5004.4  353.65  5024.6  357.33  5030.1  357.27
  5053.4  364.02  5116.3  366.89  5210.5  372.28  5255.7  375.19  5440.9  378.96
#Mann=8,-1,0
  4379.1    0.05       0  4393.5    0.08       0  4414.8    0.16       0
  4962.9    0.12       0  4998.4    0.07       0  5004.4    0.12       0
  5116.3     0.1       0  5210.5    0.05       0
Bank Sta=4998.4,5004.4
Exp/Cntr=0.3,0.1

Type RM Length L Ch R = 1,461,18,18,18
BEGIN DESCRIPTION:
UNT0781 IN SAND CR 1.1
END DESCRIPTION:
XS GIS Cut Line= 5
      3560320.95     10448986.05      3559834.33     10449119.74
      3559483.64     10449355.85      3559370.79     10449460.02
      3558978.79     10449937.01
#Sta/Elev= 30
  4108.4  379.44  4180.4  374.67  4200.5  373.97  4231.6  368.99  4264.8  371.65
  4273.1  369.72  4314.3  368.40  4333.6  365.82  4373.3  363.88  4378.4  366.08
  4407.7  361.73  4452.5  366.09  4485.8  364.61  4526.5  366.47  4589.4  362.53
  4695.6  356.86  4830.0  355.60  4941.2  355.37  4968.5  353.37  4995.4  348.97
  4998.2  348.47  5001.4  348.97  5052.7  354.20  5080.2  356.67  5104.9  358.86
  5203.4  361.14  5225.1  361.91  5326.4  363.48  5587.6  371.39  5806.8  374.51
#Mann=13,-1,0
  4108.4    0.16       0  4180.4    0.05       0  4314.3    0.16       0
  4485.8     0.1       0  4589.4    0.05       0  4830.0    0.08       0
  4995.4    0.07       0  5001.4    0.08       0  5052.7    0.16       0
  5080.2    0.08       0  5203.4    0.05       0  5225.1    0.08       0
  5326.4    0.05       0
Bank Sta=4995.4,5001.4
Exp/Cntr=0.3,0.1

Type RM Length L Ch R = 1,443,40,40,40
BEGIN DESCRIPTION:
UNT0781 IN SAND CR 1.0
END DESCRIPTION:
XS GIS Cut Line= 6
      3560312.19     10448958.83      3559823.91     10449076.01
      3559620.46     10449246.19      3559487.00     10449331.91
      3559382.83     10449421.97      3558957.90     10449927.11
#Sta/Elev= 30
  4095.2  378.12  4171.0  372.94  4177.6  370.24  4198.1  367.30  4214.0  366.86
  4249.5  369.74  4305.6  367.03  4345.1  365.82  4372.9  361.82  4381.9  362.72
  4414.1  359.19  4434.7  363.35  4458.7  362.58  4561.3  360.85  4673.8  356.33
  4817.1  354.31  4937.7  355.18  4974.0  352.70  4992.1  349.23  4994.9  348.73
  4998.1  349.23  5010.3  351.66  5031.4  351.30  5067.5  354.55  5088.0  357.91
  5211.2  361.72  5221.7  362.15  5345.9  364.60  5563.6  370.56  5819.0  374.53
#Mann=13,-1,0
  4095.2    0.16       0  4171.0    0.05       0  4305.6    0.16       0
  4458.7     0.1       0  4561.3    0.05       0  4817.1    0.08       0
  4992.1    0.07       0  4998.1    0.08       0  5067.5    0.05       0
  5088.0    0.08       0  5211.2    0.05       0  5221.7    0.08       0
  5345.9    0.05       0
Bank Sta=4992.1,4998.1
Exp/Cntr=0.3,0.1

Type RM Length L Ch R = 1,403,31,31,31
BEGIN DESCRIPTION:
UNT0781 IN SAND CR 1.2
END DESCRIPTION:
XS GIS Cut Line= 6
      3560539.17     10448864.54      3559803.52     10449042.48
      3559690.67     10449111.02      3559565.89     10449232.55
      3559360.81     10449369.27      3558948.47     10449853.23
#Sta/Elev= 30
  3840.8  391.44  3914.2  385.49  4166.7  371.06  4186.2  369.97  4208.2  363.88
  4239.0  368.40  4301.3  365.61  4383.1  361.61  4405.7  357.63  4436.4  360.26
  4539.1  358.96  4588.8  355.07  4714.8  353.21  4837.6  353.50  4964.2  353.76
  4970.2  353.42  4976.4  348.87  4979.1  348.37  4982.4  348.87  4985.3  352.44
  5000.5  349.66  5006.4  353.36  5037.1  354.02  5129.3  356.01  5154.9  359.14
  5162.4  359.73  5286.2  366.48  5310.8  366.03  5697.2  369.70  5786.6  373.51
#Mann=15,-1,0
  3840.8     0.1       0  3914.2    0.16       0  4166.7    0.05       0
  4301.3    0.16       0  4436.4     0.1       0  4539.1    0.05       0
  4714.8     0.1       0  4837.6    0.08       0  4976.4    0.07       0
  4982.4    0.08       0  5037.1    0.05       0  5154.9    0.08       0
  5162.4    0.05       0  5286.2    0.08       0  5310.8    0.05       0
Bank Sta=4976.4,4982.4
Exp/Cntr=0.3,0.1

Type RM Length L Ch R = 1,372,0,0,0
BEGIN DESCRIPTION:
UNT0781 IN SAND CR 1.3
END DESCRIPTION:
XS GIS Cut Line= 6
      3560547.89     10448836.50      3559788.33     10449022.05
      3559548.53     10449217.36      3559392.28     10449300.91
      3559271.83     10449417.01      3558940.59     10449817.53
#Sta/Elev= 30
  3825.7  390.77  3912.8  383.83  4034.7  376.15  4171.3  370.06  4201.3  368.86
  4222.8  364.15  4233.1  363.68  4248.1  367.39  4305.9  364.93  4397.8  360.16
  4414.8  356.45  4429.6  357.55  4439.0  358.92  4516.4  357.95  4532.4  356.47
  4684.4  352.32  4869.9  353.02  4961.6  353.76  4983.6  349.56  4990.0  346.43
  4992.7  345.93  4996.0  346.43  5023.0  352.84  5038.0  355.67  5065.7  356.36
  5102.6  360.31  5244.1  368.27  5329.4  366.84  5662.9  367.34  5781.9  373.29
#Mann=12,-1,0
  3825.7     0.1       0  3912.8    0.16       0  4171.3    0.05       0
  4305.9    0.16       0  4429.6    0.05       0  4516.4     0.1       0
  4532.4    0.05       0  4684.4     0.1       0  4869.9    0.08       0
  4990.0    0.07       0  4996.0    0.08       0  5023.0    0.05       0
Bank Sta=4990,4996
Exp/Cntr=0.3,0.1

Chan Stop Cuts=-1