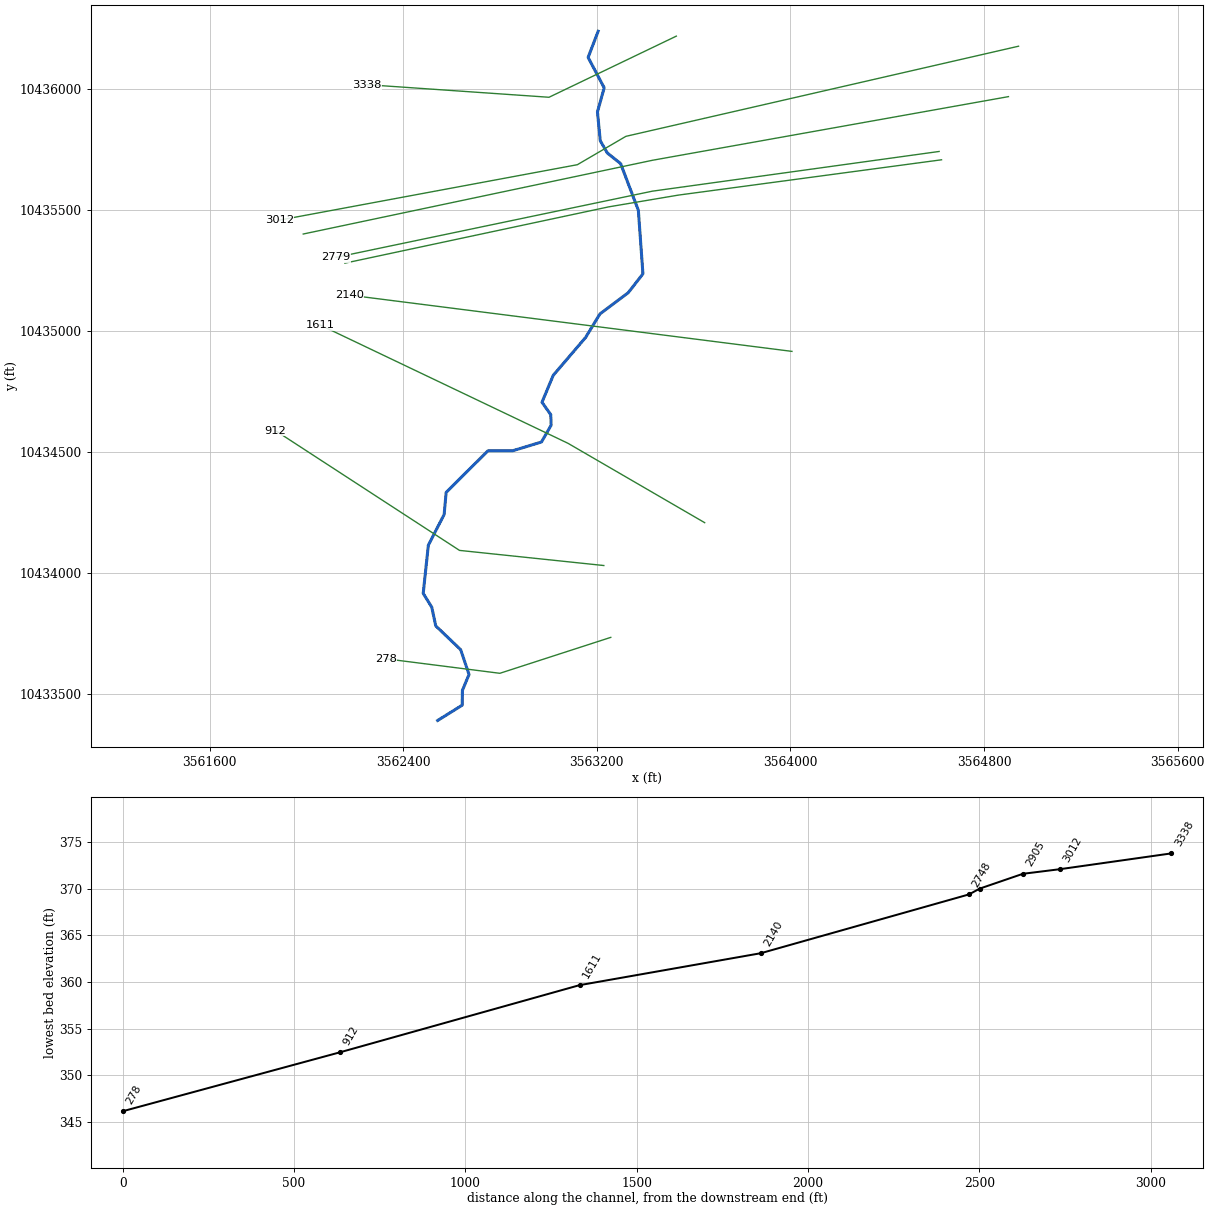
--- UNT0795 IN SAND CR.prj (project) ---

Proj Title=UNT0795 IN SAND CR Base Level Engineering
Current Plan=p01
Default Exp/Contr=0.3,0.1
English Units
Geom File=g01
Flow File=f01
Plan File=p01
BEGIN DESCRIPTION:
UNT0795 IN SAND CR
END DESCRIPTION:

--- UNT0795 IN SAND CR.p01 (plan) ---

Plan Title=Multiple Run
Short Identifier=Multiple
Geom File=g01
Flow File=f01
Subcritical Flow
K Sum by GR= 0
Std Step Tol= 0.01
Critical Tol= 0.01
Num of Std Step Trials= 20
Max Error Tol= 0.3
Flow Tol Ratio= 0.001
Split Flow NTrial= 30
Split Flow Tol= 0.02
Split Flow Ratio= 0.02
Log Output Level= 0
Friction Slope Method= 1
Unsteady Friction Slope Method= 2
Unsteady Bridges Friction Slope Method= 1
Parabolic Critical Depth
Global Vel Dist=  1 , 1 , 1
Global Log Level= 0
CheckData=True
Encroach Param= -1, 0, 0, 0
BEGIN DESCRIPTION:
Multiple Run
END DESCRIPTION:

--- UNT0795 IN SAND CR.f01 (steady flow) ---

Flow Title=Multiple
Number of Profiles=7
Profile Names=10-year,25-year,50-year,1pct_min,100-year,1pct_plu,500-year
River Rch & RM= UNT0795 IN SAND ,Reach-1,3338
     463     607     721     626     847    1146    1165
River Rch & RM= UNT0795 IN SAND ,Reach-1,2779
     751    1019    1237    1097    1484    2006    2127
Boundary for River Rch & Prof#=UNT0795 IN SAND ,Reach-1,1
Up Type=0
Dn Type=3
Dn Slope=0.005
Boundary for River Rch & Prof#=UNT0795 IN SAND ,Reach-1,2
Up Type=0
Dn Type=3
Dn Slope=0.005
Boundary for River Rch & Prof#=UNT0795 IN SAND ,Reach-1,3
Up Type=0
Dn Type=3
Dn Slope=0.005
Boundary for River Rch & Prof#=UNT0795 IN SAND ,Reach-1,4
Up Type=0
Dn Type=3
Dn Slope=0.005
Boundary for River Rch & Prof#=UNT0795 IN SAND ,Reach-1,5
Up Type=0
Dn Type=3
Dn Slope=0.005
Boundary for River Rch & Prof#=UNT0795 IN SAND ,Reach-1,6
Up Type=0
Dn Type=3
Dn Slope=0.005
Boundary for River Rch & Prof#=UNT0795 IN SAND ,Reach-1,7
Up Type=0
Dn Type=3
Dn Slope=0.005

--- UNT0795 IN SAND CR.g01 (geometry) ---

Geom Title=Existing Conditions

River Reach=UNT0795 IN SAND ,Reach-1
Reach XY= 30
      3563205.52     10436239.80      3563164.04     10436131.58
      3563230.43     10436005.96      3563202.59     10435906.34
      3563214.28     10435787.08      3563243.51     10435736.47
      3563298.37     10435692.72      3563371.62     10435499.68
      3563390.49     10435237.31      3563329.70     10435159.21
      3563212.66     10435071.40      3563154.09     10434974.93
      3563019.84     10434817.86      3562973.39     10434706.56
      3563009.62     10434655.43      3563011.15     10434611.63
      3562971.23     10434542.27      3562851.30     10434505.95
      3562750.05     10434506.06      3562577.39     10434334.17
      3562569.06     10434242.90      3562503.81     10434115.94
      3562482.58     10433916.95      3562517.90     10433859.91
      3562534.46     10433782.51      3562637.26     10433684.47
      3562671.98     10433581.81      3562644.56     10433516.13
      3562643.84     10433455.04      3562542.11     10433391.64

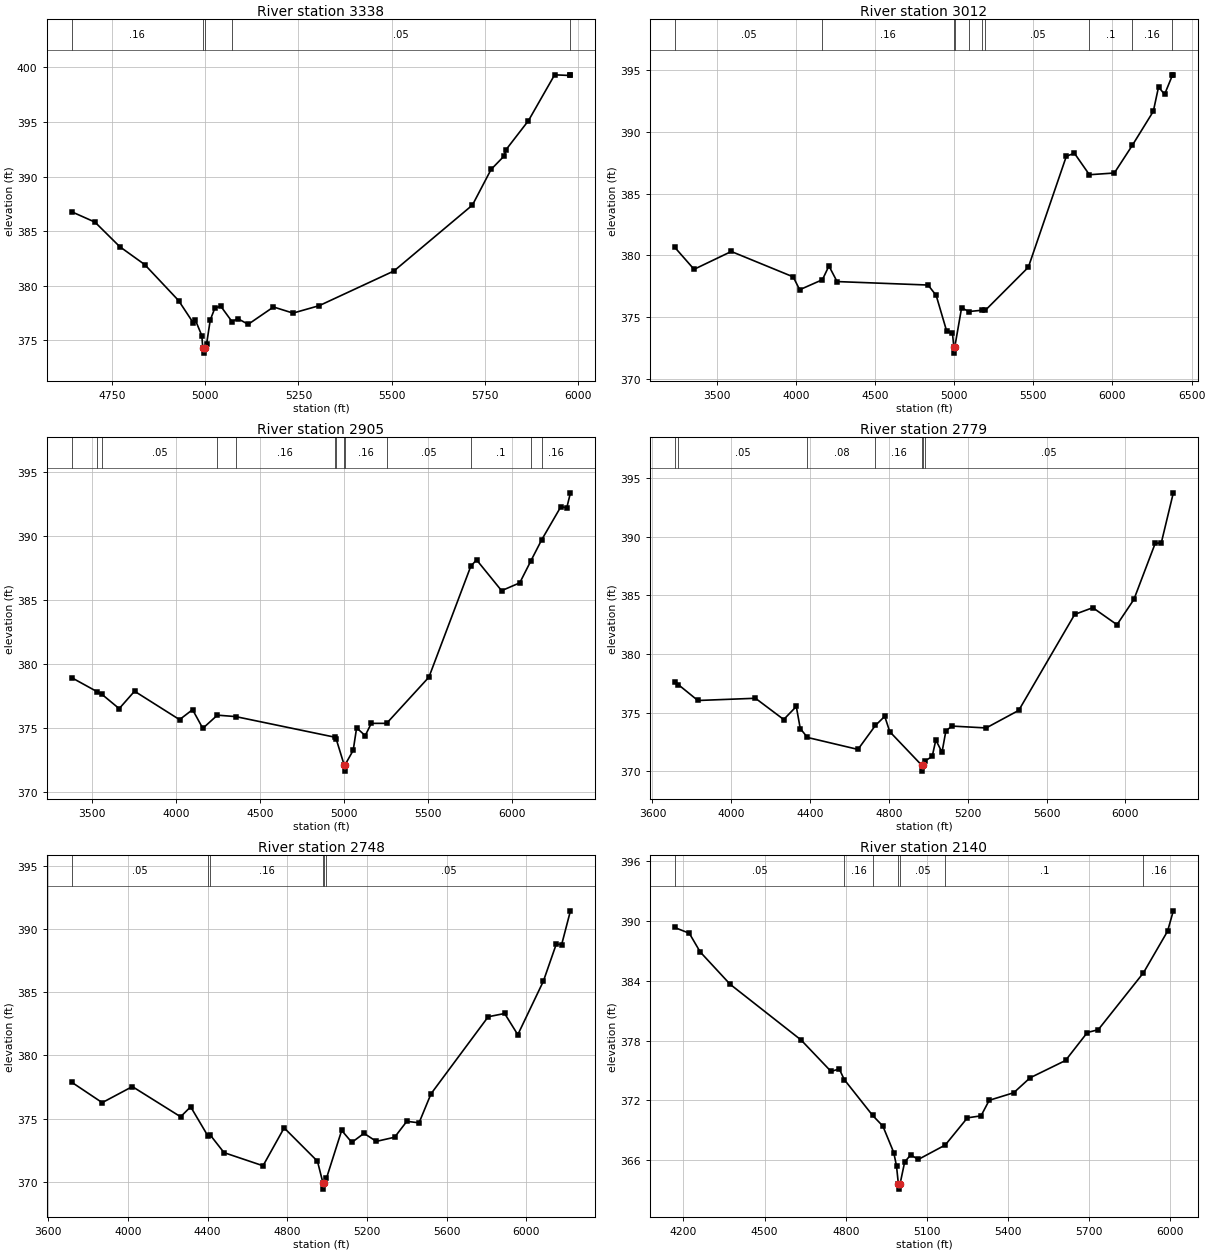
Type RM Length L Ch R = 1,3338,326,326,326
BEGIN DESCRIPTION:
UNT0795 IN SAND CR 6.0
END DESCRIPTION:
XS GIS Cut Line= 3
      3563528.50     10436219.51      3563002.42     10435966.88
      3562249.81     10436018.97
#Sta/Elev= 30
  4641.6  386.77  4704.2  385.82  4770.7  383.57  4837.9  381.92  4928.5  378.63
  4968.2  376.57  4973.8  376.82  4990.9  375.41  4993.4  374.31  4996.2  373.81
  4999.4  374.31  5003.7  374.65  5013.5  376.85  5025.9  377.94  5041.7  378.11
  5072.2  376.68  5087.0  376.98  5115.2  376.45  5183.1  378.04  5235.5  377.48
  5305.7  378.16  5506.2  381.34  5716.7  387.38  5766.8  390.65  5801.5  391.87
  5806.9  392.46  5867.0  395.12  5937.2  399.32  5978.0  399.26  5979.6  399.26
#Mann=5,-1,0
  4641.6    0.16       0  4993.4    0.07       0  4999.4    0.16       0
  5072.2    0.05       0  5978.0     0.1       0
Bank Sta=4993.4,4999.4
Exp/Cntr=0.3,0.1

Type RM Length L Ch R = 1,3012,107,107,107
BEGIN DESCRIPTION:
UNT0795 IN SAND CR 5.1
END DESCRIPTION:
XS GIS Cut Line= 4
      3564942.51     10436177.82      3563320.13     10435805.42
      3563119.61     10435688.24      3561887.86     10435459.07
#Sta/Elev= 30
  3234.6  380.68  3358.1  378.88  3593.2  380.32  3984.0  378.27  4025.0  377.23
  4168.4  378.04  4209.7  379.15  4261.0  377.89  4835.6  377.61  4886.9  376.77
  4952.6  373.91  4989.5  373.74  4998.4  372.61  5001.1  372.11  5004.4  372.61
  5047.4  375.77  5092.6  375.47  5173.6  375.57  5196.6  375.56  5468.9  379.05
  5708.7  388.01  5759.5  388.26  5854.3  386.52  6011.8  386.66  6125.1  388.89
  6257.9  391.64  6290.9  393.61  6329.1  393.01  6378.6  394.56  6384.3  394.59
#Mann=10,-1,0
  3234.6    0.05       0  4168.4    0.16       0  4998.4    0.07       0
  5004.4    0.16       0  5092.6    0.05       0  5173.6    0.16       0
  5196.6    0.05       0  5854.3     0.1       0  6125.1    0.16       0
  6378.6    0.05       0
Bank Sta=4998.4,5004.4
Exp/Cntr=0.3,0.1

Type RM Length L Ch R = 1,2905,126,126,126
BEGIN DESCRIPTION:
UNT0795 IN SAND CR 4.2
END DESCRIPTION:
XS GIS Cut Line= 3
      3564900.87     10435969.49      3563429.51     10435706.47
      3561986.91     10435401.80
#Sta/Elev= 30
  3377.0  378.92  3529.3  377.82  3555.2  377.64  3660.2  376.50  3751.6  377.86
  4019.5  375.64  4097.0  376.42  4157.9  374.96  4244.6  375.99  4352.8  375.88
  4943.7  374.27  4951.4  374.15  4998.9  372.12  5001.6  371.62  5004.9  372.12
  5053.0  373.24  5073.4  375.00  5124.5  374.39  5160.8  375.35  5251.9  375.35
  5503.9  378.96  5752.8  387.61  5787.1  388.12  5936.3  385.71  6044.4  386.32
  6111.5  388.06  6175.7  389.70  6289.7  392.28  6324.1  392.17  6346.1  393.35
#Mann=13,-1,0
  3377.0    0.05       0  3529.3    0.08       0  3555.2    0.05       0
  4244.6    0.08       0  4352.8    0.16       0  4943.7    0.05       0
  4951.4    0.16       0  4998.9    0.07       0  5004.9    0.16       0
  5251.9    0.05       0  5752.8     0.1       0  6111.5    0.05       0
  6175.7    0.16       0
Bank Sta=4998.9,5004.9
Exp/Cntr=0.3,0.1

Type RM Length L Ch R = 1,2779,31,31,31
BEGIN DESCRIPTION:
UNT0795 IN SAND CR 5.0
END DESCRIPTION:
XS GIS Cut Line= 3
      3564614.39     10435742.92      3563429.51     10435578.86
      3562122.19     10435305.42
#Sta/Elev= 30
  3711.9  377.66  3731.4  377.40  3830.5  376.05  4122.7  376.24  4266.2  374.43
  4330.0  375.54  4350.2  373.66  4386.6  372.90  4643.0  371.88  4731.4  373.92
  4778.9  374.70  4804.5  373.39  4966.8  370.53  4969.6  370.03  4972.8  370.53
  4982.7  370.89  5019.8  371.28  5038.2  372.68  5069.7  371.64  5089.3  373.46
  5120.0  373.87  5293.7  373.71  5459.2  375.21  5743.2  383.39  5835.1  383.96
  5957.7  382.51  6043.5  384.66  6151.8  389.45  6182.5  389.48  6243.7  393.75
#Mann=7,-1,0
  3711.9    0.08       0  3731.4    0.05       0  4386.6    0.08       0
  4731.4    0.16       0  4966.8    0.04       0  4972.8    0.16       0
  4982.7    0.05       0
Bank Sta=4966.8,4972.8
Exp/Cntr=0.3,0.1

Type RM Length L Ch R = 1,2748,608,608,608
BEGIN DESCRIPTION:
UNT0795 IN SAND CR 4.0
END DESCRIPTION:
XS GIS Cut Line= 4
      3564624.30     10435708.52      3563537.51     10435562.68
      3563249.32     10435514.07      3562159.06     10435281.44
#Sta/Elev= 30
  3717.8  377.88  3871.4  376.26  4022.7  377.53  4264.9  375.14  4315.3  375.93
  4400.8  373.65  4412.3  373.72  4482.8  372.30  4678.5  371.26  4784.5  374.26
  4951.7  371.62  4979.1  369.91  4981.8  369.41  4985.1  369.91  4996.7  370.26
  5073.3  374.06  5124.2  373.11  5185.3  373.83  5246.9  373.19  5339.0  373.52
  5400.3  374.78  5461.6  374.66  5521.7  376.96  5808.6  383.06  5891.1  383.32
  5957.2  381.64  6085.4  385.87  6150.2  388.81  6177.4  388.78  6221.4  391.45
#Mann=6,-1,0
  3717.8    0.05       0  4400.8    0.08       0  4412.3    0.16       0
  4979.1    0.04       0  4985.1    0.16       0  4996.7    0.05       0
Bank Sta=4979.1,4985.1
Exp/Cntr=0.3,0.1

Type RM Length L Ch R = 1,2140,529,529,529
BEGIN DESCRIPTION:
UNT0795 IN SAND CR 4.1
END DESCRIPTION:
XS GIS Cut Line= 2
      3564006.31     10434916.84      3562176.74     10435149.45
#Sta/Elev= 30
  4167.0  389.37  4221.6  388.79  4262.0  386.91  4372.8  383.66  4634.9  378.07
  4745.8  374.91  4776.1  375.16  4794.7  374.09  4899.6  370.49  4937.4  369.42
  4977.7  366.76  4987.8  365.41  4994.8  363.59  4997.6  363.09  5000.8  363.59
  5018.0  365.82  5040.4  366.53  5068.4  366.07  5168.0  367.52  5249.9  370.25
  5300.3  370.45  5330.5  372.01  5421.2  372.77  5481.7  374.27  5612.7  376.01
  5693.4  378.82  5733.7  379.10  5900.9  384.82  5989.9  388.99  6011.3  391.04
#Mann=7,-1,0
  4167.0    0.05       0  4794.7    0.16       0  4899.6    0.05       0
  4994.8    0.04       0  5000.8    0.05       0  5168.0     0.1       0
  5900.9    0.16       0
Bank Sta=4994.8,5000.8
Exp/Cntr=0.3,0.1

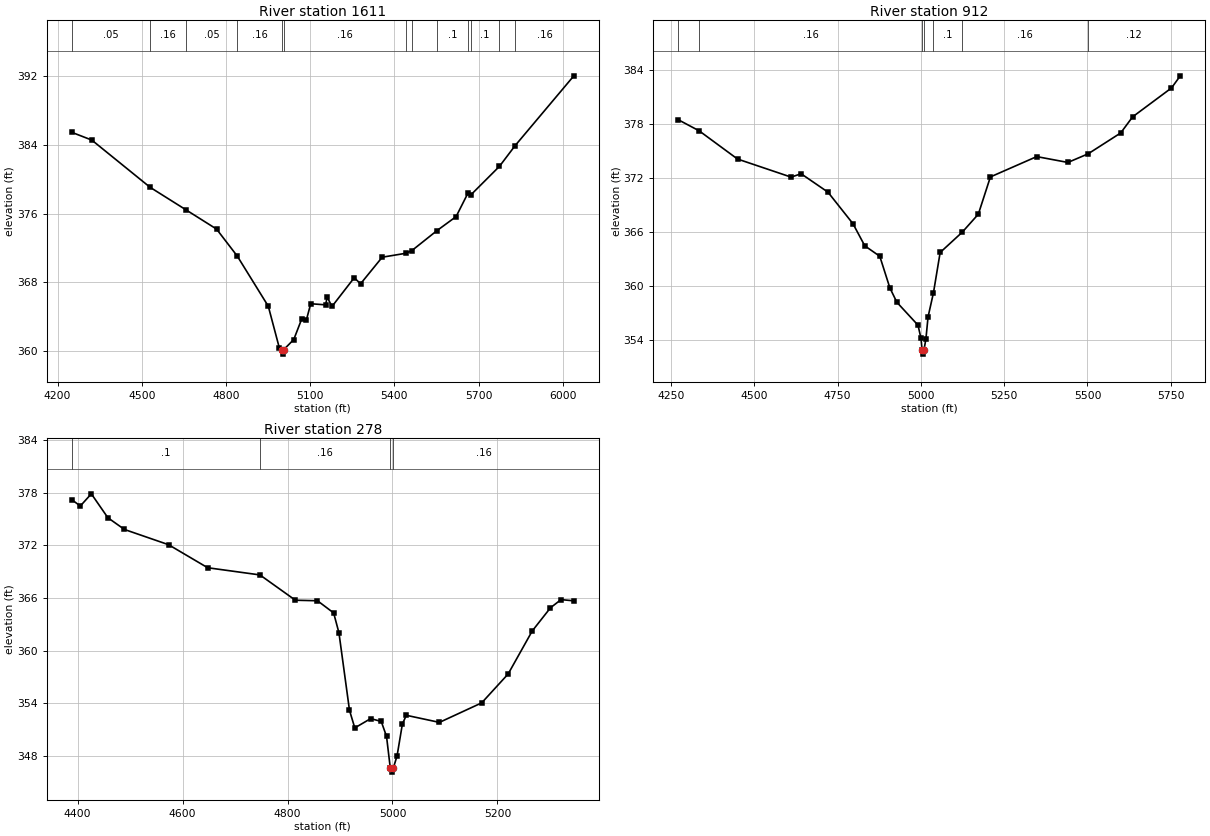
Type RM Length L Ch R = 1,1611,699,699,699
BEGIN DESCRIPTION:
UNT0795 IN SAND CR 3.0
END DESCRIPTION:
XS GIS Cut Line= 3
      3563645.65     10434209.07      3563080.55     10434537.20
      3562055.97     10435026.08
#Sta/Elev= 30
  4250.5  385.45  4321.8  384.55  4529.5  379.06  4656.8  376.45  4766.3  374.20
  4839.9  371.07  4950.6  365.23  4990.4  360.33  4999.0  360.16  5001.7  359.66
  5005.0  360.16  5041.4  361.36  5069.6  363.74  5086.7  363.67  5101.7  365.52
  5154.8  365.39  5160.4  366.29  5177.5  365.20  5256.8  368.54  5279.4  367.84
  5356.5  370.93  5439.5  371.38  5461.8  371.69  5551.1  374.01  5619.7  375.65
  5662.7  378.43  5672.4  378.18  5774.3  381.50  5829.9  383.90  6039.2  392.02
#Mann=13,-1,0
  4250.5    0.05       0  4529.5    0.16       0  4656.8    0.05       0
  4839.9    0.16       0  4999.0    0.07       0  5005.0    0.16       0
  5439.5     0.1       0  5461.8    0.16       0  5551.1     0.1       0
  5662.7    0.16       0  5672.4     0.1       0  5774.3    0.12       0
  5829.9    0.16       0
Bank Sta=4999,5005
Exp/Cntr=0.3,0.1

Type RM Length L Ch R = 1,912,634,634,634
BEGIN DESCRIPTION:
UNT0795 IN SAND CR 2.0
END DESCRIPTION:
XS GIS Cut Line= 3
      3563228.99     10434031.99      3562632.63     10434094.49
      3561872.17     10434589.31
#Sta/Elev= 30
  4271.7  378.51  4334.3  377.28  4449.6  374.14  4610.4  372.13  4640.6  372.50
  4721.0  370.46  4796.3  366.94  4831.6  364.49  4876.6  363.33  4906.9  359.81
  4928.0  358.21  4991.3  355.67  5000.4  354.19  5003.4  352.95  5006.1  352.45
  5009.4  352.95  5015.1  354.15  5021.5  356.59  5037.7  359.27  5057.8  363.75
  5124.2  366.01  5172.4  368.01  5208.6  372.15  5347.6  374.41  5441.2  373.76
  5502.0  374.72  5599.7  377.04  5635.5  378.83  5752.1  382.04  5778.6  383.39
#Mann=7,-1,0
  4271.7     0.1       0  4334.3    0.16       0  5003.4    0.07       0
  5009.4    0.16       0  5037.7     0.1       0  5124.2    0.16       0
  5502.0    0.12       0
Bank Sta=5003.4,5009.4
Exp/Cntr=0.3,0.1

Type RM Length L Ch R = 1,278,0,0,0
BEGIN DESCRIPTION:
UNT0795 IN SAND CR 1.0
END DESCRIPTION:
XS GIS Cut Line= 3
      3563257.60     10433735.10      3562799.30     10433586.67
      3562327.93     10433646.57
#Sta/Elev= 30
  4388.8  377.23  4405.1  376.51  4426.1  377.90  4457.6  375.17  4489.2  373.83
  4573.3  372.09  4647.8  369.46  4747.4  368.64  4815.0  365.75  4857.1  365.69
  4887.9  364.30  4898.0  362.03  4918.1  353.18  4928.2  351.17  4958.4  352.23
  4978.6  351.91  4988.7  350.20  4995.8  346.62  4998.5  346.12  5001.8  346.62
  5008.8  347.98  5018.9  351.61  5026.4  352.61  5089.5  351.80  5170.1  354.03
  5220.5  357.33  5266.4  362.24  5301.2  364.89  5321.3  365.82  5345.7  365.68
#Mann=4,-1,0
  4388.8     0.1       0  4747.4    0.16       0  4995.8    0.07       0
  5001.8    0.16       0
Bank Sta=4995.8,5001.8
Exp/Cntr=0.3,0.1

Chan Stop Cuts=-1