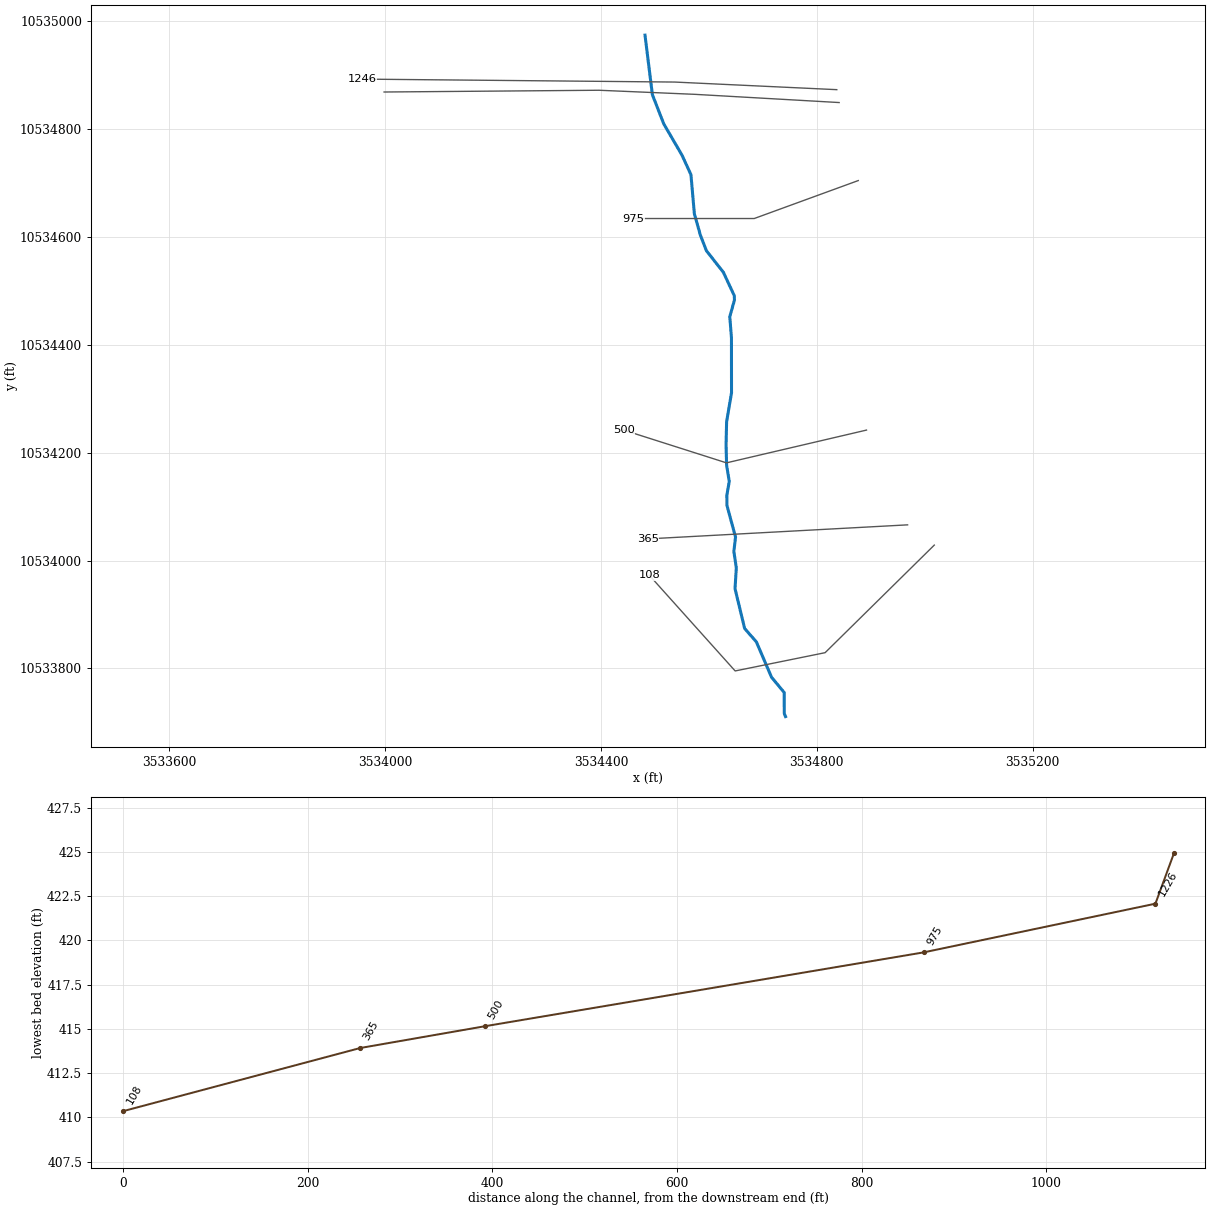
--- UNT8913 IN SAND CR.prj (project) ---

Proj Title=UNT8913 IN SAND CR Base Level Engineering
Current Plan=p01
Default Exp/Contr=0.3,0.1
English Units
Geom File=g01
Flow File=f01
Plan File=p01
Y Axis Title=Elevation
X Axis Title(PF)=Main Channel Distance
X Axis Title(XS)=Station
BEGIN DESCRIPTION:
UNT8913 IN SAND CR
END DESCRIPTION:
DSS Export Rating Curves= 0
DSS Export Rating Curve Sorted= 0
DSS Export Volume Flow Curves= 0
DXF OffsetX= 0
DXF OffsetY= 0
DXF ScaleX= 1
DXF ScaleY= 10

--- UNT8913 IN SAND CR.p01 (plan) ---

Plan Title=Multiple Run
Short Identifier=Multiple
Geom File=g01
Flow File=f01
Subcritical Flow
K Sum by GR= 0
Std Step Tol= 0.01
Critical Tol= 0.01
Num of Std Step Trials= 20
Max Error Tol= 0.3
Flow Tol Ratio= 0.001
Split Flow NTrial= 30
Split Flow Tol= 0.02
Split Flow Ratio= 0.02
Log Output Level= 0
Friction Slope Method= 1
Unsteady Friction Slope Method= 2
Unsteady Bridges Friction Slope Method= 1
Parabolic Critical Depth
Global Vel Dist=  1 , 1 , 1
Global Log Level= 0
CheckData=True
Encroach Param= -1, 0, 0, 0
BEGIN DESCRIPTION:
Multiple Run
END DESCRIPTION:

--- UNT8913 IN SAND CR.f01 (steady flow) ---

Flow Title=Multiple
Number of Profiles=7
Profile Names=10-year,25-year,50-year,1pct_min,100-year,1pct_plu,500-year
River Rch & RM= UNT8913 IN SAND ,Reach-1,1246
     161     196     222     184     249     337     312
Boundary for River Rch & Prof#=UNT8913 IN SAND ,Reach-1,1
Up Type=0
Dn Type=3
Dn Slope=0.005
Boundary for River Rch & Prof#=UNT8913 IN SAND ,Reach-1,2
Up Type=0
Dn Type=3
Dn Slope=0.005
Boundary for River Rch & Prof#=UNT8913 IN SAND ,Reach-1,3
Up Type=0
Dn Type=3
Dn Slope=0.005
Boundary for River Rch & Prof#=UNT8913 IN SAND ,Reach-1,4
Up Type=0
Dn Type=3
Dn Slope=0.005
Boundary for River Rch & Prof#=UNT8913 IN SAND ,Reach-1,5
Up Type=0
Dn Type=3
Dn Slope=0.005
Boundary for River Rch & Prof#=UNT8913 IN SAND ,Reach-1,6
Up Type=0
Dn Type=3
Dn Slope=0.005
Boundary for River Rch & Prof#=UNT8913 IN SAND ,Reach-1,7
Up Type=0
Dn Type=3
Dn Slope=0.005

--- UNT8913 IN SAND CR.g01 (geometry) ---

Geom Title=Existing Conditions
Program Version=4.10

River Reach=UNT8913 IN SAND ,Reach-1
Reach XY= 30
      3534481.73     10534973.34      3534495.43     10534863.01
      3534516.54      10534808.8      3534550.37     10534750.82
      3534566.84     10534714.86      3534573.22     10534642.18
      3534584.41     10534602.55      3534595.65     10534573.71
       3534626.9     10534534.05      3534647.13     10534490.68
      3534647.48     10534482.48       3534638.8     10534451.69
       3534641.9     10534412.65      3534642.03     10534310.77
      3534632.93     10534256.92      3534631.91     10534214.21
      3534632.94      10534176.3      3534637.85     10534146.57
       3534633.4     10534121.06      3534633.53     10534102.12
      3534649.49     10534043.45      3534646.37     10534016.62
      3534650.92      10533986.4      3534648.52     10533947.88
      3534666.35     10533874.05      3534688.01     10533849.31
      3534716.13     10533783.82      3534739.66     10533755.37
      3534739.79     10533716.57       3534742.1     10533710.86

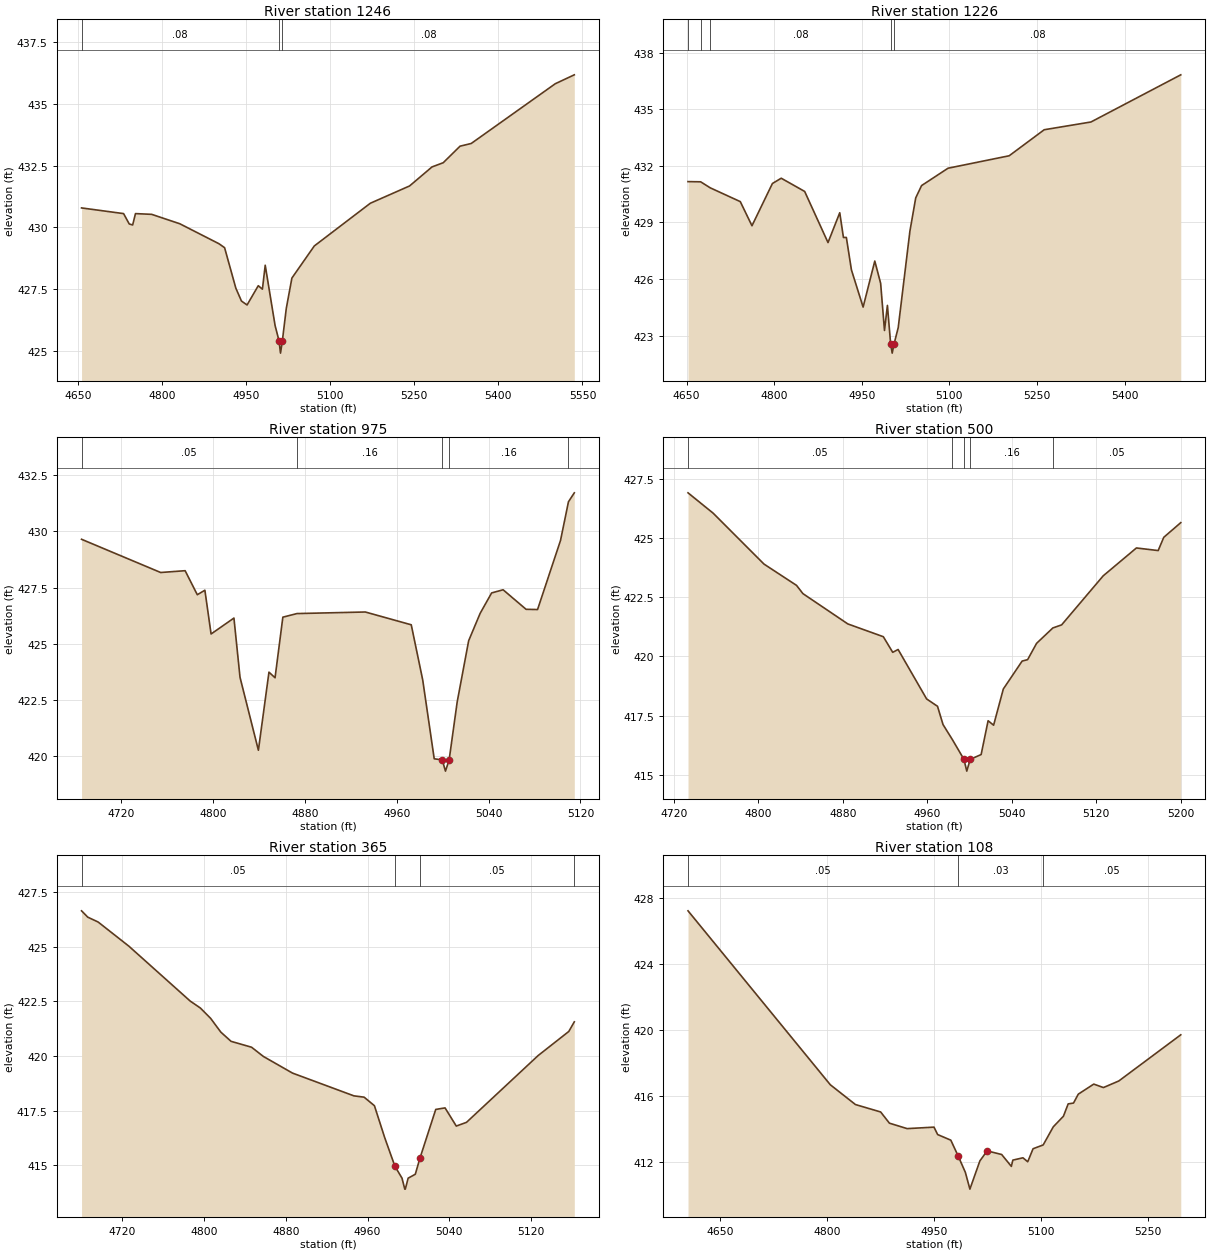
Type RM Length L Ch R = 1 ,1246    ,20,20,20
BEGIN DESCRIPTION:
UNT8913 IN SAND CR 2.0
END DESCRIPTION:
XS GIS Cut Line= 3
      3534837.07     10534872.31      3534536.55     10534886.41
      3533958.23     10534891.84
#Sta/Elev= 30
  4656.2  430.79  4731.2  430.56  4741.3  430.14  4747.4   430.1  4752.4  430.56
  4781.3  430.53  4831.4  430.15  4901.4  429.34  4911.4  429.18  4931.5  427.54
  4941.5  427.02  4951.5  426.86  4971.5  427.64  4978.9   427.5  4983.9  428.47
  5001.5  426.03  5008.5  425.41  5011.2  424.91  5014.5  425.41  5021.5  426.72
  5031.5  427.95  5071.5  429.25  5171.5  430.98  5241.5  431.68  5281.5  432.45
  5301.5  432.62  5331.5  433.29  5351.5   433.4  5501.5  435.82  5535.4  436.18
#Mann= 3 ,-1 , 0
  4656.2     .08       0  5008.5     .07       0  5014.5     .08       0
Bank Sta=5008.5,5014.5
XS Rating Curve= 0 ,0
Exp/Cntr=0.3,0.1

Type RM Length L Ch R = 1 ,1226    ,251,251,251
BEGIN DESCRIPTION:
UNT8913 IN SAND CR 2.1
END DESCRIPTION:
XS GIS Cut Line= 4
      3534841.45     10534848.44      3534574.53     10534863.63
      3534396.58     10534871.22      3533998.36     10534867.97
#Sta/Elev= 30
  4652.6  431.16  4674.2  431.15  4690.7  430.83  4742.1   430.1  4762.1  428.82
  4797.1  431.06  4812.2  431.34  4852.3  430.64  4892.3  427.93  4912.4  429.51
  4918.7   428.2  4923.7   428.2  4932.4  426.48  4952.4  424.51  4972.4  426.95
  4982.4  425.77    4989  423.27    4994   424.6  4999.5  422.57  5002.2  422.07
  5005.5  422.57  5012.5  423.42  5032.5  428.53  5042.5   430.3  5052.5  430.95
  5097.8  431.87  5202.5  432.53  5262.5  433.91  5342.5  434.32  5496.3  436.82
#Mann= 5 ,-1 , 0
  4652.6     .08       0  4674.2     .05       0  4690.7     .08       0
  4999.5     .07       0  5005.5     .08       0
Bank Sta=4999.5,5005.5
XS Rating Curve= 0 ,0
Exp/Cntr=0.3,0.1

Type RM Length L Ch R = 1 ,975     ,475,475,475
BEGIN DESCRIPTION:
UNT8913 IN SAND CR 2.2
END DESCRIPTION:
XS GIS Cut Line= 3
      3534876.82      10534703.9      3534684.12     10534633.59
      3534460.15     10534633.59
#Sta/Elev= 30
  4685.6  429.65  4754.5  428.17  4775.8  428.25  4786.4  427.18    4793  427.38
  4798.4  425.43  4818.3  426.14  4823.6   423.5  4839.6  420.25  4848.8  423.73
  4854.1  423.48  4860.9  426.18  4873.2  426.34  4932.7  426.41  4972.7  425.84
  4982.7  423.38  4992.7  419.87  4999.7  419.82  5002.5  419.32  5005.7  419.82
  5012.7   422.4  5022.7  425.13  5032.7  426.35  5042.7  427.26  5052.7   427.4
  5072.7  426.53  5082.7  426.52  5102.7   429.6  5109.6  431.32  5114.7  431.72
#Mann= 5 ,-1 , 0
  4685.6     .05       0  4873.2     .16       0  4999.7     .07       0
  5005.7     .16       0  5109.6     .05       0
Bank Sta=4999.7,5005.7
XS Rating Curve= 0 ,0
Exp/Cntr=0.3,0.1

Type RM Length L Ch R = 1 ,500     ,135,135,135
BEGIN DESCRIPTION:
UNT8913 IN SAND CR 1.0
END DESCRIPTION:
XS GIS Cut Line= 3
      3534892.11     10534241.64      3534632.62     10534180.93
      3534442.06     10534241.66
#Sta/Elev= 30
  4733.5  426.91  4757.3  426.05  4805.4   423.9  4836.2     423  4842.3  422.65
  4884.8  421.37  4918.4  420.83  4927.3  420.17  4932.4  420.29  4959.4   418.2
  4969.7  417.89  4974.9  417.12  4983.8  416.48  4994.7  415.65  4997.4  415.15
  5000.7  415.65    5011  415.85  5017.6  417.28  5022.8  417.09    5032  418.62
  5049.8   419.8    5055  419.86  5063.5  420.55  5078.9   421.2  5087.2  421.33
  5126.5   423.4    5158  424.58  5178.6  424.47  5183.9  425.03    5200  425.65
#Mann= 5 ,-1 , 0
  4733.5     .05       0  4983.8     .16       0  4994.7     .07       0
  5000.7     .16       0  5078.9     .05       0
Bank Sta=4994.7,5000.7
XS Rating Curve= 0 ,0
Exp/Cntr=0.3,0.1

Type RM Length L Ch R = 1 ,365     ,257,257,257
BEGIN DESCRIPTION:
UNT8913 IN SAND CR 1.2
END DESCRIPTION:
XS GIS Cut Line= 2
      3534968.24     10534066.06      3534486.74     10534040.03
#Sta/Elev= 30
  4680.1  426.63  4686.2  426.34  4696.3  426.12  4726.3  425.02  4786.4  422.51
  4796.4  422.19  4806.4  421.72  4816.4  421.09  4826.4  420.67  4846.5   420.4
    4858  419.98  4886.5  419.22  4946.6  418.18  4956.6  418.12  4966.7  417.73
  4976.7  416.28  4986.7  414.97  4993.7  414.42  4996.4  413.92  4996.9  413.92
  4999.7  414.42  5006.7   414.6 5011.14  415.32  5026.7  417.56  5035.8  417.63
  5046.8   416.8  5056.8  416.97  5126.9  420.02  5156.9  421.12  5162.3  421.56
#Mann= 4 ,-1 , 0
  4680.1     .05       0  4986.7     .03       0 5011.14     .05       0
  5162.3     .05       0
Bank Sta=4986.7,5011.14
XS Rating Curve= 0 ,0
Exp/Cntr=0.3,0.1

Type RM Length L Ch R = 1 ,108     ,0,0,0
BEGIN DESCRIPTION:
UNT8913 IN SAND CR 1.1
END DESCRIPTION:
XS GIS Cut Line= 4
      3535017.68     10534028.55      3534815.43     10533829.25
      3534648.76      10533795.4      3534489.92     10533972.47
#Sta/Elev= 30
  4604.8  427.23  4804.6  416.68  4839.9  415.48  4875.3  415.03  4887.6  414.35
  4912.5  414.02  4950.2  414.11  4955.3  413.66  4973.8  413.32    4984  412.37
  4994.2  411.37  5000.6  410.35  5014.6  412.06  5024.8  412.67  5045.2  412.45
  5058.8  411.73  5060.9  412.11  5075.1  412.25  5081.8  412.01  5089.3   412.8
  5103.5  413.03  5117.7  414.13  5131.9  414.77  5138.6  415.52  5146.1  415.57
  5152.8  416.11  5174.5  416.72  5188.1  416.51  5209.7  416.91  5296.7  419.71
#Mann= 3 ,-1 , 0
  4604.8     .05       0    4984     .03       0  5103.5     .05       0
Bank Sta=4984,5024.8
XS Rating Curve= 0 ,0
Exp/Cntr=0.3,0.1

Chan Stop Cuts=-1
Use User Specified Reach Order=0
Composite Channel Slope=5