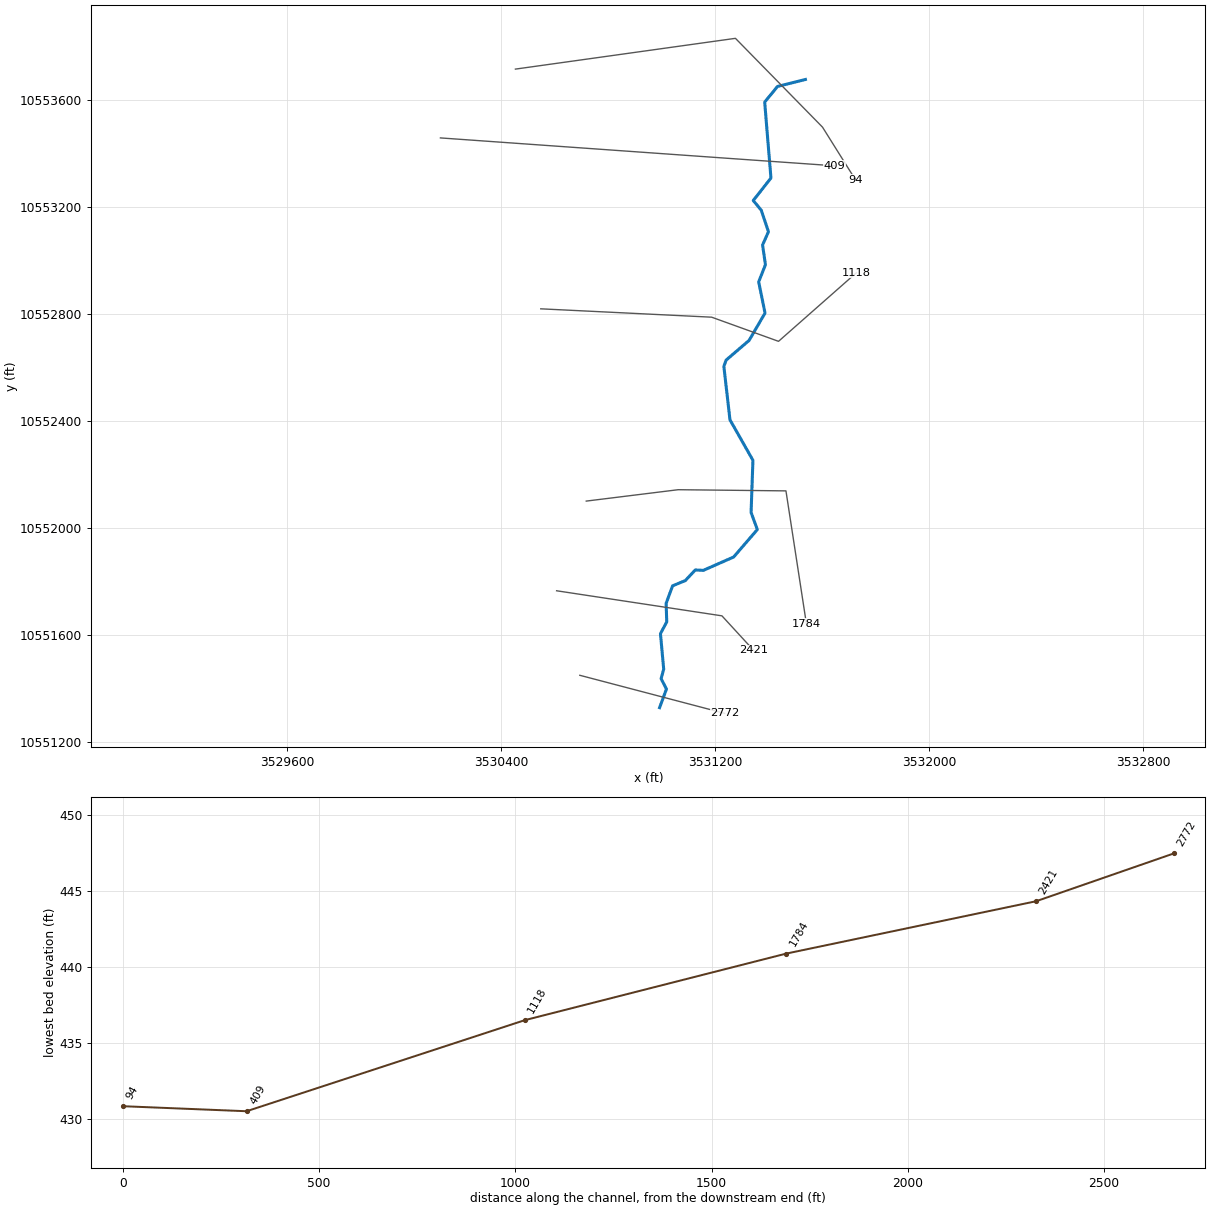
--- WFKCHAMBERSCREEK.prj (project) ---

Proj Title=W FK CHAMBERS CREEK
Current Plan=p01
Default Exp/Contr=0.3,0.1
English Units
Geom File=g01
Flow File=f01
Plan File=p01
Y Axis Title=Elevation
X Axis Title(PF)=Main Channel Distance
X Axis Title(XS)=Station
BEGIN DESCRIPTION:
UNT0633 IN SAND CR
END DESCRIPTION:
DSS Export Rating Curves= 0
DSS Export Rating Curve Sorted= 0
DSS Export Volume Flow Curves= 0
DXF OffsetX= 0
DXF OffsetY= 0
DXF ScaleX= 1
DXF ScaleY= 10

--- WFKCHAMBERSCREEK.p01 (plan) ---

Plan Title=Multiple Run
Short Identifier=Multiple
Geom File=g01
Flow File=f01
Subcritical Flow
K Sum by GR= 0
Std Step Tol= 0.01
Critical Tol= 0.01
Num of Std Step Trials= 20
Max Error Tol= 0.3
Flow Tol Ratio= 0.001
Split Flow NTrial= 30
Split Flow Tol= 0.02
Split Flow Ratio= 0.02
Log Output Level= 0
Friction Slope Method= 1
Unsteady Friction Slope Method= 2
Unsteady Bridges Friction Slope Method= 1
Parabolic Critical Depth
Global Vel Dist=  1 , 1 , 1
Global Log Level= 0
CheckData=True
Encroach Param= -1, 0, 0, 0
BEGIN DESCRIPTION:
Multiple Run
END DESCRIPTION:

--- WFKCHAMBERSCREEK.f01 (steady flow) ---

Flow Title=Multiple
Program Version=4.10
Number of Profiles= 7
Profile Names=10-year,25-year,50-year,1pct_min,100-year,1pct_plu,500-year
River Rch & RM=WFORKCHAMBERSCR,Reach-1         ,2772
     750    1011    1222    1079    1459    1973    2072
Boundary for River Rch & Prof#=WFORKCHAMBERSCR,Reach-1         , 1
Up Type= 0
Dn Type= 1
Dn Known WS=438.92
Boundary for River Rch & Prof#=WFORKCHAMBERSCR,Reach-1         , 2
Up Type= 0
Dn Type= 1
Dn Known WS=440.02
Boundary for River Rch & Prof#=WFORKCHAMBERSCR,Reach-1         , 3
Up Type= 0
Dn Type= 1
Dn Known WS=440.76
Boundary for River Rch & Prof#=WFORKCHAMBERSCR,Reach-1         , 4
Up Type= 0
Dn Type= 1
Dn Known WS=440.45
Boundary for River Rch & Prof#=WFORKCHAMBERSCR,Reach-1         , 5
Up Type= 0
Dn Type= 1
Dn Known WS=441.52
Boundary for River Rch & Prof#=WFORKCHAMBERSCR,Reach-1         , 6
Up Type= 0
Dn Type= 1
Dn Known WS=442.71
Boundary for River Rch & Prof#=WFORKCHAMBERSCR,Reach-1         , 7
Up Type= 0
Dn Type= 1
Dn Known WS=443.2
DSS Import GetInterval= 0
DSS Import GetPeak= 0
DSS Import FillOption= 0

--- WFKCHAMBERSCREEK.g01 (geometry) ---

Geom Title=Existing Conditions
Program Version=4.10

River Reach=WFORKCHAMBERSCR ,Reach-1
Reach XY= 30
      3530991.85     10551326.83      3531017.52     10551396.49
       3530997.6     10551435.26      3531007.22     10551470.87
      3530995.08     10551603.39      3531018.61     10551647.44
      3531016.31     10551716.54      3531040.44     10551782.35
      3531087.99     10551801.93       3531125.4     10551841.56
      3531155.38     10551840.14      3531268.68     10551890.02
      3531357.29     10551992.69      3531333.89     10552056.59
      3531340.81     10552251.56        3531255.     10552402.82
      3531232.09     10552602.61      3531240.66     10552626.14
      3531326.32     10552699.57      3531386.02     10552801.89
      3531362.31     10552918.79      3531387.57      10552982.5
      3531376.84     10553056.44      3531398.87     10553106.01
      3531371.82     10553186.58      3531341.97     10553222.64
      3531408.12     10553306.63      3531384.73     10553590.55
      3531432.74      10553649.1      3531537.07      10553675.1

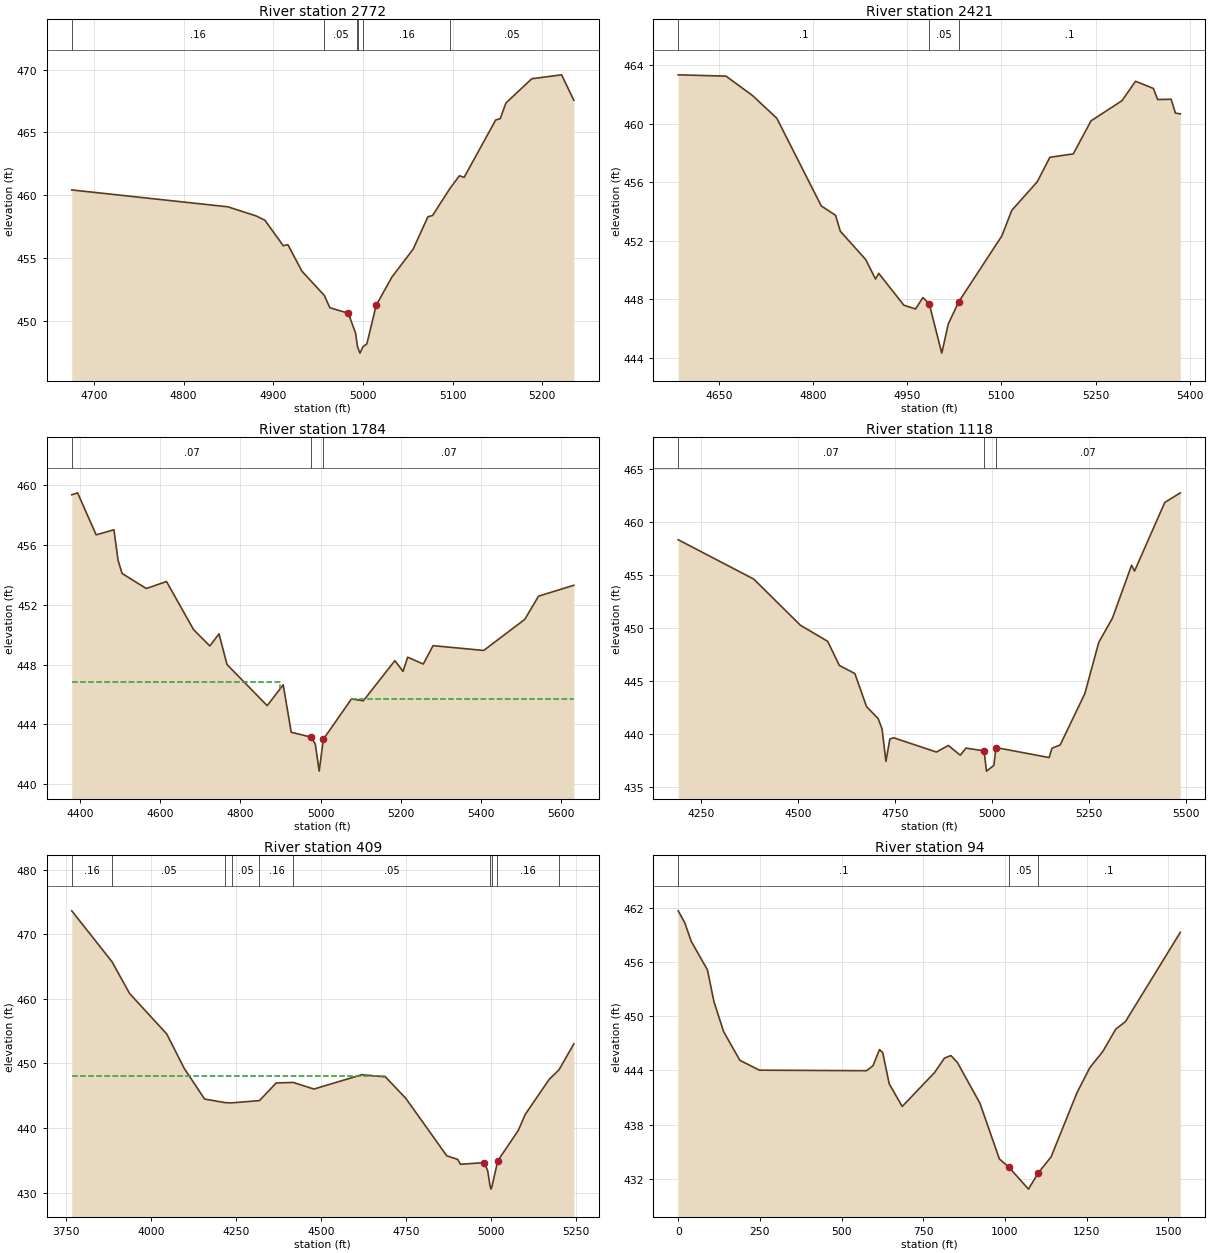
Type RM Length L Ch R = 1 ,2772    ,351,351,351
BEGIN DESCRIPTION:
UNT0633 IN SAND CR 6.0
END DESCRIPTION:
XS GIS Cut Line= 2
       3530693.7     10551447.87       3531235.4      10551305.5
#Sta/Elev= 30
  4675.2  460.43  4849.3  459.09  4881.1  458.36  4890.7  458.02  4911.1     456
  4916.3  456.08    4932  453.97    4957  452.04  4963.1  451.07  4983.7  450.63
  4991.8  449.05  4993.9  448.01    4994  447.96  4996.7  447.46    5000  447.96
  5004.4   448.2  5014.8  451.26  5032.2  453.49  5056.1  455.73  5072.5   458.3
  5077.7   458.4  5097.2  460.56  5107.7  461.56  5112.9  461.43  5148.1  465.99
  5153.2   466.1  5159.5  467.34  5188.4  469.27  5221.6  469.58  5235.3  467.56
#Mann= 6 ,-1 , 0
  4675.2     .16       0    4957     .05       0  4993.9     .16       0
    4994     .07       0    5000     .16       0  5097.2     .05       0
Bank Sta=4983.7,5014.8
XS Rating Curve= 0 ,0
Exp/Cntr=0.3,0.1

Type RM Length L Ch R = 1 ,2421    ,637,637,637
BEGIN DESCRIPTION:
UNT0633 IN SAND CR 6.1
END DESCRIPTION:
XS GIS Cut Line= 3
      3530606.89     10551763.84      3531224.94     10551670.09
        3531343.     10551541.61
#Sta/Elev= 30
  4585.4  463.36  4661.5  463.27  4703.5  461.95  4742.4  460.39  4813.2  454.39
    4836  453.75  4843.5  452.66    4884  450.72  4899.6  449.39  4904.7  449.78
  4944.7   447.6  4963.3  447.34    4975  448.12  4985.1   447.7  5005.1  444.32
  5015.5  446.32  5032.1  447.83  5100.8  452.34  5116.6  454.09  5157.1  456.04
  5177.3  457.72  5214.5  457.95  5242.8  460.21  5292.1  461.59  5313.7  462.92
  5342.1  462.43  5348.9  461.67  5370.4  461.69  5377.2  460.74    5385  460.69
#Mann= 3 , 0 , 0
  4585.4      .1       0  4985.1     .05       0  5032.1      .1       0
Bank Sta=4985.1,5032.1
XS Rating Curve= 0 ,0
Exp/Cntr=0.3,0.1

Type RM Length L Ch R = 1 ,1784    ,666,666,666
BEGIN DESCRIPTION:
UNT0633 IN SAND CR 4.0
END DESCRIPTION:
XS GIS Cut Line= 4
      3530717.69     10552099.06      3531061.48     10552141.64
      3531464.25     10552137.26      3531540.64     10551640.72
#Sta/Elev= 30
  4379.8  459.36  4394.3  459.49  4440.6  456.68    4485  457.02  4495.1  454.99
  4505.2   454.1  4565.6  453.09    4616  453.56  4683.5  450.34    4724  449.25
  4746.8  450.06  4766.8  448.01  4866.9  445.26  4906.9  446.65  4926.9  443.48
  4976.9  443.15  4986.9  442.68  4996.6  440.88  5006.9  443.01  5076.9   445.7
  5106.9  445.59  5185.3  448.27  5205.5  447.55  5217.1   448.5  5256.1  448.04
  5280.4  449.27  5406.8  448.95  5509.1  451.03  5543.4  452.58  5631.4  453.31
#Mann= 3 , 0 , 0
  4379.8     .07       0  4976.9     .03       0  5006.9     .07       0
#XS Ineff= 2 , 0
         4898.76  446.87 5076.74          445.71
Permanent Ineff=
       F       F
Bank Sta=4976.9,5006.9
XS Rating Curve= 0 ,0
Exp/Cntr=0.3,0.1

Type RM Length L Ch R = 1 ,1118    ,709,709,709
BEGIN DESCRIPTION:
UNT0633 IN SAND CR 3.0
END DESCRIPTION:
XS GIS Cut Line= 4
       3530547.6     10552817.81      3531186.48     10552786.56
      3531436.48     10552696.28      3531727.66      10552952.8
#Sta/Elev= 30
  4191.9  458.31  4386.6   454.6  4506.8  450.25  4576.9  448.74  4606.9  446.47
    4647   445.7    4677  442.59    4707  441.46    4717  440.49    4727  437.43
  4737.1  439.54  4747.1  439.65  4857.1  438.31  4887.8  438.93  4918.5  438.01
  4933.2  438.68  4979.8  438.42  4986.1  436.51  5005.1  437.05  5010.5  438.73
  5147.4  437.79  5154.9  438.67  5175.8  438.97  5239.4  443.81  5275.4  448.65
  5310.5  450.92  5359.9  455.91  5367.5  455.36  5445.3  461.82  5485.4  462.73
#Mann= 3 , 0 , 0
  4191.9     .07       0  4979.8     .03       0  5010.5     .07       0
Bank Sta=4979.8,5010.5
XS Rating Curve= 0 ,0
Exp/Cntr=0.3,0.1

Type RM Length L Ch R = 1 ,409     ,315,315,315
BEGIN DESCRIPTION:
UNT0633 IN SAND CR 1.0
END DESCRIPTION:
XS GIS Cut Line= 3
      3530172.54      10553456.7      3531248.98     10553380.31
      3531644.76     10553352.54
#Sta/Elev= 30
  3767.4  473.66  3885.7  465.77  3937.4  460.85  4046.7  454.57  4097.8  449.26
  4157.9  444.49  4218.7  443.93  4237.4   443.9  4319.2  444.25  4368.5  446.99
  4418.6  447.06  4479.2  446.04    4620  448.26  4689.3  447.93  4749.4   444.6
  4869.7   435.7  4901.9  435.14  4909.8  434.38    4980  434.64    4990  433.39
    4997  431.03  4999.8  430.53    5003  431.03  5017.2  434.34  5020.1  434.95
  5080.2  439.65  5100.3   442.1  5170.5  447.52  5199.5  449.01  5243.3  453.05
#Mann= 10 ,-1 , 0
  3767.4     .16       0  3885.7     .05       0  4218.7     .16       0
  4237.4     .05       0  4319.2     .16       0  4418.6     .05       0
    4997    .035       0    5003     .05       0  5017.2     .16       0
  5199.5     .05       0
#XS Ineff= 2 , 0
         4690.96  448.09
Permanent Ineff=
       F       F
Bank Sta=4980,5020.1
XS Rating Curve= 0 ,0
Exp/Cntr=0.3,0.1

Type RM Length L Ch R = 1 ,94      ,0,0,0
XS GIS Cut Line= 4
     3530452.907    10553713.936      3531275.39    10553828.953
     3531600.911    10553496.922     3531724.609     10553299.44
#Sta/Elev= 30
       0  461.67   19.87  460.36   39.74   458.3   89.41  455.13  109.28  451.62
  139.08  448.28  188.75  445.12  248.36  444.03  576.19  443.97  596.06  444.52
  615.93  446.31  625.87  445.98  645.73  442.52  685.47  440.01  784.82  443.78
  814.62  445.36  834.49  445.65  854.27  444.89  923.53  440.36  982.89   434.2
 1012.57  433.27 1071.93  430.86 1101.61  432.64 1141.18  434.43 1220.32  441.53
  1259.9  444.32 1299.47   446.1    1339  448.57 1368.65   449.4 1536.65  459.29
#Mann= 3 , 0 , 0
       0      .1       0 1012.57     .05       0 1101.61      .1       0
#XS Ineff= 2 , 0
          833.02  445.59
Permanent Ineff=
       F       F
Bank Sta=1012.57,1101.61
XS Rating Curve= 0 ,0
Exp/Cntr=0.3,0.1

Chan Stop Cuts=-1
Use User Specified Reach Order=0
Composite Channel Slope=5