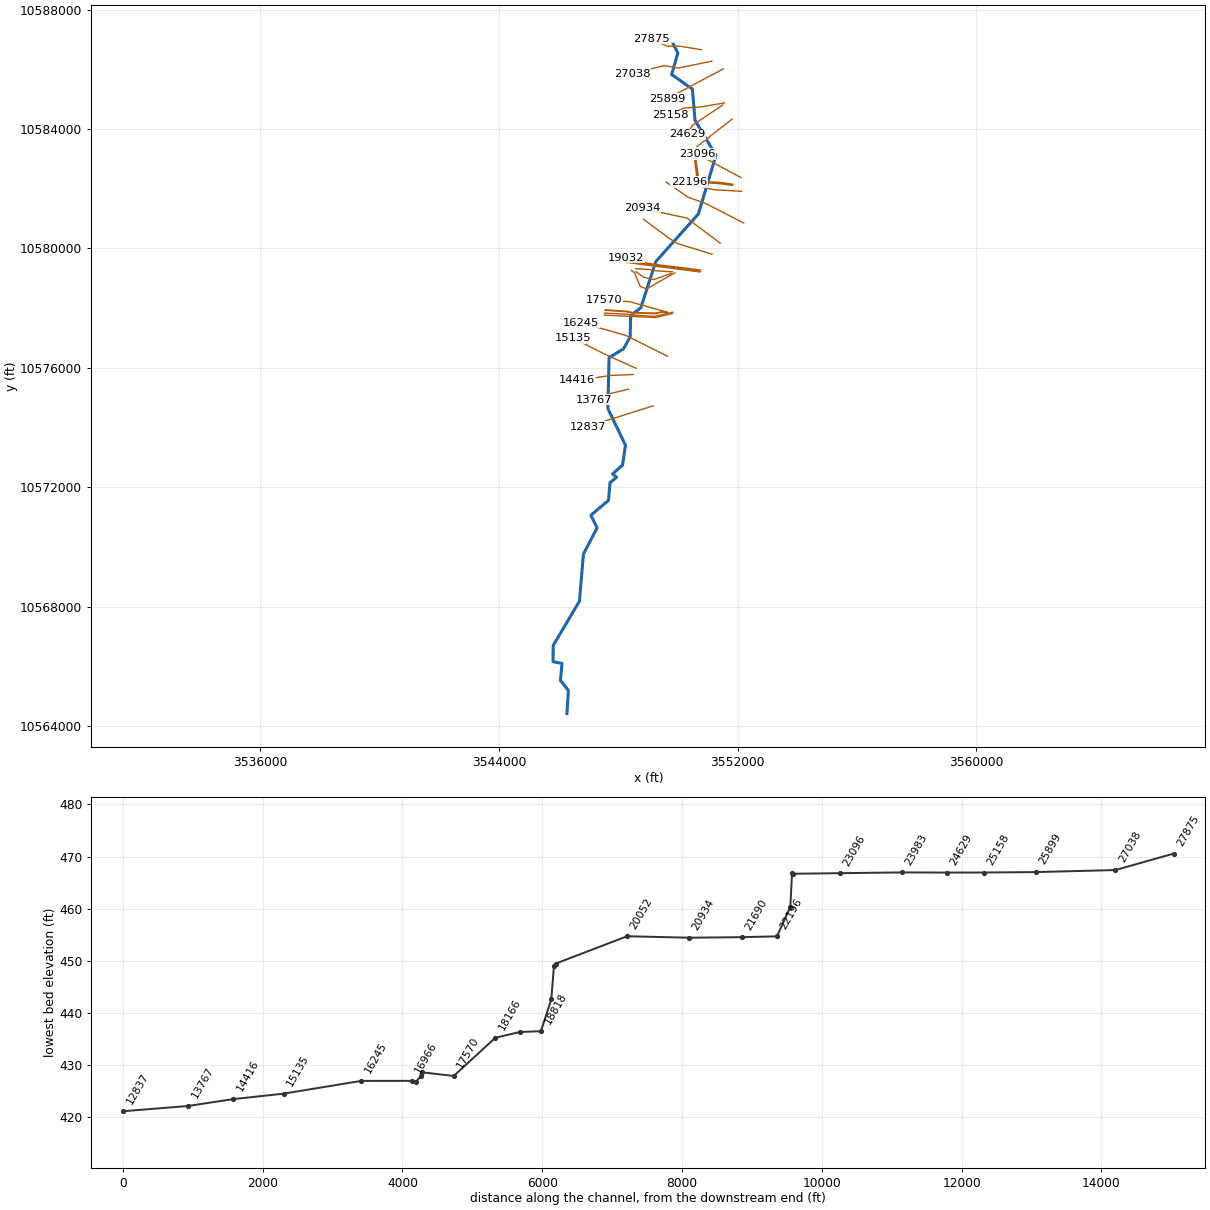
--- WHITE ROCK CREEK.prj (project) ---

Proj Title=WHITE ROCK CREEK Base Level Engineering
Current Plan=p01
Default Exp/Contr=0.3,0.1
English Units
Geom File=g01
Flow File=f01
Plan File=p01
BEGIN DESCRIPTION:
WHITE ROCK CREEK
END DESCRIPTION:

--- WHITE ROCK CREEK.p01 (plan) ---

Plan Title=Multiple Run
Short Identifier=Multiple
Geom File=g01
Flow File=f01
Subcritical Flow
K Sum by GR= 0
Std Step Tol= 0.01
Critical Tol= 0.01
Num of Std Step Trials= 20
Max Error Tol= 0.3
Flow Tol Ratio= 0.001
Split Flow NTrial= 30
Split Flow Tol= 0.02
Split Flow Ratio= 0.02
Log Output Level= 0
Friction Slope Method= 1
Unsteady Friction Slope Method= 2
Unsteady Bridges Friction Slope Method= 1
Parabolic Critical Depth
Global Vel Dist=  1 , 1 , 1
Global Log Level= 0
CheckData=True
Encroach Param= -1, 0, 0, 0
BEGIN DESCRIPTION:
Multiple Run
END DESCRIPTION:

--- WHITE ROCK CREEK.f01 (steady flow) ---

Flow Title=Multiple
Number of Profiles=7
Profile Names=10-year,25-year,50-year,1pct_min,100-year,1pct_plu,500-year
River Rch & RM= WHITE ROCK CREEK,Reach-1,27875
     751     999    1197    1046    1414    1913    1968
River Rch & RM= WHITE ROCK CREEK,Reach-1,23096
    1732    2422    2998    2702    3653    4941    5412
River Rch & RM= WHITE ROCK CREEK,Reach-1,17570
    2434    3465    4344    3959    5354    7240    8116
River Rch & RM= WHITE ROCK CREEK,Reach-1,17116
    2734    3886    4864    4422    5980    8088    9023
River Rch & RM= WHITE ROCK CREEK,Reach-1,6783
    2787    3965    4965    4517    6109    8262    9228
River Rch & RM= WHITE ROCK CREEK,Reach-1,4489
    3286    4704    5915    5401    7304    9878   11114
Boundary for River Rch & Prof#=WHITE ROCK CREEK,Reach-1,1
Up Type=0
Dn Type=3
Dn Slope=0.005
Boundary for River Rch & Prof#=WHITE ROCK CREEK,Reach-1,2
Up Type=0
Dn Type=3
Dn Slope=0.005
Boundary for River Rch & Prof#=WHITE ROCK CREEK,Reach-1,3
Up Type=0
Dn Type=3
Dn Slope=0.005
Boundary for River Rch & Prof#=WHITE ROCK CREEK,Reach-1,4
Up Type=0
Dn Type=3
Dn Slope=0.005
Boundary for River Rch & Prof#=WHITE ROCK CREEK,Reach-1,5
Up Type=0
Dn Type=3
Dn Slope=0.005
Boundary for River Rch & Prof#=WHITE ROCK CREEK,Reach-1,6
Up Type=0
Dn Type=3
Dn Slope=0.005
Boundary for River Rch & Prof#=WHITE ROCK CREEK,Reach-1,7
Up Type=0
Dn Type=3
Dn Slope=0.005

--- WHITE ROCK CREEK.g01 (geometry) ---

Geom Title=Existing Conditions

River Reach=WHITE ROCK CREEK,Reach-1
Reach XY= 30
      3549845.80     10586841.51      3549998.29     10586548.91
      3549787.31     10585826.53      3550485.53     10585336.97
      3550571.36     10584296.87      3551271.88     10583118.05
      3550683.59     10581154.23      3549257.37     10579560.48
      3548755.83     10578014.50      3548417.38     10577753.98
      3548398.84     10577042.99      3548177.95     10576639.57
      3547692.34     10576346.60      3547652.11     10574641.68
      3548241.48     10573411.18      3548145.75     10572748.18
      3547808.29     10572447.62      3547945.01     10572339.11
      3547723.77     10572155.53      3547674.21     10571565.36
      3547083.12     10571066.98      3547291.45     10570641.45
      3546833.62     10569765.86      3546700.14     10568187.61
      3545822.39     10566707.40      3545815.40     10566163.09
      3546117.00     10566103.92      3546064.36     10565537.12
      3546330.39     10565196.06      3546281.51     10564426.40

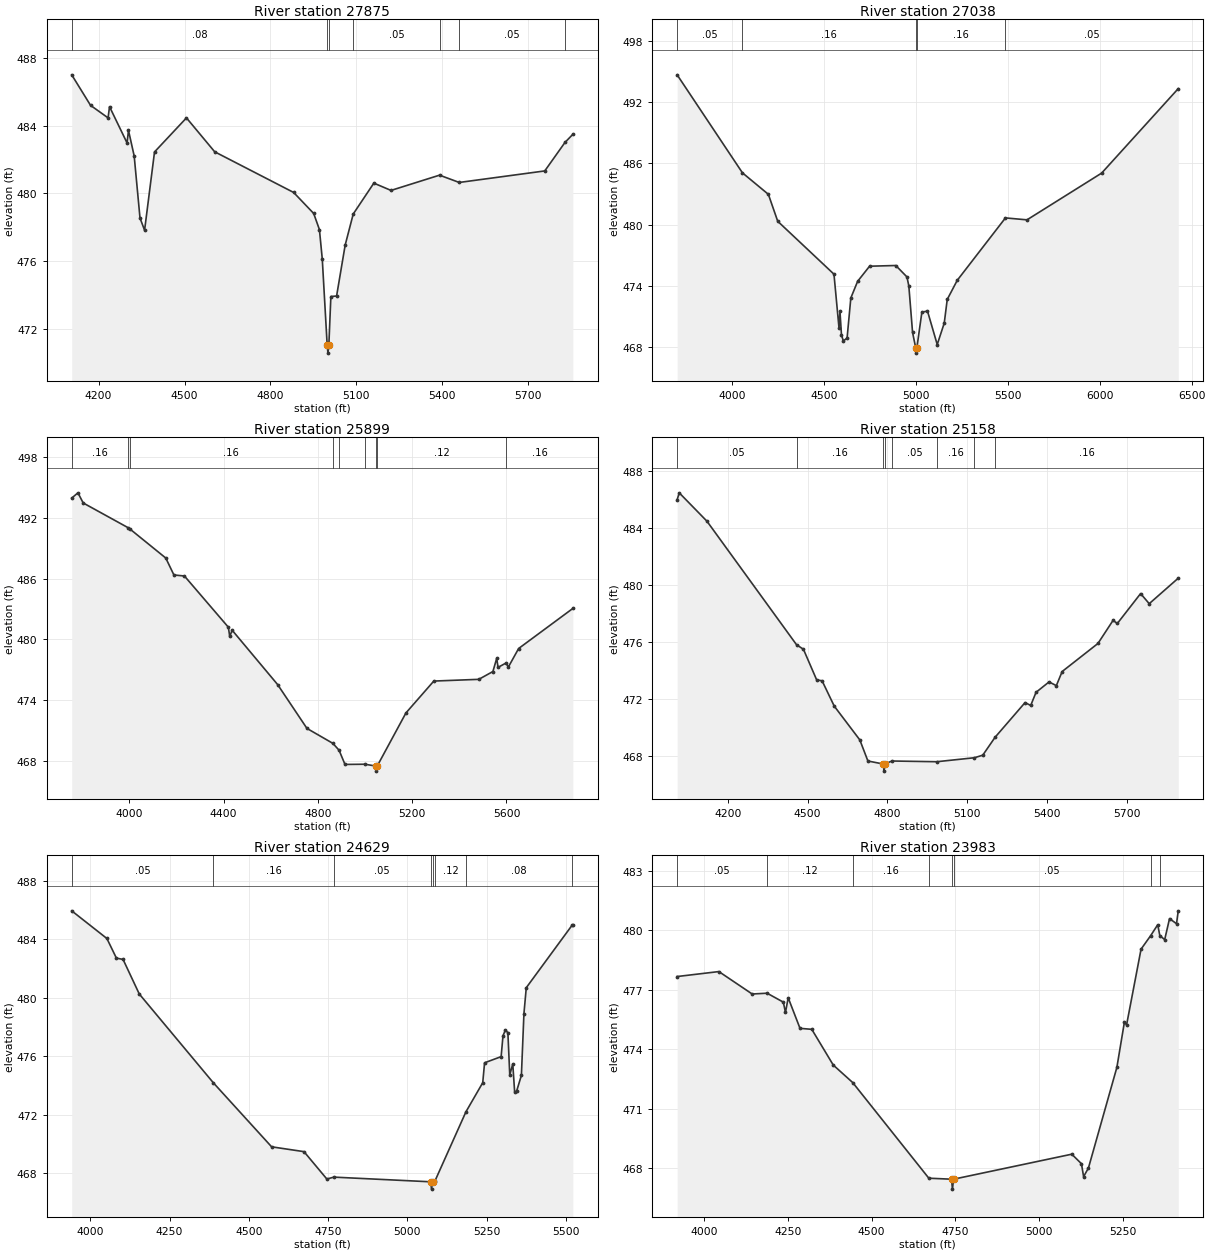
Type RM Length L Ch R = 1,27875,837,837,837
BEGIN DESCRIPTION:
WHITE ROCK CREEK 47.0
END DESCRIPTION:
XS GIS Cut Line= 4
      3550787.35     10586655.20      3550075.52     10586772.40
      3549641.49     10586772.40      3549103.30     10587024.13
#Sta/Elev= 30
  4106.2  487.00  4171.9  485.20  4233.1  484.46  4238.2  485.12  4299.4  482.98
  4304.4  483.72  4324.3  482.21  4344.6  478.55  4360.6  477.83  4395.3  482.45
  4506.8  484.46  4605.3  482.46  4881.0  480.06  4951.0  478.82  4971.0  477.87
  4981.0  476.13  4998.0  471.08  5000.8  470.58  5004.0  471.08  5011.0  473.92
  5031.0  473.95  5061.0  476.96  5089.1  478.79  5161.0  480.61  5221.0  480.18
  5390.4  481.08  5459.2  480.65  5757.8  481.33  5828.3  483.01  5855.8  483.49
#Mann=7,-1,0
  4106.2    0.08       0  4998.0    0.07       0  5004.0    0.08       0
  5089.1    0.05       0  5390.4    0.08       0  5459.2    0.05       0
  5828.3    0.08       0
Bank Sta=4998,5004
Exp/Cntr=0.3,0.1

Type RM Length L Ch R = 1,27038,1139,1139,1139
BEGIN DESCRIPTION:
WHITE ROCK CREEK 46.0
END DESCRIPTION:
XS GIS Cut Line= 4
      3551138.90     10586272.46      3550006.07     10586042.42
      3549532.98     10586124.89      3548475.53     10585851.86
#Sta/Elev= 30
  3698.8  494.66  4054.5  485.06  4195.5  482.96  4246.5  480.32  4552.7  475.14
  4580.2  469.85  4585.3  471.52  4593.5  469.19  4603.7  468.61  4624.1  468.88
  4644.5  472.81  4681.5  474.44  4746.5  475.92  4889.2  475.99  4950.1  474.87
  4960.3  473.98  4980.6  469.44  4997.9  467.91  5000.6  467.41  5003.9  467.91
  5031.3  471.42  5061.8  471.53  5114.9  468.25  5153.1  470.35  5169.4  472.67
  5223.9  474.54  5486.3  480.65  5603.6  480.46  6010.2  485.04  6427.1  493.31
#Mann=5,-1,0
  3698.8    0.05       0  4054.5    0.16       0  4997.9    0.07       0
  5003.9    0.16       0  5486.3    0.05       0
Bank Sta=4997.9,5003.9
Exp/Cntr=0.3,0.1

Type RM Length L Ch R = 1,25899,741,741,741
BEGIN DESCRIPTION:
WHITE ROCK CREEK 44.0
END DESCRIPTION:
XS GIS Cut Line= 4
      3551525.19     10586016.40      3550561.62     10585508.57
      3550127.59     10585274.19      3549650.16     10585013.78
#Sta/Elev= 30
  3755.4  493.94  3781.7  494.46  3804.1  493.46  3994.0  491.03  4001.5  490.91
  4154.5  488.03  4189.0  486.36  4233.6  486.26  4420.0  481.21  4425.8  480.31
  4436.3  480.91  4628.9  475.56  4753.6  471.23  4863.4  469.76  4889.8  469.08
  4914.9  467.68  4999.9  467.70  5045.6  467.52  5048.4  467.02  5051.6  467.52
  5173.6  472.76  5291.8  475.90  5482.7  476.07  5542.5  476.84  5558.7  478.14
  5564.4  477.25  5598.2  477.68  5608.0  477.28  5651.7  479.11  5881.7  483.06
#Mann=9,-1,0
  3755.4    0.16       0  3994.0    0.05       0  4001.5    0.16       0
  4863.4    0.12       0  4889.8    0.16       0  4999.9    0.12       0
  5045.6    0.07       0  5051.6    0.12       0  5598.2    0.16       0
Bank Sta=5045.6,5051.6
Exp/Cntr=0.3,0.1

Type RM Length L Ch R = 1,25158,529,529,529
BEGIN DESCRIPTION:
WHITE ROCK CREEK 42.0
END DESCRIPTION:
XS GIS Cut Line= 4
      3551559.85     10584874.88      3550761.27     10584740.34
      3550179.68     10584701.28      3549746.35     10584467.28
#Sta/Elev= 30
  4009.0  485.98  4016.9  486.47  4121.1  484.48  4458.2  475.81  4484.2  475.49
  4534.0  473.34  4554.3  473.28  4600.1  471.50  4696.3  469.13  4726.7  467.65
  4784.6  467.44  4787.3  466.94  4790.6  467.44  4816.9  467.65  4985.7  467.60
  5127.6  467.88  5158.8  468.06  5205.3  469.32  5317.9  471.75  5339.2  471.55
  5359.2  472.47  5408.1  473.20  5435.6  472.94  5457.5  473.93  5592.2  475.90
  5649.0  477.52  5665.0  477.30  5752.6  479.40  5785.0  478.69  5894.2  480.48
#Mann=8,-1,0
  4009.0    0.05       0  4458.2    0.16       0  4784.6    0.07       0
  4790.6    0.16       0  4816.9    0.05       0  4985.7    0.16       0
  5127.6    0.12       0  5205.3    0.16       0
Bank Sta=4784.6,4790.6
Exp/Cntr=0.3,0.1

Type RM Length L Ch R = 1,24629,646,646,646
BEGIN DESCRIPTION:
WHITE ROCK CREEK 41.1
END DESCRIPTION:
XS GIS Cut Line= 3
      3551503.49     10584805.46      3550489.19     10584126.97
      3550301.20     10583820.20
#Sta/Elev= 30
  3941.5  485.94  4052.4  484.05  4082.4  482.71  4103.4  482.62  4154.5  480.26
  4388.2  474.19  4571.8  469.82  4673.9  469.49  4746.0  467.62  4768.0  467.75
  5073.3  467.43  5076.0  466.93  5079.3  467.43  5086.7  467.48  5184.5  472.21
  5237.5  474.20  5243.3  475.56  5295.5  475.98  5301.4  477.41  5308.8  477.79
  5316.8  477.62  5322.7  474.73  5332.2  475.48  5338.1  473.57  5344.0  473.60
  5359.4  474.70  5367.4  478.92  5374.8  480.69  5518.7  484.94  5521.6  484.94
#Mann=8,-1,0
  3941.5    0.05       0  4388.2    0.16       0  4768.0    0.05       0
  5073.3   0.033       0  5079.3    0.05       0  5086.7    0.12       0
  5184.5    0.08       0  5518.7    0.05       0
Bank Sta=5073.3,5079.3
Exp/Cntr=0.3,0.1

Type RM Length L Ch R = 1,23983,887,887,887
BEGIN DESCRIPTION:
WHITE ROCK CREEK 39.0
END DESCRIPTION:
XS GIS Cut Line= 2
      3551814.94     10584333.80      3550635.74     10583411.25
#Sta/Elev= 30
  3918.9  477.67  4043.6  477.92  4143.1  476.79  4187.7  476.83  4236.2  476.38
  4242.6  475.86  4250.7  476.60  4286.0  475.06  4321.2  475.01  4385.4  473.21
  4443.4  472.33  4670.9  467.51  4738.7  467.46  4741.5  466.96  4744.7  467.46
  5098.0  468.72  5126.9  468.24  5133.3  467.59  5147.7  468.02  5232.7  473.09
  5255.3  475.38  5261.7  475.23  5305.0  479.05  5333.7  479.73  5354.8  480.28
  5361.1  479.73  5375.6  479.53  5390.1  480.59  5410.9  480.33  5416.1  480.98
#Mann=8,-1,0
  3918.9    0.05       0  4187.7    0.12       0  4443.4    0.16       0
  4670.9    0.05       0  4738.7   0.033       0  4744.7    0.05       0
  5333.7    0.08       0  5361.1     0.1       0
Bank Sta=4738.7,4744.7
Exp/Cntr=0.3,0.1

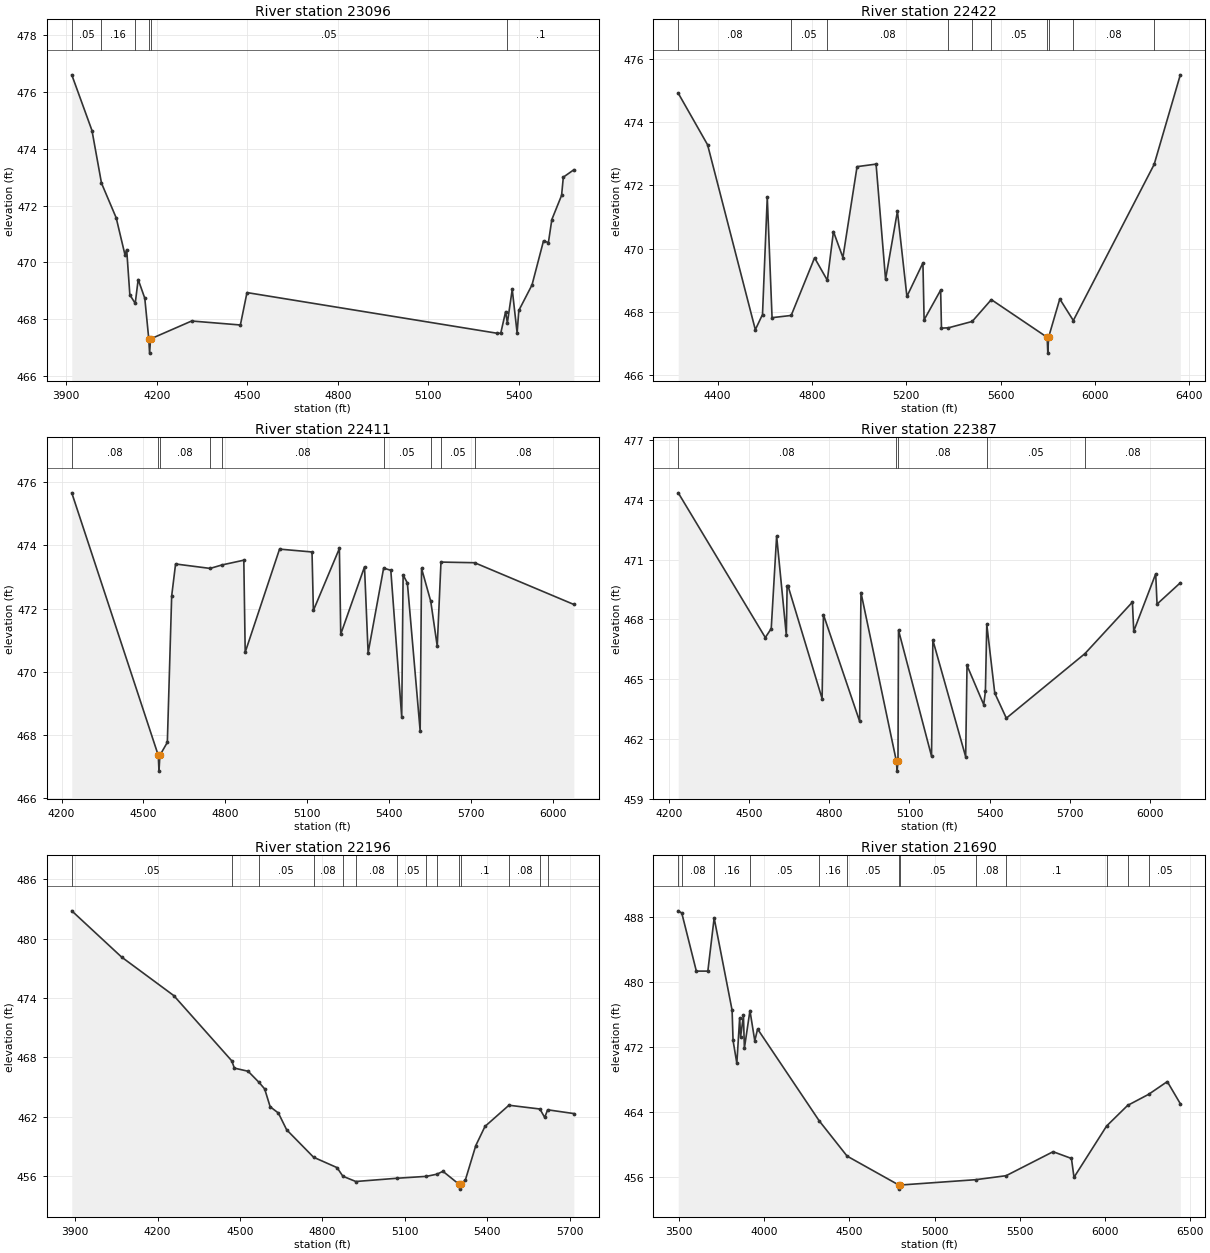
Type RM Length L Ch R = 1,23096,674,674,674
BEGIN DESCRIPTION:
WHITE ROCK CREEK 39.1
END DESCRIPTION:
XS GIS Cut Line= 2
      3552111.58     10582372.40      3550647.98     10583164.09
#Sta/Elev= 30
  3918.1  476.60  3985.1  474.64  4016.6  472.79  4065.3  471.57  4094.4  470.27
  4100.1  470.45  4110.6  468.86  4128.4  468.56  4138.2  469.40  4160.1  468.74
  4173.3  467.31  4176.0  466.81  4179.3  467.31  4315.4  467.94  4476.9  467.80
  4498.8  468.94  5327.3  467.51  5339.8  467.51  5356.0  468.27  5361.7  467.87
  5377.9  469.05  5394.1  467.52  5399.7  468.31  5443.5  469.21  5481.6  470.76
  5497.8  470.70  5509.2  471.51  5541.5  472.36  5547.2  473.00  5582.1  473.26
#Mann=6,-1,0
  3918.1    0.05       0  4016.6    0.16       0  4128.4    0.05       0
  4173.3   0.033       0  4179.3    0.05       0  5361.7     0.1       0
Bank Sta=4173.3,4179.3
Exp/Cntr=0.3,0.1

Type RM Length L Ch R = 1,22422,11,11,11
BEGIN DESCRIPTION:
WHITE ROCK CREEK 38.3
END DESCRIPTION:
XS GIS Cut Line= 6
      3551835.04     10582149.92      3551434.01     10582212.42
      3551096.33     10582224.57      3550730.02     10582264.50
      3550696.16     10582299.23      3550559.46     10583256.70
#Sta/Elev= 30
  4233.2  474.91  4357.6  473.28  4560.0  467.44  4590.4  467.92  4610.6  471.63
  4630.9  467.82  4712.0  467.89  4811.1  469.71  4865.2  469.00  4891.1  470.54
  4931.2  469.72  4991.2  472.59  5071.8  472.67  5112.0  469.03  5162.3  471.18
  5202.5  468.49  5270.4  469.55  5275.4  467.75  5345.5  468.69  5349.0  467.49
  5378.7  467.50  5479.2  467.70  5560.3  468.39  5797.0  467.20  5799.8  466.70
  5803.0  467.20  5850.5  468.41  5907.9  467.73  6250.5  472.66  6361.4  475.49
#Mann=10,-1,0
  4233.2    0.08       0  4712.0    0.05       0  4865.2    0.08       0
  5378.7    0.05       0  5479.2    0.08       0  5560.3    0.05       0
  5797.0    0.07       0  5803.0    0.05       0  5907.9    0.08       0
  6250.5    0.05       0
Bank Sta=5797,5803
Exp/Cntr=0.3,0.1

Type RM Length L Ch R = 1,22411,24,24,24
BEGIN DESCRIPTION:
WHITE ROCK CREEK 38.1
END DESCRIPTION:
XS GIS Cut Line= 6
      3551828.85     10582134.56      3551447.31     10582189.25
      3551037.16     10582217.90      3550725.96     10582249.15
      3550686.90     10582263.47      3550579.87     10582944.45
#Sta/Elev= 30
  4237.3  475.66  4554.3  467.36  4557.0  466.86  4560.3  467.36  4587.6  467.77
  4603.5  472.40  4617.8  473.41  4744.4  473.27  4788.1  473.38  4867.9  473.53
  4873.0  470.62  4998.9  473.88  5117.9  473.79  5122.9  471.94  5218.2  473.90
  5223.2  471.19  5310.3  473.32  5323.5  470.60  5380.4  473.28  5406.7  473.21
  5446.7  468.57  5451.8  473.06  5467.4  472.81  5514.3  468.13  5519.4  473.27
  5553.1  472.23  5576.9  470.81  5590.6  473.47  5713.9  473.45  6077.6  472.13
#Mann=9,-1,0
  4237.3    0.08       0  4554.3    0.07       0  4560.3    0.08       0
  4744.4    0.05       0  4788.1    0.08       0  5380.4    0.05       0
  5553.1    0.08       0  5590.6    0.05       0  5713.9    0.08       0
Bank Sta=4554.3,4560.3
Exp/Cntr=0.3,0.1

Type RM Length L Ch R = 1,22387,191,191,191
BEGIN DESCRIPTION:
WHITE ROCK CREEK 38.2
END DESCRIPTION:
XS GIS Cut Line= 6
      3551827.21     10582113.74      3551421.29     10582167.13
      3550992.82     10582197.69      3550689.34     10582221.99
      3550648.37     10582243.52      3550566.14     10582928.19
#Sta/Elev= 30
  4234.4  474.36  4560.3  467.09  4582.5  467.54  4602.7  472.19  4639.0  467.21
  4641.9  469.66  4645.9  469.66  4772.9  464.02  4777.9  468.24  4913.4  462.88
  4918.4  469.35  5050.9  460.88  5053.6  460.38  5056.9  460.88  5058.9  467.46
  5182.5  461.13  5187.5  466.96  5310.3  461.10  5315.3  465.69  5377.8  463.72
  5384.1  464.38  5389.3  467.75  5419.2  464.30  5462.5  463.04  5756.5  466.28
  5934.4  468.87  5939.4  467.41  6021.6  470.29  6026.6  468.77  6113.7  469.84
#Mann=5,-1,0
  4234.4    0.08       0  5050.9    0.07       0  5056.9    0.08       0
  5389.3    0.05       0  5756.5    0.08       0
Bank Sta=5050.9,5056.9
Exp/Cntr=0.3,0.1

Type RM Length L Ch R = 1,22196,506,506,506
BEGIN DESCRIPTION:
WHITE ROCK CREEK 38.0
END DESCRIPTION:
XS GIS Cut Line= 4
      3552132.84     10581914.82      3551221.34     10581966.90
      3550483.50     10582114.47      3550367.05     10582226.60
#Sta/Elev= 30
  3887.8  482.80  4068.8  478.14  4259.1  474.24  4469.9  467.66  4479.5  466.92
  4529.6  466.60  4569.2  465.48  4589.7  464.82  4609.7  463.02  4639.8  462.38
  4669.8  460.69  4767.8  457.92  4853.3  456.87  4874.4  456.00  4921.5  455.47
  5072.0  455.80  5178.6  455.99  5216.9  456.21  5238.5  456.50  5296.7  455.20
  5299.5  454.70  5302.7  455.20  5320.1  455.62  5358.1  459.10  5391.5  461.03
  5478.7  463.17  5591.3  462.79  5608.9  461.94  5619.5  462.71  5714.9  462.33
#Mann=14,-1,0
  3887.8    0.05       0  4469.9    0.08       0  4569.2    0.05       0
  4767.8    0.08       0  4874.4    0.05       0  4921.5    0.08       0
  5072.0    0.05       0  5178.6    0.08       0  5216.9     0.1       0
  5296.7    0.07       0  5302.7     0.1       0  5478.7    0.08       0
  5591.3    0.05       0  5619.5    0.08       0
Bank Sta=5296.7,5302.7
Exp/Cntr=0.3,0.1

Type RM Length L Ch R = 1,21690,756,756,756
BEGIN DESCRIPTION:
WHITE ROCK CREEK 37.0
END DESCRIPTION:
XS GIS Cut Line= 4
      3552206.55     10580851.47      3550973.95     10581485.13
      3550340.27     10581719.51      3549611.24     10582217.76
#Sta/Elev= 30
  3495.9  488.75  3516.8  488.47  3602.1  481.34  3669.6  481.34  3706.5  487.87
  3811.8  476.53  3817.4  472.82  3839.6  470.00  3856.1  475.58  3861.7  473.27
  3878.3  475.90  3883.9  471.86  3916.5  476.49  3944.8  472.77  3961.4  474.22
  4322.9  462.93  4486.2  458.60  4790.0  455.04  4792.7  454.54  4796.0  455.04
  5240.5  455.70  5418.8  456.19  5694.4  459.14  5802.0  458.31  5817.0  455.99
  6008.3  462.30  6131.4  464.83  6254.5  466.19  6364.2  467.76  6440.5  465.04
#Mann=13,-1,0
  3495.9    0.05       0  3516.8    0.08       0  3706.5    0.16       0
  3916.5    0.05       0  4322.9    0.16       0  4486.2    0.05       0
  4790.0   0.033       0  4796.0    0.05       0  5240.5    0.08       0
  5418.8     0.1       0  6008.3    0.05       0  6131.4    0.16       0
  6254.5    0.05       0
Bank Sta=4790,4796
Exp/Cntr=0.3,0.1

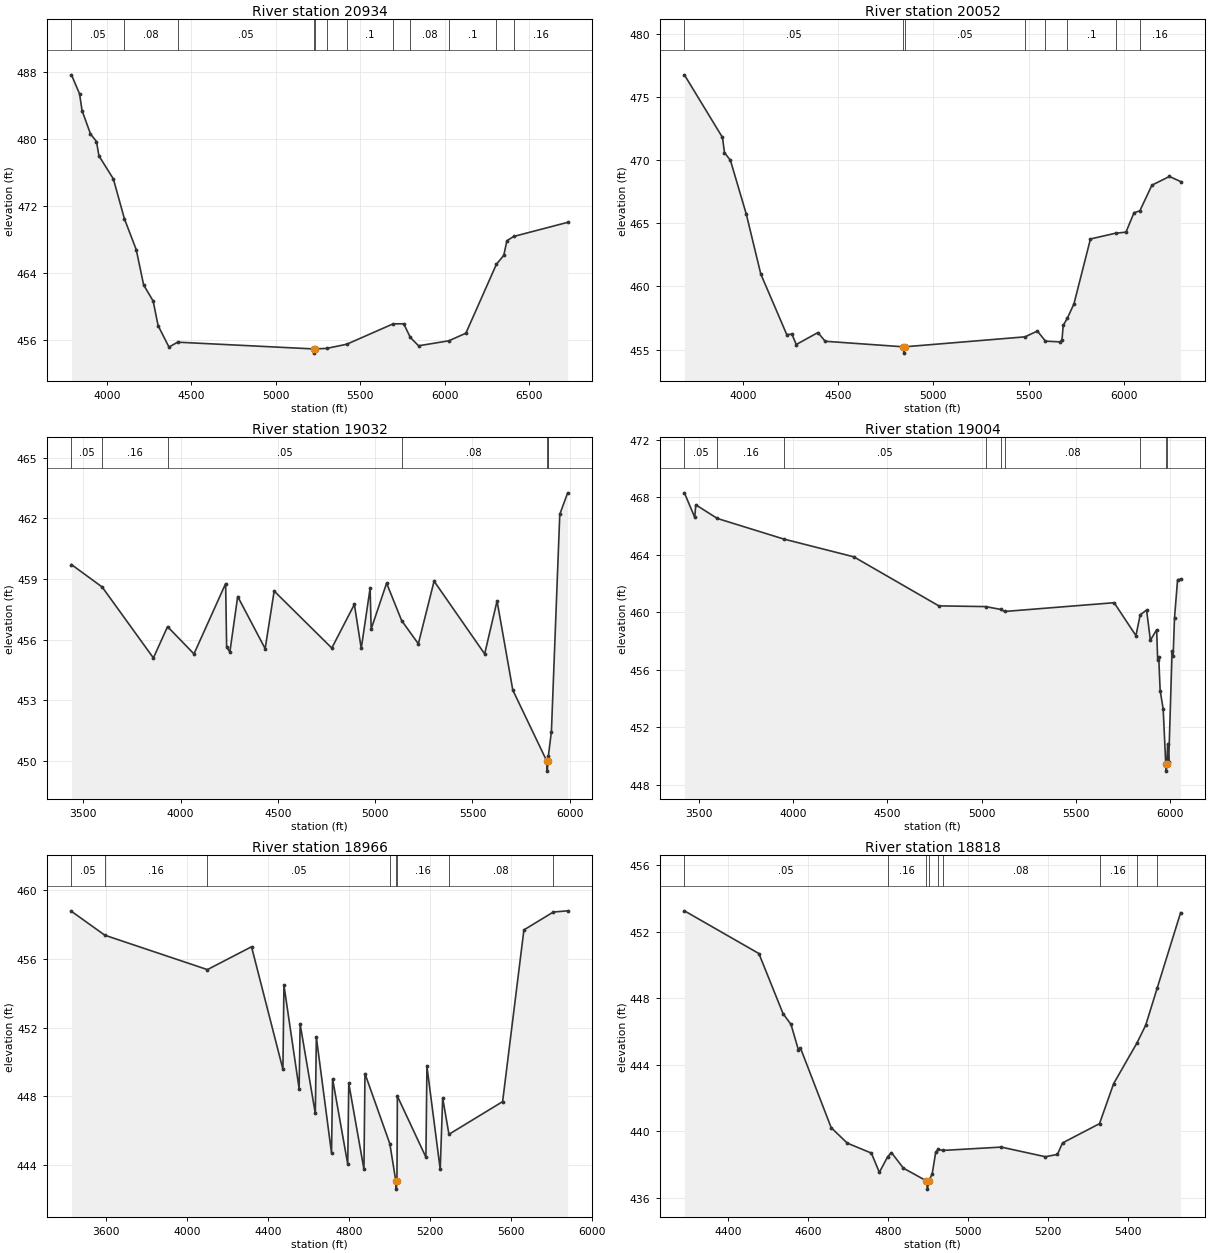
Type RM Length L Ch R = 1,20934,882,882,882
BEGIN DESCRIPTION:
WHITE ROCK CREEK 35.0
END DESCRIPTION:
XS GIS Cut Line= 4
      3551416.64     10580178.72      3550552.94     10580821.07
      3550309.88     10581016.38      3548792.13     10581341.64
#Sta/Elev= 30
  3788.8  487.72  3836.8  485.44  3851.4  483.45  3901.5  480.65  3936.9  479.74
  3951.6  478.03  4037.1  475.27  4102.6  470.50  4172.6  466.81  4216.5  462.59
  4272.8  460.67  4302.0  457.74  4366.6  455.16  4417.6  455.75  5225.5  454.94
  5228.2  454.44  5231.5  454.94  5301.9  455.01  5419.6  455.50  5694.6  457.94
  5757.7  457.95  5796.6  456.32  5845.5  455.32  6024.4  455.91  6125.8  456.82
  6306.7  465.06  6350.8  466.14  6368.7  467.87  6408.7  468.39  6729.2  470.08
#Mann=12,-1,0
  3788.8    0.05       0  4102.6    0.08       0  4417.6    0.05       0
  5225.5   0.033       0  5231.5    0.05       0  5301.9    0.08       0
  5419.6     0.1       0  5694.6    0.05       0  5796.6    0.08       0
  6024.4     0.1       0  6306.7    0.05       0  6408.7    0.16       0
Bank Sta=5225.5,5231.5
Exp/Cntr=0.3,0.1

Type RM Length L Ch R = 1,20052,1020,1020,1020
BEGIN DESCRIPTION:
WHITE ROCK CREEK 33.0
END DESCRIPTION:
XS GIS Cut Line= 4
      3551143.25     10579809.78      3549966.43     10580170.92
      3549711.06     10580337.25      3548851.56     10580972.97
#Sta/Elev= 30
  3692.7  476.76  3892.6  471.80  3903.1  470.60  3934.5  469.98  4017.9  465.71
  4093.8  460.98  4230.0  456.19  4257.5  456.22  4279.7  455.40  4393.7  456.35
  4431.6  455.66  4842.3  455.22  4845.1  454.72  4848.3  455.22  5481.1  456.01
  5545.6  456.47  5588.1  455.67  5666.7  455.61  5674.9  455.79  5681.3  456.92
  5703.4  457.50  5737.6  458.62  5824.2  463.76  5956.9  464.22  6010.7  464.30
  6052.9  465.84  6083.6  465.99  6146.8  468.02  6238.6  468.71  6297.5  468.31
#Mann=8,-1,0
  3692.7    0.05       0  4842.3   0.033       0  4848.3    0.05       0
  5481.1    0.08       0  5588.1    0.05       0  5703.4     0.1       0
  5956.9    0.05       0  6083.6    0.16       0
Bank Sta=4842.3,4848.3
Exp/Cntr=0.3,0.1

Type RM Length L Ch R = 1,19032,28,28,28
BEGIN DESCRIPTION:
WHITE ROCK CREEK 32.0
END DESCRIPTION:
XS GIS Cut Line= 5
      3550759.91     10579279.88      3549236.46     10579466.52
      3549149.65     10579481.71      3548344.53     10579603.24
      3548272.94     10579690.01
#Sta/Elev= 30
  3439.7  459.71  3597.4  458.60  3860.6  455.09  3933.4  456.64  4069.1  455.29
  4231.9  458.77  4236.9  455.64  4253.5  455.38  4293.8  458.13  4434.9  455.55
  4481.2  458.40  4777.4  455.58  4893.3  457.74  4928.6  455.56  4974.2  458.54
  4979.6  456.52  5058.9  458.79  5136.2  456.94  5222.0  455.79  5302.9  458.89
  5562.8  455.29  5626.5  457.91  5707.4  453.50  5881.9  449.99  5884.7  449.49
  5887.9  449.99  5889.9  450.22  5905.8  451.45  5948.8  462.20  5989.4  463.26
#Mann=7,-1,0
  3439.7    0.05       0  3597.4    0.16       0  3933.4    0.05       0
  5136.2    0.08       0  5881.9   0.033       0  5887.9    0.08       0
  5889.9    0.05       0
Bank Sta=5881.9,5887.9
Exp/Cntr=0.3,0.1

Type RM Length L Ch R = 1,19004,38,38,38
BEGIN DESCRIPTION:
WHITE ROCK CREEK 31.0
END DESCRIPTION:
XS GIS Cut Line= 4
      3550760.52     10579239.28      3548607.73     10579524.00
      3548281.35     10579572.61      3548230.85     10579691.41
#Sta/Elev= 30
  3424.4  468.30  3479.4  466.59  3484.5  467.47  3598.7  466.52  3950.3  465.09
  4322.6  463.85  4773.3  460.44  5021.1  460.39  5102.9  460.19  5121.4  460.05
  5702.7  460.66  5818.2  458.37  5840.7  459.81  5874.6  460.15  5894.8  458.05
  5928.1  458.78  5933.5  456.65  5939.0  456.87  5946.6  454.55  5962.6  453.28
  5976.2  449.45  5978.9  448.95  5982.2  449.45  5986.3  450.86  5991.7  449.56
  6009.9  457.30  6015.3  456.92  6022.7  459.61  6039.0  462.26  6055.0  462.30
#Mann=9,-1,0
  3424.4    0.05       0  3598.7    0.16       0  3950.3    0.05       0
  5021.1    0.16       0  5102.9    0.05       0  5121.4    0.08       0
  5840.7    0.05       0  5976.2    0.04       0  5982.2    0.05       0
Bank Sta=5976.2,5982.2
Exp/Cntr=0.3,0.1

Type RM Length L Ch R = 1,18966,148,148,148
BEGIN DESCRIPTION:
WHITE ROCK CREEK 30.1
END DESCRIPTION:
XS GIS Cut Line= 3
      3550740.32     10579214.79      3549130.12     10579418.78
      3548307.60     10579529.46
#Sta/Elev= 30
  3428.5  458.76  3593.7  457.37  4100.5  455.37  4318.6  456.70  4473.8  449.57
  4478.8  454.46  4553.9  448.44  4558.9  452.20  4634.0  447.00  4639.0  451.44
  4714.1  444.69  4719.2  449.02  4794.2  444.05  4799.3  448.75  4874.3  443.76
  4879.4  449.32  5002.3  445.24  5031.5  443.10  5034.3  442.60  5037.5  443.10
  5039.6  448.01  5180.6  444.46  5185.7  449.74  5251.4  443.75  5263.5  447.90
  5294.6  445.79  5559.8  447.69  5665.1  457.68  5810.6  458.72  5881.5  458.79
#Mann=8,-1,0
  3428.5    0.05       0  3593.7    0.16       0  4100.5    0.05       0
  5002.3    0.16       0  5031.5    0.04       0  5037.5    0.16       0
  5294.6    0.08       0  5810.6    0.05       0
Bank Sta=5031.5,5037.5
Exp/Cntr=0.3,0.1

Type RM Length L Ch R = 1,18818,303,303,303
BEGIN DESCRIPTION:
WHITE ROCK CREEK 30.0
END DESCRIPTION:
XS GIS Cut Line= 4
      3549817.66     10579216.04      3549200.51     10579260.30
      3549039.05     10579296.76      3548585.21     10579325.29
#Sta/Elev= 30
  4291.9  453.26  4477.9  450.69  4538.1  447.08  4558.1  446.42  4576.5  444.90
  4581.6  445.01  4658.4  440.21  4698.5  439.28  4758.7  438.68  4778.7  437.52
  4799.4  438.46  4808.8  438.71  4838.9  437.77  4896.0  437.01  4898.8  436.51
  4902.0  437.01  4910.6  437.42  4919.3  438.72  4924.9  438.90  4937.6  438.84
  5083.1  439.04  5193.3  438.46  5223.4  438.60  5236.0  439.29  5328.4  440.45
  5363.7  442.86  5422.2  445.32  5443.8  446.38  5472.2  448.59  5530.9  453.15
#Mann=9,-1,0
  4291.9    0.05       0  4799.4    0.16       0  4896.0    0.07       0
  4902.0    0.16       0  4924.9    0.05       0  4937.6    0.08       0
  5328.4    0.16       0  5422.2    0.05       0  5472.2    0.08       0
Bank Sta=4896,4902
Exp/Cntr=0.3,0.1

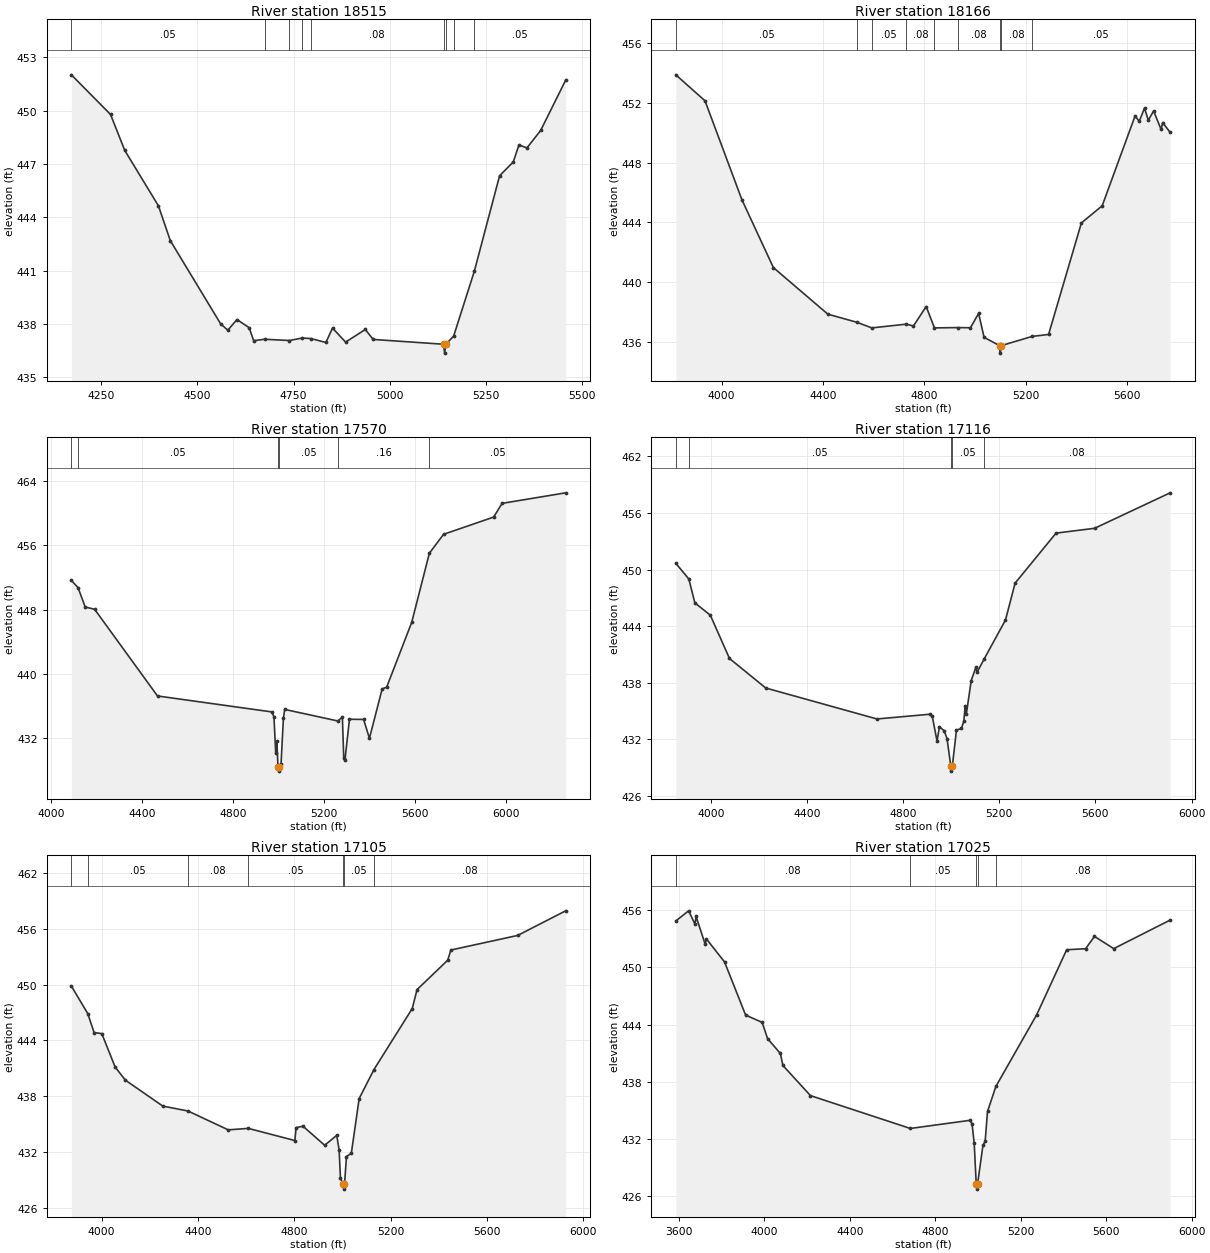
Type RM Length L Ch R = 1,18515,349,349,349
BEGIN DESCRIPTION:
WHITE ROCK CREEK 29.2
END DESCRIPTION:
XS GIS Cut Line= 4
      3549768.11     10579162.69      3549195.22     10578960.88
      3548850.17     10579036.83      3548587.08     10579226.61
#Sta/Elev= 30
  4172.3  452.02  4274.1  449.79  4311.0  447.77  4398.6  444.65  4429.5  442.69
  4560.3  438.01  4579.0  437.65  4602.8  438.25  4634.6  437.79  4646.2  437.06
  4674.6  437.14  4739.2  437.07  4772.8  437.21  4794.9  437.18  4834.1  436.96
  4851.2  437.77  4885.3  436.98  4936.5  437.69  4957.0  437.13  5139.9  436.86
  5142.7  436.36  5145.9  436.86  5166.2  437.32  5220.1  440.98  5285.6  446.34
  5321.2  447.12  5335.9  448.07  5356.8  447.91  5392.4  448.89  5457.4  451.72
#Mann=9,-1,0
  4172.3    0.05       0  4674.6    0.16       0  4739.2    0.05       0
  4772.8    0.16       0  4794.9    0.08       0  5139.9    0.07       0
  5145.9    0.08       0  5166.2    0.16       0  5220.1    0.05       0
Bank Sta=5139.9,5145.9
Exp/Cntr=0.3,0.1

Type RM Length L Ch R = 1,18166,596,596,596
BEGIN DESCRIPTION:
WHITE ROCK CREEK 29.0
END DESCRIPTION:
XS GIS Cut Line= 5
      3549896.43     10579183.89      3548950.29     10578645.72
      3548737.62     10578728.19      3548542.11     10579191.64
      3548436.28     10579265.76
#Sta/Elev= 30
  3819.8  453.89  3934.8  452.15  4080.4  445.52  4204.4  440.98  4419.1  437.86
  4534.8  437.31  4592.2  436.94  4728.1  437.19  4756.6  437.07  4806.9  438.37
  4839.4  436.94  4930.7  436.96  4981.4  436.95  5013.6  437.91  5035.1  436.31
  5096.3  435.75  5099.0  435.25  5102.3  435.75  5224.8  436.37  5289.4  436.50
  5418.8  443.97  5500.8  445.12  5630.3  451.13  5646.8  450.78  5667.7  451.66
  5682.6  450.85  5703.5  451.47  5733.1  450.23  5739.2  450.69  5768.6  450.04
#Mann=9,-1,0
  3819.8    0.05       0  4534.8    0.16       0  4592.2    0.05       0
  4728.1    0.08       0  4839.4    0.05       0  4930.7    0.08       0
  5096.3    0.07       0  5102.3    0.08       0  5224.8    0.05       0
Bank Sta=5096.3,5102.3
Exp/Cntr=0.3,0.1

Type RM Length L Ch R = 1,17570,454,454,454
BEGIN DESCRIPTION:
WHITE ROCK CREEK 29.1
END DESCRIPTION:
XS GIS Cut Line= 3
      3549650.65     10577864.48      3548374.64     10578220.37
      3547525.55     10578259.36
#Sta/Elev= 30
  4088.2  451.65  4117.5  450.76  4149.0  448.35  4190.5  448.06  4467.1  437.28
  4969.1  435.30  4979.5  434.71  4987.1  430.23  4992.3  431.62  4997.3  428.43
  5000.0  427.93  5003.3  428.43  5010.7  428.84  5021.0  434.48  5026.5  435.61
  5260.3  434.17  5280.6  434.64  5286.6  429.53  5291.8  429.31  5311.7  434.38
  5374.0  434.36  5399.5  432.01  5455.5  438.15  5475.5  438.38  5585.6  446.44
  5663.3  455.04  5725.8  457.39  5946.0  459.53  5983.3  461.24  6262.9  462.55
#Mann=6,-1,0
  4088.2    0.08       0  4117.5    0.05       0  4997.3    0.04       0
  5003.3    0.05       0  5260.3    0.16       0  5663.3    0.05       0
Bank Sta=4997.3,5003.3
Exp/Cntr=0.3,0.1

Type RM Length L Ch R = 1,17116,11,11,11
BEGIN DESCRIPTION:
WHITE ROCK CREEK 28.03
END DESCRIPTION:
XS GIS Cut Line= 6
      3549618.41     10577848.74      3549479.53     10577886.93
      3549252.10     10577836.58      3548503.84     10577850.47
      3548279.88     10577897.34      3547578.54     10577945.95
#Sta/Elev= 30
  3853.8  450.66  3908.0  448.99  3932.9  446.47  3997.3  445.16  4077.1  440.57
  4228.1  437.44  4690.8  434.16  4910.9  434.66  4920.9  434.47  4940.9  431.82
  4950.9  433.34  4970.9  432.90  4982.6  432.07  4998.4  429.13  5001.1  428.63
  5004.4  429.13  5021.8  432.98  5042.2  433.15  5052.5  433.93  5057.8  435.56
  5062.9  434.68  5083.1  438.22  5102.7  439.64  5107.8  439.11  5137.1  440.52
  5225.8  444.65  5265.9  448.56  5436.3  453.86  5596.7  454.37  5911.0  458.13
#Mann=5,-1,0
  3853.8    0.08       0  3908.0    0.05       0  4998.4    0.04       0
  5004.4    0.05       0  5137.1    0.08       0
Bank Sta=4998.4,5004.4
Exp/Cntr=0.3,0.1

Type RM Length L Ch R = 1,17105,80,80,80
BEGIN DESCRIPTION:
WHITE ROCK CREEK 28.02
END DESCRIPTION:
XS GIS Cut Line= 6
      3549594.09     10577841.80      3549470.85     10577869.57
      3549245.16     10577815.75      3548486.48     10577843.52
      3548283.35     10577879.98      3547556.50     10577930.29
#Sta/Elev= 30
  3874.8  449.84  3942.9  446.87  3969.1  444.84  4001.1  444.72  4056.6  441.12
  4098.7  439.72  4254.4  436.92  4359.1  436.39  4526.2  434.36  4609.4  434.52
  4802.9  433.21  4807.9  434.60  4836.6  434.75  4926.7  432.70  4976.7  433.77
  4986.7  432.16  4992.0  429.18  5002.9  428.48  5005.7  427.98  5008.9  428.48
  5017.1  431.49  5037.4  431.85  5069.8  437.73  5131.2  440.85  5290.2  447.42
  5310.2  449.46  5437.7  452.63  5450.6  453.72  5727.9  455.29  5927.3  457.94
#Mann=7,-1,0
  3874.8    0.08       0  3942.9    0.05       0  4359.1    0.08       0
  4609.4    0.05       0  5002.9    0.04       0  5008.9    0.05       0
  5131.2    0.08       0
Bank Sta=5002.9,5008.9
Exp/Cntr=0.3,0.1

Type RM Length L Ch R = 1,17025,59,59,59
BEGIN DESCRIPTION:
WHITE ROCK CREEK 28.0
END DESCRIPTION:
XS GIS Cut Line= 5
      3549830.26     10577867.84      3549215.65     10577725.47
      3548479.53     10577768.87      3548356.27     10577794.91
      3547538.59     10577836.58
#Sta/Elev= 30
  3586.2  454.86  3645.9  455.92  3675.8  454.53  3681.0  455.33  3723.7  452.40
  3728.8  452.99  3814.2  450.56  3912.8  444.99  3990.0  444.23  4015.4  442.53
  4075.4  440.97  4087.3  439.71  4216.3  436.55  4683.5  433.11  4962.1  433.96
  4972.3  433.61  4982.5  431.55  4992.0  427.25  4994.7  426.75  4998.0  427.25
  5023.4  431.35  5033.6  431.76  5044.7  434.89  5084.0  437.52  5274.9  445.03
  5415.1  451.84  5503.8  451.95  5545.2  453.24  5635.3  451.96  5899.2  454.95
#Mann=5,-1,0
  3586.2    0.08       0  4683.5    0.05       0  4992.0    0.04       0
  4998.0    0.05       0  5084.0    0.08       0
Bank Sta=4992,4998
Exp/Cntr=0.3,0.1

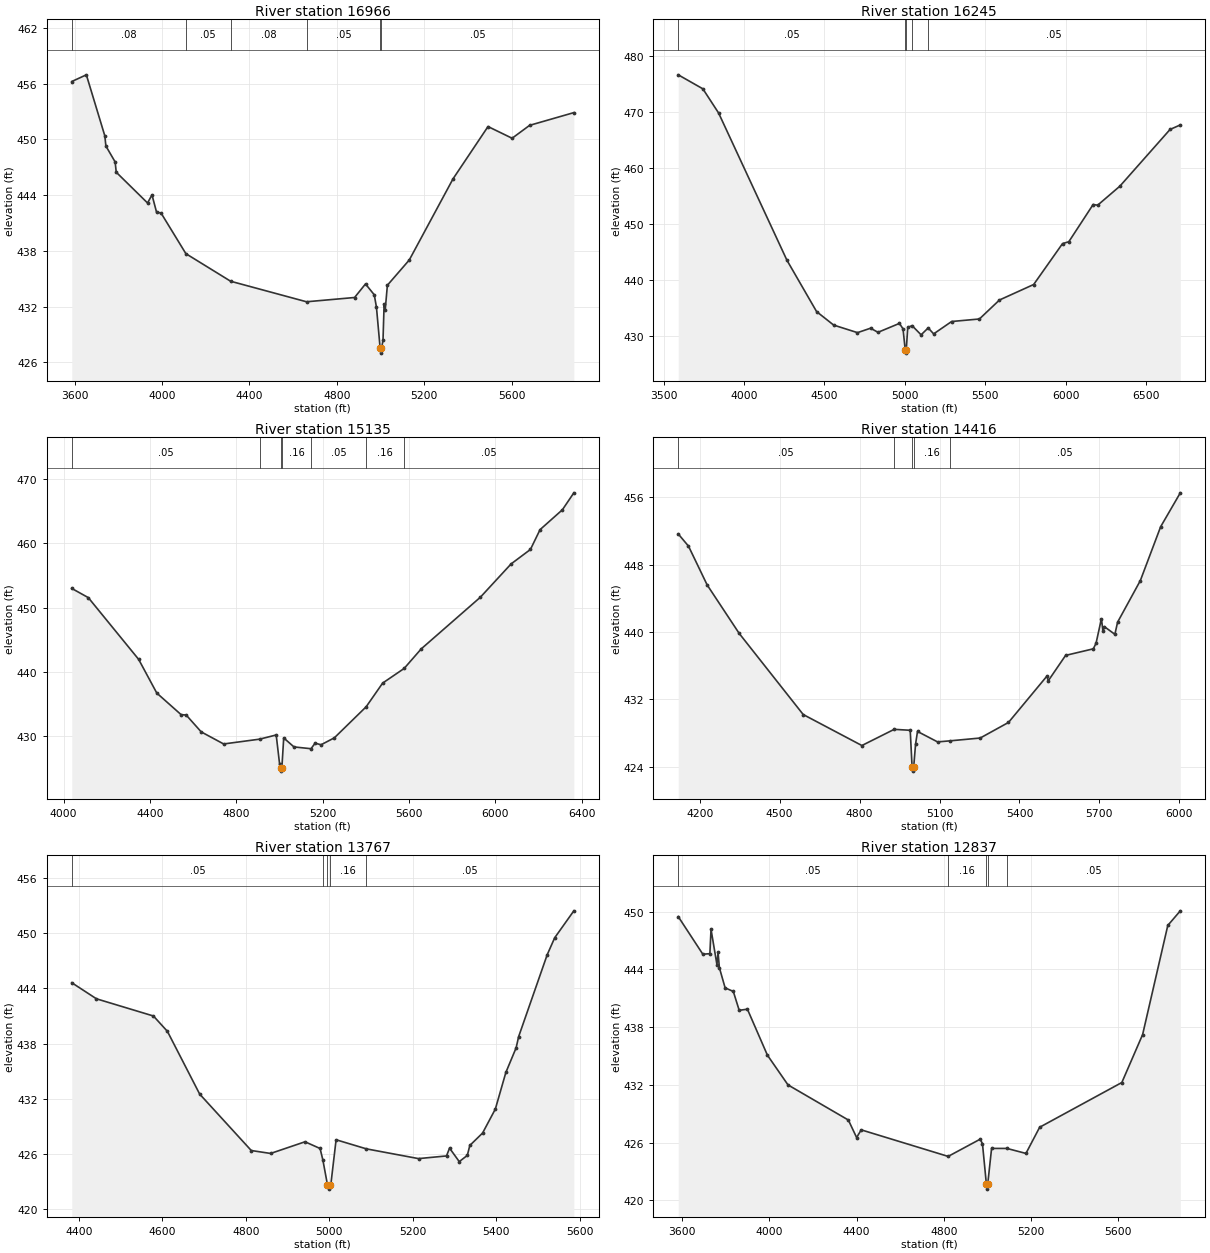
Type RM Length L Ch R = 1,16966,721,721,721
BEGIN DESCRIPTION:
WHITE ROCK CREEK 28.01
END DESCRIPTION:
XS GIS Cut Line= 3
      3549809.43     10577822.70      3549239.95     10577687.27
      3547529.88     10577767.14
#Sta/Elev= 30
  3586.9  456.24  3653.6  456.96  3738.0  450.40  3743.1  449.29  3785.3  447.58
  3790.4  446.47  3933.6  443.16  3954.0  444.03  3974.8  442.17  3995.3  442.08
  4109.1  437.70  4313.9  434.73  4661.0  432.52  4880.9  432.98  4930.9  434.44
  4971.0  433.27  4981.0  431.94  4998.0  427.49  5000.8  426.99  5004.0  427.49
  5011.0  428.37  5016.1  432.28  5021.1  431.65  5031.0  434.30  5131.2  437.02
  5331.4  445.76  5491.5  451.39  5601.7  450.13  5681.8  451.52  5884.2  452.89
#Mann=6,-1,0
  3586.9    0.08       0  4109.1    0.05       0  4313.9    0.08       0
  4661.0    0.05       0  4998.0    0.03       0  5004.0    0.05       0
Bank Sta=4998,5004
Exp/Cntr=0.3,0.1

Type RM Length L Ch R = 1,16245,1110,1110,1110
BEGIN DESCRIPTION:
WHITE ROCK CREEK 26.0
END DESCRIPTION:
XS GIS Cut Line= 4
      3549649.06     10576393.13      3548537.97     10576948.67
      3548255.85     10577087.56      3546750.79     10577516.96
#Sta/Elev= 30
  3591.1  476.70  3744.2  474.20  3842.1  469.88  4266.9  443.58  4451.4  434.40
  4557.6  431.99  4705.7  430.64  4786.8  431.43  4833.3  430.70  4966.3  432.29
  4988.8  431.32  5002.7  427.48  5005.4  426.98  5008.7  427.48  5018.2  431.57
  5045.2  431.89  5101.1  430.25  5145.2  431.48  5179.3  430.42  5291.1  432.63
  5463.7  433.08  5588.4  436.47  5801.1  439.24  5980.6  446.55  6019.6  446.88
  6170.8  453.53  6199.1  453.41  6337.2  456.81  6649.1  466.94  6712.9  467.75
#Mann=5,-1,0
  3591.1    0.05       0  5002.7    0.03       0  5008.7    0.05       0
  5045.2    0.16       0  5145.2    0.05       0
Bank Sta=5002.7,5008.7
Exp/Cntr=0.3,0.1

Type RM Length L Ch R = 1,15135,719,719,719
BEGIN DESCRIPTION:
WHITE ROCK CREEK 24.0
END DESCRIPTION:
XS GIS Cut Line= 3
      3548592.10     10575991.65      3547692.11     10576391.64
      3546492.12     10576991.64
#Sta/Elev= 30
  4037.5  452.98  4114.1  451.55  4347.3  441.94  4431.4  436.69  4544.3  433.32
  4567.6  433.27  4637.3  430.64  4741.3  428.76  4908.2  429.51  4984.8  430.16
  5000.5  425.64  5005.0  425.03  5007.8  424.53  5011.0  425.03  5019.6  429.70
  5067.1  428.30  5146.2  428.02  5164.9  428.88  5192.9  428.64  5254.4  429.72
  5401.6  434.55  5478.0  438.24  5577.7  440.52  5656.9  443.57  5930.8  451.61
  6073.3  456.80  6162.8  459.05  6207.5  462.14  6310.9  465.23  6364.0  467.87
#Mann=7,-1,0
  4037.5    0.05       0  4908.2    0.16       0  5005.0    0.07       0
  5011.0    0.16       0  5146.2    0.05       0  5401.6    0.16       0
  5577.7    0.05       0
Bank Sta=5005,5011
Exp/Cntr=0.3,0.1

Type RM Length L Ch R = 1,14416,649,649,649
BEGIN DESCRIPTION:
WHITE ROCK CREEK 23.0
END DESCRIPTION:
XS GIS Cut Line= 3
      3548500.59     10575779.40      3547750.64     10575748.15
      3546629.15     10575584.96
#Sta/Elev= 30
  4119.6  451.65  4158.1  450.20  4228.2  445.59  4348.3  439.84  4588.5  430.21
  4808.7  426.53  4929.9  428.45  4990.0  428.34  4997.1  423.99  4999.8  423.49
  5003.1  423.99  5010.2  426.72  5017.4  428.20  5092.6  426.96  5137.5  427.08
  5252.7  427.42  5358.8  429.27  5503.0  434.77  5508.1  434.22  5573.1  437.23
  5677.1  438.01  5687.3  438.67  5707.5  441.58  5713.3  440.11  5718.3  440.65
  5758.0  439.73  5768.1  441.17  5853.5  446.11  5929.8  452.51  6003.5  456.53
#Mann=5,-1,0
  4119.6    0.05       0  4929.9    0.16       0  4997.1    0.07       0
  5003.1    0.16       0  5137.5    0.05       0
Bank Sta=4997.1,5003.1
Exp/Cntr=0.3,0.1

Type RM Length L Ch R = 1,13767,930,930,930
BEGIN DESCRIPTION:
WHITE ROCK CREEK 21.0
END DESCRIPTION:
XS GIS Cut Line= 3
      3548342.08     10575291.64      3547742.11     10575141.64
      3547192.09     10574941.64
#Sta/Elev= 30
  4382.6  444.62  4441.8  442.87  4578.4  441.00  4611.9  439.33  4689.2  432.51
  4812.9  426.37  4859.3  426.05  4941.8  427.32  4977.9  426.59  4984.6  425.34
  4995.5  422.67  4998.2  422.17  5001.5  422.67  5003.7  422.67  5016.3  427.54
  5088.9  426.55  5213.9  425.49  5281.0  425.78  5288.3  426.63  5311.6  425.16
  5330.9  425.84  5336.9  426.92  5367.5  428.27  5398.1  430.88  5423.3  434.86
  5448.0  437.55  5453.9  438.75  5522.4  447.66  5540.4  449.51  5586.3  452.44
#Mann=5,-1,0
  4382.6    0.05       0  4984.6    0.16       0  4995.5    0.07       0
  5001.5    0.16       0  5088.9    0.05       0
Bank Sta=4995.5,5001.5
Exp/Cntr=0.3,0.1

Type RM Length L Ch R = 1,12837,400,400,400
BEGIN DESCRIPTION:
WHITE ROCK CREEK 20.0
END DESCRIPTION:
XS GIS Cut Line= 2
      3549171.82     10574731.55      3546977.38     10574037.11
#Sta/Elev= 30
  3582.7  449.48  3695.5  445.57  3727.8  445.63  3733.0  448.16  3760.1  444.49
  3765.3  445.75  3771.2  444.18  3797.6  442.08  3835.2  441.70  3862.2  439.74
  3899.8  439.86  3991.5  435.08  4085.9  431.99  4362.6  428.34  4400.5  426.52
  4421.5  427.32  4820.1  424.56  4966.9  426.35  4977.4  425.88  4995.4  421.66
  4998.1  421.16  5001.4  421.66  5019.2  425.39  5089.3  425.39  5176.7  424.87
  5239.6  427.59  5616.4  432.24  5711.6  437.22  5827.0  448.56  5884.4  450.08
#Mann=5,-1,0
  3582.7    0.05       0  4820.1    0.16       0  4995.4    0.07       0
  5001.4    0.16       0  5089.3    0.05       0
Bank Sta=4995.4,5001.4
Exp/Cntr=0.3,0.1