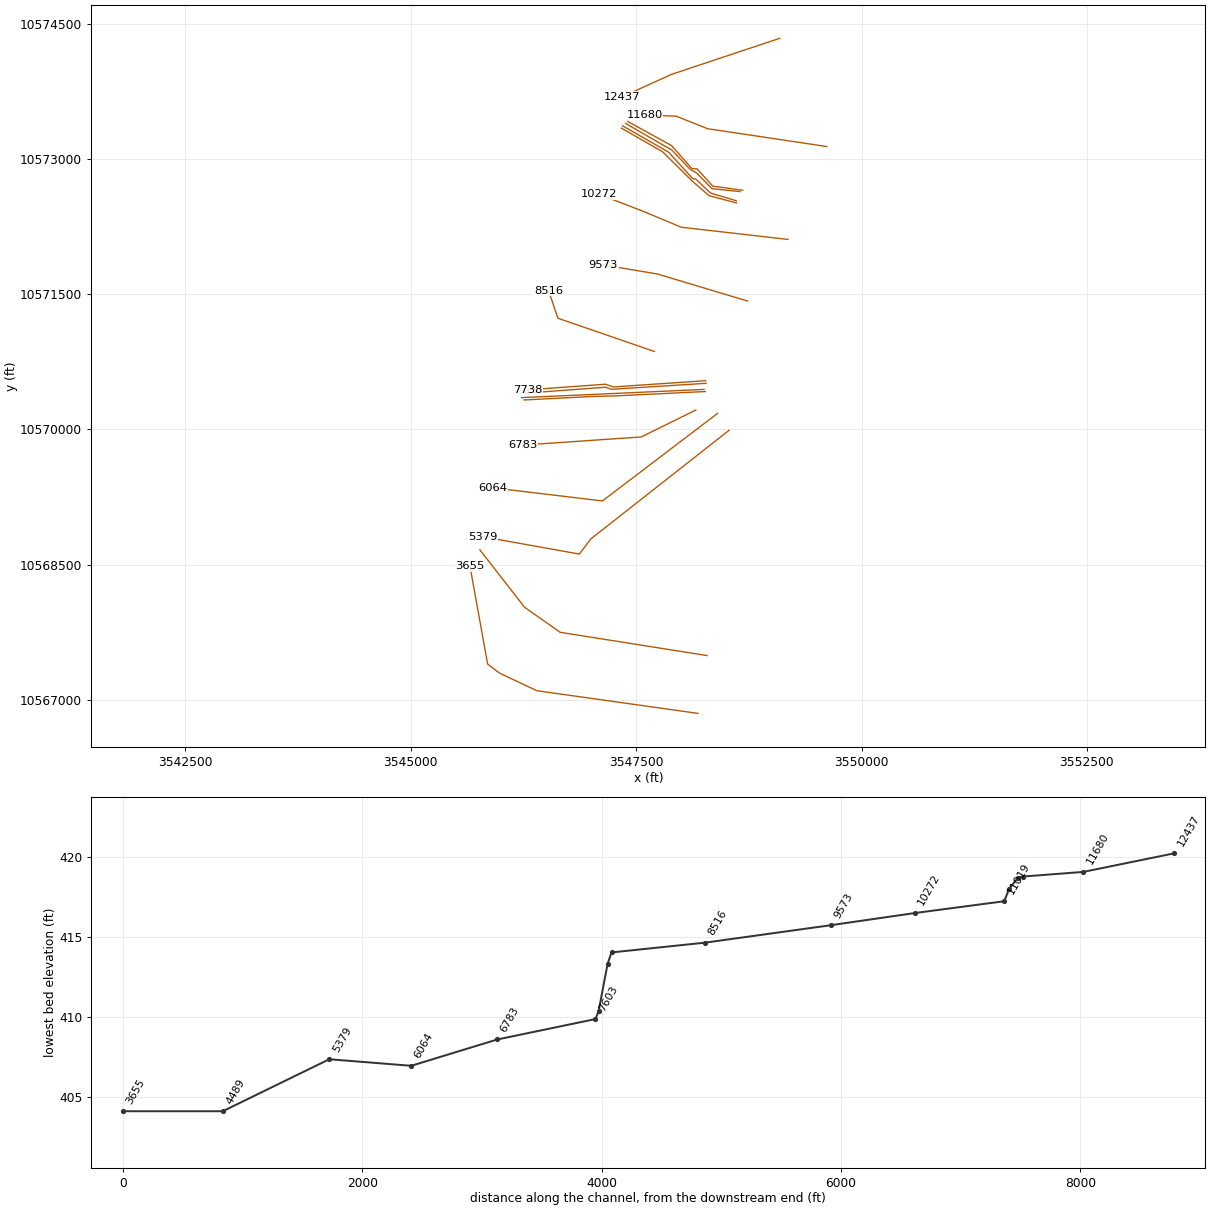
HEC-RAS study WHITE ROCK CREEK.prj: WHITE ROCK CREEK Base Level Engineering

--- WHITE ROCK CREEK.g01 (geometry) --- (continued)

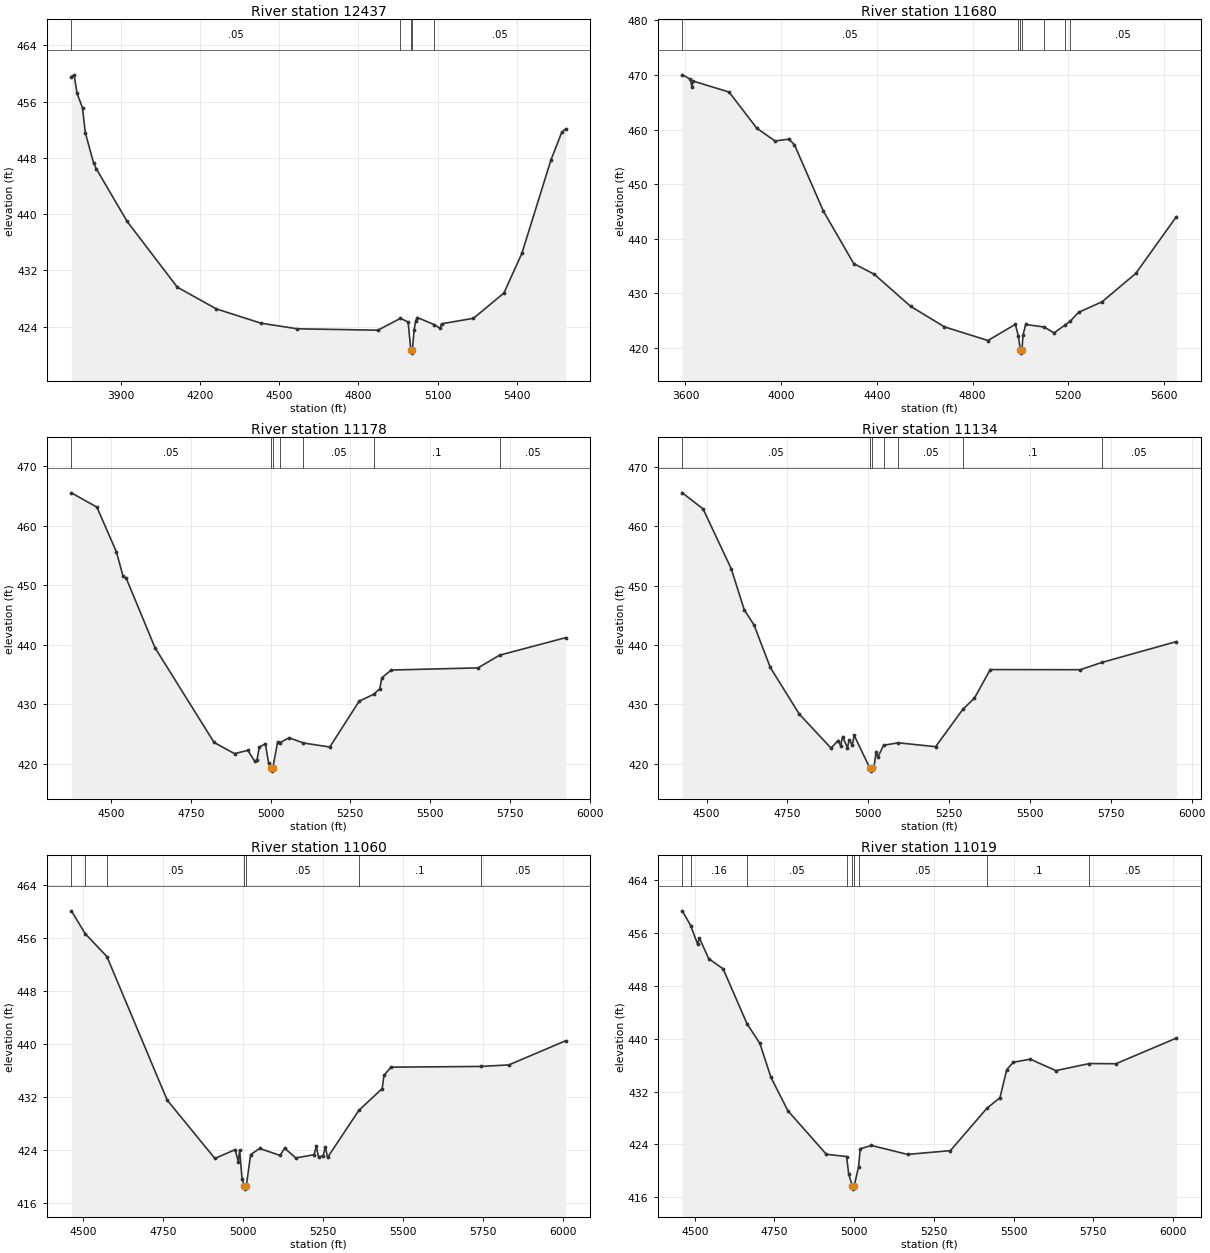
Type RM Length L Ch R = 1,12437,757,757,757
BEGIN DESCRIPTION:
WHITE ROCK CREEK 18.0
END DESCRIPTION:
XS GIS Cut Line= 3
      3549092.08     10574341.63      3547892.11     10573941.64
      3547342.13     10573691.66
#Sta/Elev= 30
  3714.0  459.55  3724.5  459.81  3735.1  457.22  3756.1  455.11  3766.7  451.59
  3798.3  447.24  3808.8  446.42  3924.8  438.98  4114.5  429.63  4262.1  426.54
  4430.8  424.51  4567.8  423.71  4873.5  423.51  4958.8  425.20  4987.7  424.67
  4997.8  420.75  5000.6  420.25  5003.8  420.75  5010.7  423.60  5016.2  424.82
  5022.8  425.31  5086.5  424.30  5108.5  423.77  5114.0  424.42  5234.8  425.20
  5350.2  428.80  5418.3  434.47  5528.1  447.73  5568.8  451.64  5583.0  452.11
#Mann=5,-1,0
  3714.0    0.05       0  4958.8    0.16       0  4997.8    0.07       0
  5003.8    0.16       0  5086.5    0.05       0
Bank Sta=4997.8,5003.8
Exp/Cntr=0.3,0.1

Type RM Length L Ch R = 1,11680,502,502,502
BEGIN DESCRIPTION:
WHITE ROCK CREEK 17.0
END DESCRIPTION:
XS GIS Cut Line= 4
      3549615.21     10573140.51      3548292.31     10573338.43
      3547945.08     10573477.32      3547592.07     10573491.64
#Sta/Elev= 30
  3586.9  470.01  3620.4  469.21  3626.9  467.80  3631.9  468.87  3782.2  466.86
  3898.5  460.23  3974.3  457.91  4031.9  458.24  4055.2  457.25  4176.5  445.07
  4303.5  435.46  4388.8  433.53  4540.5  427.67  4682.1  423.90  4864.1  421.40
  4978.8  424.36  4990.6  422.31  5000.0  419.59  5002.8  419.09  5006.0  419.59
  5010.9  422.43  5021.7  424.33  5098.8  423.87  5140.3  422.79  5184.1  424.17
  5207.0  424.88  5242.6  426.55  5341.5  428.50  5481.6  433.66  5651.8  444.07
#Mann=7,-1,0
  3586.9    0.05       0  4990.6    0.16       0  5000.0    0.07       0
  5006.0    0.16       0  5098.8    0.05       0  5184.1    0.16       0
  5207.0    0.05       0
Bank Sta=5000,5006
Exp/Cntr=0.3,0.1

Type RM Length L Ch R = 1,11178,44,44,44
BEGIN DESCRIPTION:
WHITE ROCK CREEK 15.03
END DESCRIPTION:
XS GIS Cut Line= 6
      3548681.97     10572655.12      3548351.06     10572700.69
      3548174.20     10572893.83      3548119.94     10572893.83
      3547893.16     10573150.99      3547406.57     10573418.67
#Sta/Elev= 30
  4375.9  465.54  4455.9  463.14  4517.1  455.61  4538.0  451.51  4547.4  451.25
  4638.2  439.50  4823.0  423.62  4887.1  421.74  4929.0  422.29  4950.6  420.44
  4957.4  420.66  4964.8  422.82  4983.9  423.41  4993.9  420.15  5000.9  419.30
  5003.7  418.80  5006.9  419.30  5022.5  423.76  5028.8  423.56  5058.5  424.41
  5102.5  423.53  5185.7  422.85  5277.7  430.55  5323.1  431.70  5342.2  432.63
  5348.8  434.48  5378.3  435.78  5650.1  436.14  5718.1  438.28  5924.3  441.21
#Mann=7,-1,0
  4375.9    0.05       0  5000.9    0.03       0  5006.9    0.05       0
  5028.8    0.16       0  5102.5    0.05       0  5323.1     0.1       0
  5718.1    0.05       0
Bank Sta=5000.9,5006.9
Exp/Cntr=0.3,0.1

Type RM Length L Ch R = 1,11134,74,74,74
BEGIN DESCRIPTION:
WHITE ROCK CREEK 15.02
END DESCRIPTION:
XS GIS Cut Line= 6
      3548652.67     10572639.93      3548340.21     10572673.56
      3548170.94     10572847.17      3548098.24     10572888.41
      3547897.50     10573100.00      3547382.68     10573396.97
#Sta/Elev= 30
  4424.8  465.65  4489.1  462.93  4576.1  452.85  4616.5  445.91  4646.6  443.37
  4696.9  436.21  4786.1  428.38  4884.8  422.60  4906.4  423.89  4914.4  423.02
  4920.4  424.55  4935.4  422.70  4941.4  424.04  4950.3  423.11  4956.4  424.77
  5004.8  419.23  5007.5  418.73  5010.8  419.23  5017.6  419.45  5023.9  421.89
  5029.9  421.11  5047.1  423.08  5092.2  423.51  5208.2  422.85  5292.6  429.17
  5328.3  431.04  5377.1  435.85  5655.7  435.83  5722.0  437.05  5953.0  440.57
#Mann=7,-1,0
  4424.8    0.05       0  5004.8    0.03       0  5010.8    0.05       0
  5047.1    0.16       0  5092.2    0.05       0  5292.6     0.1       0
  5722.0    0.05       0
Bank Sta=5004.8,5010.8
Exp/Cntr=0.3,0.1

Type RM Length L Ch R = 1,11060,41,41,41
BEGIN DESCRIPTION:
WHITE ROCK CREEK 15.0
END DESCRIPTION:
XS GIS Cut Line= 6
      3548612.37     10572537.93      3548323.76     10572624.73
      3548165.52     10572775.56      3548125.37     10572786.41
      3547859.53     10573078.29      3547348.45     10573371.27
#Sta/Elev= 30
  4462.6  460.05  4506.0  456.59  4573.8  453.14  4762.2  431.47  4911.5  422.65
  4975.0  423.99  4984.7  422.18  4989.0  423.89  4996.5  419.53  5003.8  418.52
  5006.6  418.02  5009.8  418.52  5023.3  423.24  5051.6  424.16  5115.3  423.11
  5129.6  424.20  5164.8  422.73  5221.5  423.22  5228.8  424.47  5235.6  422.89
  5249.8  423.04  5257.1  424.38  5264.0  422.81  5361.7  429.91  5434.7  433.20
  5440.4  435.19  5462.2  436.44  5743.8  436.55  5831.1  436.78  6008.2  440.42
#Mann=7,-1,0
  4462.6    0.05       0  4506.0    0.16       0  4573.8    0.05       0
  5003.8    0.03       0  5009.8    0.05       0  5361.7     0.1       0
  5743.8    0.05       0
Bank Sta=5003.8,5009.8
Exp/Cntr=0.3,0.1

Type RM Length L Ch R = 1,11019,747,747,747
BEGIN DESCRIPTION:
WHITE ROCK CREEK 15.01
END DESCRIPTION:
XS GIS Cut Line= 5
      3548612.55     10572514.06      3548307.66     10572595.44
      3548121.03     10572758.20      3547794.42     10573081.55
      3547337.61     10573344.14
#Sta/Elev= 30
  4461.0  459.33  4487.3  457.10  4508.9  454.29  4514.1  455.26  4543.8  452.09
  4589.1  450.55  4664.1  442.24  4704.2  439.29  4739.1  434.13  4792.1  429.10
  4912.7  422.52  4976.2  422.18  4983.0  419.49  4994.1  417.75  4996.9  417.25
  5000.1  417.75  5013.7  420.61  5019.0  423.35  5054.1  423.85  5167.3  422.50
  5301.7  423.07  5416.5  429.49  5457.2  431.07  5478.4  435.31  5498.9  436.43
  5552.1  436.90  5632.6  435.17  5737.9  436.24  5821.0  436.21  6010.7  440.09
#Mann=9,-1,0
  4461.0    0.05       0  4487.3    0.16       0  4664.1    0.05       0
  4976.2    0.16       0  4994.1    0.07       0  5000.1    0.16       0
  5013.7    0.05       0  5416.5     0.1       0  5737.9    0.05       0
Bank Sta=4994.1,5000.1
Exp/Cntr=0.3,0.1

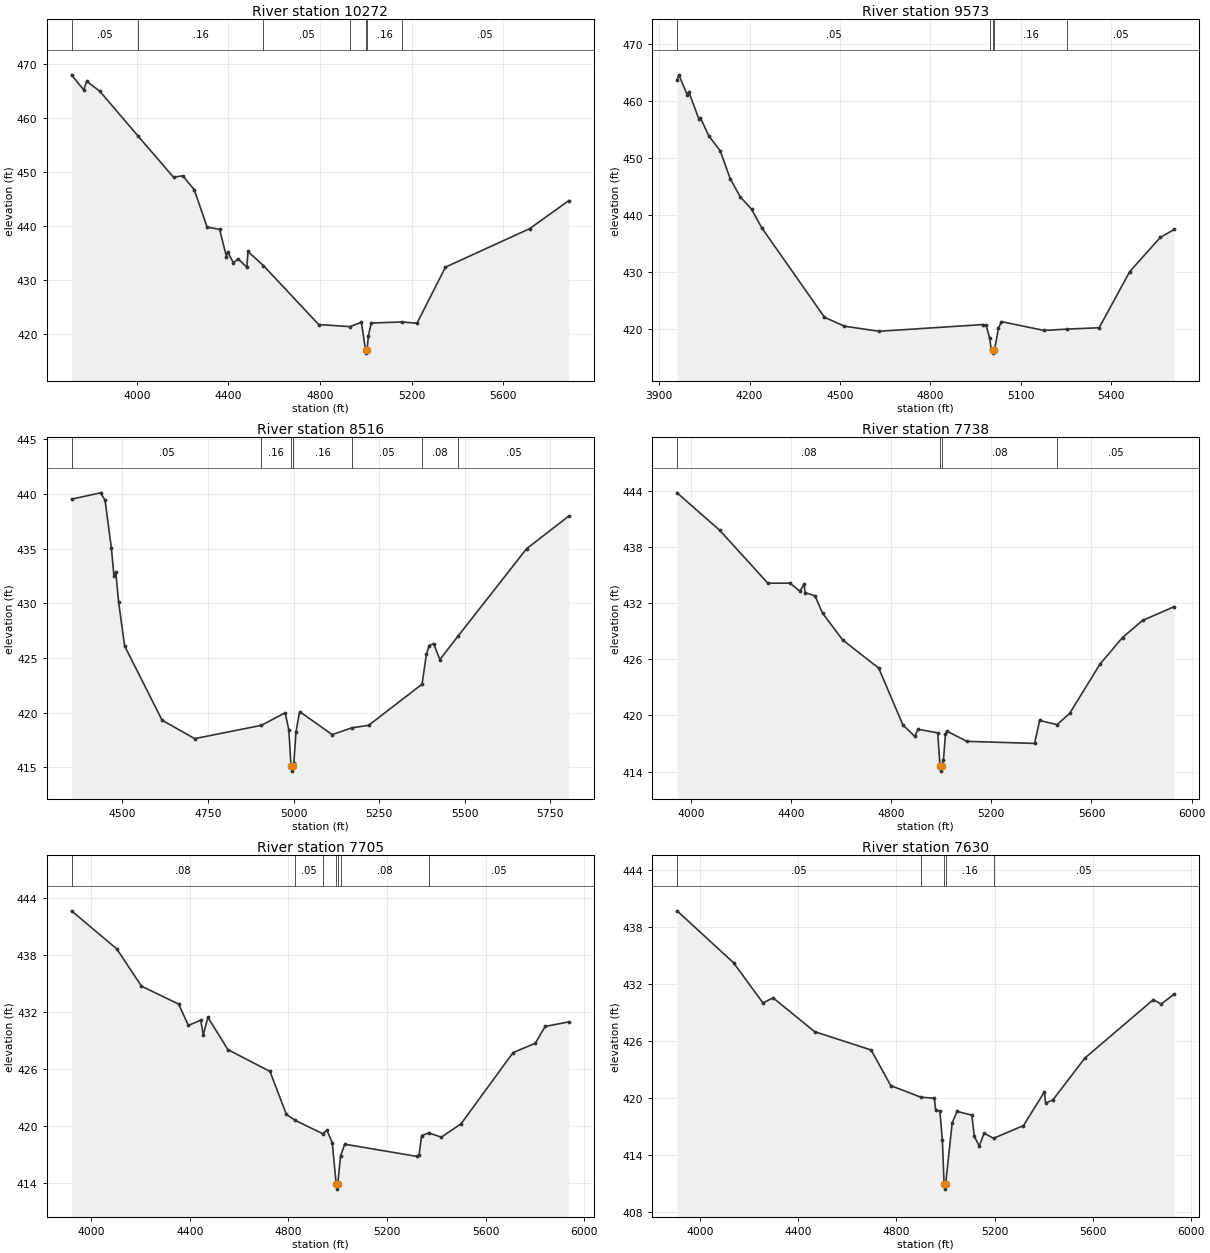
Type RM Length L Ch R = 1,10272,699,699,699
BEGIN DESCRIPTION:
WHITE ROCK CREEK 14.0
END DESCRIPTION:
XS GIS Cut Line= 4
      3549184.71     10572109.26      3548000.64     10572244.68
      3547577.03     10572421.76      3547090.96     10572609.25
#Sta/Elev= 30
  3714.8  468.07  3767.7  465.29  3781.3  466.87  3838.2  465.04  4005.1  456.74
  4160.3  449.10  4200.6  449.37  4250.9  446.79  4307.0  439.86  4361.6  439.45
  4391.3  434.40  4396.3  435.30  4422.0  433.24  4442.1  433.97  4480.6  432.43
  4485.6  435.34  4553.3  432.72  4794.4  421.81  4931.1  421.42  4980.9  422.23
  4999.5  417.01  5002.3  416.51  5005.5  417.01  5011.7  419.76  5024.2  422.09
  5157.5  422.28  5223.8  422.05  5348.2  432.44  5716.0  439.57  5886.7  444.76
#Mann=7,-1,0
  3714.8    0.05       0  4005.1    0.16       0  4553.3    0.05       0
  4931.1    0.16       0  4999.5    0.07       0  5005.5    0.16       0
  5157.5    0.05       0
Bank Sta=4999.5,5005.5
Exp/Cntr=0.3,0.1

Type RM Length L Ch R = 1,9573,1057,1057,1057
BEGIN DESCRIPTION:
WHITE ROCK CREEK 12.0
END DESCRIPTION:
XS GIS Cut Line= 3
      3548735.14     10571425.68      3547735.16     10571725.67
      3547136.13     10571825.51
#Sta/Elev= 30
  3959.0  463.66  3964.9  464.53  3992.7  461.04  3997.9  461.56  4031.0  456.86
  4036.2  457.05  4064.1  453.85  4102.3  451.22  4135.4  446.35  4168.5  443.17
  4206.7  440.96  4239.8  437.76  4448.6  422.04  4514.7  420.47  4630.3  419.58
  4975.8  420.76  4985.3  420.61  4997.5  418.32  5002.0  416.48  5007.1  416.25
  5009.8  415.75  5013.1  416.25  5026.4  420.12  5036.5  421.27  5178.5  419.72
  5253.7  419.96  5360.9  420.20  5462.3  430.03  5563.7  436.02  5610.3  437.43
#Mann=5,-1,0
  3959.0    0.05       0  4997.5    0.16       0  5007.1    0.07       0
  5013.1    0.16       0  5253.7    0.05       0
Bank Sta=5007.1,5013.1
Exp/Cntr=0.3,0.1

Type RM Length L Ch R = 1,8516,778,778,778
BEGIN DESCRIPTION:
WHITE ROCK CREEK 10.0
END DESCRIPTION:
XS GIS Cut Line= 3
      3547702.25     10570865.66      3546632.78     10571233.73
      3546529.05     10571537.99
#Sta/Elev= 30
  4351.1  439.52  4435.9  440.10  4449.0  439.43  4467.6  435.03  4475.0  432.51
  4480.2  432.90  4488.7  430.10  4506.2  426.10  4615.6  419.31  4710.8  417.62
  4906.0  418.84  4975.2  419.99  4985.8  418.44  4992.3  415.15  4995.0  414.65
  4998.3  415.15  5000.5  415.39  5006.9  418.26  5017.5  420.09  5112.7  417.99
  5169.8  418.61  5219.1  418.84  5375.1  422.60  5387.7  425.32  5395.9  426.13
  5408.8  426.31  5427.2  424.85  5481.2  427.04  5680.5  434.99  5803.6  437.97
#Mann=7,-1,0
  4351.1    0.05       0  4906.0    0.16       0  4992.3    0.07       0
  4998.3    0.16       0  5169.8    0.05       0  5375.1    0.08       0
  5481.2    0.05       0
Bank Sta=4992.3,4998.3
Exp/Cntr=0.3,0.1

Type RM Length L Ch R = 1,7738,33,33,33
BEGIN DESCRIPTION:
WHITE ROCK CREEK 9.0
END DESCRIPTION:
XS GIS Cut Line= 4
      3548271.72     10570540.93      3547245.28     10570471.49
      3547158.47     10570501.87      3546295.92     10570439.02
#Sta/Elev= 30
  3945.0  443.85  4115.0  439.85  4307.6  434.17  4395.6  434.18  4435.7  433.32
  4451.9  434.05  4456.9  433.16  4495.9  432.81  4525.9  430.97  4606.1  428.10
  4750.4  425.07  4846.7  419.00  4894.6  417.75  4906.8  418.53  4985.9  418.14
  4995.3  414.54  4998.1  414.04  5001.3  414.54  5008.9  415.25  5017.0  418.04
  5022.2  418.33  5102.2  417.23  5372.9  417.01  5393.0  419.47  5462.7  419.02
  5513.3  420.24  5633.6  425.49  5723.9  428.35  5804.1  430.18  5930.6  431.66
#Mann=4,-1,0
  3945.0    0.08       0  4995.3    0.07       0  5001.3    0.08       0
  5462.7    0.05       0
Bank Sta=4995.3,5001.3
Exp/Cntr=0.3,0.1

Type RM Length L Ch R = 1,7705,75,75,75
BEGIN DESCRIPTION:
WHITE ROCK CREEK 8.0
END DESCRIPTION:
XS GIS Cut Line= 4
      3548275.29     10570511.85      3547226.92     10570445.44
      3547157.48     10570468.23      3546266.79     10570402.06
#Sta/Elev= 30
  3920.5  442.62  4104.1  438.61  4204.3  434.69  4354.6  432.81  4394.6  430.56
  4444.7  431.11  4454.8  429.55  4473.6  431.41  4555.0  428.01  4725.3  425.72
  4792.1  421.19  4827.1  420.58  4939.7  419.16  4956.4  419.54  4978.1  418.19
  4994.1  413.83  4996.8  413.33  5000.1  413.83  5011.7  416.82  5028.7  418.06
  5320.2  416.78  5330.2  416.91  5340.4  418.96  5369.5  419.24  5420.5  418.80
  5500.7  420.21  5711.3  427.70  5801.5  428.68  5841.6  430.45  5937.2  430.93
#Mann=7,-1,0
  3920.5    0.08       0  4827.1    0.05       0  4939.7    0.16       0
  4994.1    0.07       0  5000.1    0.16       0  5011.7    0.08       0
  5369.5    0.05       0
Bank Sta=4994.1,5000.1
Exp/Cntr=0.3,0.1

Type RM Length L Ch R = 1,7630,27,27,27
BEGIN DESCRIPTION:
WHITE ROCK CREEK 7.0
END DESCRIPTION:
XS GIS Cut Line= 3
      3548251.85     10570444.14      3547100.84     10570392.06
      3546228.41     10570353.00
#Sta/Elev= 30
  3906.8  439.66  4136.8  434.20  4256.9  429.96  4297.9  430.50  4467.1  426.94
  4697.4  425.01  4777.4  421.26  4899.6  420.04  4955.1  419.92  4960.1  418.72
  4977.6  418.55  4987.7  415.50  4994.7  410.86  4997.4  410.36  5000.7  410.86
  5027.7  417.35  5047.7  418.54  5107.8  418.15  5117.8  415.91  5137.8  414.90
  5157.8  416.25  5196.1  415.71  5318.0  417.05  5403.4  420.60  5408.4  419.41
  5438.1  419.76  5568.2  424.16  5847.1  430.31  5878.5  429.84  5932.3  430.89
#Mann=5,-1,0
  3906.8    0.05       0  4899.6    0.16       0  4994.7    0.07       0
  5000.7    0.16       0  5196.1    0.05       0
Bank Sta=4994.7,5000.7
Exp/Cntr=0.3,0.1

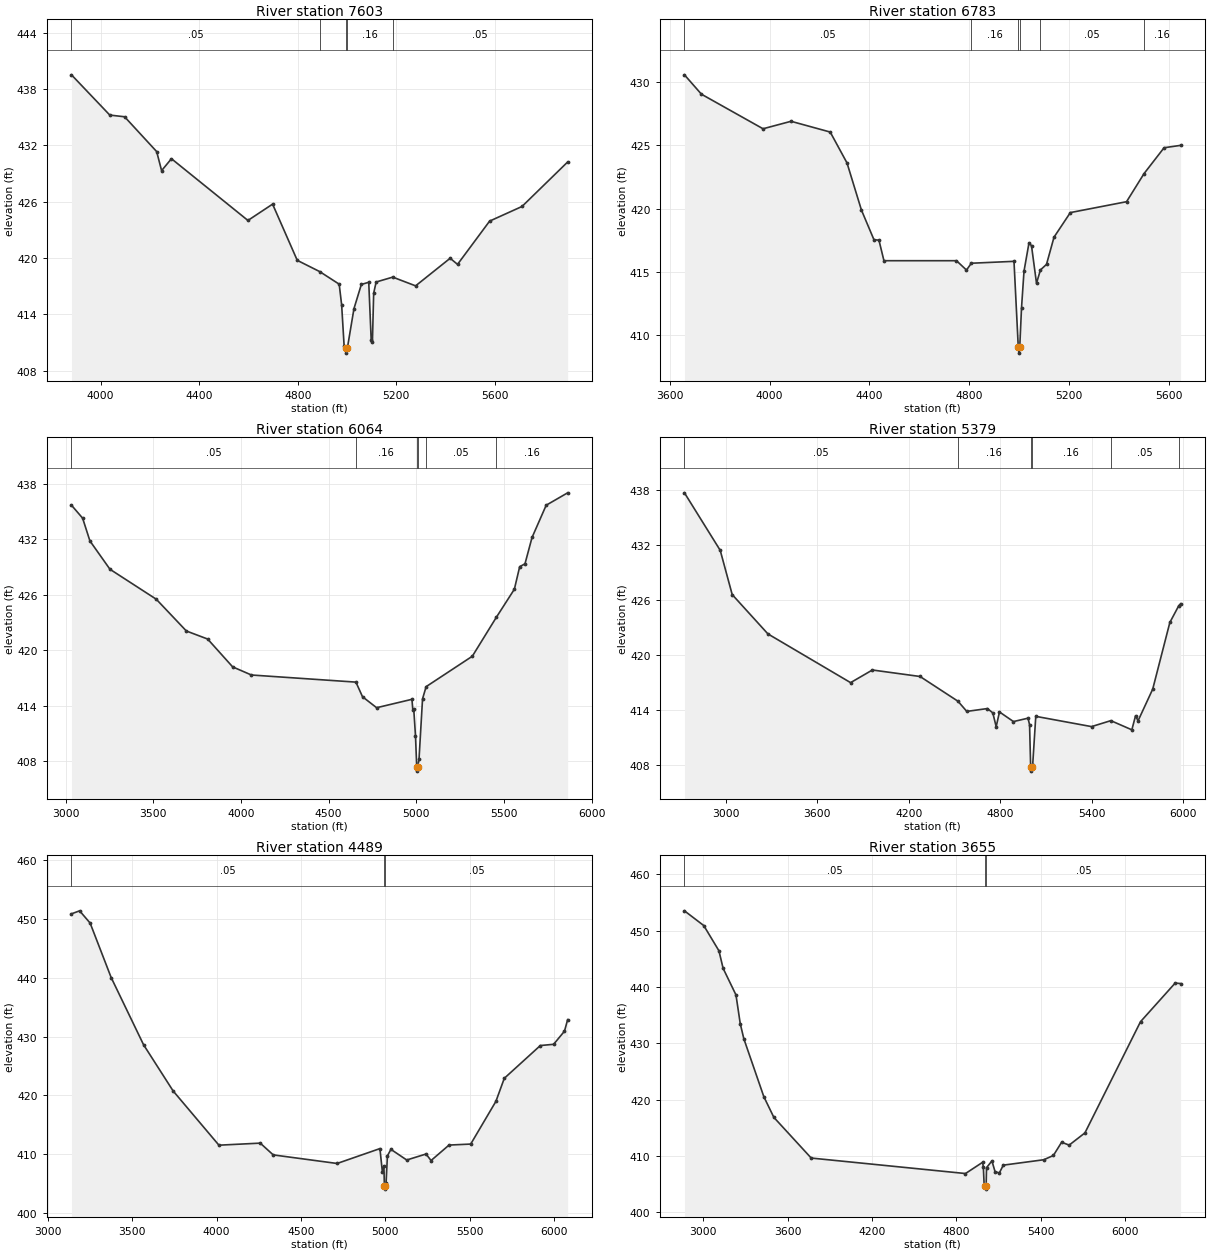
Type RM Length L Ch R = 1,7603,820,820,820
BEGIN DESCRIPTION:
WHITE ROCK CREEK 6.0
END DESCRIPTION:
XS GIS Cut Line= 4
      3548267.45     10570420.70      3547246.67     10570371.23
      3547020.11     10570366.02      3546255.81     10570327.02
#Sta/Elev= 30
  3881.7  439.52  4037.2  435.23  4097.3  435.05  4227.5  431.34  4247.5  429.31
  4287.5  430.58  4597.9  424.00  4698.0  425.74  4798.1  419.75  4889.2  418.55
  4968.3  417.21  4978.3  415.00  4988.3  410.65  4995.3  410.36  4998.0  409.86
  5001.3  410.36  5028.3  414.60  5058.3  417.18  5088.3  417.41  5098.2  411.26
  5103.2  411.06  5108.3  416.24  5118.3  417.44  5185.7  417.96  5278.5  417.03
  5418.7  419.97  5448.7  419.32  5578.9  423.93  5710.4  425.49  5895.6  430.23
#Mann=5,-1,0
  3881.7    0.05       0  4889.2    0.16       0  4995.3    0.07       0
  5001.3    0.16       0  5185.7    0.05       0
Bank Sta=4995.3,5001.3
Exp/Cntr=0.3,0.1

Type RM Length L Ch R = 1,6783,719,719,719
BEGIN DESCRIPTION:
WHITE ROCK CREEK 6.1
END DESCRIPTION:
XS GIS Cut Line= 3
      3548161.54     10570215.17      3547557.34     10569916.54
      3546246.01     10569826.34
#Sta/Elev= 30
  3659.0  430.56  3727.1  429.03  3974.0  426.30  4086.2  426.89  4243.2  426.04
  4310.5  423.60  4368.3  419.88  4418.4  417.54  4438.5  417.50  4458.5  415.88
  4749.2  415.88  4789.3  415.14  4808.8  415.68  4979.7  415.83  4996.8  409.08
  4999.5  408.58  5002.8  409.08  5009.8  412.14  5019.8  415.05  5039.9  417.30
  5049.9  417.06  5069.9  414.10  5085.7  415.15  5110.0  415.59  5140.1  417.74
  5205.5  419.68  5430.8  420.54  5500.9  422.76  5581.1  424.80  5647.4  424.99
#Mann=6,-1,0
  3659.0    0.05       0  4808.8    0.16       0  4996.8    0.07       0
  5002.8    0.16       0  5085.7    0.05       0  5500.9    0.16       0
Bank Sta=4996.8,5002.8
Exp/Cntr=0.3,0.1

Type RM Length L Ch R = 1,6064,685,685,685
BEGIN DESCRIPTION:
WHITE ROCK CREEK 5.0
END DESCRIPTION:
XS GIS Cut Line= 3
      3548403.58     10570178.15      3547125.84     10569205.95
      3545910.51     10569351.79
#Sta/Elev= 30
  3033.2  435.70  3096.7  434.30  3138.3  431.84  3252.7  428.77  3516.7  425.53
  3688.5  422.09  3809.9  421.22  3952.3  418.21  4059.4  417.33  4655.4  416.56
  4692.9  414.98  4773.4  413.79  4974.9  414.70  4980.1  413.50  4985.1  413.66
  4995.0  410.78  5002.1  407.43  5004.8  406.93  5008.1  407.43  5015.2  408.21
  5035.3  414.75  5055.8  416.07  5319.2  419.36  5456.1  423.57  5559.0  426.61
  5589.3  429.05  5619.5  429.36  5659.8  432.21  5740.5  435.70  5862.8  437.04
#Mann=6,-1,0
  3033.2    0.05       0  4655.4    0.16       0  5002.1    0.07       0
  5008.1    0.16       0  5055.8    0.05       0  5456.1    0.16       0
Bank Sta=5002.1,5008.1
Exp/Cntr=0.3,0.1

Type RM Length L Ch R = 1,5379,890,890,890
BEGIN DESCRIPTION:
WHITE ROCK CREEK 3.0
END DESCRIPTION:
XS GIS Cut Line= 4
      3548531.80     10569991.38      3546995.31     10568783.02
      3546870.31     10568616.35      3545797.43     10568809.05
#Sta/Elev= 30
  2728.2  437.72  2962.8  431.44  3041.4  426.61  3275.5  422.32  3817.6  417.00
  3960.4  418.38  4273.1  417.67  4521.6  414.97  4579.4  413.86  4714.6  414.17
  4750.0  413.70  4772.1  412.19  4793.7  413.80  4885.4  412.75  4980.9  413.12
  4991.0  412.40  4998.1  407.84  5000.8  407.34  5004.1  407.84  5011.3  407.97
  5031.7  413.32  5397.2  412.20  5523.8  412.85  5661.6  411.85  5685.9  413.39
  5702.2  412.83  5798.4  416.29  5910.8  423.57  5969.0  425.39  5981.3  425.61
#Mann=6,-1,0
  2728.2    0.05       0  4521.6    0.16       0  4998.1    0.07       0
  5004.1    0.16       0  5523.8    0.05       0  5969.0    0.16       0
Bank Sta=4998.1,5004.1
Exp/Cntr=0.3,0.1

Type RM Length L Ch R = 1,4489,834,834,834
BEGIN DESCRIPTION:
WHITE ROCK CREEK 2.0
END DESCRIPTION:
XS GIS Cut Line= 4
      3548287.07     10567489.48      3546657.49     10567747.56
      3546261.39     10568026.67      3545766.58     10568662.85
#Sta/Elev= 30
  3139.8  450.88  3188.0  451.39  3250.3  449.31  3375.0  440.05  3567.1  428.62
  3742.2  420.77  4013.6  411.55  4258.5  411.90  4335.4  409.90  4714.1  408.44
  4967.7  410.97  4982.5  406.96  4991.2  408.07  4994.3  404.58  4997.0  404.08
  5000.3  404.58  5004.2  405.10  5012.1  409.74  5033.0  410.84  5126.6  409.03
  5241.1  410.05  5270.7  408.94  5377.3  411.57  5505.8  411.74  5655.1  419.00
  5704.8  422.92  5918.4  428.49  5997.1  428.70  6061.4  430.93  6080.2  432.89
#Mann=3,-1,0
  3139.8    0.05       0  4994.3    0.03       0  5000.3    0.05       0
Bank Sta=4994.3,5000.3
Exp/Cntr=0.3,0.1

Type RM Length L Ch R = 1,3655,0,0,0
BEGIN DESCRIPTION:
WHITE ROCK CREEK 1.0
END DESCRIPTION:
XS GIS Cut Line= 5
      3548185.10     10566847.68      3546397.73     10567099.43
      3545983.76     10567295.22      3545852.30     10567395.91
      3545656.81     10568479.48
#Sta/Elev= 30
  2865.3  453.52  3002.9  450.90  3110.7  446.42  3140.3  443.31  3231.9  438.58
  3262.2  433.49  3287.7  430.80  3430.1  420.50  3501.3  416.83  3767.1  409.60
  4864.6  406.85  4986.0  408.84  4991.5  408.08  4997.3  404.86  5005.4  404.58
  5008.1  404.08  5011.4  404.58  5014.3  407.89  5052.6  409.09  5074.8  407.20
  5105.3  406.95  5133.6  408.34  5421.6  409.30  5489.9  410.06  5548.5  412.41
  5602.1  411.90  5714.3  414.07  6109.6  433.82  6356.4  440.69  6394.9  440.60
#Mann=3,-1,0
  2865.3    0.05       0  5005.4    0.03       0  5011.4    0.05       0
Bank Sta=5005.4,5011.4
Exp/Cntr=0.3,0.1

Chan Stop Cuts=-1