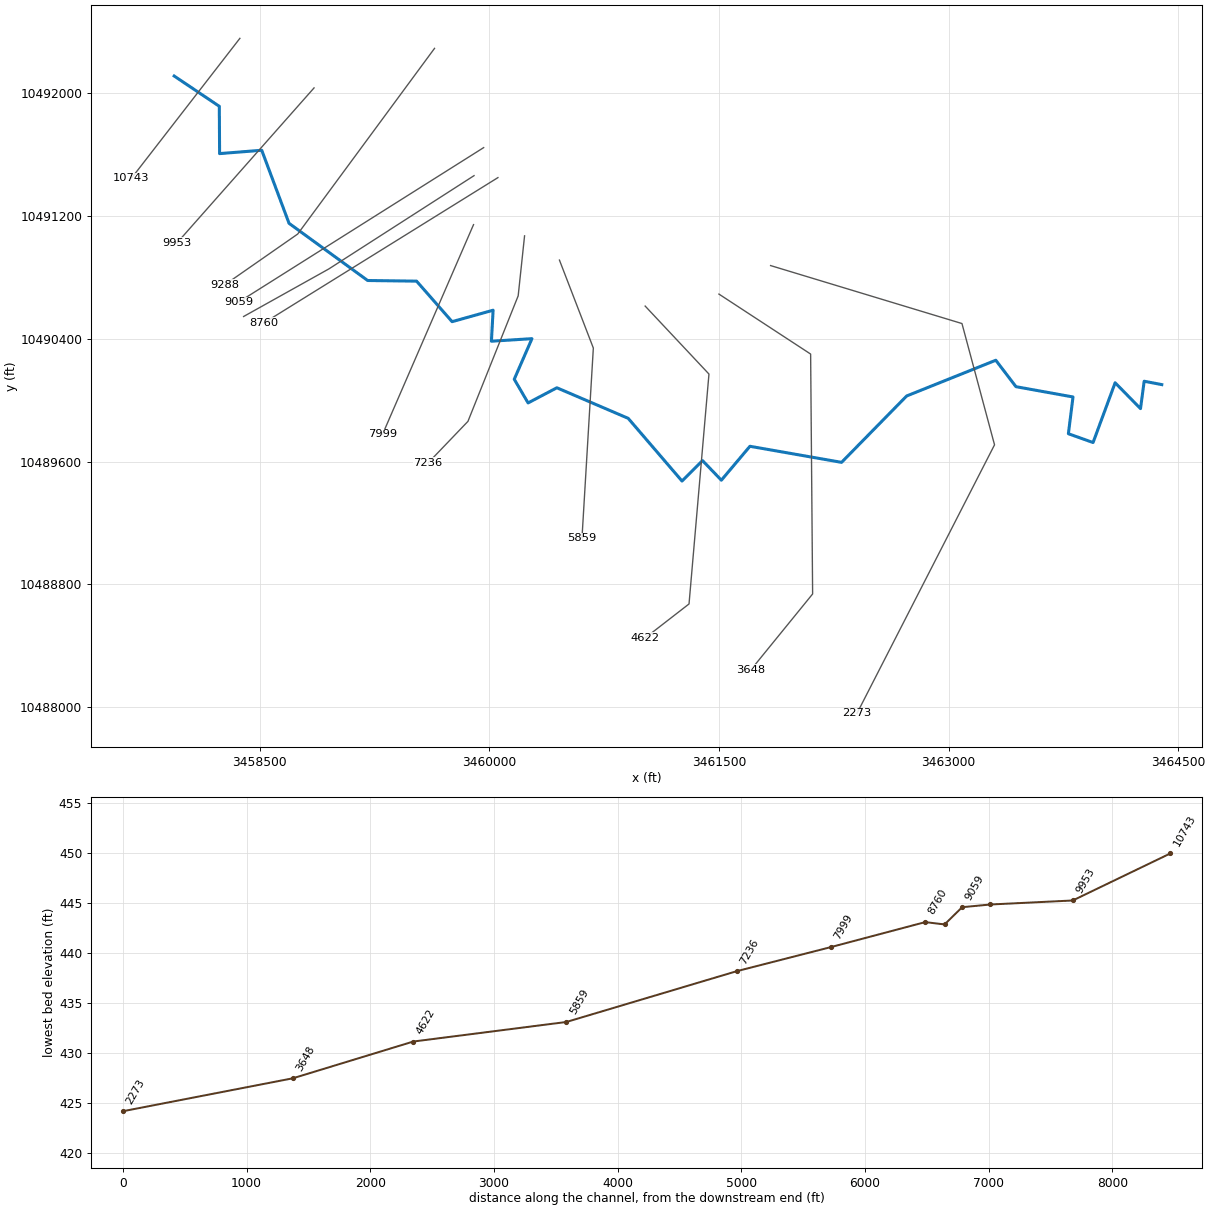
--- ALLIGATOR CREEK.prj (project) ---

Proj Title=ALLIGATOR CREEK Base Level Engineering
Current Plan=p01
Default Exp/Contr=0.3,0.1
English Units
Geom File=g01
Flow File=f01
Plan File=p01
BEGIN DESCRIPTION:
ALLIGATOR CREEK
END DESCRIPTION:

--- ALLIGATOR CREEK.p01 (plan) ---

Plan Title=Multiple Run
Short Identifier=Multiple
Geom File=g01
Flow File=f01
Subcritical Flow
K Sum by GR= 0
Std Step Tol= 0.01
Critical Tol= 0.01
Num of Std Step Trials= 20
Max Error Tol= 0.3
Flow Tol Ratio= 0.001
Split Flow NTrial= 30
Split Flow Tol= 0.02
Split Flow Ratio= 0.02
Log Output Level= 0
Friction Slope Method= 1
Unsteady Friction Slope Method= 2
Unsteady Bridges Friction Slope Method= 1
Parabolic Critical Depth
Global Vel Dist=  1 , 1 , 1
Global Log Level= 0
CheckData=True
Encroach Param= -1, 0, 0, 0
BEGIN DESCRIPTION:
Multiple Run
END DESCRIPTION:

--- ALLIGATOR CREEK.f01 (steady flow) ---

Flow Title=Multiple
Number of Profiles=7
Profile Names=10-year,25-year,50-year,1pct_min,100-year,1pct_plu,500-year
River Rch & RM= ALLIGATOR CREEK,Reach-1,10743
     872    1192    1455    1296    1752    2370    2535
River Rch & RM= ALLIGATOR CREEK,Reach-1,9953
    1261    1751    2157    1935    2617    3540    3847
Boundary for River Rch & Prof#=ALLIGATOR CREEK,Reach-1,1
Up Type=0
Dn Type=3
Dn Slope=0.005
Boundary for River Rch & Prof#=ALLIGATOR CREEK,Reach-1,2
Up Type=0
Dn Type=3
Dn Slope=0.005
Boundary for River Rch & Prof#=ALLIGATOR CREEK,Reach-1,3
Up Type=0
Dn Type=3
Dn Slope=0.005
Boundary for River Rch & Prof#=ALLIGATOR CREEK,Reach-1,4
Up Type=0
Dn Type=3
Dn Slope=0.005
Boundary for River Rch & Prof#=ALLIGATOR CREEK,Reach-1,5
Up Type=0
Dn Type=3
Dn Slope=0.005
Boundary for River Rch & Prof#=ALLIGATOR CREEK,Reach-1,6
Up Type=0
Dn Type=3
Dn Slope=0.005
Boundary for River Rch & Prof#=ALLIGATOR CREEK,Reach-1,7
Up Type=0
Dn Type=3
Dn Slope=0.005

--- ALLIGATOR CREEK.g01 (geometry) ---

Geom Title=Existing Conditions

River Reach=ALLIGATOR CREEK,Reach-1
Reach XY= 30
      3457941.63     10492111.49      3458236.41     10491914.09
      3458238.24     10491606.13      3458513.43     10491627.96
      3458691.74     10491152.17      3459205.37     10490779.59
      3459524.80     10490775.45      3459756.85     10490511.52
      3460024.71     10490586.19      3460013.61     10490384.19
      3460278.44     10490400.82      3460162.78     10490136.63
      3460253.14     10489982.23      3460441.11     10490080.93
      3460907.12     10489881.82      3461258.55     10489473.46
      3461392.45     10489606.70      3461515.59     10489478.99
      3461702.15     10489699.86      3462300.64     10489595.17
      3462725.80     10490027.51      3463308.02     10490260.28
      3463439.60     10490088.11      3463812.43     10490021.10
      3463782.11     10489781.64      3463943.43     10489724.27
      3464087.58     10490113.66      3464253.29     10489945.08
      3464277.19     10490123.50      3464392.11     10490101.64

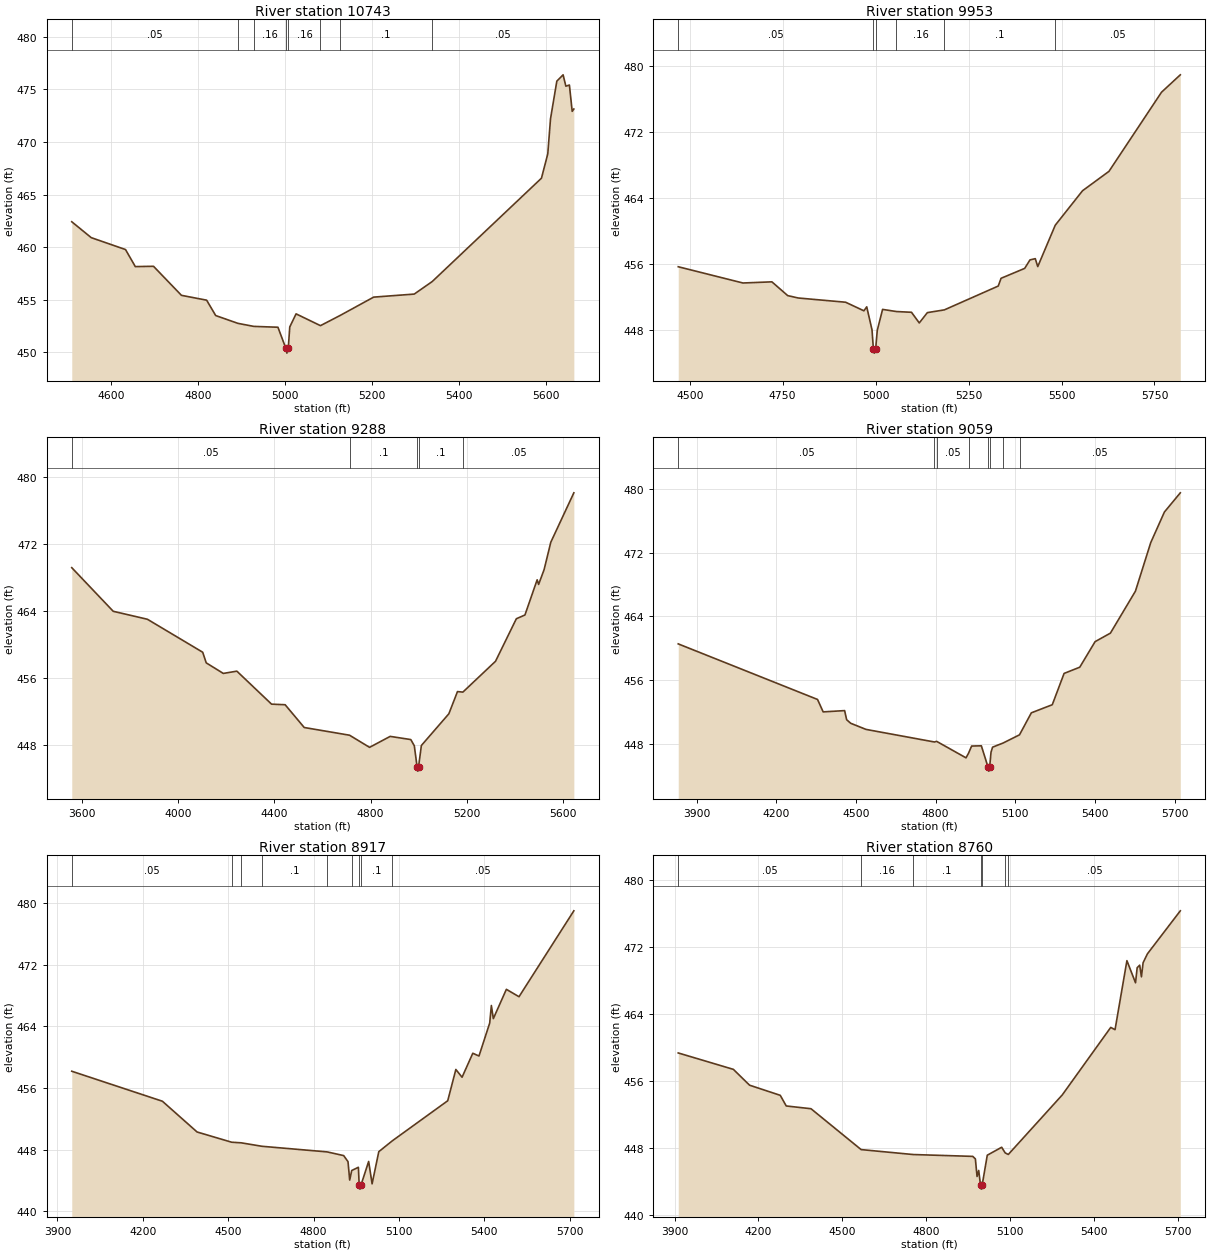
Type RM Length L Ch R = 1,10743,790,790,790
BEGIN DESCRIPTION:
ALLIGATOR CREEK 16.0
END DESCRIPTION:
XS GIS Cut Line= 2
      3458370.72     10492356.94      3457662.84     10491446.06
#Sta/Elev= 30
  4510.2  462.42  4555.0  460.91  4633.7  459.78  4656.2  458.16  4698.0  458.19
  4762.2  455.43  4820.1  454.97  4840.9  453.51  4891.8  452.77  4928.4  452.48
  4983.9  452.40  5001.7  450.44  5004.5  449.94  5007.7  450.44  5011.1  452.43
  5025.6  453.67  5081.6  452.55  5126.4  453.51  5203.8  455.26  5297.1  455.55
  5338.4  456.74  5589.4  466.56  5603.9  468.87  5610.2  472.20  5624.7  475.78
  5639.1  476.38  5645.5  475.30  5653.6  475.41  5660.0  472.91  5663.8  473.13
#Mann=8,-1,0
  4510.2    0.05       0  4891.8     0.1       0  4928.4    0.16       0
  5001.7    0.07       0  5007.7    0.16       0  5081.6    0.05       0
  5126.4     0.1       0  5338.4    0.05       0
Bank Sta=5001.7,5007.7
Exp/Cntr=0.3,0.1

Type RM Length L Ch R = 1,9953,665,665,665
BEGIN DESCRIPTION:
ALLIGATOR CREEK 14.0
END DESCRIPTION:
XS GIS Cut Line= 2
      3458855.13     10492034.07      3457959.27     10491023.62
#Sta/Elev= 30
  4469.1  455.71  4643.2  453.74  4721.0  453.88  4763.6  452.21  4792.1  451.92
  4919.2  451.41  4968.5  450.37  4976.1  450.85  4990.3  448.06  4994.0  445.74
  4996.7  445.24  5000.0  445.74  5004.5  448.01  5018.7  450.54  5056.0  450.28
  5096.5  450.19  5117.4  448.90  5139.2  450.15  5184.8  450.48  5329.8  453.37
  5337.4  454.31  5400.9  455.51  5415.2  456.54  5429.4  456.69  5436.1  455.73
  5483.1  460.74  5556.5  464.92  5627.6  467.27  5768.9  476.86  5819.5  478.97
#Mann=6,-1,0
  4469.1    0.05       0  4994.0   0.035       0  5000.0    0.05       0
  5056.0    0.16       0  5184.8     0.1       0  5483.1    0.05       0
Bank Sta=4994,5000
Exp/Cntr=0.3,0.1

Type RM Length L Ch R = 1,9288,229,229,229
BEGIN DESCRIPTION:
ALLIGATOR CREEK 13.0
END DESCRIPTION:
XS GIS Cut Line= 3
      3459642.08     10492291.61      3458748.34     10491082.29
      3458270.64     10490750.61
#Sta/Elev= 30
  3559.1  469.14  3731.3  463.93  3873.2  462.98  4102.9  459.04  4117.6  457.77
  4188.5  456.51  4244.8  456.78  4388.9  452.84  4445.3  452.77  4524.6  450.05
  4712.8  449.13  4796.0  447.68  4881.6  448.99  4967.2  448.61  4981.8  447.87
  4993.4  445.34  4996.2  444.84  4999.4  445.34  5011.1  447.90  5125.3  451.69
  5161.1  454.34  5183.6  454.28  5319.1  457.96  5405.6  463.04  5441.3  463.49
  5492.0  467.69  5498.1  467.14  5520.9  468.91  5548.7  472.18  5644.4  478.08
#Mann=5,-1,0
  3559.1    0.05       0  4712.8     0.1       0  4993.4    0.07       0
  4999.4     0.1       0  5183.6    0.05       0
Bank Sta=4993.4,4999.4
Exp/Cntr=0.3,0.1

Type RM Length L Ch R = 1,9059,142,142,142
BEGIN DESCRIPTION:
Mapping XS 53ce40a5
END DESCRIPTION:
XS GIS Cut Line= 2
      3459962.93     10491645.15      3458361.38     10490638.21
#Sta/Elev= 30
  3830.0  460.55  4354.9  453.57  4376.1  452.01  4457.0  452.17  4464.5  451.03
  4479.8  450.58  4537.5  449.81  4795.3  448.23  4803.6  448.31  4914.3  446.24
  4923.7  446.81  4935.5  447.72  4972.1  447.75  4997.4  445.07  5000.1  444.57
  5003.4  445.07  5008.6  446.95  5014.5  447.58  5054.8  448.11  5115.9  449.13
  5160.5  451.89  5239.4  452.91  5283.9  456.84  5342.9  457.62  5400.7  460.83
  5458.4  461.90  5552.7  467.17  5610.4  473.27  5661.9  477.11  5721.8  479.52
#Mann=8,-1,0
  3830.0    0.05       0  4795.3     0.1       0  4803.6    0.05       0
  4923.7     0.1       0  4997.4    0.07       0  5003.4     0.1       0
  5054.8    0.16       0  5115.9    0.05       0
Bank Sta=4997.4,5003.4
Exp/Cntr=0.3,0.1

Type RM Length L Ch R = 1,8917,157,157,157
BEGIN DESCRIPTION:
ALLIGATOR CREEK 12.0
END DESCRIPTION:
XS GIS Cut Line= 3
      3459900.15     10491462.62      3458952.02     10490855.17
      3458395.03     10490545.13
#Sta/Elev= 30
  3950.6  458.18  4268.9  454.28  4390.8  450.28  4512.2  448.95  4546.0  448.87
  4618.9  448.42  4847.9  447.69  4905.7  447.21  4920.9  446.42  4926.8  444.03
  4933.9  445.27  4957.3  445.69  4960.2  443.35  4962.9  442.85  4966.2  443.35
  4993.4  446.45  5005.5  443.54  5029.0  447.72  5076.8  449.14  5271.1  454.34
  5299.7  458.41  5321.5  457.40  5359.2  460.52  5380.9  460.16  5418.6  464.45
  5424.4  466.73  5431.3  465.02  5477.1  468.83  5521.5  467.87  5714.1  479.04
#Mann=9,-1,0
  3950.6    0.05       0  4512.2     0.1       0  4546.0    0.16       0
  4618.9     0.1       0  4847.9    0.16       0  4933.9     0.1       0
  4960.2    0.07       0  4966.2     0.1       0  5076.8    0.05       0
Bank Sta=4960.2,4966.2
Exp/Cntr=0.3,0.1

Type RM Length L Ch R = 1,8760,761,761,761
BEGIN DESCRIPTION:
Mapping XS 54018d28
END DESCRIPTION:
XS GIS Cut Line= 2
      3460056.22     10491449.82      3458528.48     10490503.66
#Sta/Elev= 30
  3912.9  459.34  4110.3  457.38  4168.2  455.49  4278.1  454.28  4299.4  453.01
  4388.1  452.68  4567.5  447.80  4753.9  447.21  4967.0  446.99  4976.4  446.69
  4982.4  444.59  4988.3  445.31  4994.8  443.58  4997.5  443.08  5000.8  443.58
  5019.0  447.13  5070.5  448.08  5083.2  447.40  5094.3  447.22  5287.2  454.32
  5460.9  462.39  5476.3  462.12  5518.8  470.36  5549.6  467.72  5555.5  469.52
  5564.5  469.82  5570.8  468.43  5576.7  470.11  5592.1  471.17  5709.9  476.31
#Mann=7,-1,0
  3912.9    0.05       0  4567.5    0.16       0  4753.9     0.1       0
  4994.8    0.07       0  5000.8     0.1       0  5083.2    0.16       0
  5094.3    0.05       0
Bank Sta=4994.8,5000.8
Exp/Cntr=0.3,0.1

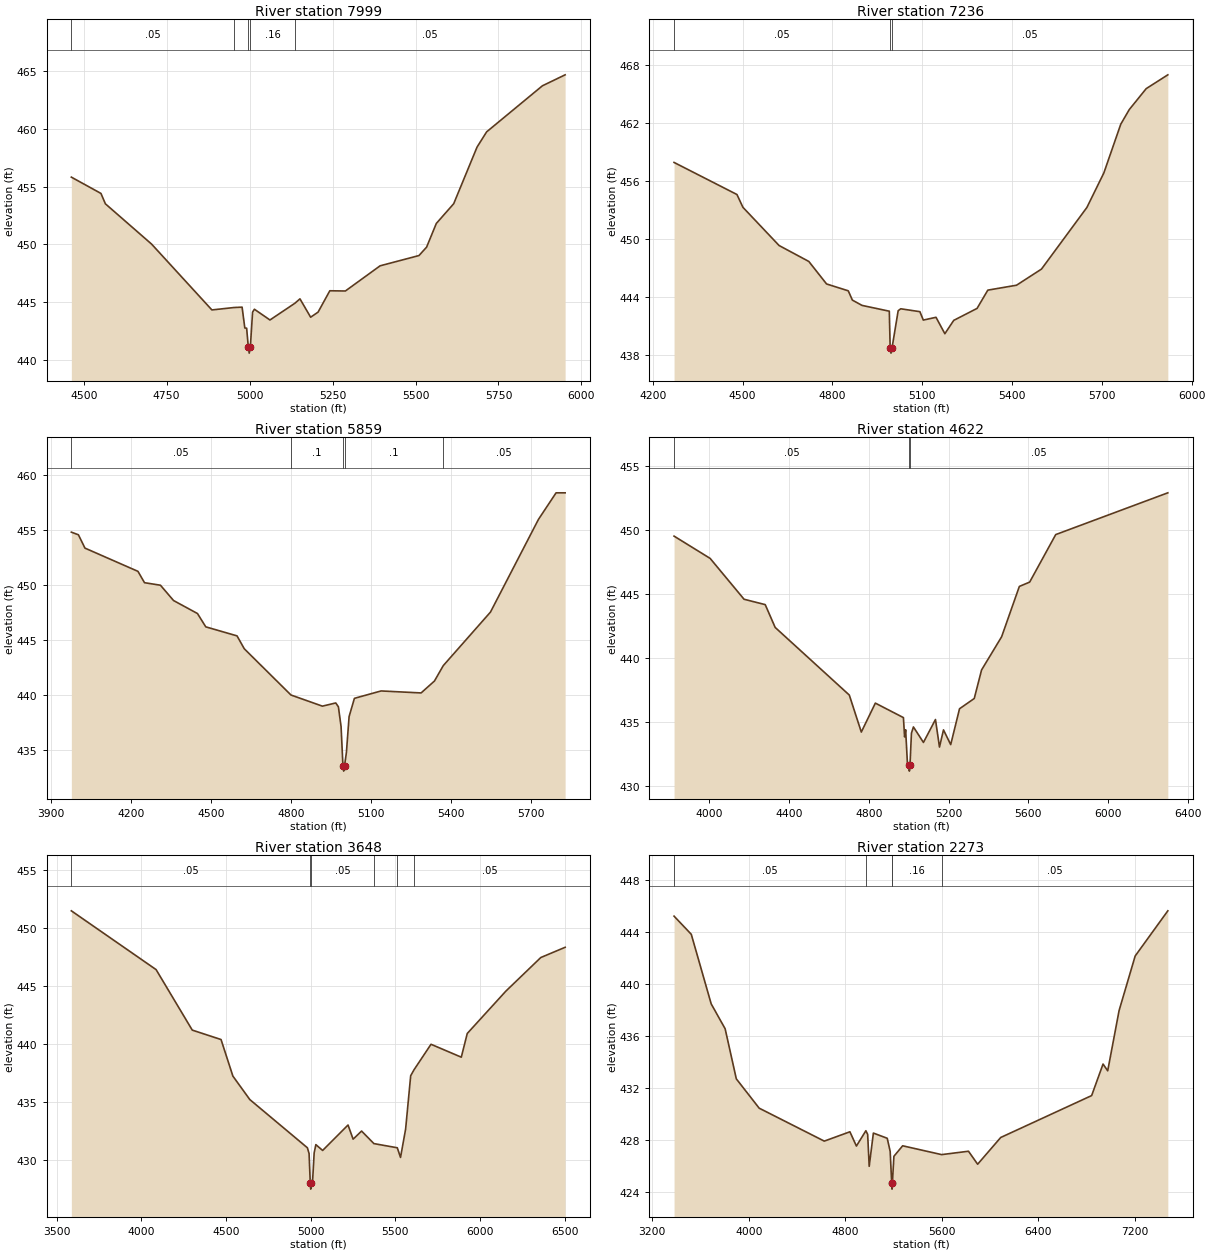
Type RM Length L Ch R = 1,7999,763,763,763
BEGIN DESCRIPTION:
ALLIGATOR CREEK 11.0
END DESCRIPTION:
XS GIS Cut Line= 2
      3459896.81     10491143.47      3459303.04     10489778.85
#Sta/Elev= 30
  4462.7  455.83  4551.9  454.42  4565.3  453.52  4704.6  450.03  4886.3  444.33
  4953.4  444.54  4977.3  444.57  4985.5  442.77  4991.0  442.75  4996.1  441.09
  4998.8  440.59  5002.1  441.09  5008.9  444.14  5014.4  444.39  5061.3  443.46
  5136.5  444.91  5151.7  445.29  5183.9  443.70  5206.3  444.14  5241.7  445.99
  5288.6  445.97  5393.2  448.15  5510.4  449.04  5533.4  449.77  5562.7  451.82
  5615.1  453.53  5685.4  458.43  5714.3  459.75  5882.4  463.74  5950.9  464.69
#Mann=5,-1,0
  4462.7    0.05       0  4953.4    0.16       0  4996.1    0.07       0
  5002.1    0.16       0  5136.5    0.05       0
Bank Sta=4996.1,5002.1
Exp/Cntr=0.3,0.1

Type RM Length L Ch R = 1,7236,1377,1377,1377
BEGIN DESCRIPTION:
ALLIGATOR CREEK 9.0
END DESCRIPTION:
XS GIS Cut Line= 4
      3460230.13     10491070.52      3460188.46     10490679.89
      3459860.34     10489862.19      3459599.95     10489591.39
#Sta/Elev= 30
  4270.8  457.92  4480.9  454.60  4501.0  453.27  4621.7  449.32  4721.0  447.67
  4780.3  445.34  4852.8  444.63  4866.5  443.67  4898.8  443.12  4989.9  442.52
  4992.8  438.68  4995.5  438.18  4998.8  438.68  5019.5  442.57  5028.1  442.77
  5092.1  442.47  5103.5  441.60  5145.9  441.89  5175.5  440.19  5205.1  441.57
  5283.1  442.81  5319.0  444.70  5414.9  445.21  5498.3  446.88  5650.0  453.26
  5706.6  456.83  5763.2  461.88  5791.5  463.39  5848.1  465.56  5920.4  466.99
#Mann=3,-1,0
  4270.8    0.05       0  4992.8   0.035       0  4998.8    0.05       0
Bank Sta=4992.8,4998.8
Exp/Cntr=0.3,0.1

Type RM Length L Ch R = 1,5859,1237,1237,1237
BEGIN DESCRIPTION:
ALLIGATOR CREEK 8.0
END DESCRIPTION:
XS GIS Cut Line= 3
      3460457.98     10490912.55      3460679.35     10490339.62
      3460605.13     10489101.75
#Sta/Elev= 30
  3975.6  454.81  4002.1  454.57  4026.7  453.36  4225.7  451.25  4250.3  450.22
  4310.2  449.99  4359.4  448.60  4449.2  447.42  4480.4  446.21  4597.8  445.39
  4625.0  444.22  4800.4  440.02  4918.4  439.01  4968.5  439.30  4978.5  438.95
  4988.5  437.15  4995.5  433.61  4998.3  433.11  5001.5  433.61  5008.5  434.79
  5018.6  438.06  5038.6  439.72  5138.8  440.39  5289.0  440.21  5339.1  441.29
  5372.3  442.69  5549.5  447.55  5729.8  455.97  5795.9  458.38  5829.9  458.38
#Mann=5,-1,0
  3975.6    0.05       0  4800.4     0.1       0  4995.5    0.07       0
  5001.5     0.1       0  5372.3    0.05       0
Bank Sta=4995.5,5001.5
Exp/Cntr=0.3,0.1

Type RM Length L Ch R = 1,4622,974,974,974
BEGIN DESCRIPTION:
ALLIGATOR CREEK 5.0
END DESCRIPTION:
XS GIS Cut Line= 4
      3461017.86     10490613.08      3461434.55     10490170.34
      3461304.35     10488672.95      3461017.85     10488451.57
#Sta/Elev= 30
  3825.2  449.51  4005.9  447.77  4175.8  444.58  4281.8  444.16  4331.6  442.38
  4702.9  437.10  4763.1  434.21  4833.4  436.47  4973.9  435.34  4979.9  433.83
  4985.0  434.39  4994.0  431.77  5001.0  431.66  5003.8  431.16  5007.0  431.66
  5014.1  434.12  5024.1  434.61  5074.3  433.40  5134.5  435.19  5154.6  433.04
  5174.7  434.38  5210.8  433.23  5255.0  436.03  5328.7  436.83  5365.4  439.06
  5465.8  441.65  5554.6  445.58  5606.3  445.92  5736.8  449.63  6298.3  452.89
#Mann=3,-1,0
  3825.2    0.05       0  5001.0   0.035       0  5007.0    0.05       0
Bank Sta=5001,5007
Exp/Cntr=0.3,0.1

Type RM Length L Ch R = 1,3648,1375,1375,1375
BEGIN DESCRIPTION:
ALLIGATOR CREEK 2.0
END DESCRIPTION:
XS GIS Cut Line= 4
      3461499.69     10490691.16      3462098.62     10490300.55
      3462111.64     10488738.05      3461708.02     10488243.30
#Sta/Elev= 30
  3586.1  451.45  4086.5  446.39  4300.2  441.18  4470.1  440.37  4540.1  437.22
  4640.1  435.20  4980.1  431.05  4990.1  430.55  4997.1  427.99  4999.8  427.49
  5003.1  427.99  5010.1  428.03  5020.1  430.61  5030.1  431.32  5070.1  430.82
  5220.1  433.01  5250.1  431.79  5300.1  432.49  5372.8  431.41  5511.0  431.05
  5530.1  430.22  5560.1  432.65  5590.1  437.25  5609.1  437.75  5710.1  439.96
  5889.0  438.85  5924.2  440.89  6152.5  444.54  6358.6  447.43  6502.2  448.31
#Mann=6,-1,0
  3586.1    0.05       0  4997.1   0.035       0  5003.1    0.05       0
  5372.8     0.1       0  5511.0    0.16       0  5609.1    0.05       0
Bank Sta=4997.1,5003.1
Exp/Cntr=0.3,0.1

Type RM Length L Ch R = 1,2273,0,0,0
BEGIN DESCRIPTION:
ALLIGATOR CREEK 1.0
END DESCRIPTION:
XS GIS Cut Line= 4
      3461837.10     10490876.89      3463087.10     10490499.28
      3463299.77     10489709.35      3462401.35     10487960.24
#Sta/Elev= 30
  3381.5  445.24  3524.2  443.84  3689.0  438.48  3804.6  436.56  3897.2  432.70
  4086.6  430.44  4625.9  427.90  4838.1  428.62  4892.0  427.52  4970.4  428.70
  4985.2  428.42  4997.9  425.96  5032.6  428.52  5147.3  428.12  5171.6  427.11
  5184.2  424.70  5187.0  424.20  5190.2  424.70  5202.6  426.73  5275.1  427.54
  5597.8  426.86  5820.4  427.12  5896.2  426.12  6087.4  428.18  6840.6  431.41
  6935.0  433.84  6973.7  433.32  7068.1  437.97  7201.2  442.17  7471.7  445.65
#Mann=5,-1,0
  3381.5    0.05       0  4970.4    0.16       0  5184.2    0.07       0
  5190.2    0.16       0  5597.8    0.05       0
Bank Sta=5184.2,5190.2
Exp/Cntr=0.3,0.1

Chan Stop Cuts=-1