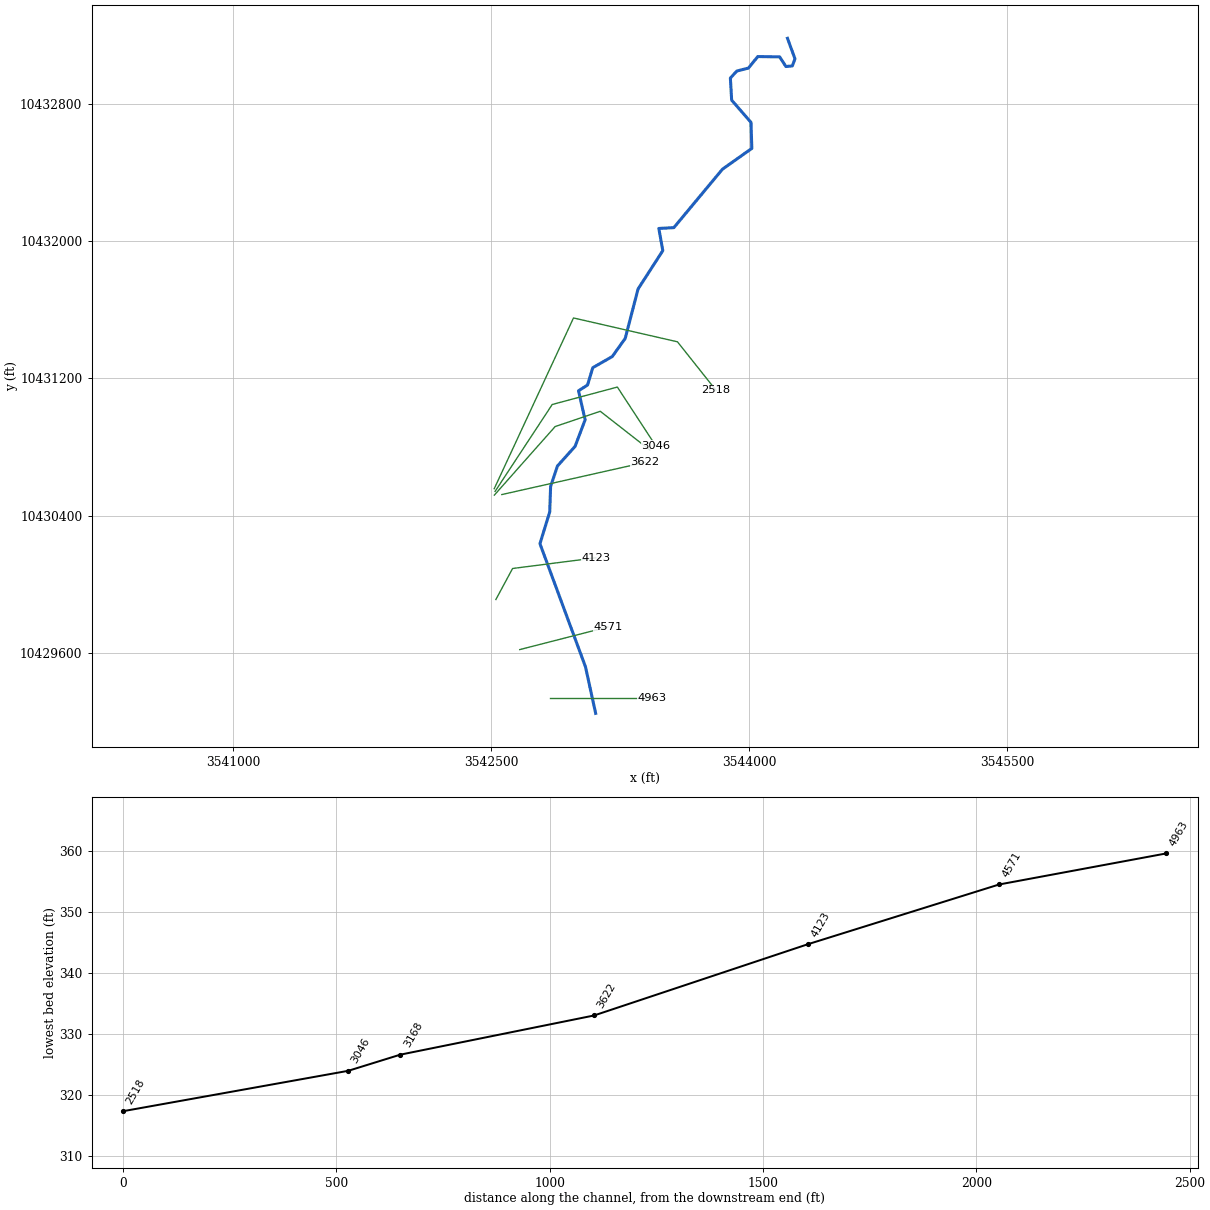
--- BEAR CREEK EAST TRIB 3.prj (project) ---

Proj Title=BEAR CREEK EAST TRIB 3 Base Level Engineering
Current Plan=p01
Default Exp/Contr=0.3,0.1
English Units
Geom File=g01
Flow File=f01
Plan File=p01
BEGIN DESCRIPTION:
BEAR CREEK EAST TRIB 3
END DESCRIPTION:

--- BEAR CREEK EAST TRIB 3.p01 (plan) ---

Plan Title=Multiple Run
Short Identifier=Multiple
Geom File=g01
Flow File=f01
Subcritical Flow
K Sum by GR= 0
Std Step Tol= 0.01
Critical Tol= 0.01
Num of Std Step Trials= 20
Max Error Tol= 0.3
Flow Tol Ratio= 0.001
Split Flow NTrial= 30
Split Flow Tol= 0.02
Split Flow Ratio= 0.02
Log Output Level= 0
Friction Slope Method= 1
Unsteady Friction Slope Method= 2
Unsteady Bridges Friction Slope Method= 1
Parabolic Critical Depth
Global Vel Dist=  1 , 1 , 1
Global Log Level= 0
CheckData=True
Encroach Param= -1, 0, 0, 0
BEGIN DESCRIPTION:
Multiple Run
END DESCRIPTION:

--- BEAR CREEK EAST TRIB 3.f01 (steady flow) ---

Flow Title=Multiple
Number of Profiles=7
Profile Names=10-year,25-year,50-year,1pct_min,100-year,1pct_plu,500-year
River Rch & RM= BEAR CREEK EAST ,Reach-1,4963
     548     734     883     779    1054    1425    1492
Boundary for River Rch & Prof#=BEAR CREEK EAST ,Reach-1,1
Up Type=0
Dn Type=3
Dn Slope=0.005
Boundary for River Rch & Prof#=BEAR CREEK EAST ,Reach-1,2
Up Type=0
Dn Type=3
Dn Slope=0.005
Boundary for River Rch & Prof#=BEAR CREEK EAST ,Reach-1,3
Up Type=0
Dn Type=3
Dn Slope=0.005
Boundary for River Rch & Prof#=BEAR CREEK EAST ,Reach-1,4
Up Type=0
Dn Type=3
Dn Slope=0.005
Boundary for River Rch & Prof#=BEAR CREEK EAST ,Reach-1,5
Up Type=0
Dn Type=3
Dn Slope=0.005
Boundary for River Rch & Prof#=BEAR CREEK EAST ,Reach-1,6
Up Type=0
Dn Type=3
Dn Slope=0.005
Boundary for River Rch & Prof#=BEAR CREEK EAST ,Reach-1,7
Up Type=0
Dn Type=3
Dn Slope=0.005

--- BEAR CREEK EAST TRIB 3.g01 (geometry) ---

Geom Title=Existing Conditions

River Reach=BEAR CREEK EAST ,Reach-1
Reach XY= 30
      3543107.88     10429249.33      3543048.80     10429520.27
      3542783.89     10430237.54      3542840.71     10430422.31
      3542845.85     10430570.44      3542885.58     10430689.67
      3542988.10     10430804.05      3543046.60     10430958.61
      3543008.19     10431127.73      3543060.71     10431161.37
      3543091.09     10431262.28      3543204.38     10431327.17
      3543279.62     10431432.30      3543354.63     10431720.70
      3543498.50     10431943.92      3543475.38     10432073.10
      3543562.74     10432077.92      3543845.53     10432418.27
      3544016.31     10432539.05      3544011.59     10432690.60
      3543898.96     10432820.16      3543891.58     10432948.63
      3543928.90     10432989.87      3543996.61     10433007.01
      3544051.08     10433074.07      3544178.04     10433072.29
      3544214.70     10433016.10      3544251.99     10433019.67
      3544267.39     10433060.91      3544223.70     10433180.19

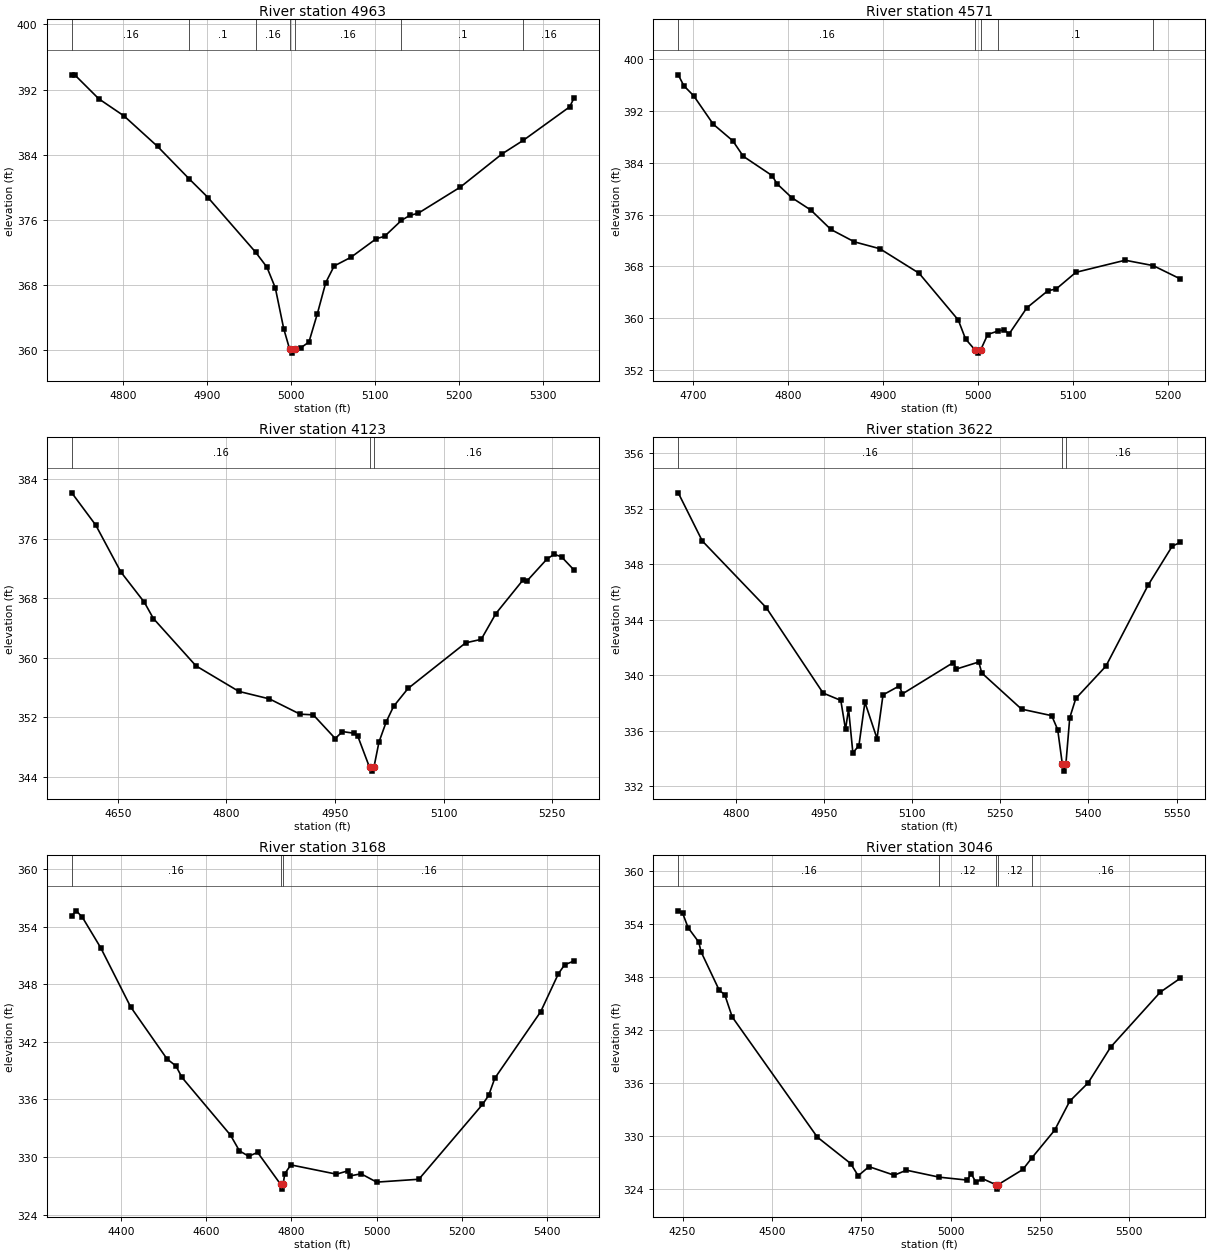
Type RM Length L Ch R = 1,4963,392,392,392
BEGIN DESCRIPTION:
BEAR CREEK EAST TRIB 3 5.0
END DESCRIPTION:
XS GIS Cut Line= 2
      3542840.02     10429336.03      3543437.22     10429336.03
#Sta/Elev= 30
  4739.3  393.81  4742.8  393.81  4771.4  390.87  4801.4  388.77  4841.4  385.02
  4879.1  381.03  4901.4  378.75  4958.0  372.05  4971.4  370.22  4981.4  367.68
  4991.4  362.67  4998.4  360.17  5001.1  359.67  5004.4  360.17  5011.4  360.30
  5021.4  361.03  5031.4  364.50  5041.4  368.32  5051.4  370.36  5071.4  371.43
  5101.4  373.70  5111.4  374.00  5131.4  375.95  5141.4  376.57  5151.4  376.83
  5201.4  380.03  5251.4  384.13  5276.6  385.79  5331.4  389.87  5336.5  390.91
#Mann=7,-1,0
  4739.3    0.16       0  4879.1     0.1       0  4958.0    0.16       0
  4998.4    0.07       0  5004.4    0.16       0  5131.4     0.1       0
  5276.6    0.16       0
Bank Sta=4998.4,5004.4
Exp/Cntr=0.3,0.1

Type RM Length L Ch R = 1,4571,448,448,448
BEGIN DESCRIPTION:
BEAR CREEK EAST TRIB 3 4.0
END DESCRIPTION:
XS GIS Cut Line= 2
      3542666.38     10429620.75      3543178.66     10429752.28
#Sta/Elev= 30
  4684.2  397.62  4690.1  395.93  4700.4  394.39  4721.1  389.98  4741.7  387.41
  4752.7  385.02  4783.0  382.04  4788.3  380.76  4803.7  378.63  4823.9  376.70
  4845.0  373.70  4869.8  371.78  4896.6  370.72  4937.9  366.93  4979.2  359.69
  4986.9  356.75  4996.8  355.07  4999.6  354.57  5002.8  355.07  5010.2  357.45
  5021.4  358.01  5027.6  358.15  5032.8  357.55  5051.5  361.59  5073.5  364.21
  5082.4  364.50  5103.1  367.07  5155.0  368.94  5184.5  368.11  5213.1  366.05
#Mann=5,-1,0
  4684.2    0.16       0  4996.8    0.07       0  5002.8    0.16       0
  5021.4     0.1       0  5184.5    0.16       0
Bank Sta=4996.8,5002.8
Exp/Cntr=0.3,0.1

Type RM Length L Ch R = 1,4123,501,501,501
BEGIN DESCRIPTION:
BEAR CREEK EAST TRIB 3 3.0
END DESCRIPTION:
XS GIS Cut Line= 3
      3542527.51     10429912.40      3542624.74     10430092.98
      3543108.96     10430155.23
#Sta/Elev= 30
  4586.4  382.15  4619.6  377.80  4654.1  371.53  4686.6  367.45  4699.1  365.27
  4757.9  358.91  4817.1  355.48  4859.4  354.47  4901.7  352.42  4919.9  352.33
  4950.2  349.15  4960.2  350.08  4976.2  349.86  4981.3  349.48  4997.6  345.27
  5000.3  344.77  5003.6  345.27  5010.6  348.67  5020.7  351.41  5030.8  353.47
  5050.7  355.87  5130.3  362.00  5151.8  362.47  5172.0  365.93  5209.8  370.48
  5214.8  370.29  5242.5  373.25  5252.6  373.90  5262.7  373.55  5279.7  371.81
#Mann=3,-1,0
  4586.4    0.16       0  4997.6    0.07       0  5003.6    0.16       0
Bank Sta=4997.6,5003.6
Exp/Cntr=0.3,0.1

Type RM Length L Ch R = 1,3622,454,454,454
BEGIN DESCRIPTION:
BEAR CREEK EAST TRIB 3 2.0
END DESCRIPTION:
XS GIS Cut Line= 2
      3542562.22     10430523.53      3543395.59     10430711.03
#Sta/Elev= 30
  4702.2  353.15  4743.1  349.68  4851.9  344.87  4948.7  338.71  4978.8  338.18
  4986.8  336.09  4992.0  337.56  4999.3  334.40  5009.6  334.92  5019.8  338.05
  5040.4  335.43  5050.6  338.58  5078.5  339.23  5083.6  338.65  5170.2  340.91
  5175.3  340.44  5213.5  340.95  5218.6  340.16  5286.3  337.55  5337.6  337.08
  5347.8  336.07  5355.7  333.58  5358.4  333.08  5361.7  333.58  5368.3  336.93
  5378.6  338.32  5429.8  340.65  5501.6  346.49  5542.6  349.30  5556.4  349.58
#Mann=3,-1,0
  4702.2    0.16       0  5355.7    0.07       0  5361.7    0.16       0
Bank Sta=5355.7,5361.7
Exp/Cntr=0.3,0.1

Type RM Length L Ch R = 1,3168,122,122,122
BEGIN DESCRIPTION:
Mapping XS 2ffae
END DESCRIPTION:
XS GIS Cut Line= 4
      3542518.45     10430520.18      3542872.18     10430919.48
      3543134.76     10431008.46      3543423.40     10430782.75
#Sta/Elev= 30
  4285.3  355.19  4296.1  355.68  4310.4  354.99  4353.0  351.84  4423.3  345.66
  4508.6  340.23  4529.5  339.50  4543.7  338.30  4657.5  332.28  4678.4  330.64
  4700.1  330.08  4721.0  330.48  4774.9  327.15  4777.7  326.65  4780.9  327.15
  4784.6  328.25  4798.8  329.18  4905.9  328.21  4932.0  328.55  4937.3  328.02
  4963.5  328.25  5000.2  327.38  5099.0  327.68  5248.2  335.48  5262.6  336.42
  5277.1  338.22  5384.6  345.15  5426.3  349.13  5440.8  350.05  5462.4  350.44
#Mann=3,-1,0
  4285.3    0.16       0  4774.9    0.07       0  4780.9    0.16       0
Bank Sta=4774.9,4780.9
Exp/Cntr=0.3,0.1

Type RM Length L Ch R = 1,3046,528,528,528
BEGIN DESCRIPTION:
Mapping XS 2ffae7d9
END DESCRIPTION:
XS GIS Cut Line= 4
      3542523.01     10430542.17      3542855.27     10431047.96
      3543234.18     10431149.52      3543456.82     10430808.40
#Sta/Elev= 30
  4237.8  355.45  4250.2  355.18  4265.3  353.55  4295.5  351.90  4301.4  350.84
  4352.7  346.46  4367.8  345.99  4388.8  343.46  4626.9  329.88  4720.3  326.89
  4741.3  325.51  4771.5  326.54  4842.2  325.57  4876.2  326.14  4968.3  325.35
  5046.7  325.02  5057.1  325.75  5071.1  324.77  5088.2  325.20  5126.6  324.50
  5129.3  324.00  5132.6  324.50  5202.0  326.22  5228.0  327.57  5291.0  330.66
  5333.2  333.94  5384.5  336.00  5447.7  340.05  5586.6  346.26  5642.6  347.83
#Mann=5,-1,0
  4237.8    0.16       0  4968.3    0.12       0  5126.6    0.07       0
  5132.6    0.12       0  5228.0    0.16       0
Bank Sta=5126.6,5132.6
Exp/Cntr=0.3,0.1

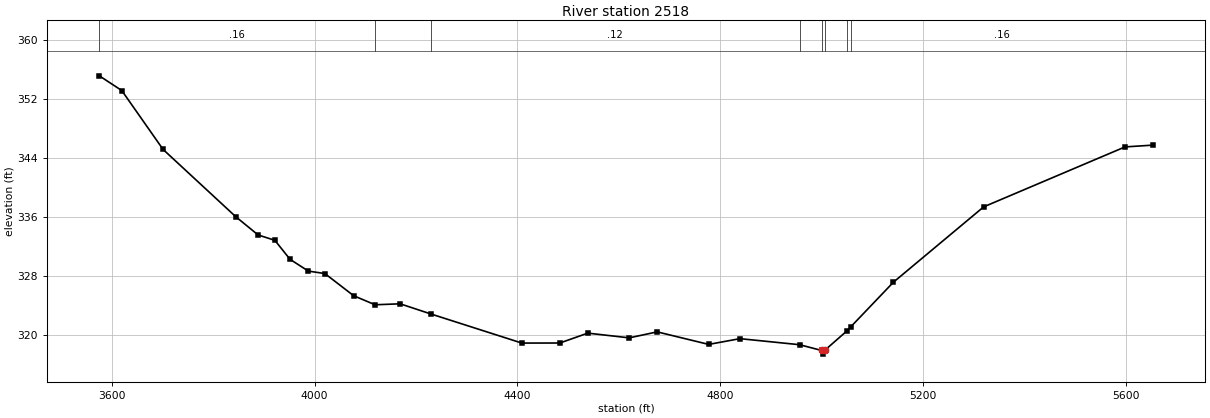
Type RM Length L Ch R = 1,2518,0,0,0
BEGIN DESCRIPTION:
Mapping XS 46ca7a17
END DESCRIPTION:
XS GIS Cut Line= 4
      3542517.92     10430557.59      3542979.02     10431552.00
      3543583.86     10431412.96      3543808.30     10431130.26
#Sta/Elev= 30
  3575.5  355.15  3619.8  353.15  3701.2  345.16  3844.5  336.03  3888.6  333.55
  3921.7  332.82  3951.6  330.24  3987.8  328.64  4020.3  328.31  4077.1  325.30
  4119.3  324.07  4168.8  324.20  4229.5  322.82  4408.9  318.87  4483.8  318.88
  4538.9  320.22  4620.6  319.58  4675.8  320.39  4777.4  318.69  4839.0  319.47
  4956.5  318.65  5000.0  317.87  5002.7  317.37  5006.0  317.87  5049.8  320.51
  5057.8  321.09  5141.8  327.14  5319.7  337.36  5598.5  345.50  5653.2  345.74
#Mann=8,-1,0
  3575.5    0.16       0  4119.3    0.05       0  4229.5    0.12       0
  4956.5    0.05       0  5000.0    0.04       0  5006.0    0.05       0
  5049.8    0.12       0  5057.8    0.16       0
Bank Sta=5000,5006
Exp/Cntr=0.3,0.1

Chan Stop Cuts=-1