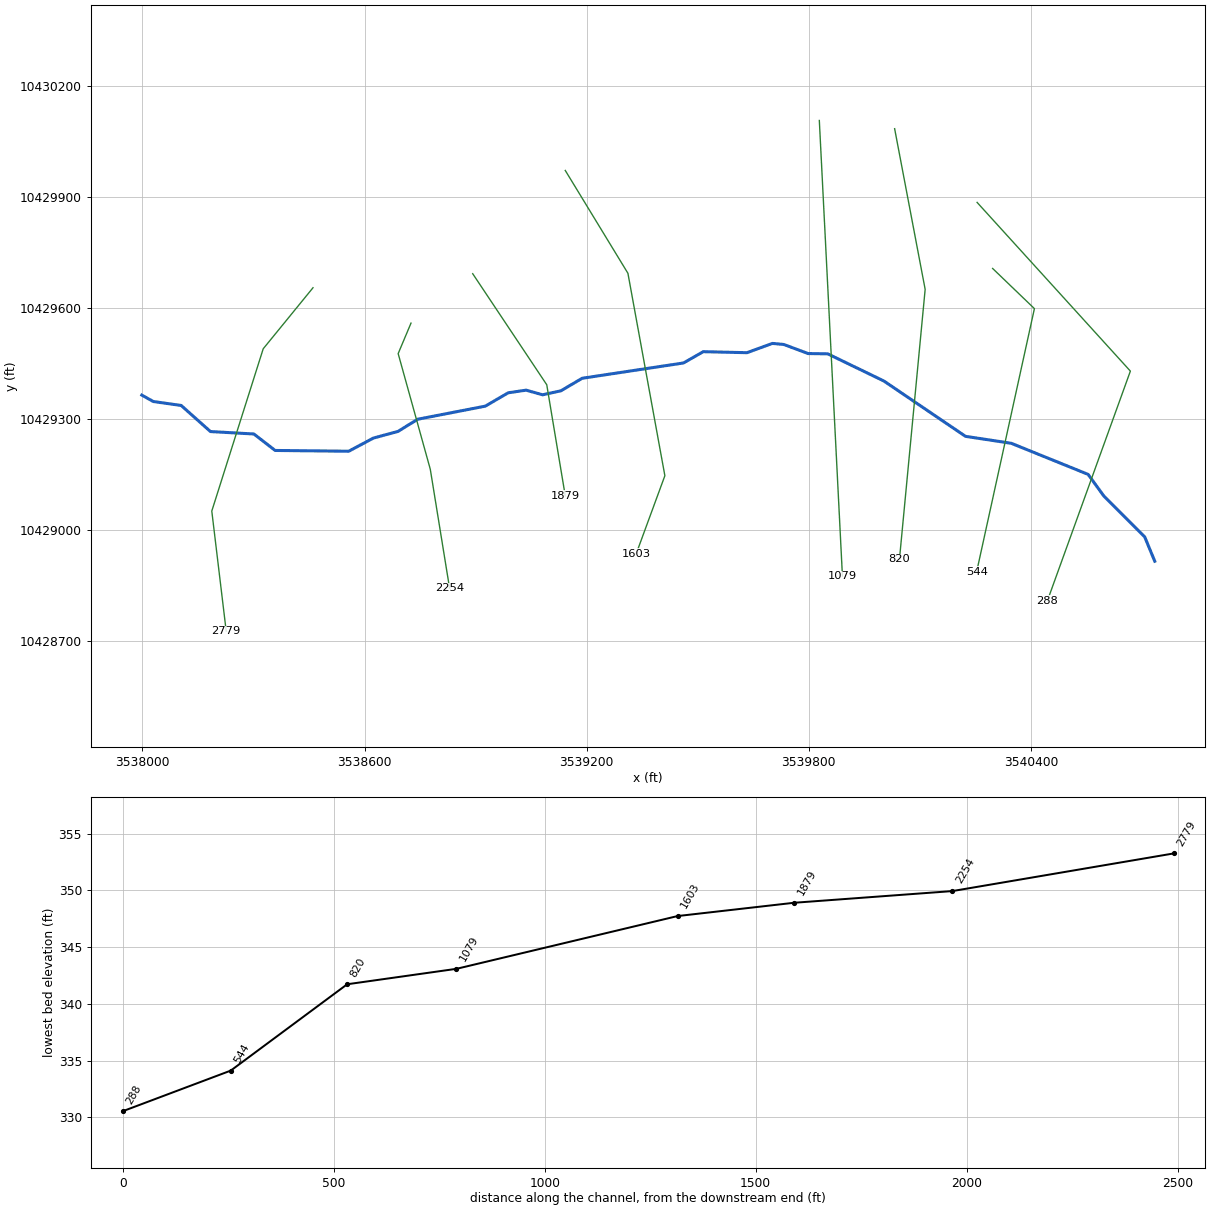
--- BEAR CREEK EAST TRIB 4.prj (project) ---

Proj Title=BEAR CREEK EAST TRIB 4 Base Level Engineering
Current Plan=p01
Default Exp/Contr=0.3,0.1
English Units
Geom File=g01
Flow File=f01
Plan File=p01
Y Axis Title=Elevation
X Axis Title(PF)=Main Channel Distance
X Axis Title(XS)=Station
BEGIN DESCRIPTION:
BEAR CREEK EAST TRIB 4
END DESCRIPTION:
DSS Export Rating Curves= 0
DSS Export Rating Curve Sorted= 0
DSS Export Volume Flow Curves= 0
DXF OffsetX= 0
DXF OffsetY= 0
DXF ScaleX= 1
DXF ScaleY= 10

--- BEAR CREEK EAST TRIB 4.p01 (plan) ---

Plan Title=Multiple Run
Short Identifier=Multiple
Geom File=g01
Flow File=f01
Subcritical Flow
K Sum by GR= 0
Std Step Tol= 0.01
Critical Tol= 0.01
Num of Std Step Trials= 20
Max Error Tol= 0.3
Flow Tol Ratio= 0.001
Split Flow NTrial= 30
Split Flow Tol= 0.02
Split Flow Ratio= 0.02
Log Output Level= 0
Friction Slope Method= 1
Unsteady Friction Slope Method= 2
Unsteady Bridges Friction Slope Method= 1
Parabolic Critical Depth
Global Vel Dist=  1 , 1 , 1
Global Log Level= 0
CheckData=True
Encroach Param= -1, 0, 0, 0
BEGIN DESCRIPTION:
Multiple Run
END DESCRIPTION:

--- BEAR CREEK EAST TRIB 4.f01 (steady flow) ---

Flow Title=Multiple
Program Version=4.10
Number of Profiles= 7
Profile Names=10-year,25-year,50-year,1pct_min,100-year,1pct_plu,500-year
River Rch & RM=BEAR CREEK EAST,Reach-1         ,2779
    1003    1395    1724    1556    2104    2846    3125
Boundary for River Rch & Prof#=BEAR CREEK EAST,Reach-1         , 1
Up Type= 0
Dn Type= 3
Dn Slope=0.0145
Boundary for River Rch & Prof#=BEAR CREEK EAST,Reach-1         , 2
Up Type= 0
Dn Type= 3
Dn Slope=0.0145
Boundary for River Rch & Prof#=BEAR CREEK EAST,Reach-1         , 3
Up Type= 0
Dn Type= 3
Dn Slope=0.0145
Boundary for River Rch & Prof#=BEAR CREEK EAST,Reach-1         , 4
Up Type= 0
Dn Type= 3
Dn Slope=0.0145
Boundary for River Rch & Prof#=BEAR CREEK EAST,Reach-1         , 5
Up Type= 0
Dn Type= 3
Dn Slope=0.0145
Boundary for River Rch & Prof#=BEAR CREEK EAST,Reach-1         , 6
Up Type= 0
Dn Type= 3
Dn Slope=0.0145
Boundary for River Rch & Prof#=BEAR CREEK EAST,Reach-1         , 7
Up Type= 0
Dn Type= 3
Dn Slope=0.0145
DSS Import GetInterval= 0
DSS Import GetPeak= 0
DSS Import FillOption= 0

--- BEAR CREEK EAST TRIB 4.g01 (geometry) ---

Geom Title=Existing Conditions
Program Version=4.10

River Reach=BEAR CREEK EAST ,Reach-1
Reach XY= 30
      3537998.21     10429363.67      3538029.46     10429346.31
      3538104.57     10429335.71       3538183.6     10429265.24
      3538300.95     10429258.65       3538358.4     10429214.17
      3538557.25      10429212.1      3538623.78     10429247.61
      3538690.44     10429265.66      3538743.43     10429298.46
      3538926.18      10429333.9      3538988.04     10429369.98
      3539036.46     10429377.05      3539080.97     10429364.53
      3539130.43     10429375.35       3539187.8     10429409.16
       3539461.4     10429450.48      3539514.87     10429481.03
      3539632.93     10429478.26      3539701.77     10429503.32
      3539732.52     10429500.42      3539798.29     10429475.91
      3539851.07     10429475.22      3540003.15     10429401.61
      3540223.29      10429252.3       3540346.9     10429233.55
      3540554.54     10429149.52       3540596.9     10429091.19
      3540707.32     10428980.77      3540734.59     10428914.95

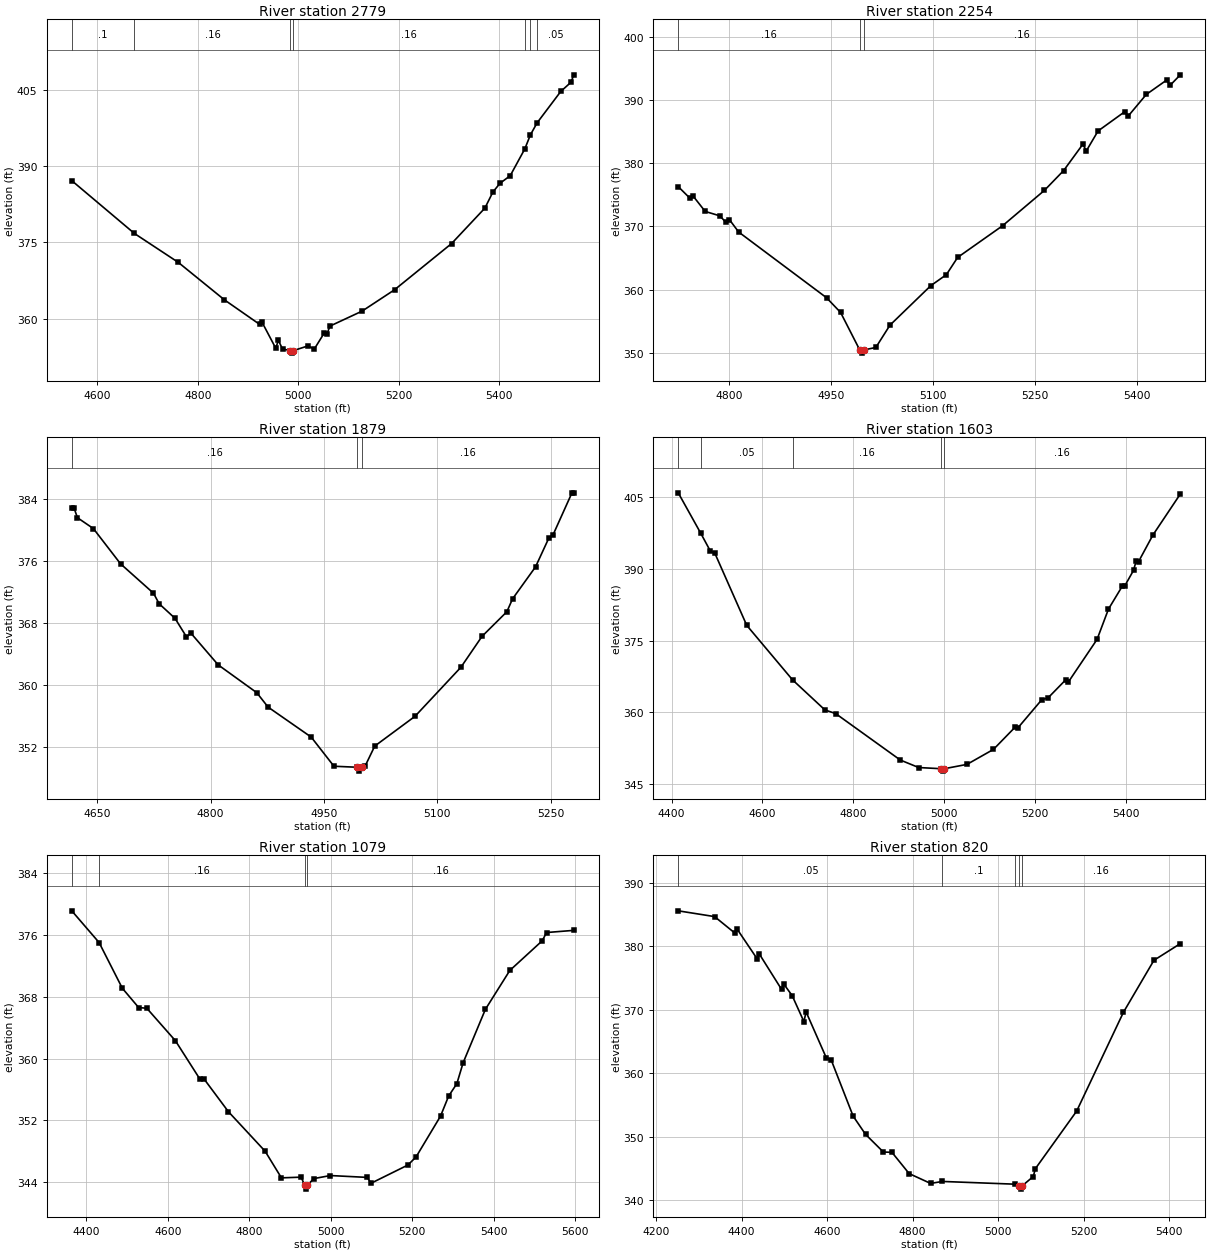
Type RM Length L Ch R = 1 ,2779    ,525,525,525
BEGIN DESCRIPTION:
BEAR CREEK EAST TRIB 4 6.0
END DESCRIPTION:
XS GIS Cut Line= 4
       3538460.7     10429653.77      3538326.13     10429488.81
      3538187.24     10429050.44       3538226.2      10428725.8
#Sta/Elev= 30
  4548.9  387.13  4673.6  376.76    4761  371.08  4852.9  363.72  4922.8  358.92
    4928  359.28    4955  354.23  4960.3  355.76  4968.6  354.06  4984.3  353.76
  4987.1  353.26  4990.3  353.76  5019.6  354.69  5031.6  354.03  5051.9  357.26
  5057.2  357.09    5063  358.57    5127  361.51  5191.6   365.7  5305.2  374.78
  5371.5  381.74  5387.5  384.91  5401.7  386.62  5421.9   388.1    5451  393.37
  5462.1  396.12  5475.5  398.49  5522.6  404.65  5542.7  406.43  5548.6  407.91
#Mann= 7 ,-1 , 0
  4548.9      .1       0  4673.6     .16       0  4984.3     .07       0
  4990.3     .16       0    5451     .05       0  5462.1     .16       0
  5475.5     .05       0
Bank Sta=4984.3,4990.3
XS Rating Curve= 0 ,0
Exp/Cntr=0.3,0.1

Type RM Length L Ch R = 1 ,2254    ,375,375,375
BEGIN DESCRIPTION:
BEAR CREEK EAST TRIB 4 5.0
END DESCRIPTION:
XS GIS Cut Line= 4
      3538725.42     10429558.21      3538690.71     10429475.79
      3538777.52     10429163.29      3538829.59     10428842.15
#Sta/Elev= 30
  4725.3   376.3  4742.3  374.49  4747.7  374.74    4765  372.37  4786.7  371.67
  4795.2  370.66  4800.6  371.08  4814.3  369.11  4943.6  358.71  4964.3  356.38
  4992.5  350.44  4995.2  349.94  4998.5  350.44  5016.2  350.84    5037  354.37
  5097.1  360.62    5120  362.36  5136.6  365.09  5202.8  370.11  5264.4  375.71
  5292.7  378.85    5321  383.02    5326  381.95  5343.3  385.11  5382.6  388.16
  5387.7  387.47  5414.3  390.89  5444.2  393.16  5449.3  392.33  5464.4     394
#Mann= 3 ,-1 , 0
  4725.3     .16       0  4992.5     .07       0  4998.5     .16       0
Bank Sta=4992.5,4998.5
XS Rating Curve= 0 ,0
Exp/Cntr=0.3,0.1

Type RM Length L Ch R = 1 ,1879    ,276,276,276
BEGIN DESCRIPTION:
BEAR CREEK EAST TRIB 4 4.0
END DESCRIPTION:
XS GIS Cut Line= 3
      3538892.08     10429691.67      3539092.11     10429391.64
       3539142.1     10429091.67
#Sta/Elev= 30
  4616.1  382.85  4619.1  382.85  4623.6   381.6  4644.7   380.2  4680.7  375.65
  4724.3  371.86  4731.8   370.5  4752.8  368.62  4767.9  366.24  4773.9   366.7
  4809.9  362.62    4861  359.03    4876  357.17  4933.1   353.3  4963.2  349.54
    4994  349.41  4996.7  348.91    5000  349.41  5004.6  349.59  5017.2  352.14
  5070.5  355.98  5131.3  362.31  5159.2  366.29  5192.1  369.47  5199.7  371.14
  5230.1  375.26  5247.9  379.02  5252.9  379.31  5278.3  384.81  5280.8  384.81
#Mann= 3 ,-1 , 0
  4616.1     .16       0    4994     .07       0    5000     .16       0
Bank Sta=4994,5000
XS Rating Curve= 0 ,0
Exp/Cntr=0.3,0.1

Type RM Length L Ch R = 1 ,1603    ,524,524,524
BEGIN DESCRIPTION:
BEAR CREEK EAST TRIB 4 3.0
END DESCRIPTION:
XS GIS Cut Line= 4
      3539142.12     10429970.54      3539311.37      10429692.8
       3539411.2     10429145.93       3539333.7     10428934.97
#Sta/Elev= 30
  4414.6  405.93  4464.3  397.46  4485.6  393.71  4495.2  393.31  4565.5  378.22
  4666.3  366.83  4737.6  360.54  4761.4  359.77  4903.7  350.06  4944.3  348.49
  4994.4  348.24  4997.1  347.74  5000.4  348.24  5050.6  349.15    5109  352.29
  5157.2  356.99  5162.2  356.72  5215.5  362.69    5229  363.04  5268.7  366.89
  5273.8  366.36  5337.1  375.28  5362.3  381.63  5392.8  386.43  5398.1  386.46
  5417.5  389.73  5423.2  391.67  5428.6  391.56  5460.1   397.1  5520.5  405.68
#Mann= 5 ,-1 , 0
  4414.6     .16       0  4464.3     .05       0  4666.3     .16       0
  4994.4     .07       0  5000.4     .16       0
Bank Sta=4994.4,5000.4
XS Rating Curve= 0 ,0
Exp/Cntr=0.3,0.1

Type RM Length L Ch R = 1 ,1079    ,259,259,259
BEGIN DESCRIPTION:
Mapping XS d10d48ec
END DESCRIPTION:
XS GIS Cut Line= 2
      3539828.43      10430105.6      3539890.84     10428874.78
#Sta/Elev= 30
  4364.5  379.14  4431.6  375.03  4488.6  369.11  4528.7  366.61  4548.7  366.52
  4618.8  362.32  4678.9  357.35  4688.9  357.38    4749  353.12  4839.1     348
  4879.1  344.55  4927.5  344.64  4936.2  343.59  4938.9  343.09  4942.2  343.59
  4959.2  344.46  4999.3  344.85  5089.4  344.61  5099.4  343.86  5189.5  346.21
  5209.5  347.25  5269.6  352.54  5289.6  355.15  5309.7  356.75  5325.2  359.47
  5379.8  366.38  5439.8  371.42  5519.1  375.25    5530  376.33  5596.9  376.61
#Mann= 4 ,-1 , 0
  4364.5     .05       0  4431.6     .16       0  4936.2     .07       0
  4942.2     .16       0
Bank Sta=4936.2,4942.2
XS Rating Curve= 0 ,0
Exp/Cntr=0.3,0.1

Type RM Length L Ch R = 1 ,820     ,276,276,276
BEGIN DESCRIPTION:
BEAR CREEK EAST TRIB 4 2.0
END DESCRIPTION:
XS GIS Cut Line= 3
      3540031.86     10430083.41      3540114.32      10429649.4
      3540044.88     10428920.27
#Sta/Elev= 30
    4252   385.6    4337  384.69  4384.1  382.11  4389.2  382.77  4436.4  378.05
  4441.5  378.81  4493.7  373.21  4498.8  374.06  4518.4  372.24  4545.9  368.14
    4551  369.67  4598.2  362.44  4610.1  362.03    4661  353.24  4690.1  350.36
  4731.7  347.58  4751.8  347.53    4792  344.18  4842.2  342.63  4869.9  342.94
  5039.5  342.51  5050.1  342.23  5052.9  341.73  5056.1  342.23  5082.3  343.72
  5087.3  344.96  5183.7  354.02  5293.2  369.61  5364.5   377.8  5426.2  380.43
#Mann= 5 ,-1 , 0
    4252     .05       0  4869.9      .1       0  5039.5     .16       0
  5050.1     .07       0  5056.1     .16       0
Bank Sta=5050.1,5056.1
XS Rating Curve= 0 ,0
Exp/Cntr=0.3,0.1

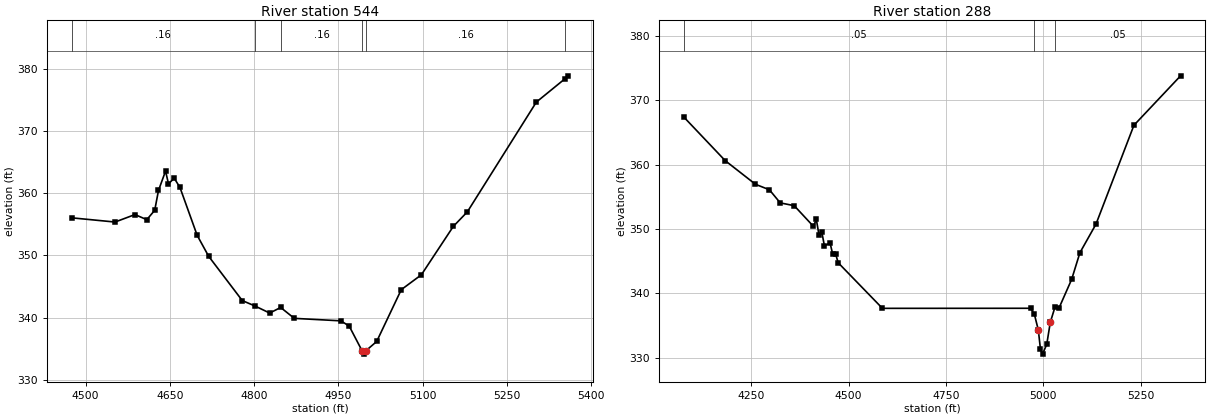
Type RM Length L Ch R = 1 ,544     ,256,256,256
BEGIN DESCRIPTION:
BEAR CREEK EAST TRIB 4 1.5
END DESCRIPTION:
XS GIS Cut Line= 3
      3540296.59     10429705.85      3540409.46     10429597.32
      3540253.33     10428886.03
#Sta/Elev= 30
  4474.8  356.03  4552.3  355.35  4587.8  356.55  4608.9  355.73    4623  357.24
  4629.7  360.42  4642.3  363.55  4647.5  361.49  4657.7   362.4  4667.9  360.92
  4698.6  353.21  4719.1  349.84  4778.9  342.73  4801.2  341.87  4827.8  340.72
  4847.3  341.62  4871.6  339.87  4954.6  339.47  4969.4  338.62  4992.5  334.62
  4995.3  334.12  4998.5  334.62  5018.3  336.15  5062.1  344.48  5097.9  346.87
  5154.8  354.65  5179.8  356.99  5302.7  374.63  5354.1  378.41  5359.6  378.85
#Mann= 6 ,-1 , 0
  4474.8     .16       0  4801.2     .05       0  4847.3     .16       0
  4992.5     .07       0  4998.5     .16       0  5354.1     .05       0
Bank Sta=4992.5,4998.5
XS Rating Curve= 0 ,0
Exp/Cntr=0.3,0.1

Type RM Length L Ch R = 1 ,288     ,0,0,0
BEGIN DESCRIPTION:
BEAR CREEK EAST TRIB 4 1.0
END DESCRIPTION:
XS GIS Cut Line= 3
      3540254.66     10429884.23      3540668.71     10429428.52
      3540444.76     10428808.76
#Sta/Elev= 30
  4077.2  367.42  4183.5  360.63  4261.2  356.95  4296.9   356.1  4324.7  354.06
  4360.5  353.63  4409.9  350.41  4417.3  351.49  4424.1  349.09  4431.5  349.48
  4438.2  347.34  4452.4  347.87  4459.2  346.11  4466.6  346.16  4473.4  344.75
  4586.9  337.66  4966.9  337.67  4976.7  336.76  4986.9  334.29  4992.3  331.35
  4997.7  330.54  5008.6  332.08  5017.6  335.48  5029.9  337.91  5040.5  337.78
  5072.4  342.16  5093.6  346.31  5134.9  350.76  5232.2  366.13  5351.9  373.82
#Mann= 3 ,-1 , 0
  4077.2     .05       0  4976.7     .03       0  5029.9     .05       0
Bank Sta=4986.9,5017.6
XS Rating Curve= 0 ,0
Exp/Cntr=0.3,0.1

Chan Stop Cuts=-1
Use User Specified Reach Order=0
Composite Channel Slope=5