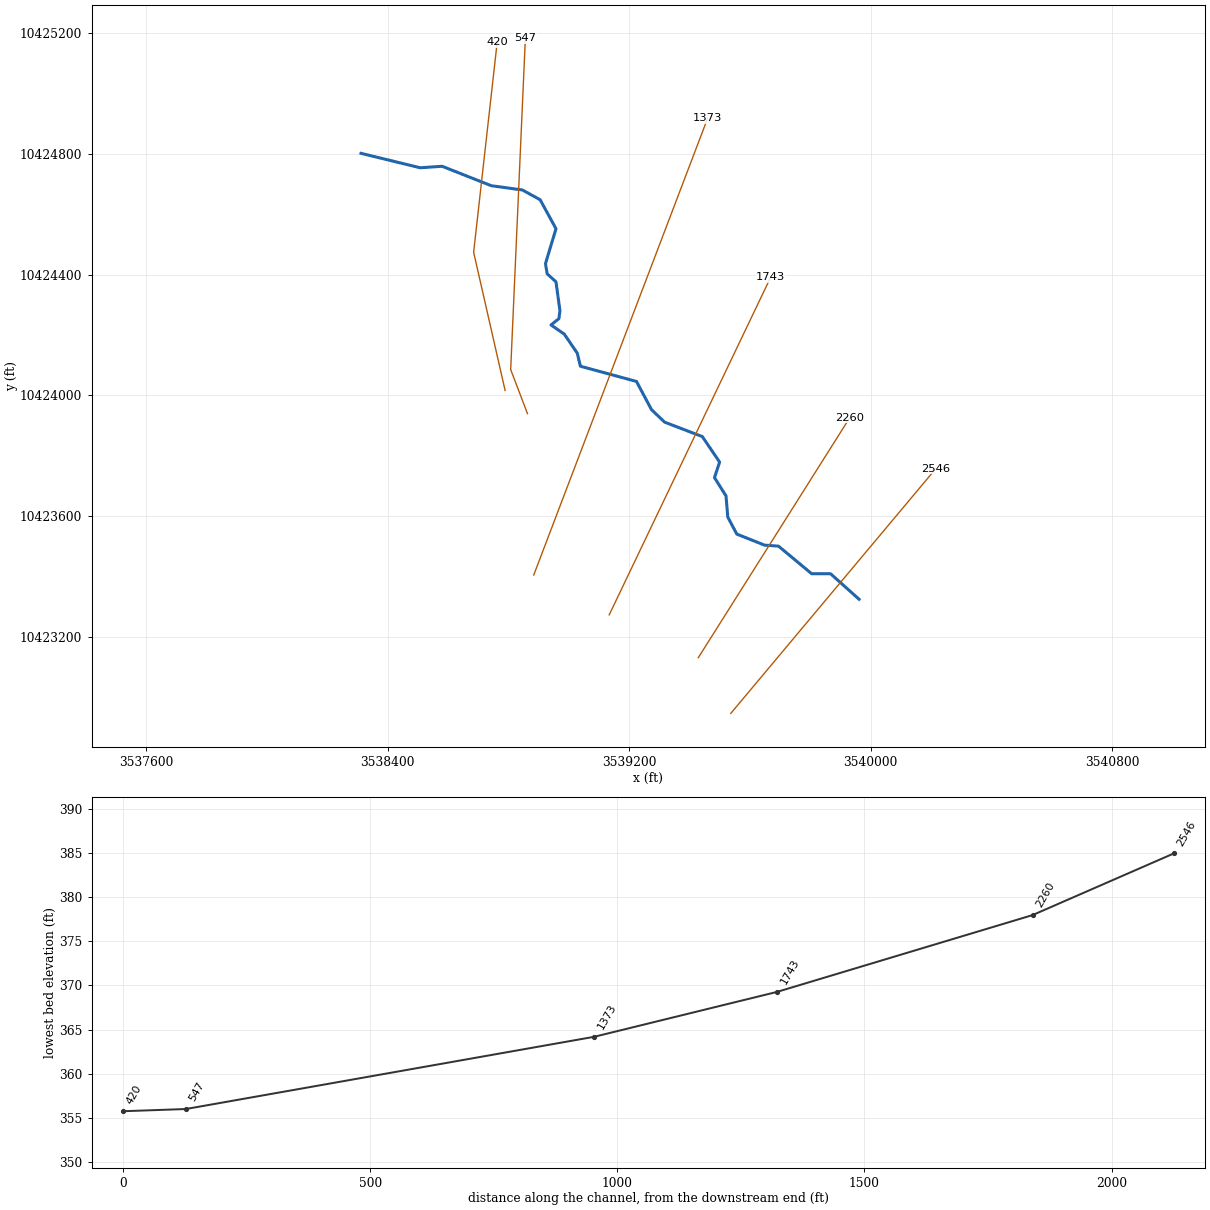
--- BEAR CREEK EAST TRIB 6 1.prj (project) ---

Proj Title=BEAR CREEK EAST TRIB 6 1 Base Level Engineering
Current Plan=p01
Default Exp/Contr=0.3,0.1
English Units
Geom File=g01
Flow File=f01
Plan File=p01
BEGIN DESCRIPTION:
BEAR CREEK EAST TRIB 6 1
END DESCRIPTION:

--- BEAR CREEK EAST TRIB 6 1.p01 (plan) ---

Plan Title=Multiple Run
Short Identifier=Multiple
Geom File=g01
Flow File=f01
Subcritical Flow
K Sum by GR= 0
Std Step Tol= 0.01
Critical Tol= 0.01
Num of Std Step Trials= 20
Max Error Tol= 0.3
Flow Tol Ratio= 0.001
Split Flow NTrial= 30
Split Flow Tol= 0.02
Split Flow Ratio= 0.02
Log Output Level= 0
Friction Slope Method= 1
Unsteady Friction Slope Method= 2
Unsteady Bridges Friction Slope Method= 1
Parabolic Critical Depth
Global Vel Dist=  1 , 1 , 1
Global Log Level= 0
CheckData=True
Encroach Param= -1, 0, 0, 0
BEGIN DESCRIPTION:
Multiple Run
END DESCRIPTION:

--- BEAR CREEK EAST TRIB 6 1.f01 (steady flow) ---

Flow Title=Multiple
Number of Profiles=7
Profile Names=10-year,25-year,50-year,1pct_min,100-year,1pct_plu,500-year
River Rch & RM= BEAR CREEK EAST ,Reach-1,2546
     444     587     702     616     834    1127    1167
Boundary for River Rch & Prof#=BEAR CREEK EAST ,Reach-1,1
Up Type=0
Dn Type=3
Dn Slope=0.005
Boundary for River Rch & Prof#=BEAR CREEK EAST ,Reach-1,2
Up Type=0
Dn Type=3
Dn Slope=0.005
Boundary for River Rch & Prof#=BEAR CREEK EAST ,Reach-1,3
Up Type=0
Dn Type=3
Dn Slope=0.005
Boundary for River Rch & Prof#=BEAR CREEK EAST ,Reach-1,4
Up Type=0
Dn Type=3
Dn Slope=0.005
Boundary for River Rch & Prof#=BEAR CREEK EAST ,Reach-1,5
Up Type=0
Dn Type=3
Dn Slope=0.005
Boundary for River Rch & Prof#=BEAR CREEK EAST ,Reach-1,6
Up Type=0
Dn Type=3
Dn Slope=0.005
Boundary for River Rch & Prof#=BEAR CREEK EAST ,Reach-1,7
Up Type=0
Dn Type=3
Dn Slope=0.005

--- BEAR CREEK EAST TRIB 6 1.g01 (geometry) ---

Geom Title=Existing Conditions

River Reach=BEAR CREEK EAST ,Reach-1
Reach XY= 30
      3539961.82     10423324.54      3539867.22     10423409.12
      3539804.72     10423409.12      3539695.01     10423500.45
      3539648.48     10423503.93      3539556.82     10423540.38
      3539526.94     10423596.62      3539521.05     10423666.77
      3539482.86     10423727.54      3539499.81     10423778.91
      3539442.49     10423863.39      3539317.52     10423911.29
      3539274.29     10423952.58      3539224.46     10424046.02
      3539038.65     10424096.50      3539028.26     10424139.72
      3538985.25     10424202.84      3538941.34     10424233.20
      3538967.35     10424253.98      3538970.98     10424280.82
      3538957.67     10424376.17      3538928.57     10424402.56
      3538923.02     10424436.41      3538957.84     10424551.85
      3538905.31     10424647.97      3538846.59     10424680.30
      3538743.28     10424694.48      3538580.83     10424758.76
      3538507.86     10424753.87      3538312.11     10424801.64

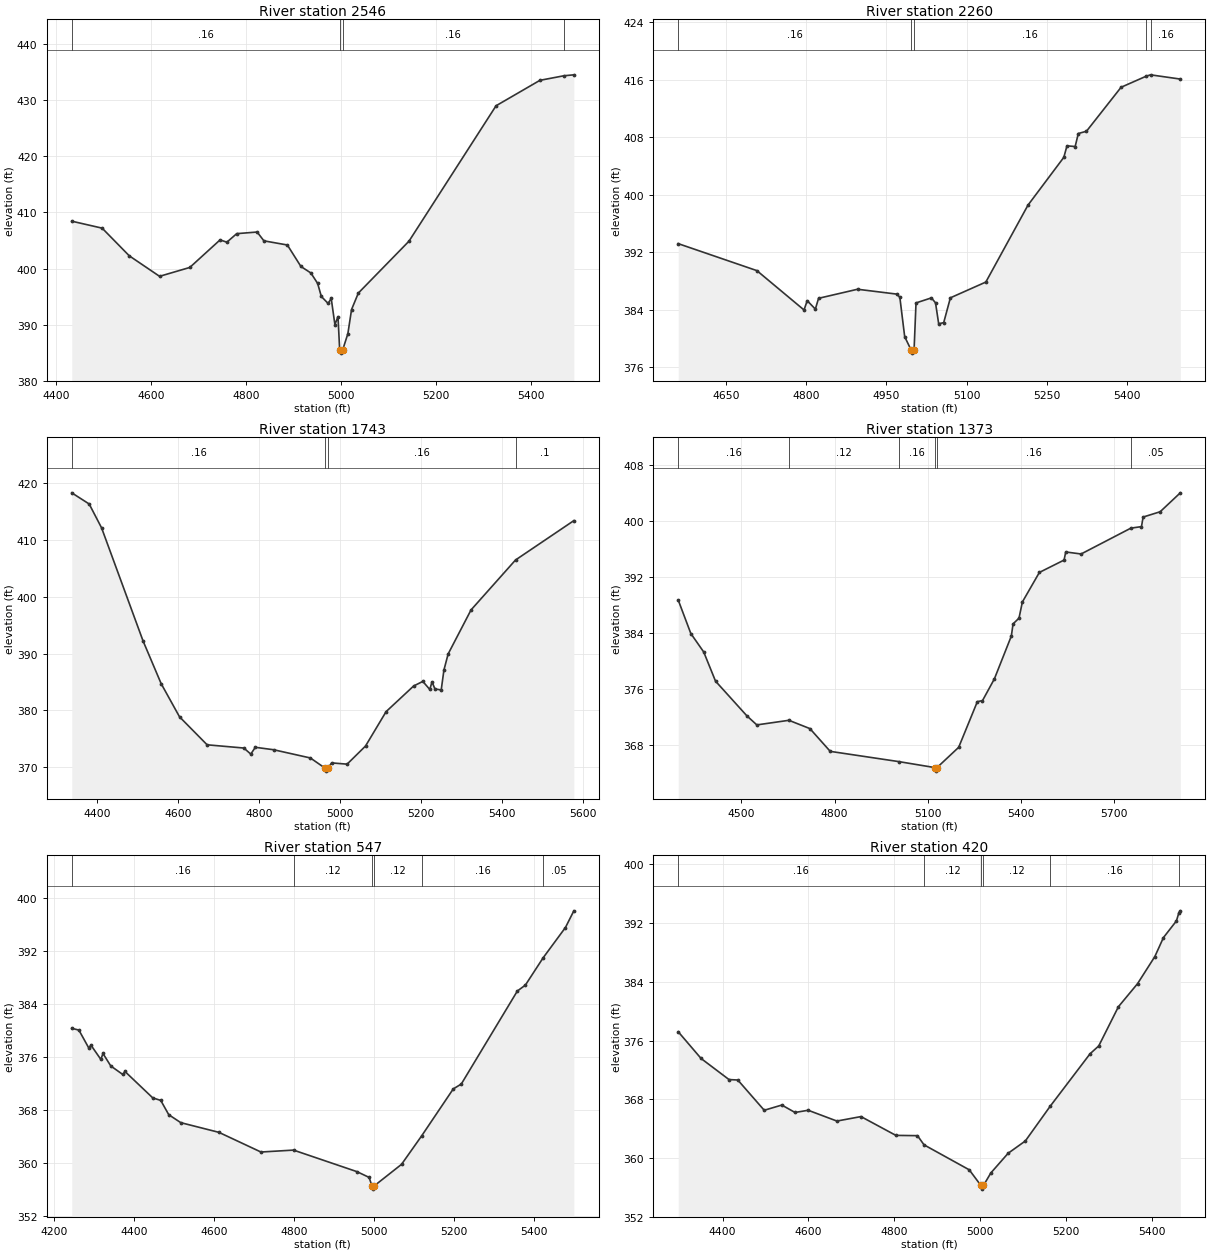
Type RM Length L Ch R = 1,2546,286,286,286
BEGIN DESCRIPTION:
BEAR CREEK EAST TRIB 6.1 4.0
END DESCRIPTION:
XS GIS Cut Line= 2
      3539536.91     10422946.52      3540216.27     10423757.59
#Sta/Elev= 30
  4432.4  408.44  4496.4  407.20  4553.6  402.27  4617.4  398.62  4681.1  400.20
  4744.9  405.11  4759.2  404.70  4780.0  406.22  4823.0  406.51  4837.3  404.94
  4886.7  404.20  4915.3  400.37  4936.2  399.22  4950.5  397.36  4958.3  395.03
  4972.6  393.79  4979.1  394.69  4986.9  390.02  4993.4  391.44  4997.0  385.44
  4999.7  384.94  5003.0  385.44  5014.2  388.40  5022.0  392.71  5036.3  395.64
  5143.0  404.88  5326.5  429.00  5418.9  433.53  5469.3  434.34  5490.4  434.51
#Mann=4,-1,0
  4432.4    0.16       0  4997.0    0.07       0  5003.0    0.16       0
  5469.3    0.05       0
Bank Sta=4997,5003
Exp/Cntr=0.3,0.1

Type RM Length L Ch R = 1,2260,517,517,517
BEGIN DESCRIPTION:
Mapping XS 04492d51
END DESCRIPTION:
XS GIS Cut Line= 2
      3539429.29     10423131.11      3539930.57     10423925.35
#Sta/Elev= 30
  4560.5  393.18  4707.6  389.43  4795.8  383.96  4801.8  385.25  4817.0  384.08
  4823.0  385.58  4895.9  386.84  4968.8  386.17  4975.0  385.75  4984.1  380.25
  4995.7  378.46  4998.4  377.96  5001.7  378.46  5005.3  384.94  5034.1  385.64
  5041.8  384.95  5047.7  382.04  5057.1  382.20  5069.6  385.65  5135.9  387.84
  5214.8  398.54  5281.8  405.18  5287.7  406.78  5303.0  406.68  5308.9  408.49
  5324.2  408.81  5388.9  414.92  5435.9  416.46  5444.0  416.65  5499.7  416.06
#Mann=5,-1,0
  4560.5    0.16       0  4995.7    0.07       0  5001.7    0.16       0
  5435.9     0.1       0  5444.0    0.16       0
Bank Sta=4995.7,5001.7
Exp/Cntr=0.3,0.1

Type RM Length L Ch R = 1,1743,370,370,370
BEGIN DESCRIPTION:
BEAR CREEK EAST TRIB 6.1 3.0
END DESCRIPTION:
XS GIS Cut Line= 2
      3539134.11     10423272.88      3539668.86     10424390.98
#Sta/Elev= 30
  4338.3  418.32  4381.3  416.35  4411.9  412.14  4514.3  392.21  4559.0  384.68
  4604.3  378.84  4672.4  373.91  4763.1  373.34  4780.2  372.27  4791.4  373.47
  4836.6  373.04  4927.3  371.59  4964.1  369.77  4966.9  369.27  4970.1  369.77
  4979.9  370.72  5018.0  370.50  5063.4  373.69  5114.3  379.76  5182.3  384.28
  5204.9  385.08  5222.1  383.66  5227.6  385.01  5234.8  383.75  5250.3  383.58
  5257.0  387.09  5267.4  389.92  5323.9  397.68  5433.7  406.48  5577.7  413.42
#Mann=4,-1,0
  4338.3    0.16       0  4964.1    0.07       0  4970.1    0.16       0
  5433.7     0.1       0
Bank Sta=4964.1,4970.1
Exp/Cntr=0.3,0.1

Type RM Length L Ch R = 1,1373,826,826,826
BEGIN DESCRIPTION:
BEAR CREEK EAST TRIB 6.1 2.0
END DESCRIPTION:
XS GIS Cut Line= 2
      3538884.13     10423404.86      3539460.13     10424917.72
#Sta/Elev= 30
  4296.1  388.69  4336.7  383.90  4378.3  381.25  4416.3  377.08  4517.4  372.11
  4549.5  370.81  4652.9  371.47  4720.7  370.28  4786.2  367.02  5007.8  365.55
  5124.3  364.69  5127.0  364.19  5130.3  364.69  5200.3  367.60  5260.5  374.14
  5277.1  374.29  5315.4  377.40  5370.2  383.55  5375.6  385.28  5394.8  386.10
  5405.7  388.42  5460.5  392.65  5540.1  394.42  5545.5  395.58  5595.0  395.29
  5755.4  398.99  5789.7  399.21  5795.0  400.58  5849.9  401.34  5914.9  404.05
#Mann=6,-1,0
  4296.1    0.16       0  4652.9    0.12       0  5007.8    0.16       0
  5124.3    0.07       0  5130.3    0.16       0  5755.4    0.05       0
Bank Sta=5124.3,5130.3
Exp/Cntr=0.3,0.1

Type RM Length L Ch R = 1,547,127,127,127
BEGIN DESCRIPTION:
BEAR CREEK EAST TRIB 6.1 1.5
END DESCRIPTION:
XS GIS Cut Line= 3
      3538863.27     10423939.61      3538807.73     10424085.40
      3538856.35     10425182.61
#Sta/Elev= 30
  4244.6  380.29  4262.4  380.02  4287.1  377.32  4292.5  377.75  4317.2  375.60
  4322.6  376.49  4342.0  374.61  4372.1  373.32  4377.4  373.78  4446.9  369.79
  4466.9  369.41  4486.9  367.25  4517.0  366.05  4612.2  364.59  4717.2  361.62
  4798.6  361.91  4957.4  358.65  4987.4  357.79  4994.4  356.52  4997.2  356.02
  5000.4  356.52  5068.4  359.76  5118.6  364.05  5197.6  371.14  5217.7  371.88
  5357.8  385.92  5377.8  386.81  5422.4  390.95  5477.9  395.50  5498.9  398.02
#Mann=6,-1,0
  4244.6    0.16       0  4798.6    0.12       0  4994.4    0.07       0
  5000.4    0.12       0  5118.6    0.16       0  5422.4    0.05       0
Bank Sta=4994.4,5000.4
Exp/Cntr=0.3,0.1

Type RM Length L Ch R = 1,420,0,0,0
BEGIN DESCRIPTION:
BEAR CREEK EAST TRIB 6.1 1.0
END DESCRIPTION:
XS GIS Cut Line= 3
      3538789.26     10424016.16      3538685.00     10424474.09
      3538763.12     10425170.67
#Sta/Elev= 30
  4296.5  377.20  4349.8  373.56  4414.9  370.69  4435.4  370.63  4497.0  366.51
  4538.0  367.22  4568.8  366.21  4599.5  366.51  4666.4  365.04  4722.6  365.65
  4803.9  363.09  4854.3  363.05  4869.6  361.80  4975.0  358.40  5002.2  356.27
  5004.9  355.77  5008.2  356.27  5025.3  357.97  5065.6  360.65  5105.8  362.33
  5164.0  367.08  5256.8  374.21  5276.9  375.27  5322.8  380.61  5367.4  383.75
  5407.7  387.44  5427.8  390.03  5458.0  392.29  5463.7  393.40  5467.1  393.67
#Mann=6,-1,0
  4296.5    0.16       0  4869.6    0.12       0  5002.2    0.07       0
  5008.2    0.12       0  5164.0    0.16       0  5463.7    0.05       0
Bank Sta=5002.2,5008.2
Exp/Cntr=0.3,0.1

Chan Stop Cuts=-1