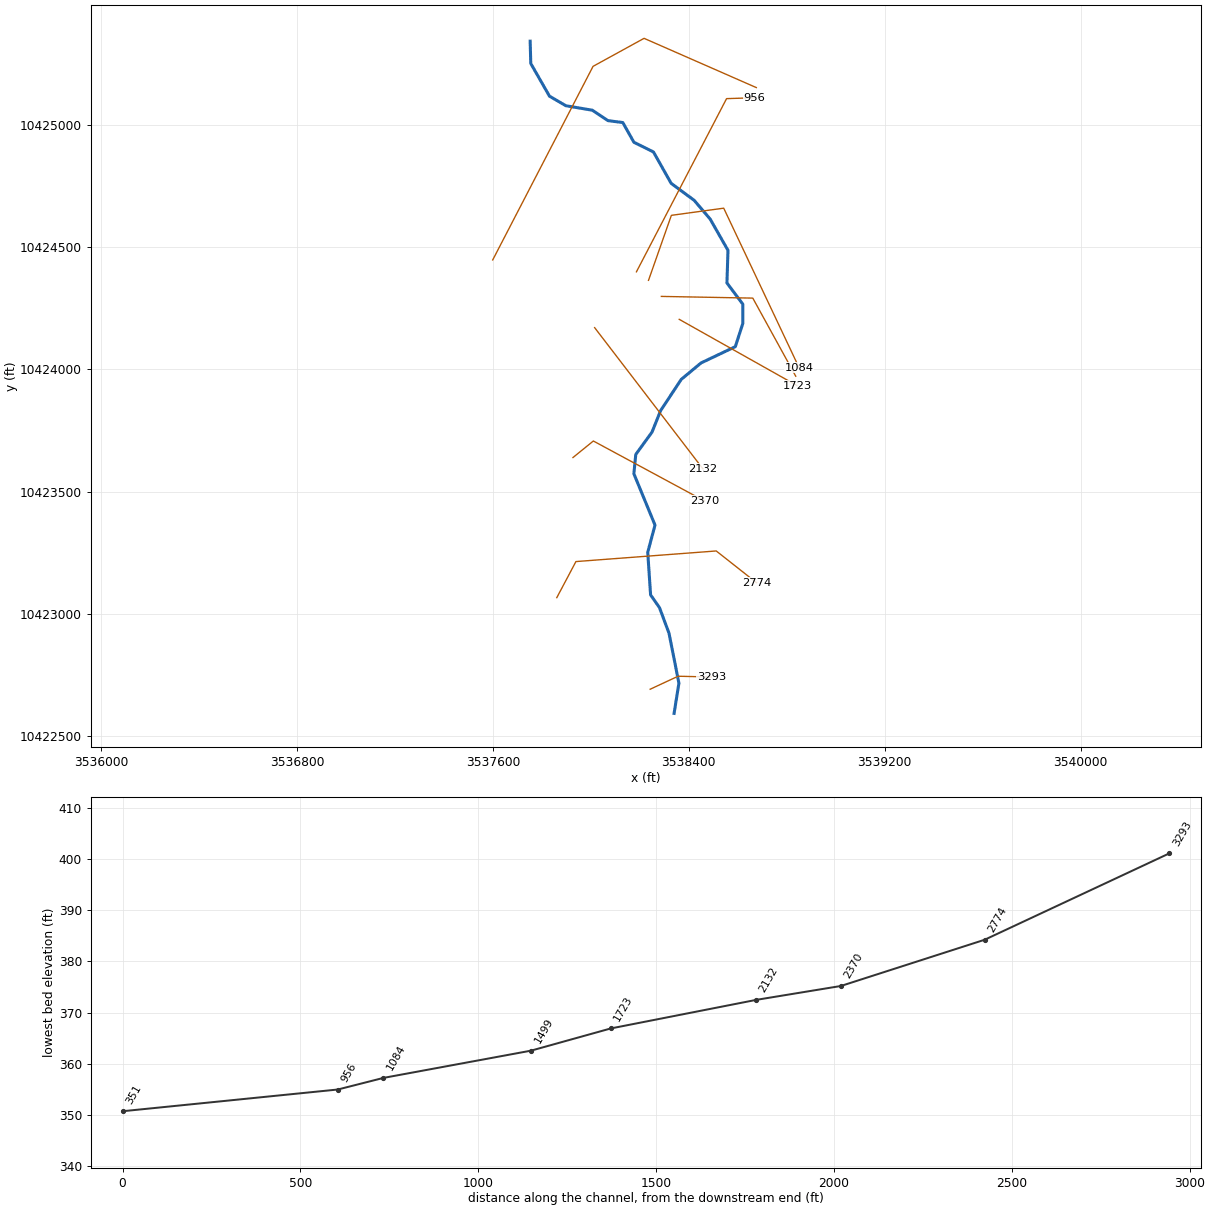
--- BEAR CREEK EAST TRIB 6.prj (project) ---

Proj Title=BEAR CREEK EAST TRIB 6 Base Level Engineering
Current Plan=p01
Default Exp/Contr=0.3,0.1
English Units
Geom File=g01
Flow File=f01
Plan File=p01
Y Axis Title=Elevation
X Axis Title(PF)=Main Channel Distance
X Axis Title(XS)=Station
BEGIN DESCRIPTION:
BEAR CREEK EAST TRIB 6
END DESCRIPTION:
DSS Export Rating Curves= 0
DSS Export Rating Curve Sorted= 0
DSS Export Volume Flow Curves= 0
DXF OffsetX= 0
DXF OffsetY= 0
DXF ScaleX= 1
DXF ScaleY= 10

--- BEAR CREEK EAST TRIB 6.p01 (plan) ---

Plan Title=Multiple Run
Short Identifier=Multiple
Geom File=g01
Flow File=f01
Subcritical Flow
K Sum by GR= 0
Std Step Tol= 0.01
Critical Tol= 0.01
Num of Std Step Trials= 20
Max Error Tol= 0.3
Flow Tol Ratio= 0.001
Split Flow NTrial= 30
Split Flow Tol= 0.02
Split Flow Ratio= 0.02
Log Output Level= 0
Friction Slope Method= 1
Unsteady Friction Slope Method= 2
Unsteady Bridges Friction Slope Method= 1
Parabolic Critical Depth
Global Vel Dist=  1 , 1 , 1
Global Log Level= 0
CheckData=True
Encroach Param= -1, 0, 0, 0
BEGIN DESCRIPTION:
Multiple Run
END DESCRIPTION:

--- BEAR CREEK EAST TRIB 6.f01 (steady flow) ---

Flow Title=Multiple
Number of Profiles=7
Profile Names=10-year,25-year,50-year,1pct_min,100-year,1pct_plu,500-year
River Rch & RM= BEAR CREEK EAST ,Reach-1,3293
     470     625     749     660     892    1206    1256
River Rch & RM= BEAR CREEK EAST ,Reach-1,956
     884    1227    1515    1369    1851    2503    2752
Boundary for River Rch & Prof#=BEAR CREEK EAST ,Reach-1,1
Up Type=0
Dn Type=3
Dn Slope=0.005
Boundary for River Rch & Prof#=BEAR CREEK EAST ,Reach-1,2
Up Type=0
Dn Type=3
Dn Slope=0.005
Boundary for River Rch & Prof#=BEAR CREEK EAST ,Reach-1,3
Up Type=0
Dn Type=3
Dn Slope=0.005
Boundary for River Rch & Prof#=BEAR CREEK EAST ,Reach-1,4
Up Type=0
Dn Type=3
Dn Slope=0.005
Boundary for River Rch & Prof#=BEAR CREEK EAST ,Reach-1,5
Up Type=0
Dn Type=3
Dn Slope=0.005
Boundary for River Rch & Prof#=BEAR CREEK EAST ,Reach-1,6
Up Type=0
Dn Type=3
Dn Slope=0.005
Boundary for River Rch & Prof#=BEAR CREEK EAST ,Reach-1,7
Up Type=0
Dn Type=3
Dn Slope=0.005

--- BEAR CREEK EAST TRIB 6.g01 (geometry) ---

Geom Title=Existing Conditions
Program Version=4.10

River Reach=BEAR CREEK EAST ,Reach-1
Reach XY= 30
       3538339.8      10422592.9       3538359.5     10422716.21
      3538319.13     10422920.39      3538280.05     10423025.44
      3538243.86      10423077.4      3538232.21     10423251.49
      3538261.92     10423362.86      3538175.54     10423572.77
      3538183.38      10423651.8      3538249.49     10423742.73
       3538284.7      10423830.6      3538368.82     10423958.38
       3538449.8     10424025.81      3538589.84     10424092.49
      3538620.44     10424187.43       3538620.5     10424265.98
      3538555.54     10424353.04      3538559.86     10424486.23
      3538487.05     10424614.15      3538421.82     10424690.85
      3538327.88     10424760.21      3538255.47     10424888.73
      3538175.78     10424928.19      3538130.28     10425008.89
      3538069.41     10425016.77      3538006.15     10425059.28
      3537897.86     10425077.65      3537831.02     10425116.71
      3537754.63     10425250.39      3537752.11     10425341.64

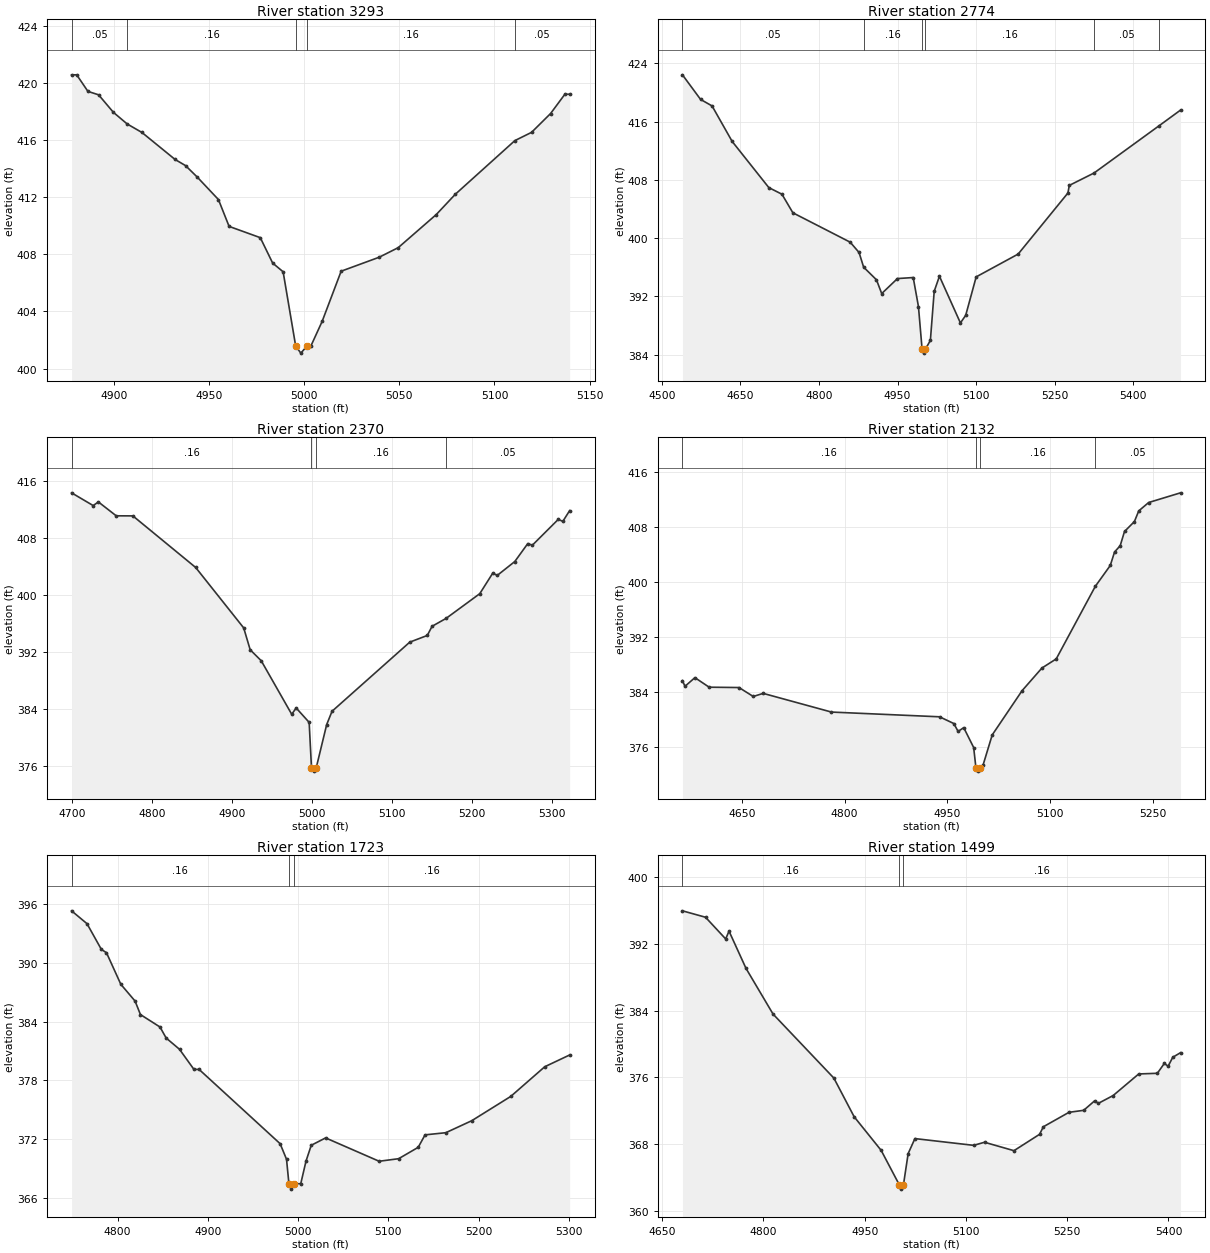
Type RM Length L Ch R = 1 ,3293    ,519,519,519
BEGIN DESCRIPTION:
BEAR CREEK EAST TRIB 6 6.0
END DESCRIPTION:
XS GIS Cut Line= 3
      3538242.14     10422691.66      3538356.19     10422744.77
      3538492.15     10422741.64
#Sta/Elev= 30
  4877.7  420.58  4880.4  420.58  4886.3  419.42  4891.9  419.18  4899.7  417.95
  4906.9  417.14  4914.7  416.54  4932.1  414.65  4937.6  414.22  4943.8  413.41
  4954.9  411.84  4960.5  409.96  4976.9  409.17  4983.4  407.39  4988.9  406.78
  4995.5  401.58  4998.2  401.08  5001.5  401.58  5003.5  401.58  5009.4   403.3
  5019.4  406.82  5039.4   407.8  5049.4  408.47  5069.4  410.79  5079.4  412.21
  5110.7  415.97  5119.5  416.55  5129.5  417.87    5137  419.22  5139.5  419.22
#Mann= 5 ,-1 , 0
  4877.7     .05       0  4906.9     .16       0  4995.5     .07       0
  5001.5     .16       0  5110.7     .05       0
Bank Sta=4995.5,5001.5
XS Rating Curve= 0 ,0
Exp/Cntr=0.3,0.1

Type RM Length L Ch R = 1 ,2774    ,404,404,404
BEGIN DESCRIPTION:
BEAR CREEK EAST TRIB 6 5.0
END DESCRIPTION:
XS GIS Cut Line= 4
      3537860.86     10423066.08      3537938.98     10423213.64
      3538511.89     10423257.04      3538676.79     10423126.86
#Sta/Elev= 30
  4539.1  422.41  4573.7  419.04  4595.7  418.14  4634.1  413.27  4704.1  406.94
  4729.2  406.03  4750.1  403.48  4859.6  399.45  4876.5  398.04  4885.3  396.02
  4909.8  394.29  4919.8   392.4  4949.9  394.46    4980   394.6    4990  390.62
    4997  384.73  4999.8  384.23    5003  384.73  5012.8  385.98  5020.1  392.71
  5030.1  394.78  5070.2  388.37  5080.3  389.42  5100.3  394.69  5180.5  397.82
  5275.6   406.2  5278.2  407.24  5325.5  408.94  5449.9  415.43  5490.7  417.57
#Mann= 6 ,-1 , 0
  4539.1     .05       0  4885.3     .16       0    4997     .07       0
    5003     .16       0  5325.5     .05       0  5449.9     .16       0
Bank Sta=4997,5003
XS Rating Curve= 0 ,0
Exp/Cntr=0.3,0.1

Type RM Length L Ch R = 1 ,2370    ,238,238,238
BEGIN DESCRIPTION:
BEAR CREEK EAST TRIB 6 4.0
END DESCRIPTION:
XS GIS Cut Line= 3
      3537926.85       10423639.      3538010.16     10423706.69
      3538463.32     10423461.88
#Sta/Elev= 30
  4699.2  414.31  4726.2  412.52  4732.7  413.03    4755  411.08  4775.8  411.07
  4854.3  403.82  4914.3  395.33  4922.4  392.26  4936.2  390.72  4974.3   383.2
  4979.9  384.08  4996.1  382.06    4999  375.71  5001.7  375.21    5005  375.71
    5018  381.75  5024.7  383.62  5121.8  393.33  5143.7  394.27  5149.7  395.56
  5167.1  396.66  5209.3  400.14  5225.5  403.02  5231.2  402.71  5253.1  404.66
  5269.3  407.18    5275  406.95  5307.4  410.58  5313.1   410.3  5321.6  411.81
#Mann= 4 ,-1 , 0
  4699.2     .16       0    4999     .07       0    5005     .16       0
  5167.1     .05       0
Bank Sta=4999,5005
XS Rating Curve= 0 ,0
Exp/Cntr=0.3,0.1

Type RM Length L Ch R = 1 ,2132    ,409,409,409
BEGIN DESCRIPTION:
BEAR CREEK EAST TRIB 6 3.0
END DESCRIPTION:
XS GIS Cut Line= 2
      3538015.37     10424170.22      3538457.62      10423592.7
#Sta/Elev= 30
  4563.1  385.67  4566.8  384.85  4581.3  386.11  4602.1  384.72  4645.7  384.67
  4666.5  383.37    4681  383.82  4780.7   381.1  4938.6  380.41  4959.4  379.43
  4965.7  378.28  4973.9  378.83  4988.4  375.94  4991.7     373  4994.5   372.5
  4997.7     373  5002.1  373.37  5015.5  377.77  5059.1  384.21  5088.1  387.51
    5109  388.84  5166.1  399.41  5187.9  402.44  5194.2  404.41  5202.4  405.32
  5208.7  407.39  5223.2  408.84  5229.5  410.39    5244  411.61  5290.5  413.02
#Mann= 4 ,-1 , 0
  4563.1     .16       0  4991.7     .07       0  4997.7     .16       0
  5166.1     .05       0
Bank Sta=4991.7,4997.7
XS Rating Curve= 0 ,0
Exp/Cntr=0.3,0.1

Type RM Length L Ch R = 1 ,1723    ,224,224,224
BEGIN DESCRIPTION:
Mapping XS 596d9184
END DESCRIPTION:
XS GIS Cut Line= 2
      3538360.78     10424204.18      3538841.66     10423933.36
#Sta/Elev= 30
  4748.9  395.28    4766  393.97  4781.9  391.35  4787.6  391.01  4803.5  387.79
  4819.3  386.08  4825.2  384.71  4846.9  383.44  4853.7  382.32  4868.5  381.17
  4884.5  379.12  4890.2  379.12    4980  371.55  4987.1  369.96  4989.8  367.42
  4992.6  366.92  4995.8  367.42  5002.9  367.49  5008.7  369.78  5014.5  371.39
  5030.4  372.14  5089.7  369.76  5111.3  370.02    5133  371.18  5140.6  372.45
  5163.6  372.67  5192.3  373.89  5235.6  376.37  5273.2  379.39  5300.8  380.59
#Mann= 3 ,-1 , 0
  4748.9     .16       0  4989.8     .07       0  4995.8     .16       0
Bank Sta=4989.8,4995.8
XS Rating Curve= 0 ,0
Exp/Cntr=0.3,0.1

Type RM Length L Ch R = 1 ,1499    ,415,415,415
BEGIN DESCRIPTION:
Mapping XS 35a6c963
END DESCRIPTION:
XS GIS Cut Line= 3
      3538287.89     10424297.92      3538661.14     10424290.98
      3538836.48     10423971.56
#Sta/Elev= 30
  4680.1  395.96  4714.3  395.19  4744.1  392.59  4749.1  393.52  4774.3  389.05
  4814.3  383.58  4904.4   375.9  4934.4  371.27  4974.4  367.24  5001.4  363.09
  5004.1  362.59  5007.4  363.09  5014.4  366.85  5024.4  368.65  5111.4  367.84
  5127.5  368.21  5171.1   367.2    5209  369.16  5214.7  370.07  5252.6   371.8
  5274.4  372.04  5290.5  373.17  5296.2  372.88    5318  373.81  5355.9   376.4
  5383.5  376.48  5393.8  377.66  5399.5  377.33  5406.3   378.4  5417.8  378.95
#Mann= 3 ,-1 , 0
  4680.1     .16       0  5001.4     .07       0  5007.4     .16       0
Bank Sta=5001.4,5007.4
XS Rating Curve= 0 ,0
Exp/Cntr=0.3,0.1

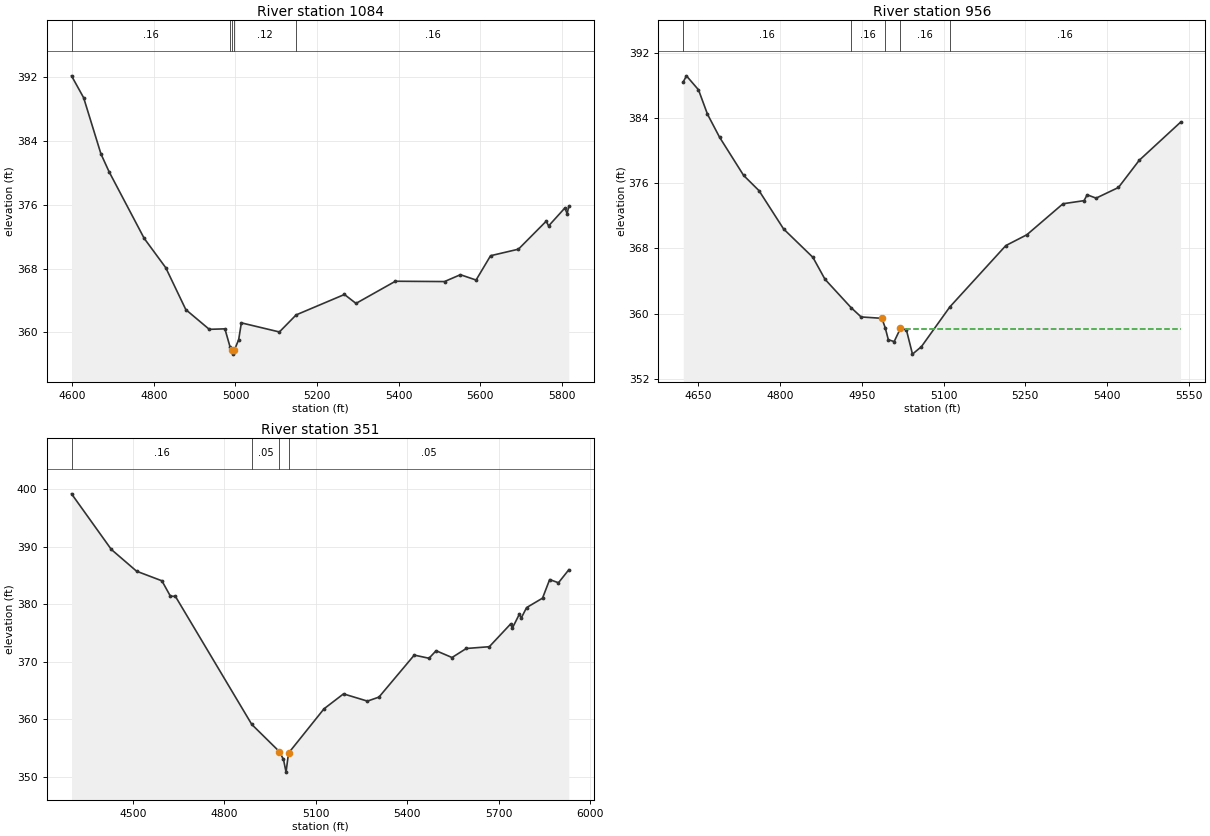
Type RM Length L Ch R = 1 ,1084    ,128,128,128
BEGIN DESCRIPTION:
BEAR CREEK EAST TRIB 6 1.5
END DESCRIPTION:
XS GIS Cut Line= 4
      3538235.37     10424363.63      3538328.68     10424629.45
      3538542.44     10424658.75      3538850.33      10424006.1
#Sta/Elev= 30
  4598.1  392.17  4627.8  389.42  4670.2  382.38    4690  380.16  4776.2  371.79
  4829.2   368.1  4878.3  362.85  4935.8  360.38  4974.1  360.44  4987.1  358.11
  4991.3  357.77  4994.1  357.27  4997.3  357.77  5007.9  359.09  5014.5  361.19
  5107.7  360.05  5148.8  362.19  5267.2  364.75  5295.5  363.63  5392.1  366.41
  5512.5  366.37  5551.5  367.23  5589.9  366.56  5625.4  369.61  5693.7  370.43
    5762  373.95  5767.6  373.34  5807.6   375.6  5813.1  374.88  5817.2   375.8
#Mann= 5 ,-1 , 0
  4598.1     .16       0  4987.1     .12       0  4991.3     .07       0
  4997.3     .12       0  5148.8     .16       0
Bank Sta=4991.3,4997.3
XS Rating Curve= 0 ,0
Exp/Cntr=0.3,0.1

Type RM Length L Ch R = 1 ,956     ,605,605,605
BEGIN DESCRIPTION:
BEAR CREEK EAST TRIB 6 1.4
END DESCRIPTION:
XS GIS Cut Line= 3
      3538186.03     10424398.41      3538554.07      10425106.7
      3538667.91     10425110.15
#Sta/Elev= 30
  4622.7  388.47  4628.5  389.21  4650.6  387.49  4667.1  384.49  4689.2  381.67
  4733.4  376.97  4761.6   375.1  4806.7  370.39  4860.5   366.9  4882.6  364.21
  4930.4  360.73  4948.9  359.58    4987  359.41  4993.2  358.22  4998.8  356.78
  5009.5  356.55  5020.9  358.16  5031.8  358.02  5043.1  355.01  5059.5  355.93
  5111.6  360.81  5214.3  368.35  5252.9  369.68  5319.2  373.49  5357.8  373.87
  5363.5  374.59  5379.9  374.18  5420.9  375.49    5459  378.83  5534.8  383.51
#Mann= 5 ,-1 , 0
  4622.7     .16       0  4930.4     .16       0  4993.2     .12       0
  5020.9     .16       0  5111.6     .16       0
#XS Ineff= 2 , 0
       0                 5031.82       0  358.11
Permanent Ineff=
       F       T
Bank Sta=4987,5020.9
XS Rating Curve= 0 ,0
Exp/Cntr=0.3,0.1

Type RM Length L Ch R = 1 ,351     ,0,0,0
BEGIN DESCRIPTION:
BEAR CREEK EAST TRIB 6 1.0
END DESCRIPTION:
XS GIS Cut Line= 4
      3537599.19     10424446.95      3538008.93     10425238.65
      3538217.26     10425353.23      3538675.57     10425151.85
#Sta/Elev= 30
  4299.1  399.21  4429.5  389.53  4512.4  385.74  4595.3  384.07  4623.1   381.4
  4639.6  381.36  4889.9  359.07    4980  354.36  4993.8  352.98  5002.2  350.77
  5010.3  354.08  5126.6  361.79  5190.5  364.39  5268.9  363.13  5306.7  363.83
  5422.4  371.14  5470.7  370.59    5494   371.9  5546.2  370.72  5592.9  372.29
  5668.4   372.6  5738.5  376.57  5743.9  375.83  5767.3  378.31  5772.8  377.57
  5790.6  379.41  5842.8  381.05  5866.2  384.29    5895  383.73  5928.9  385.99
#Mann= 4 ,-1 , 0
  4299.1     .16       0  4889.9     .05       0    4980     .03       0
  5010.3     .05       0
Bank Sta=4980,5010.3
XS Rating Curve= 0 ,0
Exp/Cntr=0.3,0.1

Chan Stop Cuts=-1
Use User Specified Reach Order=0
Composite Channel Slope=5