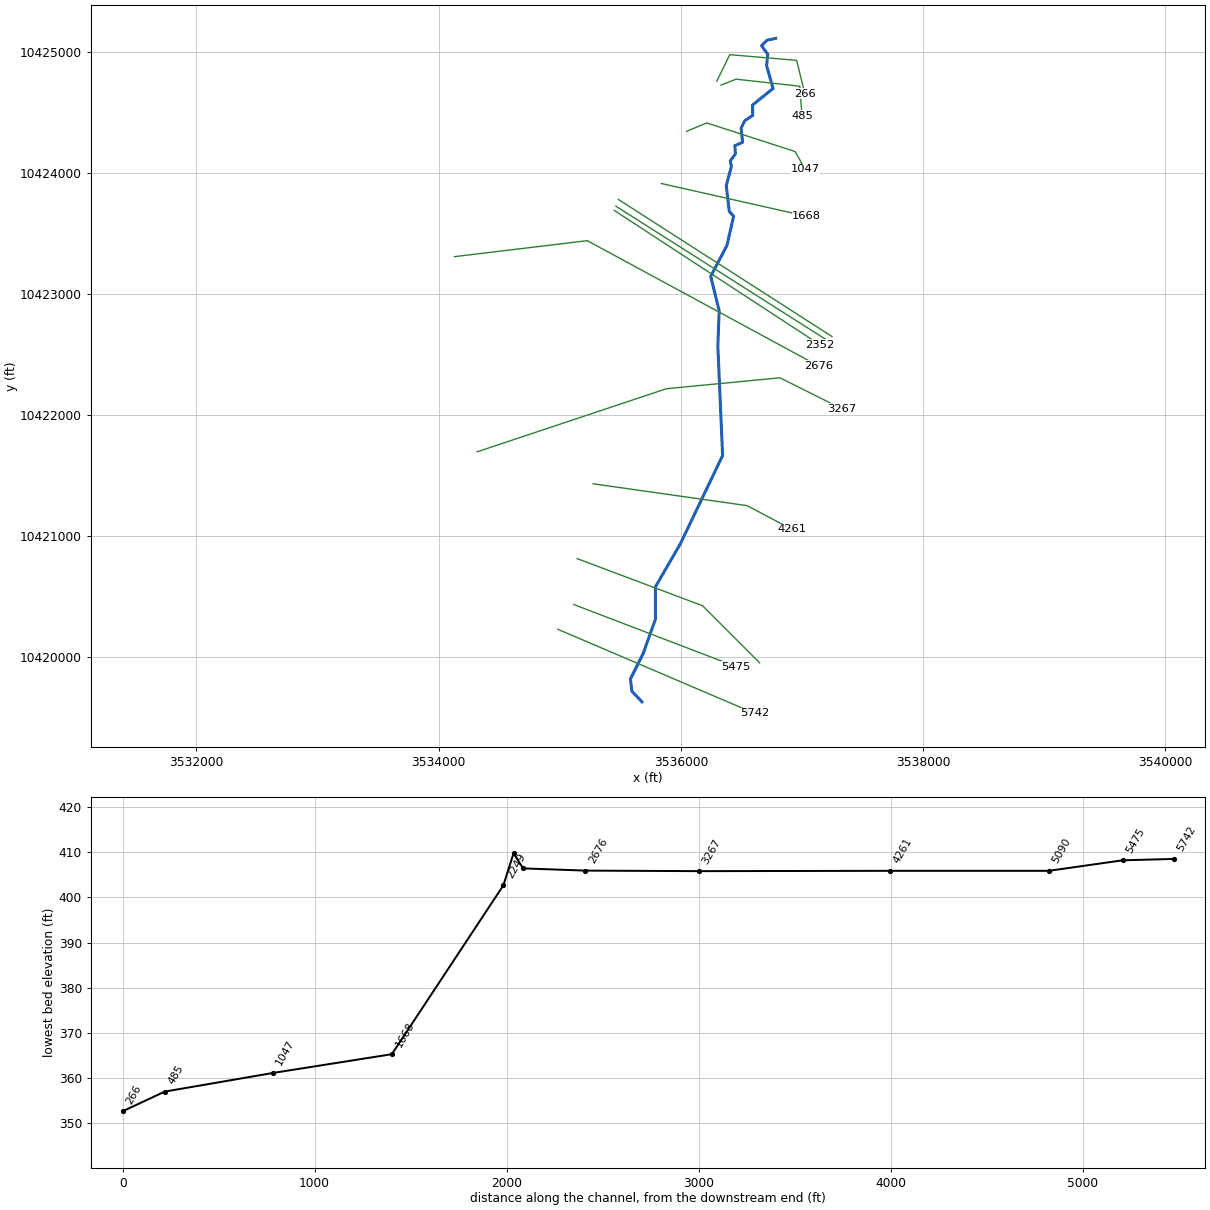
--- BEAR CREEK EAST TRIB 7.prj (project) ---

Proj Title=BEAR CREEK EAST TRIB 7 Base Level Engineering
Current Plan=p01
Default Exp/Contr=0.3,0.1
English Units
Geom File=g01
Flow File=f01
Plan File=p01
BEGIN DESCRIPTION:
BEAR CREEK EAST TRIB 7
END DESCRIPTION:

--- BEAR CREEK EAST TRIB 7.p01 (plan) ---

Plan Title=Multiple Run
Short Identifier=Multiple
Geom File=g01
Flow File=f01
Subcritical Flow
K Sum by GR= 0
Std Step Tol= 0.01
Critical Tol= 0.01
Num of Std Step Trials= 20
Max Error Tol= 0.3
Flow Tol Ratio= 0.001
Split Flow NTrial= 30
Split Flow Tol= 0.02
Split Flow Ratio= 0.02
Log Output Level= 0
Friction Slope Method= 1
Unsteady Friction Slope Method= 2
Unsteady Bridges Friction Slope Method= 1
Parabolic Critical Depth
Global Vel Dist=  1 , 1 , 1
Global Log Level= 0
CheckData=True
Encroach Param= -1, 0, 0, 0
BEGIN DESCRIPTION:
Multiple Run
END DESCRIPTION:

--- BEAR CREEK EAST TRIB 7.f01 (steady flow) ---

Flow Title=Multiple
Number of Profiles=7
Profile Names=10-year,25-year,50-year,1pct_min,100-year,1pct_plu,500-year
River Rch & RM= BEAR CREEK EAST ,Reach-1,5742
    1011    1409    1743    1575    2131    2881    3174
Boundary for River Rch & Prof#=BEAR CREEK EAST ,Reach-1,1
Up Type=0
Dn Type=3
Dn Slope=0.005
Boundary for River Rch & Prof#=BEAR CREEK EAST ,Reach-1,2
Up Type=0
Dn Type=3
Dn Slope=0.005
Boundary for River Rch & Prof#=BEAR CREEK EAST ,Reach-1,3
Up Type=0
Dn Type=3
Dn Slope=0.005
Boundary for River Rch & Prof#=BEAR CREEK EAST ,Reach-1,4
Up Type=0
Dn Type=3
Dn Slope=0.005
Boundary for River Rch & Prof#=BEAR CREEK EAST ,Reach-1,5
Up Type=0
Dn Type=3
Dn Slope=0.005
Boundary for River Rch & Prof#=BEAR CREEK EAST ,Reach-1,6
Up Type=0
Dn Type=3
Dn Slope=0.005
Boundary for River Rch & Prof#=BEAR CREEK EAST ,Reach-1,7
Up Type=0
Dn Type=3
Dn Slope=0.005

--- BEAR CREEK EAST TRIB 7.g01 (geometry) ---

Geom Title=Existing Conditions

River Reach=BEAR CREEK EAST ,Reach-1
Reach XY= 30
      3535677.74     10419633.99      3535594.16     10419722.16
      3535582.86     10419823.69      3535688.73     10420034.64
      3535789.21     10420316.43      3535788.94     10420582.80
      3535995.69     10420940.37      3536343.74     10421666.99
      3536304.34     10422571.09      3536315.38     10422864.23
      3536245.49     10423146.65      3536379.37     10423401.30
      3536434.68     10423643.96      3536398.80     10423682.03
      3536373.91     10423896.68      3536416.19     10424052.85
      3536406.91     10424099.41      3536449.48     10424157.53
      3536444.59     10424225.47      3536508.77     10424253.30
      3536496.54     10424370.78      3536527.80     10424432.63
      3536592.86     10424474.72      3536590.74     10424560.79
      3536760.34     10424697.55      3536706.66     10424886.80
      3536716.75     10424979.90      3536664.94     10425050.44
      3536708.90     10425095.50      3536782.11     10425111.64

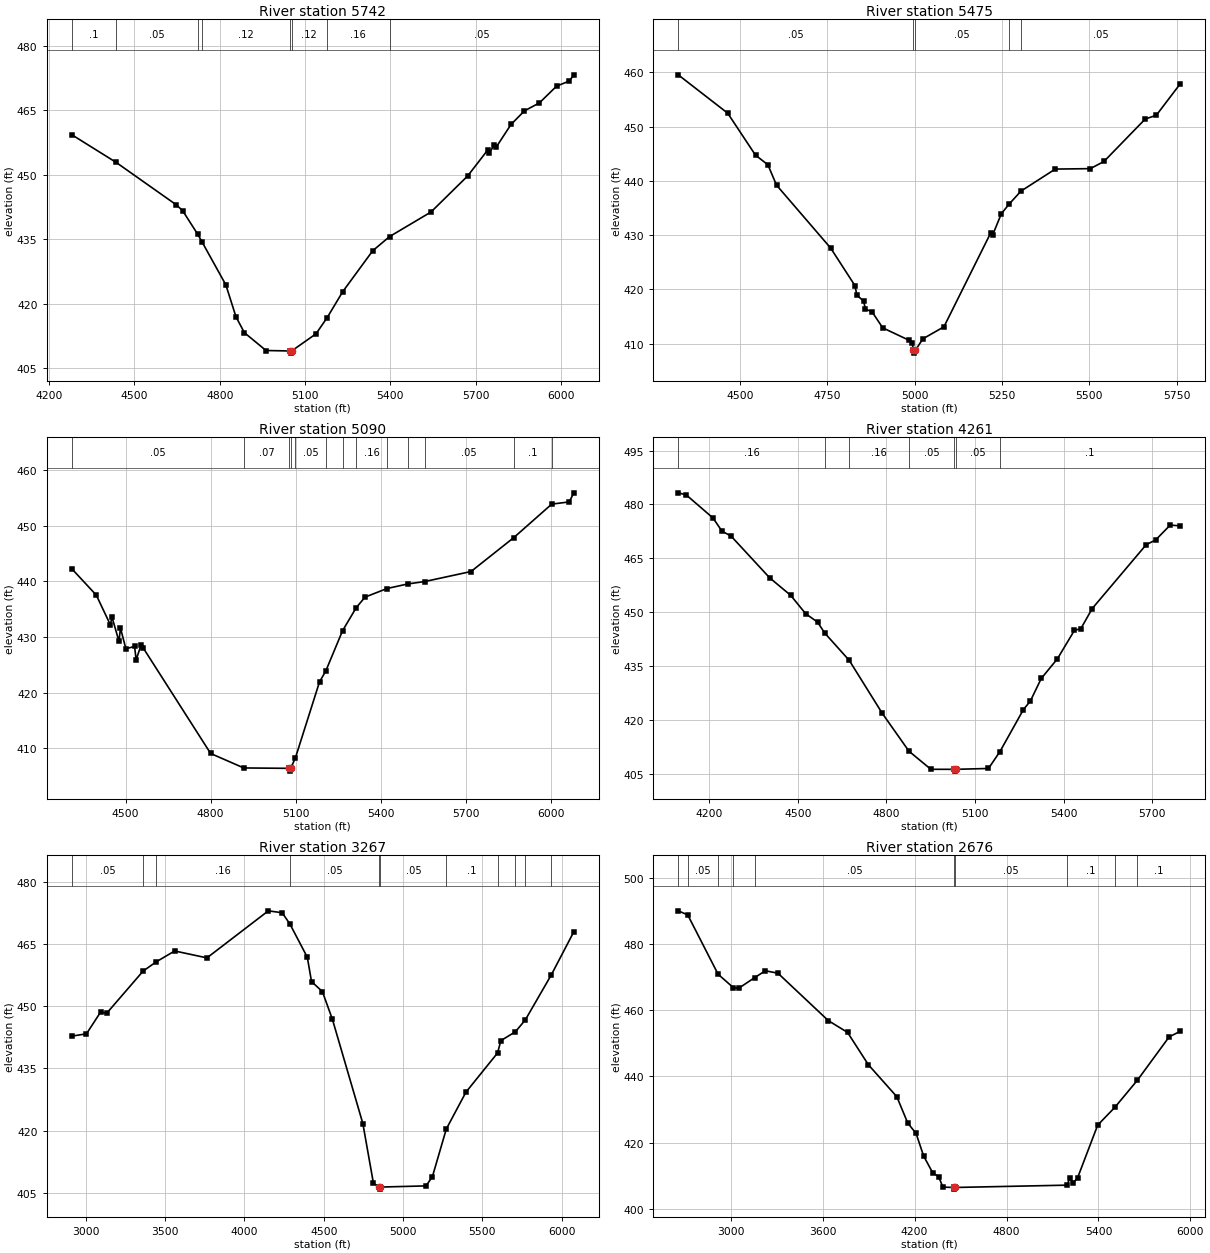
Type RM Length L Ch R = 1,5742,267,267,267
BEGIN DESCRIPTION:
BEAR CREEK EAST TRIB 7 12.0
END DESCRIPTION:
XS GIS Cut Line= 2
      3534983.67     10420232.74      3536607.88     10419538.63
#Sta/Elev= 30
  4279.4  459.31  4435.0  452.90  4646.6  443.04  4669.2  441.68  4722.7  436.15
  4737.5  434.42  4821.4  424.42  4857.1  416.99  4886.7  413.30  4962.8  409.16
  5046.8  409.05  5049.6  408.55  5052.8  409.05  5138.5  413.03  5177.4  416.75
  5232.9  422.86  5338.1  432.34  5397.3  435.63  5543.2  441.35  5672.1  449.72
  5742.9  455.77  5748.3  455.16  5766.5  456.91  5771.9  456.36  5824.6  461.69
  5871.7  464.85  5924.4  466.70  5985.0  470.60  6029.7  471.79  6045.7  473.23
#Mann=8,-1,0
  4279.4     0.1       0  4435.0    0.05       0  4722.7    0.16       0
  4737.5    0.12       0  5046.8    0.07       0  5052.8    0.12       0
  5177.4    0.16       0  5397.3    0.05       0
Bank Sta=5046.8,5052.8
Exp/Cntr=0.3,0.1

Type RM Length L Ch R = 1,5475,385,385,385
BEGIN DESCRIPTION:
Mapping XS 3e3cc60c
END DESCRIPTION:
XS GIS Cut Line= 2
      3535114.88     10420437.17      3536456.10     10419924.12
#Sta/Elev= 30
  4324.1  459.53  4465.6  452.46  4545.1  444.72  4580.5  442.96  4605.2  439.20
  4760.1  427.60  4829.5  420.68  4835.1  418.91  4854.2  417.84  4859.6  416.32
  4877.9  415.91  4909.0  412.90  4984.9  410.59  4993.8  410.07  4996.2  408.74
  4998.9  408.24  5002.2  408.74  5023.9  410.88  5084.0  413.09  5218.2  430.45
  5223.5  430.03  5248.2  433.93  5270.1  435.68  5304.4  438.10  5402.5  442.16
  5502.7  442.24  5541.7  443.56  5659.5  451.37  5691.6  452.09  5760.1  457.89
#Mann=5,-1,0
  4324.1    0.05       0  4996.2    0.03       0  5002.2    0.05       0
  5270.1    0.16       0  5304.4    0.05       0
Bank Sta=4996.2,5002.2
Exp/Cntr=0.3,0.1

Type RM Length L Ch R = 1,5090,829,829,829
BEGIN DESCRIPTION:
BEAR CREEK EAST TRIB 7 11.0
END DESCRIPTION:
XS GIS Cut Line= 3
      3535143.37     10420816.08      3536178.09     10420427.19
      3536649.46     10419955.83
#Sta/Elev= 30
  4310.1  442.25  4396.7  437.51  4446.5  432.16  4451.8  433.62  4476.7  429.22
  4482.0  431.59  4501.0  427.89  4531.8  428.29  4537.2  425.91  4554.5  428.50
  4562.1  428.04  4800.2  409.08  4917.1  406.48  5076.6  406.41  5079.4  405.91
  5082.6  406.41  5099.4  408.29  5184.5  421.94  5206.6  423.89  5265.8  431.12
  5313.7  435.23  5345.0  437.15  5422.8  438.70  5496.1  439.52  5555.8  439.95
  5719.2  441.75  5870.4  447.85  6004.0  453.85  6065.7  454.25  6082.1  455.88
#Mann=13,-1,0
  4310.1    0.05       0  4917.1    0.07       0  5076.6    0.07       0
  5082.6    0.07       0  5099.4    0.05       0  5206.6    0.16       0
  5265.8    0.05       0  5313.7    0.16       0  5422.8    0.05       0
  5496.1    0.16       0  5555.8    0.05       0  5870.4     0.1       0
  6004.0    0.05       0
Bank Sta=5076.6,5082.6
Exp/Cntr=0.3,0.1

Type RM Length L Ch R = 1,4261,994,994,994
BEGIN DESCRIPTION:
BEAR CREEK EAST TRIB 7 10.0
END DESCRIPTION:
XS GIS Cut Line= 3
      3535275.33     10421434.14      3536546.15     10421253.58
      3536914.17     10421059.16
#Sta/Elev= 30
  4095.1  483.24  4122.1  482.67  4213.0  476.23  4243.3  472.57  4273.6  471.25
  4405.0  459.59  4475.7  454.77  4526.2  449.68  4566.6  447.32  4591.3  444.26
  4674.1  436.68  4786.0  421.95  4876.3  411.44  4950.4  406.42  5028.2  406.41
  5030.9  405.91  5034.2  406.41  5145.5  406.65  5184.2  411.33  5263.5  422.98
  5287.3  425.40  5324.1  431.65  5378.7  437.11  5436.3  445.00  5458.3  445.52
  5496.7  451.09  5679.5  468.84  5711.2  470.13  5760.9  474.29  5794.9  474.04
#Mann=7,-1,0
  4095.1    0.16       0  4591.3    0.05       0  4674.1    0.16       0
  4876.3    0.05       0  5028.2   0.033       0  5034.2    0.05       0
  5184.2     0.1       0
Bank Sta=5028.2,5034.2
Exp/Cntr=0.3,0.1

Type RM Length L Ch R = 1,3267,591,591,591
BEGIN DESCRIPTION:
BEAR CREEK EAST TRIB 7 6.0
END DESCRIPTION:
XS GIS Cut Line= 4
      3534317.00     10421698.03      3535879.48     10422218.86
      3536816.98     10422309.14      3537330.89     10422052.18
#Sta/Elev= 30
  2912.6  442.81  3005.3  443.37  3094.9  448.66  3131.8  448.30  3362.3  458.54
  3445.1  460.77  3561.0  463.39  3764.3  461.72  4151.3  473.09  4238.6  472.62
  4287.6  469.86  4396.7  461.87  4423.1  456.00  4491.6  453.58  4554.8  446.87
  4746.6  421.69  4813.4  407.23  4851.0  406.34  4853.8  405.84  4857.0  406.34
  5144.9  406.62  5185.1  408.89  5272.5  420.38  5396.1  429.27  5595.3  438.74
  5616.1  441.72  5708.0  443.87  5770.5  446.75  5933.4  457.57  6076.0  468.04
#Mann=11,-1,0
  2912.6    0.05       0  3362.3     0.1       0  3445.1    0.16       0
  4287.6    0.05       0  4851.0   0.033       0  4857.0    0.05       0
  5272.5     0.1       0  5595.3    0.05       0  5708.0     0.1       0
  5770.5    0.05       0  5933.4     0.1       0
Bank Sta=4851,4857
Exp/Cntr=0.3,0.1

Type RM Length L Ch R = 1,2676,324,324,324
BEGIN DESCRIPTION:
BEAR CREEK EAST TRIB 7 9.0
END DESCRIPTION:
XS GIS Cut Line= 3
      3534129.47     10423309.14      3535226.70     10423441.08
      3537136.19     10422406.48
#Sta/Elev= 30
  2657.2  489.98  2719.2  488.75  2917.3  470.84  3016.4  466.81  3051.4  466.59
  3155.9  469.81  3225.8  471.88  3307.9  471.15  3636.6  456.84  3762.3  453.27
  3898.4  443.50  4083.9  433.86  4155.2  425.90  4209.4  422.79  4258.8  415.96
  4318.8  410.83  4356.8  409.74  4384.4  406.57  4457.5  406.46  4460.2  405.96
  4463.5  406.46  5194.8  407.16  5212.9  409.27  5235.5  407.91  5263.1  409.31
  5394.9  425.29  5507.6  430.69  5654.2  438.85  5861.2  451.92  5934.1  453.62
#Mann=10,-1,0
  2657.2     0.1       0  2719.2    0.05       0  2917.3     0.1       0
  3016.4    0.16       0  3155.9    0.05       0  4457.5   0.033       0
  4463.5    0.05       0  5194.8     0.1       0  5507.6    0.05       0
  5654.2     0.1       0
Bank Sta=4457.5,4463.5
Exp/Cntr=0.3,0.1

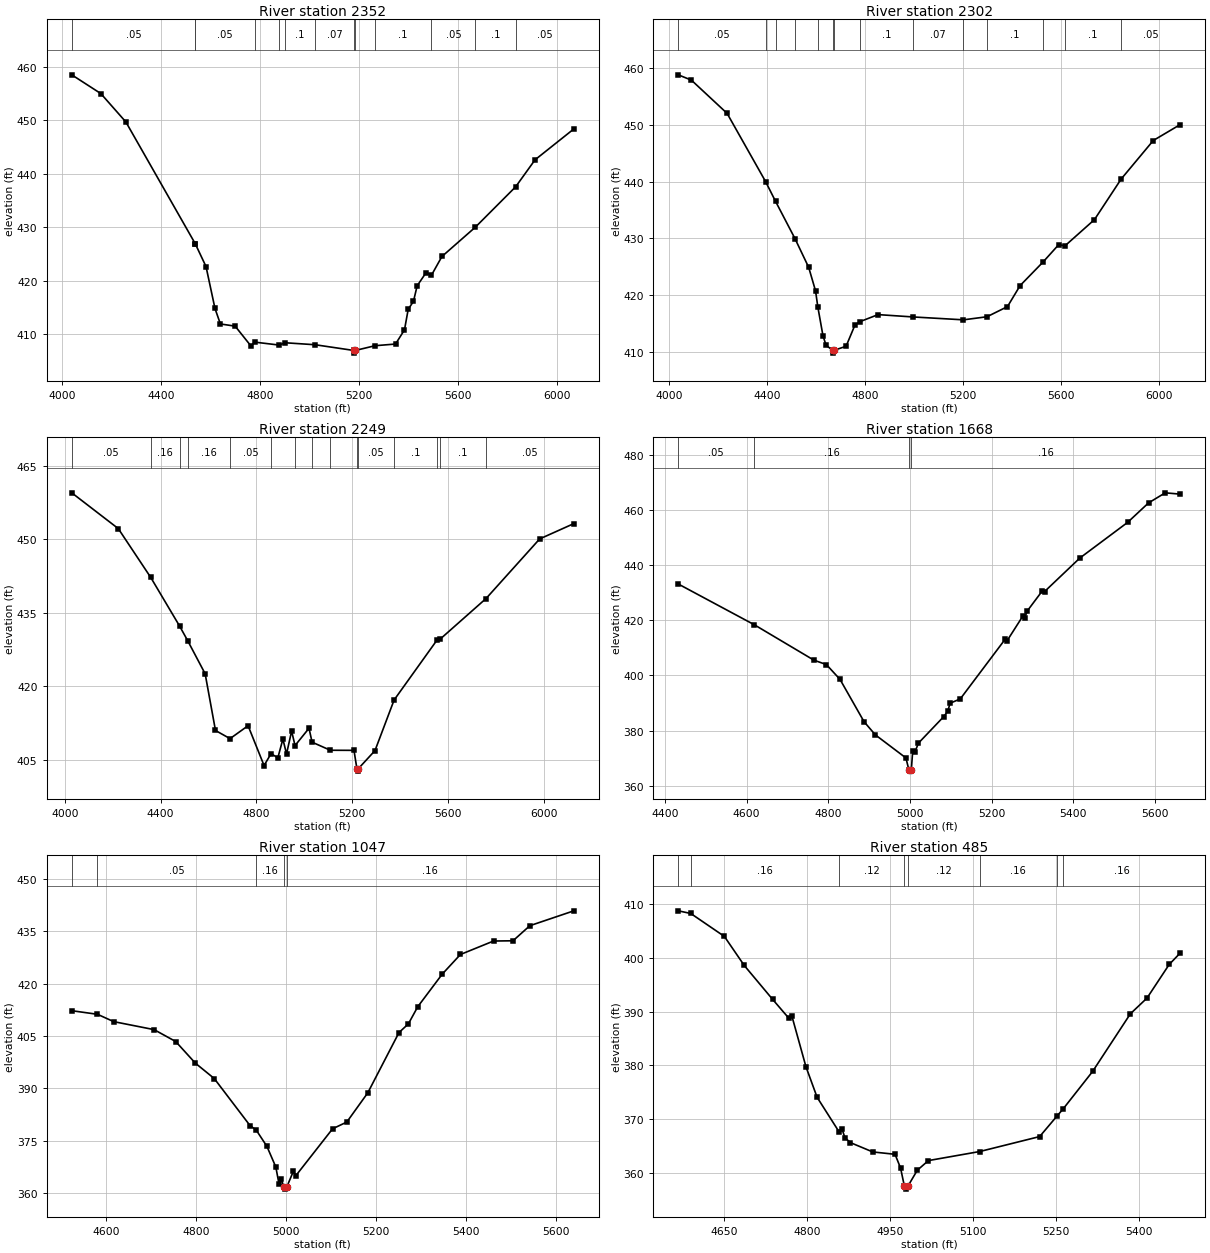
Type RM Length L Ch R = 1,2352,50,50,50
BEGIN DESCRIPTION:
Mapping XS 7c7d53b6
END DESCRIPTION:
XS GIS Cut Line= 2
      3535448.96     10423691.06      3537148.71     10422581.02
#Sta/Elev= 30
  4039.9  458.55  4157.4  455.04  4258.6  449.73  4539.3  426.92  4539.7  426.88
  4582.7  422.66  4618.9  414.82  4640.8  411.91  4700.5  411.50  4763.7  407.83
  4781.6  408.50  4878.2  407.96  4902.8  408.39  5024.0  408.02  5180.1  406.95
  5182.8  406.45  5186.1  406.95  5266.3  407.84  5349.0  408.15  5385.2  410.81
  5400.3  414.67  5421.4  416.13  5436.5  419.06  5472.7  421.53  5494.1  421.02
  5536.6  424.54  5672.0  430.04  5834.7  437.59  5913.1  442.64  6070.0  448.42
#Mann=13,-1,0
  4039.9    0.05       0  4539.3    0.16       0  4539.7    0.05       0
  4781.6     0.1       0  4878.2    0.07       0  4902.8     0.1       0
  5024.0    0.07       0  5180.1    0.07       0  5186.1    0.07       0
  5266.3     0.1       0  5494.1    0.05       0  5672.0     0.1       0
  5834.7    0.05       0
Bank Sta=5180.1,5186.1
Exp/Cntr=0.3,0.1

Type RM Length L Ch R = 1,2302,53,53,53
BEGIN DESCRIPTION:
Mapping XS e3c29b4e
END DESCRIPTION:
XS GIS Cut Line= 2
      3535462.79     10423725.82      3537191.95     10422628.60
#Sta/Elev= 30
  4037.9  458.83  4091.4  457.90  4237.1  452.04  4394.2  440.01  4434.8  436.53
  4514.3  429.94  4570.0  424.89  4598.0  420.74  4607.2  417.93  4628.5  412.78
  4641.1  411.15  4667.8  410.27  4670.6  409.77  4673.8  410.27  4722.5  410.98
  4758.9  414.74  4779.7  415.33  4853.0  416.56  4994.5  416.15  5201.3  415.64
  5297.1  416.18  5380.8  417.97  5432.4  421.68  5525.9  425.83  5590.0  428.90
  5615.3  428.68  5735.7  433.31  5844.7  440.47  5975.5  447.25  6085.8  450.07
#Mann=14,-1,0
  4037.9    0.05       0  4394.2    0.16       0  4434.8    0.05       0
  4514.3    0.16       0  4607.2    0.05       0  4667.8    0.07       0
  4673.8    0.05       0  4779.7     0.1       0  4994.5    0.07       0
  5201.3    0.05       0  5297.1     0.1       0  5525.9    0.05       0
  5615.3     0.1       0  5844.7    0.05       0
Bank Sta=4667.8,4673.8
Exp/Cntr=0.3,0.1

Type RM Length L Ch R = 1,2249,581,581,581
BEGIN DESCRIPTION:
Mapping XS 0a81cb92
END DESCRIPTION:
XS GIS Cut Line= 2
      3535483.61     10423781.38      3537247.29     10422649.58
#Sta/Elev= 30
  4029.2  459.49  4223.3  452.19  4358.7  442.23  4479.2  432.30  4512.8  429.33
  4585.9  422.56  4629.0  410.99  4689.8  409.32  4765.1  411.96  4831.8  403.83
  4861.0  406.26  4889.3  405.40  4910.4  409.23  4925.6  406.19  4946.8  410.86
  4961.1  407.91  5019.4  411.44  5032.2  408.60  5108.5  406.95  5207.1  406.93
  5219.3  403.19  5222.0  402.69  5225.3  403.19  5294.9  406.89  5374.6  417.21
  5553.8  429.45  5566.5  429.62  5758.4  437.92  5982.1  450.08  6124.8  453.21
#Mann=15,-1,0
  4029.2    0.05       0  4358.7    0.16       0  4479.2    0.05       0
  4512.8    0.16       0  4689.8    0.05       0  4861.0     0.1       0
  4961.1    0.05       0  5032.2    0.07       0  5108.5    0.05       0
  5219.3    0.04       0  5225.3    0.05       0  5374.6     0.1       0
  5553.8    0.05       0  5566.5     0.1       0  5758.4    0.05       0
Bank Sta=5219.3,5225.3
Exp/Cntr=0.3,0.1

Type RM Length L Ch R = 1,1668,621,621,621
BEGIN DESCRIPTION:
BEAR CREEK EAST TRIB 7 3.0
END DESCRIPTION:
XS GIS Cut Line= 2
      3535837.86     10423913.29      3537038.14     10423642.71
#Sta/Elev= 30
  4432.3  433.14  4618.9  418.34  4764.7  405.52  4795.4  403.91  4828.8  398.53
  4887.7  383.19  4915.3  378.43  4990.2  370.06  4997.5  365.77  5000.2  365.27
  5003.5  365.77  5006.9  372.57  5012.0  372.07  5021.0  375.44  5082.5  384.97
  5092.7  386.96  5098.5  389.90  5123.5  391.46  5233.3  413.07  5238.5  412.63
  5276.6  421.46  5281.7  420.93  5287.5  423.33  5324.9  430.72  5330.1  430.40
  5416.5  442.55  5533.5  455.47  5584.8  462.54  5625.8  466.20  5662.7  465.72
#Mann=4,-1,0
  4432.3    0.05       0  4618.9    0.16       0  4997.5    0.07       0
  5003.5    0.16       0
Bank Sta=4997.5,5003.5
Exp/Cntr=0.3,0.1

Type RM Length L Ch R = 1,1047,562,562,562
BEGIN DESCRIPTION:
BEAR CREEK EAST TRIB 7 2.0
END DESCRIPTION:
XS GIS Cut Line= 4
      3536046.17     10424343.87      3536212.81     10424413.31
      3536941.98     10424177.19      3537025.30     10424031.39
#Sta/Elev= 30
  4523.8  412.21  4580.9  411.18  4616.9  409.08  4706.6  406.79  4754.6  403.38
  4798.2  397.19  4840.2  392.78  4919.9  379.26  4933.2  378.05  4957.1  373.36
  4976.9  367.44  4983.9  362.65  4989.1  363.95  4994.9  361.60  4997.6  361.10
  5000.9  361.60  5015.9  366.22  5021.1  364.91  5103.0  378.39  5134.5  380.31
  5181.1  388.68  5250.4  405.95  5271.2  408.43  5292.2  413.37  5346.4  422.68
  5386.8  428.31  5460.4  432.17  5503.6  432.24  5541.0  436.56  5638.7  440.82
#Mann=5,-1,0
  4523.8    0.16       0  4580.9    0.05       0  4933.2    0.16       0
  4994.9    0.07       0  5000.9    0.16       0
Bank Sta=4994.9,5000.9
Exp/Cntr=0.3,0.1

Type RM Length L Ch R = 1,485,219,219,219
BEGIN DESCRIPTION:
BEAR CREEK EAST TRIB 7 1.1
END DESCRIPTION:
XS GIS Cut Line= 4
      3536330.87     10424725.80      3536455.87     10424774.42
      3536980.89     10424716.40      3536999.12     10424471.61
#Sta/Elev= 30
  4567.3  408.76  4589.9  408.27  4650.7  404.00  4686.7  398.59  4737.9  392.29
  4767.6  388.74  4772.6  389.25  4798.2  379.76  4818.4  374.06  4857.9  367.67
  4863.4  368.17  4868.7  366.55  4878.7  365.63  4919.0  363.90  4959.3  363.46
  4969.3  360.90  4976.3  357.48  4979.1  356.98  4982.3  357.48  4999.5  360.49
  5019.6  362.29  5112.6  363.98  5220.8  366.76  5251.6  370.51  5262.9  371.86
  5316.5  378.87  5384.8  389.60  5414.9  392.53  5455.0  398.78  5475.1  400.93
#Mann=8,-1,0
  4567.3    0.12       0  4589.9    0.16       0  4857.9    0.12       0
  4976.3    0.07       0  4982.3    0.12       0  5112.6    0.16       0
  5251.6    0.12       0  5262.9    0.16       0
Bank Sta=4976.3,4982.3
Exp/Cntr=0.3,0.1

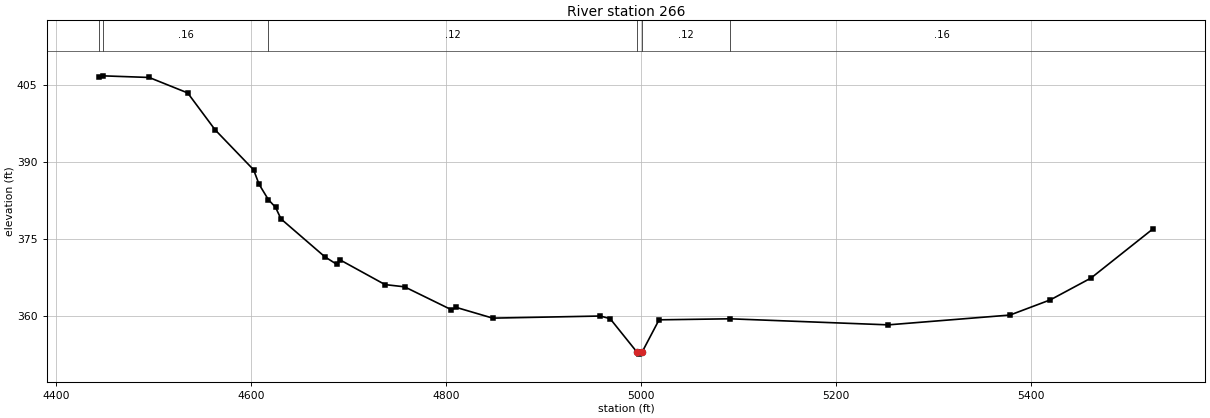
Type RM Length L Ch R = 1,266,0,0,0
BEGIN DESCRIPTION:
BEAR CREEK EAST TRIB 7 1.0
END DESCRIPTION:
XS GIS Cut Line= 4
      3536295.97     10424758.03      3536402.76     10424976.81
      3536954.85     10424929.94      3537022.21     10424655.31
#Sta/Elev= 30
  4444.4  406.57  4447.7  406.83  4495.5  406.51  4535.0  403.50  4563.1  396.32
  4602.6  388.53  4608.2  385.71  4617.7  382.73  4625.1  381.22  4630.7  378.96
  4675.7  371.58  4687.8  370.13  4691.1  371.00  4737.4  366.17  4757.4  365.74
  4805.4  361.28  4810.4  361.73  4847.8  359.64  4958.2  360.05  4968.2  359.54
  4995.3  353.13  4998.1  352.63  5001.3  353.13  5018.4  359.31  5091.2  359.51
  5253.5  358.33  5378.3  360.24  5419.8  363.21  5461.4  367.45  5524.7  376.99
#Mann=6,-1,0
  4444.4    0.12       0  4447.7    0.16       0  4617.7    0.12       0
  4995.3    0.07       0  5001.3    0.12       0  5091.2    0.16       0
Bank Sta=4995.3,5001.3
Exp/Cntr=0.3,0.1

Chan Stop Cuts=-1