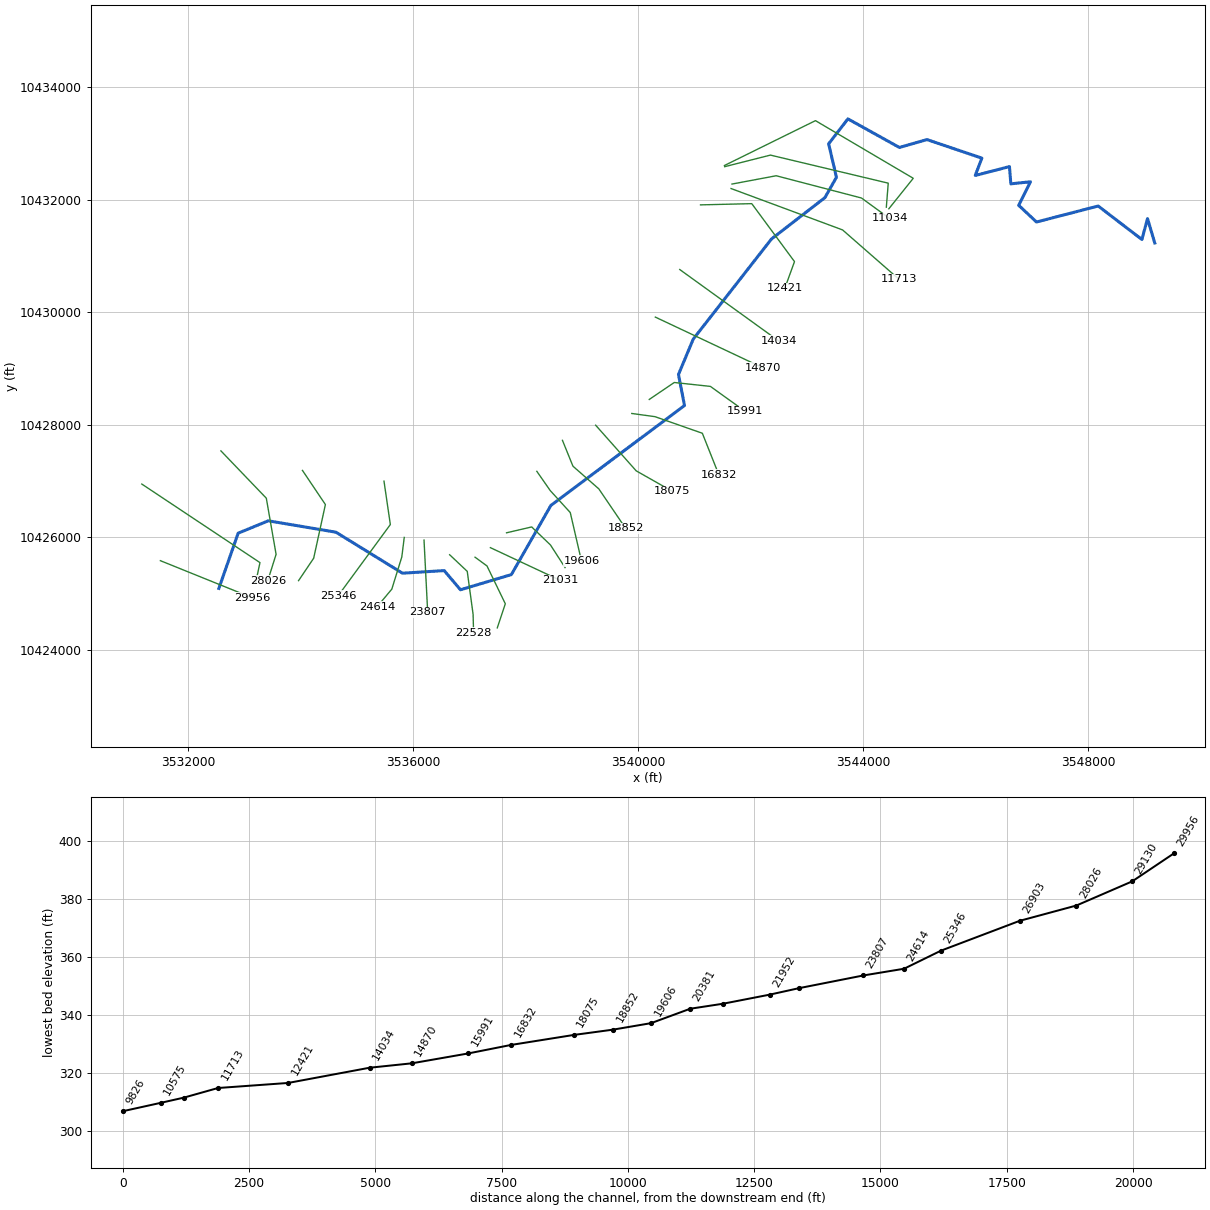
--- BEAR CREEK EAST.prj (project) ---

Proj Title=BEAR CREEK EAST Base Level Engineering
Current Plan=p01
Default Exp/Contr=0.3,0.1
English Units
Geom File=g01
Flow File=f01
Plan File=p01
Y Axis Title=Elevation
X Axis Title(PF)=Main Channel Distance
X Axis Title(XS)=Station
BEGIN DESCRIPTION:
BEAR CREEK EAST
END DESCRIPTION:
DSS Export Rating Curves= 0
DSS Export Rating Curve Sorted= 0
DSS Export Volume Flow Curves= 0
DXF OffsetX= 0
DXF OffsetY= 0
DXF ScaleX= 1
DXF ScaleY= 10

--- BEAR CREEK EAST.p01 (plan) ---

Plan Title=Multiple Run
Short Identifier=Multiple
Geom File=g01
Flow File=f01
Subcritical Flow
K Sum by GR= 0
Std Step Tol= 0.01
Critical Tol= 0.01
Num of Std Step Trials= 20
Max Error Tol= 0.3
Flow Tol Ratio= 0.001
Split Flow NTrial= 30
Split Flow Tol= 0.02
Split Flow Ratio= 0.02
Log Output Level= 0
Friction Slope Method= 1
Unsteady Friction Slope Method= 2
Unsteady Bridges Friction Slope Method= 1
Parabolic Critical Depth
Global Vel Dist=  1 , 1 , 1
Global Log Level= 0
CheckData=True
Encroach Param= -1, 0, 0, 0
BEGIN DESCRIPTION:
Multiple Run
END DESCRIPTION:

--- BEAR CREEK EAST.f01 (steady flow) ---

Flow Title=Multiple
Program Version=4.10
Number of Profiles= 7
Profile Names=10-year,25-year,50-year,1pct_min,100-year,1pct_plu,500-year
River Rch & RM=BEAR CREEK EAST,Reach-1         ,29956
    1466    2108    2662    2457    3322    4493    5161
River Rch & RM=BEAR CREEK EAST,Reach-1         ,28026
    1853    2681    3401    3147    4255    5755    6648
River Rch & RM=BEAR CREEK EAST,Reach-1         ,22528
    2456    3603    4612    4302    5818    7868    9240
River Rch & RM=BEAR CREEK EAST,Reach-1         ,21031
    3078    4540    5831    5451    7371    9969   11760
River Rch & RM=BEAR CREEK EAST,Reach-1         ,14870
    3391    5001    6421    5996    8108   10966   12912
River Rch & RM=BEAR CREEK EAST,Reach-1         ,11713
    3678    5411    6934    6457    8733   11810   13832
River Rch & RM=BEAR CREEK EAST,Reach-1         ,11034
    3678    5411    6934    6457    8733   11810   13832
Boundary for River Rch & Prof#=BEAR CREEK EAST,Reach-1         , 1
Up Type= 0
Dn Type= 3
Dn Slope=0.005
Boundary for River Rch & Prof#=BEAR CREEK EAST,Reach-1         , 2
Up Type= 0
Dn Type= 3
Dn Slope=0.005
Boundary for River Rch & Prof#=BEAR CREEK EAST,Reach-1         , 3
Up Type= 0
Dn Type= 3
Dn Slope=0.005
Boundary for River Rch & Prof#=BEAR CREEK EAST,Reach-1         , 4
Up Type= 0
Dn Type= 3
Dn Slope=0.005
Boundary for River Rch & Prof#=BEAR CREEK EAST,Reach-1         , 5
Up Type= 0
Dn Type= 3
Dn Slope=0.005
Boundary for River Rch & Prof#=BEAR CREEK EAST,Reach-1         , 6
Up Type= 0
Dn Type= 3
Dn Slope=0.005
Boundary for River Rch & Prof#=BEAR CREEK EAST,Reach-1         , 7
Up Type= 0
Dn Type= 3
Dn Slope=0.005
DSS Import GetInterval= 0
DSS Import GetPeak= 0
DSS Import FillOption= 0

--- BEAR CREEK EAST.g01 (geometry) ---

Geom Title=Existing Conditions
Program Version=4.10

River Reach=BEAR CREEK EAST ,Reach-1
Reach XY= 30
      3532543.11     10425087.45       3532885.9     10426069.91
      3533422.45     10426290.29      3534624.55     10426087.62
      3535807.32     10425358.24      3536548.98     10425404.55
      3536838.21     10425063.48      3537743.56      10425333.4
      3538445.97     10426563.94      3540821.66     10428341.01
      3540714.22     10428892.97       3540977.4      10429523.2
      3542366.96     10431302.73      3543317.35     10432038.83
      3543523.06       10432401.      3543384.07     10432996.27
      3543726.77     10433440.02      3544642.09     10432931.52
      3545132.02      10433071.8      3546107.71     10432741.94
       3545990.7     10432433.26      3546598.69     10432591.24
      3546623.34      10432284.3       3546972.3     10432321.45
      3546762.96     10431902.46      3547079.29      10431605.7
       3548176.4     10431889.83      3548953.55     10431294.25
      3549053.37     10431666.35      3549182.11     10431231.64

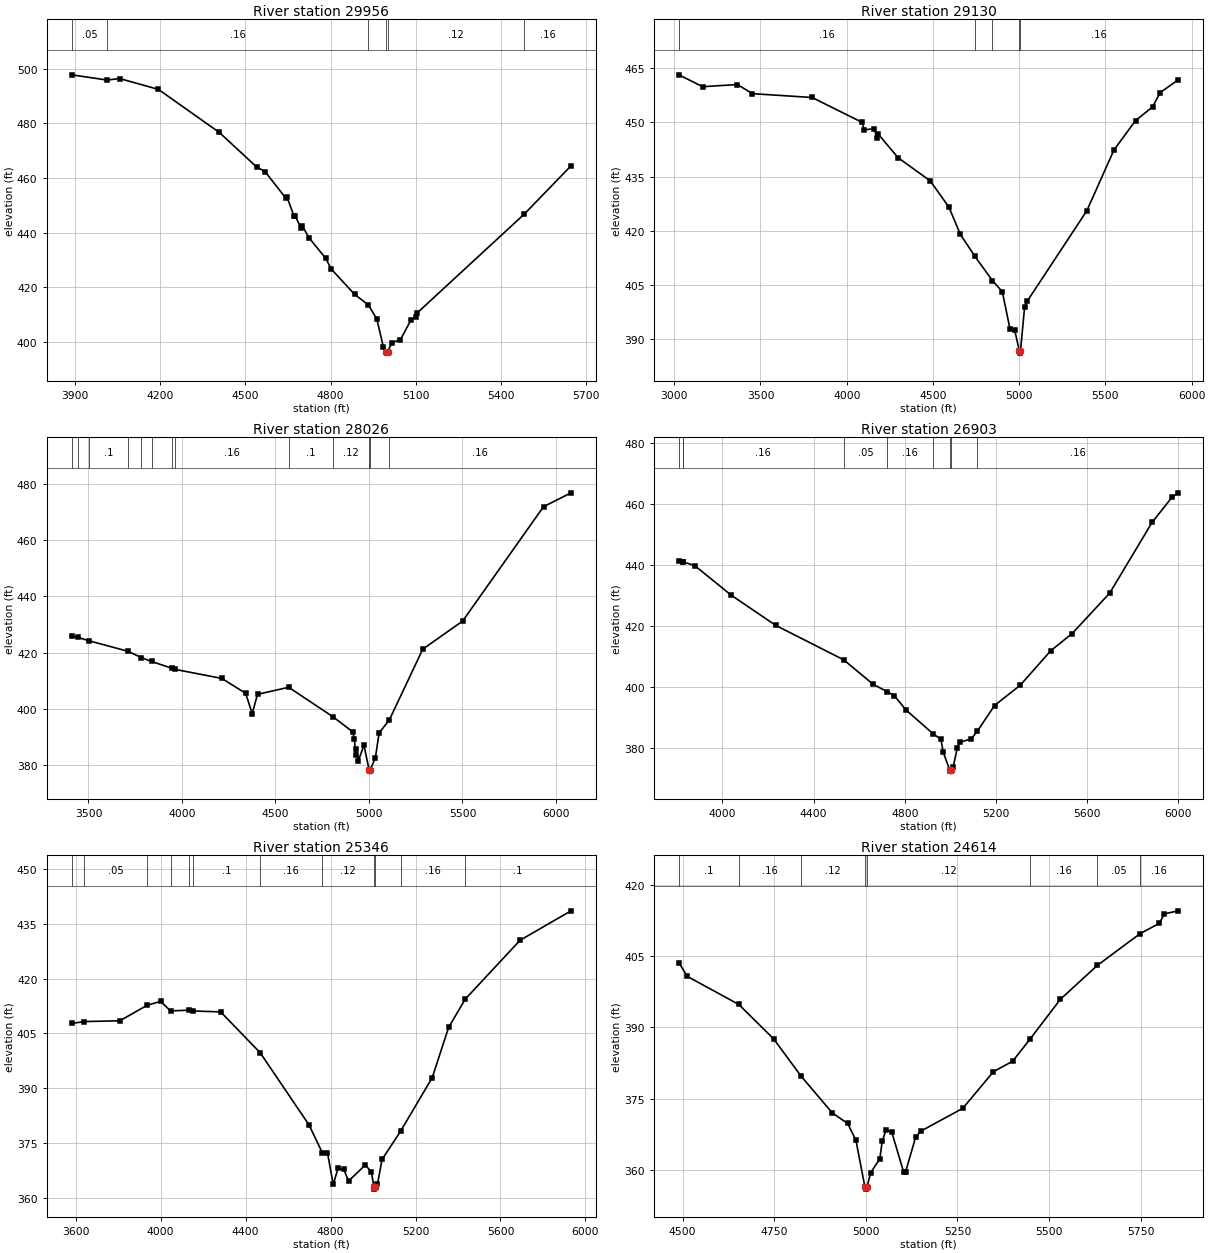
Type RM Length L Ch R = 1 ,29956   ,826,826,826
BEGIN DESCRIPTION:
BEAR CREEK EAST 41.0
END DESCRIPTION:
XS GIS Cut Line= 2
       3531503.1     10425581.14        3533135.     10424921.44
#Sta/Elev= 30
  3887.3  497.84  4012.3  495.93  4056.4  496.48  4193.2   492.5  4407.8  476.72
  4539.2  464.08  4568.8   462.4  4641.1  452.79  4646.5  452.98  4670.7   446.2
    4676   446.1  4694.8  441.74  4700.2  442.52  4724.3  438.04  4783.3  430.52
  4802.1  426.66  4885.2  417.33  4933.4  413.46    4963  408.32  4986.4  397.95
  4994.9  396.33  4997.7  395.83  5000.9  396.33  5016.7  399.67  5046.2  400.79
  5083.5  407.96  5099.8  409.02  5105.2  410.56  5482.6  446.78  5647.5  464.49
#Mann= 6 ,-1 , 0
  3887.3     .05       0  4012.3     .16       0  4933.4     .12       0
  4994.9     .07       0  5000.9     .12       0  5482.6     .16       0
Bank Sta=4994.9,5000.9
XS Rating Curve= 0 ,0
Exp/Cntr=0.3,0.1

Type RM Length L Ch R = 1 ,29130   ,1104,1104,1104
BEGIN DESCRIPTION:
BEAR CREEK EAST 39.0
END DESCRIPTION:
XS GIS Cut Line= 3
      3531173.24     10426943.98       3533273.9     10425546.44
      3533195.78     10425181.88
#Sta/Elev= 30
  3026.7  463.17  3164.9  459.89  3366.3  460.48  3453.5  457.96  3799.1   456.9
  4087.7  450.06  4102.7  447.96  4159.8  448.26  4174.8  445.75  4180.9  446.88
  4298.1  440.23  4484.4  433.83  4592.7  426.57  4658.8  419.05  4743.6  412.93
  4845.3  406.22  4902.3  403.18  4947.1  392.79  4974.4  392.47  5001.5  386.68
  5004.2  386.18  5007.5  386.68  5031.5  398.88  5046.5  400.53  5392.2  425.56
  5549.6  442.37    5675  450.53  5773.8  454.31  5818.1  458.28  5922.6   461.8
#Mann= 5 ,-1 , 0
  3026.7     .16       0  4743.6     .12       0  4845.3     .16       0
  5001.5     .07       0  5007.5     .16       0
Bank Sta=5001.5,5007.5
XS Rating Curve= 0 ,0
Exp/Cntr=0.3,0.1

Type RM Length L Ch R = 1 ,28026   ,1123,1123,1123
BEGIN DESCRIPTION:
BEAR CREEK EAST 37.0
END DESCRIPTION:
XS GIS Cut Line= 4
      3532579.46     10427534.27      3533386.74     10426692.27
      3533560.35     10425694.01      3533413.01     10425225.98
#Sta/Elev= 30
  3410.2   425.8  3444.7  425.43  3502.2  424.26  3711.2  420.51  3782.4  418.28
  3837.7  416.88    3949   414.4  3962.7  414.07  4213.2  410.85  4340.6  405.56
  4375.8  398.33  4404.1  405.18  4570.7   407.7  4810.1  397.09  4912.3  391.88
  4922.4  389.34  4928.2  383.67  4933.3   385.7  4942.7  381.36  4973.2  387.13
  5000.6  378.36  5003.4  377.86  5006.6  378.36  5034.1  382.48  5054.4  391.46
  5108.8  396.06  5287.8  421.25    5501  431.26  5933.4  471.95  6080.6  476.89
#Mann= 13 ,-1 , 0
  3410.2      .1       0  3444.7     .05       0  3502.2      .1       0
  3711.2     .16       0  3782.4      .1       0  3837.7     .16       0
    3949      .1       0  3962.7     .16       0  4570.7      .1       0
  4810.1     .12       0  5000.6     .07       0  5006.6     .12       0
  5108.8     .16       0
Bank Sta=5000.6,5006.6
XS Rating Curve= 0 ,0
Exp/Cntr=0.3,0.1

Type RM Length L Ch R = 1 ,26903   ,1557,1557,1557
BEGIN DESCRIPTION:
BEAR CREEK EAST 34.0
END DESCRIPTION:
XS GIS Cut Line= 4
      3534029.11     10427187.05      3534437.09     10426579.42
      3534228.76     10425624.56      3533960.12     10425225.94
#Sta/Elev= 30
  3809.4  441.18  3825.6  441.14    3826  441.11  3879.9  439.77  4038.9  430.16
  4233.9  420.28  4531.6  409.03  4661.8  400.97  4722.4  398.62    4754   397.3
  4805.1   392.6    4925  384.75  4958.5  383.02  4968.9  378.69  4996.6  373.08
  4999.3  372.58  5002.6  373.08  5012.6  374.06  5030.3  380.14  5040.5     382
  5091.7  383.15  5118.2  385.62  5193.5  394.05  5306.7  400.72  5439.7  411.94
  5533.8   417.6  5698.7  430.84  5884.7     454  5971.6  462.18  5999.3  463.65
#Mann= 9 ,-1 , 0
  3809.4     .16       0  3825.6      .1       0    3826     .16       0
  4531.6     .05       0  4722.4     .16       0    4925     .12       0
  4996.6     .07       0  5002.6     .12       0  5118.2     .16       0
Bank Sta=4996.6,5002.6
XS Rating Curve= 0 ,0
Exp/Cntr=0.3,0.1

Type RM Length L Ch R = 1 ,25346   ,732,732,732
BEGIN DESCRIPTION:
BEAR CREEK EAST 32.0
END DESCRIPTION:
XS GIS Cut Line= 3
      3535478.76     10426996.06       3535591.6     10426223.52
      3534662.97     10424956.41
#Sta/Elev= 30
  3580.7  407.74  3641.1  408.26  3807.5  408.47    3937  412.75  3999.5  413.78
  4046.6  411.18  4134.2  411.38  4152.2  411.16  4282.5  410.91  4468.8  399.69
  4698.5  379.92    4761  372.31  4785.3  372.34  4812.6  363.59  4834.9  367.98
  4862.8   367.7  4884.5  364.51  4963.1   368.9  4992.4  367.05  5004.1   362.8
  5006.8   362.3  5010.1   362.8  5020.9  363.67  5042.6  370.44    5130  378.21
  5278.8  392.88    5356  406.66  5434.4  414.42  5692.6  430.56  5932.4  438.63
#Mann= 12 ,-1 , 0
  3580.7      .1       0  3641.1     .05       0    3937     .16       0
  4046.6     .05       0  4134.2     .16       0  4152.2      .1       0
  4468.8     .16       0    4761     .12       0  5004.1     .07       0
  5010.1     .12       0    5130     .16       0  5434.4      .1       0
Bank Sta=5004.1,5010.1
XS Rating Curve= 0 ,0
Exp/Cntr=0.3,0.1

Type RM Length L Ch R = 1 ,24614   ,807,807,807
BEGIN DESCRIPTION:
BEAR CREEK EAST 30.0
END DESCRIPTION:
XS GIS Cut Line= 4
      3535838.99     10425994.53       3535795.6     10425647.35
      3535617.65     10425074.43      3535352.89     10424757.59
#Sta/Elev= 30
  4489.8   403.6  4512.9  400.72  4653.1  394.84  4748.3  387.62  4823.7  379.74
  4908.5  372.06  4950.4  369.84    4973   366.3  4997.3  356.56  5000.1  356.06
  5003.3  356.56  5013.2  359.51  5038.1  362.42  5044.6  366.07  5055.1  368.52
  5070.7  368.03  5103.3  359.61  5108.5  359.69  5135.8  366.97  5149.3  368.21
  5264.5  373.02  5348.3  380.73  5400.6  382.91  5447.9  387.55    5531  395.93
  5631.5  403.02  5748.2   409.7  5800.4  411.84  5814.7  413.86  5852.5  414.49
#Mann= 8 ,-1 , 0
  4489.8      .1       0  4653.1     .16       0  4823.7     .12       0
  4997.3     .07       0  5003.3     .12       0  5447.9     .16       0
  5631.5     .05       0  5748.2     .16       0
Bank Sta=4997.3,5003.3
XS Rating Curve= 0 ,0
Exp/Cntr=0.3,0.1

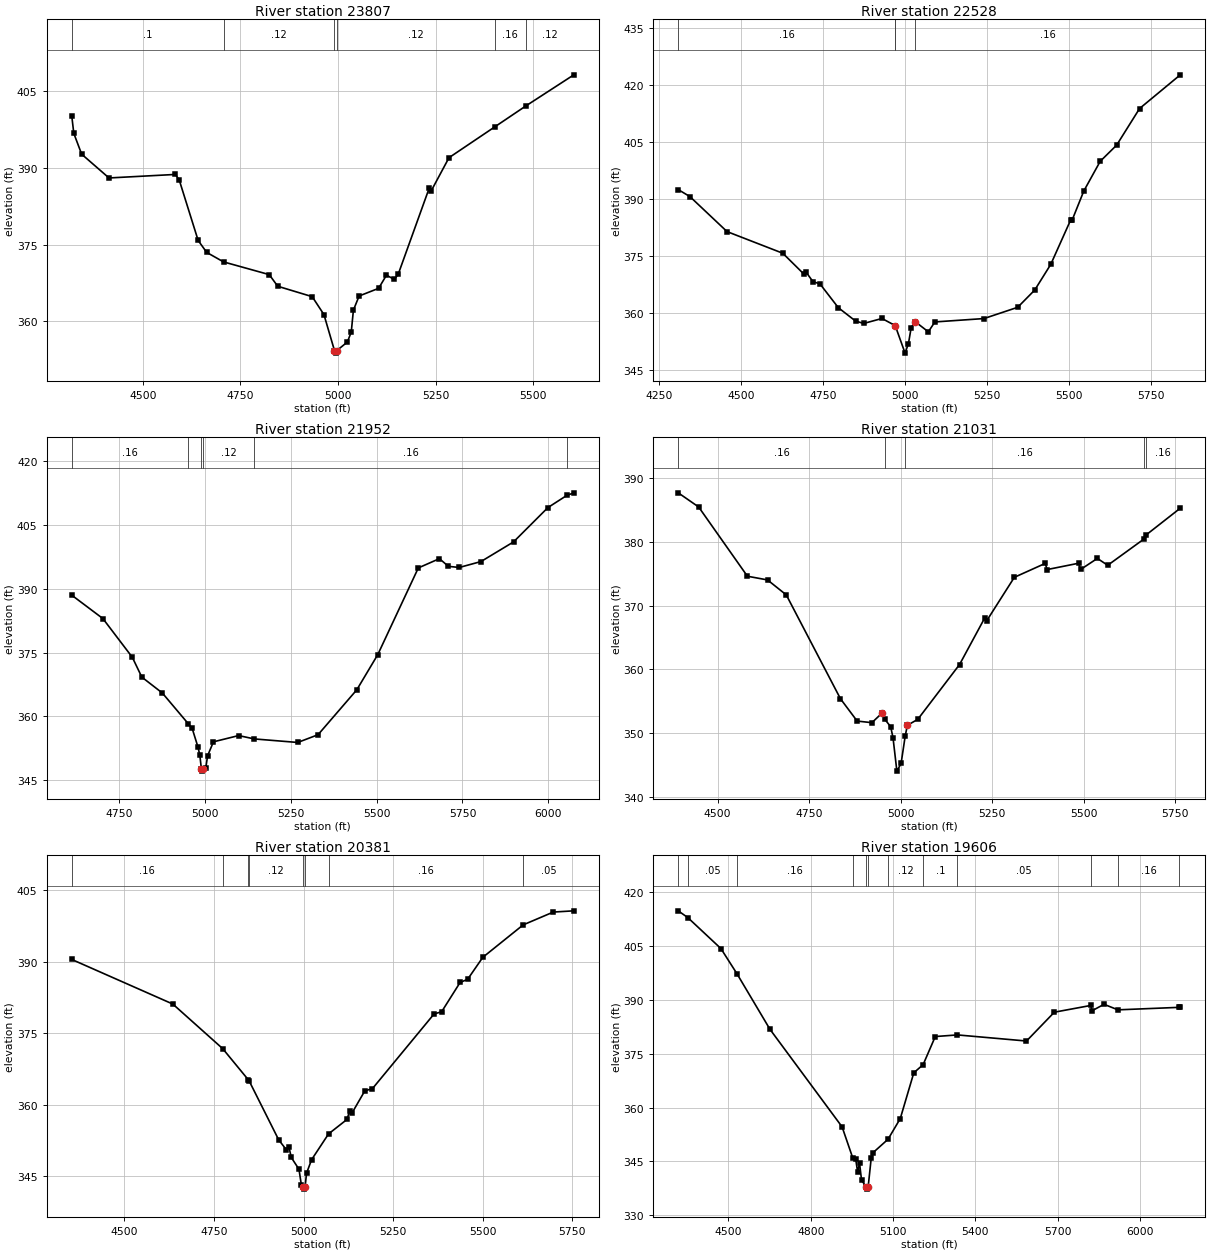
Type RM Length L Ch R = 1 ,23807   ,1279,1279,1279
BEGIN DESCRIPTION:
BEAR CREEK EAST 29.0
END DESCRIPTION:
XS GIS Cut Line= 2
      3536190.56     10425946.87      3536255.67     10424662.12
#Sta/Elev= 30
  4317.7  400.18  4322.9  396.79    4343  392.71  4413.1  388.05  4583.3  388.74
  4593.3  387.59  4641.5  375.81  4663.4  373.47  4706.5  371.61  4823.6  369.12
  4845.4  366.84  4933.7   364.8  4963.8  361.29  4990.8  354.24  4993.5  353.74
  4996.8  354.24  5023.8  355.91  5033.8  357.87  5039.3  362.16  5053.9  364.93
  5103.9  366.43    5124  369.01    5144  368.18    5154  369.17  5233.2  385.99
  5238.2  385.46  5284.2  392.02  5401.2  398.04  5481.4  402.17  5604.1  408.25
#Mann= 6 ,-1 , 0
  4317.7      .1       0  4706.5     .12       0  4990.8     .07       0
  4996.8     .12       0  5401.2     .16       0  5481.4     .12       0
Bank Sta=4990.8,4996.8
XS Rating Curve= 0 ,0
Exp/Cntr=0.3,0.1

Type RM Length L Ch R = 1 ,22528   ,576,576,576
BEGIN DESCRIPTION:
BEAR CREEK EAST 28.0
END DESCRIPTION:
XS GIS Cut Line= 4
       3536646.3      10425686.4      3536958.79     10425391.27
      3537062.96     10424627.38      3537071.64     10424297.48
#Sta/Elev= 30
  4308.7  392.48  4344.3  390.64  4457.5   381.4  4627.5  375.69    4691  370.26
  4698.3  370.73  4719.3  368.21  4740.9   367.6  4796.9  361.32  4849.2  357.81
  4874.2  357.17  4929.9  358.48  4970.3   356.6  5000.3  349.34  5010.6  351.87
  5018.9  356.05  5030.8  357.67  5071.2  354.96  5091.2  357.57  5240.9  358.46
  5343.7  361.43  5395.7  365.99  5444.6  372.77  5504.8   384.4  5509.5   384.4
  5545.2   392.1  5595.3  399.95  5645.3   404.2  5715.3  413.87  5839.5  422.76
#Mann= 4 ,-1 , 0
  4308.7     .16       0  4970.3     .12       0  4970.3     .12       0
  5030.8     .16       0
Bank Sta=4970.3,5030.8
XS Rating Curve= 0 ,0
Exp/Cntr=0.3,0.1

Type RM Length L Ch R = 1 ,21952   ,921,921,921
BEGIN DESCRIPTION:
BEAR CREEK EAST 26.0
END DESCRIPTION:
XS GIS Cut Line= 4
      3537097.64     10425643.03      3537310.35     10425486.76
      3537635.87     10424814.01      3537493.04      10424385.5
#Sta/Elev= 30
  4611.6  388.49  4702.3  382.99    4788  373.89  4815.7  369.23  4875.5  365.49
  4951.1  358.26  4962.2  357.23  4979.3  352.79  4984.8  350.85  4989.3  347.62
  4992.1  347.12  4995.3  347.62  5001.9  347.75  5007.4  350.73  5024.4  354.01
  5097.8  355.48  5143.6  354.69    5270  353.86  5329.2  355.68  5442.2  366.25
  5503.3  374.52  5621.4   394.9  5682.8  397.08  5709.2  395.27  5740.8  395.01
    5804   396.4  5898.9  401.02    5999  409.09  6053.9  411.94  6074.6  412.56
#Mann= 6 ,-1 , 0
  4611.6     .16       0  4951.1     .12       0  4989.3     .07       0
  4995.3     .12       0  5143.6     .16       0  6053.9      .1       0
Bank Sta=4989.3,4995.3
XS Rating Curve= 0 ,0
Exp/Cntr=0.3,0.1

Type RM Length L Ch R = 1 ,21031   ,650,650,650
BEGIN DESCRIPTION:
BEAR CREEK EAST 25.0
END DESCRIPTION:
XS GIS Cut Line= 2
      3537371.08      10425812.3      3538612.47     10425230.66
#Sta/Elev= 30
  4392.7  387.71  4448.4  385.49  4581.6  374.61  4636.5  374.03  4687.7  371.68
  4835.7  355.36  4881.3  351.86  4921.5  351.61  4949.8  353.15    4957  352.12
  4972.7  350.98  4979.1  349.27  4989.7     344  5001.2   345.2  5012.3  349.46
  5018.3   351.2  5046.7  352.13  5160.8  360.74  5229.3  368.03  5234.8   367.6
  5310.4  374.44  5394.6  376.62  5400.1  375.66  5485.9  376.65  5491.4  375.67
  5537.1  377.41  5565.4  376.33  5663.5  380.42  5670.1  381.09  5763.6   385.3
#Mann= 5 ,-1 , 0
  4392.7     .16       0    4957     .12       0  5012.3     .16       0
  5663.5     .05       0  5670.1     .16       0
Bank Sta=4949.8,5018.3
XS Rating Curve= 0 ,0
Exp/Cntr=0.3,0.1

Type RM Length L Ch R = 1 ,20381   ,775,775,775
BEGIN DESCRIPTION:
BEAR CREEK EAST 23.0
END DESCRIPTION:
XS GIS Cut Line= 4
      3537657.54     10426077.03      3538104.62      10426181.2
      3538438.83     10425860.02      3538698.08     10425458.17
#Sta/Elev= 30
  4353.3  390.48  4635.2  381.12  4774.4  371.76  4846.2  365.19  4848.1     365
  4930.6  352.62  4951.7  350.56  4958.9  351.19  4965.8  348.91  4987.2  346.44
  4994.1  343.04  4998.3  342.77  5001.1  342.27  5004.3  342.77  5008.3  345.59
  5022.4  348.45  5069.7  353.86  5121.5  356.92  5128.4  358.73  5135.6   358.3
  5170.9   362.9  5192.2  363.37  5364.1  379.04  5385.2   379.5  5436.7  385.65
  5457.8  386.32  5500.1  390.93  5612.7  397.74  5696.7  400.43  5754.1  400.69
#Mann= 8 ,-1 , 0
  4353.3     .16       0  4774.4     .12       0  4846.2     .16       0
  4848.1     .12       0  4998.3     .07       0  5004.3     .12       0
  5069.7     .16       0  5612.7     .05       0
Bank Sta=4998.3,5004.3
XS Rating Curve= 0 ,0
Exp/Cntr=0.3,0.1

Type RM Length L Ch R = 1 ,19606   ,754,754,754
BEGIN DESCRIPTION:
BEAR CREEK EAST 21.0
END DESCRIPTION:
XS GIS Cut Line= 4
      3538195.76     10427170.81      3538434.49      10426827.9
      3538790.39     10426437.28      3538989.69     10425575.08
#Sta/Elev= 30
  4316.7  414.85  4351.5  412.97  4472.3  404.34  4530.8  397.33  4651.2  381.84
  4914.3  354.65  4953.6   345.9  4963.7  345.78  4971.1  342.04  4977.9  344.56
  4985.3  339.81  5003.2   337.8    5006   337.3  5009.2   337.8  5020.4  345.85
  5027.2  347.46  5081.8  351.19  5126.5  356.96  5175.9  369.72  5209.9  371.99
  5254.2  379.82    5335  380.27  5586.9  378.57  5688.4   386.6  5820.6  388.47
  5826.9  387.04  5869.6   388.8  5920.5  387.26  6142.6  387.95  6147.9  387.97
#Mann= 12 ,-1 , 0
  4316.7      .1       0  4351.5     .05       0  4530.8     .16       0
  4953.6     .05       0  5003.2     .04       0  5009.2     .05       0
  5081.8     .12       0  5209.9      .1       0    5335     .05       0
  5820.6      .1       0  5920.5     .16       0  6142.6      .1       0
Bank Sta=5003.2,5009.2
XS Rating Curve= 0 ,0
Exp/Cntr=0.3,0.1

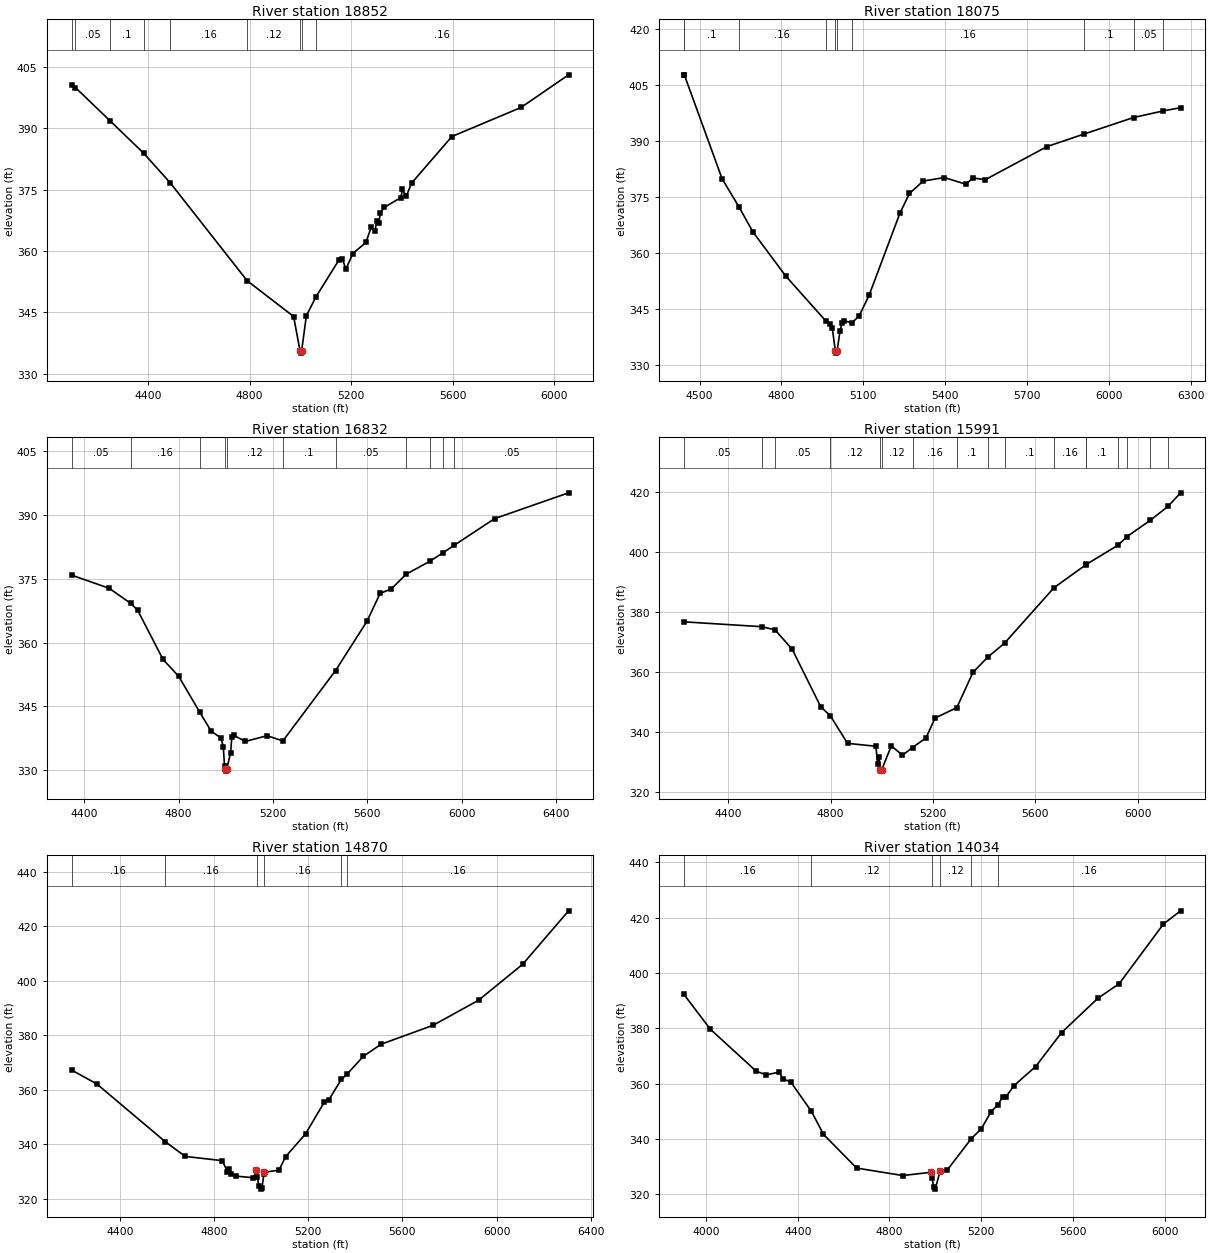
Type RM Length L Ch R = 1 ,18852   ,777,777,777
BEGIN DESCRIPTION:
BEAR CREEK EAST 19.0
END DESCRIPTION:
XS GIS Cut Line= 4
       3538651.5       10427722.      3538838.13     10427261.93
       3539298.2     10426858.28      3539775.11     10426155.92
#Sta/Elev= 30
  4098.8  400.43    4114   399.9  4249.5  391.85  4383.5  383.83  4487.8  376.62
  4790.3  352.75  4973.5     344  4998.9  335.56  5001.7  335.06  5004.9  335.56
  5023.7  344.21  5061.9  348.84  5150.9  357.71  5165.1  358.14  5179.4  355.55
  5206.6  359.38  5258.2  362.08  5279.2  365.82  5294.2  364.81  5300.2  367.36
  5309.1   366.8  5315.1  369.38  5330.1  370.64  5395.9  373.04    5402  375.02
  5416.9  373.32  5437.9  376.56  5596.6  387.94  5869.1  395.04  6056.3  403.01
#Mann= 9 ,-1 , 0
  4098.8      .1       0    4114     .05       0  4249.5      .1       0
  4383.5     .05       0  4487.8     .16       0  4790.3     .12       0
  4998.9     .07       0  5004.9     .12       0  5061.9     .16       0
Bank Sta=4998.9,5004.9
XS Rating Curve= 0 ,0
Exp/Cntr=0.3,0.1

Type RM Length L Ch R = 1 ,18075   ,1243,1243,1243
BEGIN DESCRIPTION:
BEAR CREEK EAST 17.0
END DESCRIPTION:
XS GIS Cut Line= 3
      3539241.79     10427991.08      3539962.26     10427179.47
      3540603.08     10426815.76
#Sta/Elev= 30
    4441  407.74  4444.5  407.64  4582.6  379.89  4643.6  372.47  4695.5  365.68
  4815.9  353.86  4962.4  341.86    4979  341.16  4986.5  339.86  4997.8  333.73
  5000.5  333.23  5003.8  333.73    5015  339.25  5021.7  341.23  5028.6  341.95
  5058.2   341.3  5085.2  343.25  5121.2  348.69  5234.1  370.65  5269.3  375.98
  5319.4  379.29  5397.2  380.24  5474.9  378.48  5503.4  380.09  5547.8  379.69
  5774.2  388.55  5909.4  391.89  6090.8  396.31  6199.6  398.08  6263.1  398.94
#Mann= 10 ,-1 , 0
    4441     .05       0  4444.5      .1       0  4643.6     .16       0
  4962.4     .12       0  4997.8     .07       0  5003.8     .12       0
  5058.2     .16       0  5909.4      .1       0  6090.8     .05       0
  6199.6      .1       0
Bank Sta=4997.8,5003.8
XS Rating Curve= 0 ,0
Exp/Cntr=0.3,0.1

Type RM Length L Ch R = 1 ,16832   ,841,841,841
BEGIN DESCRIPTION:
BEAR CREEK EAST 15.0
END DESCRIPTION:
XS GIS Cut Line= 4
      3539884.17     10428199.43      3540296.46     10428143.01
      3541138.48     10427847.87      3541433.43     10427106.14
#Sta/Elev= 30
  4346.2  375.87  4505.6  372.77  4597.4  369.21  4626.7  367.58  4734.1  356.03
  4800.1   352.1  4888.9   343.7  4937.9  339.19  4980.2  337.53  4989.4  335.48
  4994.7  330.96  4998.4  330.28  5001.2  329.78  5004.4  330.28  5020.4  334.12
  5025.7  337.81  5033.2  338.22  5082.4  336.76  5175.4  338.11  5241.8  336.87
  5465.2  353.42    5599  365.07  5653.9  371.56    5702  372.64  5763.7  376.05
  5863.9  379.09  5918.5  381.04  5967.9  382.87  6139.1  389.14  6452.8  395.21
#Mann= 11 ,-1 , 0
  4346.2     .05       0  4597.4     .16       0  4888.9     .12       0
  4998.4     .07       0  5004.4     .12       0  5241.8      .1       0
  5465.2     .05       0  5763.7     .16       0  5863.9     .05       0
  5918.5     .16       0  5967.9     .05       0
Bank Sta=4998.4,5004.4
XS Rating Curve= 0 ,0
Exp/Cntr=0.3,0.1

Type RM Length L Ch R = 1 ,15991   ,1121,1121,1121
BEGIN DESCRIPTION:
BEAR CREEK EAST 13.0
END DESCRIPTION:
XS GIS Cut Line= 4
       3540194.5     10428449.02      3540639.35     10428750.65
      3541281.71      10428681.2      3541897.54     10428238.85
#Sta/Elev= 30
  4225.6  376.77  4530.9  375.14  4583.2  374.07  4650.3  367.58  4761.7  348.38
  4799.2  345.36  4866.4  336.15  4977.1  335.18  4984.2  329.18  4989.3  331.62
  4994.2  327.37  4996.9  326.87  5000.2  327.37  5037.4   335.3    5081   332.2
  5120.3  334.76  5172.8  337.97  5208.4  344.61  5293.3  348.09  5356.4  359.86
  5413.2  364.89  5480.2  369.67  5672.9  388.16  5798.2  395.86  5799.2  395.94
  5923.4  402.39  5958.6  405.27  6048.7  410.66  6118.1  415.32  6167.4  419.87
#Mann= 17 ,-1 , 0
  4225.6     .05       0  4530.9     .16       0  4583.2     .05       0
  4799.2     .12       0  4994.2     .07       0  5000.2     .12       0
  5120.3     .16       0  5293.3      .1       0  5413.2     .16       0
  5480.2      .1       0  5672.9     .16       0  5798.2     .05       0
  5799.2      .1       0  5923.4     .05       0  5958.6      .1       0
  6048.7     .05       0  6118.1     .16       0
Bank Sta=4994.2,5000.2
XS Rating Curve= 0 ,0
Exp/Cntr=0.3,0.1

Type RM Length L Ch R = 1 ,14870   ,836,836,836
BEGIN DESCRIPTION:
BEAR CREEK EAST 10.0
END DESCRIPTION:
XS GIS Cut Line= 2
      3540303.02     10429913.82      3542212.71     10429013.23
#Sta/Elev= 30
  4194.6   367.2  4301.9  362.08  4591.8  340.94  4677.4  335.46  4834.9  333.91
    4857  329.91  4865.2  330.84  4870.7  329.07  4893.5  328.23  4967.5  327.63
  4978.6   330.4  4984.6  327.99  4990.1   324.6  5000.4  323.45  5003.7  323.95
  5012.2  329.17  5012.9  329.65  5075.7   330.4    5104  335.36  5188.7  343.74
    5269  355.49  5286.3  356.06  5340.7  363.74  5365.5  365.72    5434   372.2
  5509.3  376.65  5730.1   383.6  5923.4  392.81  6111.1  406.03    6306  425.65
#Mann= 6 ,-1 , 0
  4194.6     .16       0  4591.8     .16       0  4984.6     .12       0
  5012.2     .16       0  5340.7     .05       0  5365.5     .16       0
Bank Sta=4978.6,5012.9
XS Rating Curve= 0 ,0
Exp/Cntr=0.3,0.1

Type RM Length L Ch R = 1 ,14034   ,1613,1613,1613
BEGIN DESCRIPTION:
BEAR CREEK EAST 8.0
END DESCRIPTION:
XS GIS Cut Line= 2
        3540737.      10430760.2      3542494.79     10429490.68
#Sta/Elev= 30
  3901.6  392.46  4018.9  379.66  4218.8  364.53  4262.9  363.19  4319.4  364.21
  4334.1  361.84  4369.7   360.6  4459.9  349.98  4512.3  341.71  4656.7  329.54
  4857.7  326.84  4979.3  327.99  4985.5  326.05  4993.4   322.7  4999.9  321.93
  5021.1  328.57  5050.5  328.66  5157.2  340.18  5201.3  343.78  5243.1  349.89
  5274.2  352.49  5293.4  355.14  5308.1  355.27  5343.7  359.35  5437.5  366.19
    5551  378.48  5708.9  390.84  5802.4  396.15  5995.1  417.66  6069.9  422.45
#Mann= 6 ,-1 , 0
  3901.6     .16       0  4459.9     .12       0  4985.5     .08       0
  5021.1     .12       0  5157.2      .1       0  5274.2     .16       0
Bank Sta=4979.3,5021.1
XS Rating Curve= 0 ,0
Exp/Cntr=0.3,0.1

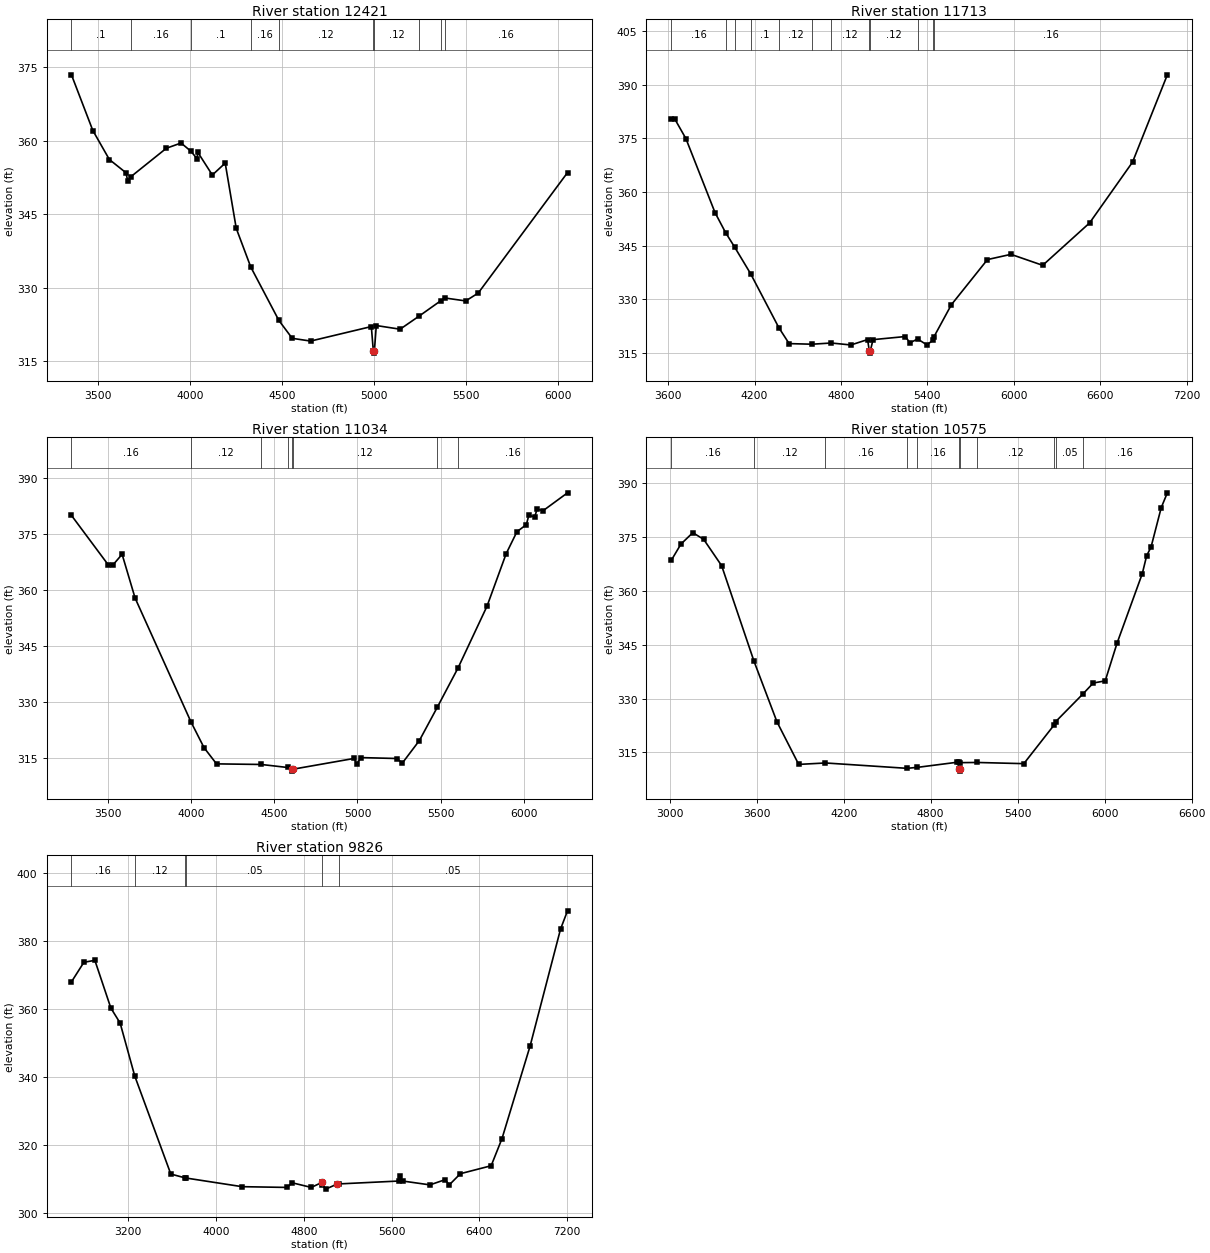
Type RM Length L Ch R = 1 ,12421   ,1387,1387,1387
BEGIN DESCRIPTION:
BEAR CREEK EAST 4.0
END DESCRIPTION:
XS GIS Cut Line= 4
      3541105.95     10431910.37      3542017.39     10431932.07
      3542776.93     10430901.25      3542603.85     10430425.27
#Sta/Elev= 30
    3355  373.46  3471.2   362.1  3561.2  356.18  3651.2  353.49  3661.2  351.81
  3678.1  352.67  3871.3  358.48  3951.3  359.55  4006.1  357.83  4037.5  356.36
  4042.5  357.64  4121.4  353.02  4191.4  355.45  4251.4  342.14  4330.4  334.25
  4483.5  323.34    4556   319.7  4656.2  319.14  4986.3   322.1  4997.1  317.18
  4999.8  316.68  5003.1  317.18  5013.3  322.31  5142.9  321.56  5246.5  324.24
    5365  327.39  5386.7  327.93    5500  327.33    5568  328.94  6053.6  353.51
#Mann= 10 ,-1 , 0
    3355      .1       0  3678.1     .16       0  4006.1      .1       0
  4330.4     .16       0  4483.5     .12       0  4997.1     .07       0
  5003.1     .12       0  5246.5     .16       0    5365     .05       0
  5386.7     .16       0
Bank Sta=4997.1,5003.1
XS Rating Curve= 0 ,0
Exp/Cntr=0.3,0.1

Type RM Length L Ch R = 1 ,11713   ,679,679,679
BEGIN DESCRIPTION:
Mapping XS 779e
END DESCRIPTION:
XS GIS Cut Line= 3
       3541649.2     10432200.95       3543631.8     10431464.85
       3544631.8     10430589.85
#Sta/Elev= 30
  3622.1  380.26  3646.5  380.36  3723.6  374.89  3925.5  354.23    3999  348.62
  4061.3  344.61  4172.1  337.18  4368.9  322.04  4440.1   317.6  4599.2  317.43
  4732.5  317.77  4868.9  317.22    4985  318.73    4997  315.44  4999.8  314.94
    5003  315.44  5022.6  318.71  5247.6  319.58  5278.6   317.8  5331.8   318.9
  5395.9  317.26  5438.8  318.53  5446.6  319.58  5566.6  328.48  5817.1  341.09
  5980.2  342.55  6200.4  339.48  6525.9  351.32  6823.9  368.31  7065.7  392.72
#Mann= 12 ,-1 , 0
  3622.1     .16       0    3999      .1       0  4061.3     .16       0
  4172.1      .1       0  4368.9     .12       0  4599.2     .16       0
  4732.5     .12       0    4997     .07       0    5003     .12       0
  5331.8     .16       0  5438.8     .05       0  5446.6     .16       0
Bank Sta=4997,5003
XS Rating Curve= 0 ,0
Exp/Cntr=0.3,0.1

Type RM Length L Ch R = 1 ,11034   ,459,459,459
BEGIN DESCRIPTION:
Mapping XS 779edec2
END DESCRIPTION:
XS GIS Cut Line= 4
      3541666.17     10432280.79      3542451.76     10432428.36
      3543967.39     10432032.52      3544465.75     10431669.94
#Sta/Elev= 30
  3280.8  379.97  3500.5  366.84  3527.6   366.6  3585.2  369.58  3663.3  357.88
  3998.8  324.81  4077.8  317.88  4152.8  313.55  4421.9  313.39  4580.6  312.58
  4604.6  312.11  4607.3  311.61  4610.6  312.11  4979.7     315  4996.1  313.46
    5021  315.23  5238.9  314.98    5269  313.71  5372.4  319.79  5481.1  328.77
  5604.4  339.16  5778.9  355.69  5894.1  369.74    5959  375.62  6015.4   377.5
  6030.1  379.95  6065.6  379.61  6080.3  381.67  6115.8  381.22  6262.9  386.01
#Mann= 8 ,-1 , 0
  3280.8     .16       0  3998.8     .12       0  4421.9     .16       0
  4580.6     .12       0  4604.6     .07       0  4610.6     .12       0
  5481.1     .05       0  5604.4     .16       0
Bank Sta=4604.6,4610.6
XS Rating Curve= 0 ,0
Exp/Cntr=0.3,0.1

Type RM Length L Ch R = 1 ,10575   ,749,749,749
BEGIN DESCRIPTION:
BEAR CREEK EAST 1.1
END DESCRIPTION:
XS GIS Cut Line= 4
       3541535.6     10432589.62      3542349.42     10432795.78
       3544443.6     10432296.65      3544409.77     10431869.56
#Sta/Elev= 30
  3011.4  368.48  3077.8  372.99  3159.8  376.17  3234.7  374.31  3358.5  366.99
  3581.6  340.41  3740.2  323.52    3890  311.68  4074.8  312.08  4636.3  310.59
  4709.1  310.86  4984.5  312.29  4994.8  312.25    4997  310.31  4999.8  309.81
    5003  310.31  5005.1  312.17  5120.4  312.22  5442.5  311.89  5652.5  322.71
  5661.9  323.57  5851.6  331.35  5921.3  334.33  6003.8  334.93    6085  345.37
  6259.6  364.79  6289.7  369.77  6319.8  372.16    6390  383.13  6432.2  387.26
#Mann= 11 ,-1 , 0
  3011.4     .16       0  3581.6     .12       0  4074.8     .16       0
  4636.3     .12       0  4709.1     .16       0    4997     .07       0
    5003     .16       0  5120.4     .12       0  5652.5     .16       0
  5661.9     .05       0  5851.6     .16       0
Bank Sta=4997,5003
XS Rating Curve= 0 ,0
Exp/Cntr=0.3,0.1

Type RM Length L Ch R = 1 ,9826    ,0,0,0
BEGIN DESCRIPTION:
BEAR CREEK EAST 1.0
END DESCRIPTION:
XS GIS Cut Line= 4
       3541530.7     10432610.08       3543149.6     10433408.68
      3544888.24     10432383.29      3544454.23     10431840.78
#Sta/Elev= 30
  2684.2  367.91  2797.3  373.66  2897.3  374.24  3043.1  360.19  3127.4  355.79
  3260.6  340.21    3589  311.37    3717  310.26  3730.4  310.18  4238.7  307.65
  4649.9  307.43  4692.8  308.81  4868.5  307.43  4964.1  308.88  4969.9  308.22
  4999.8  306.93  5102.7   308.4  5118.3  308.46  5664.8  309.31  5672.6  310.87
  5699.8  309.32  5949.7  308.18  6088.2  309.72  6125.3  308.17  6226.8  311.47
  6507.2  313.81  6605.9   321.8    6862  349.05  7138.9   383.4  7202.6   388.8
#Mann= 6 ,-1 , 0
  2684.2     .16       0  3260.6     .12       0    3717     .16       0
  3730.4     .05       0  4969.9     .03       0  5118.3     .05       0
Bank Sta=4964.1,5102.7
XS Rating Curve= 0 ,0
Exp/Cntr=0.3,0.1

Chan Stop Cuts=-1
Use User Specified Reach Order=0
Composite Channel Slope=5