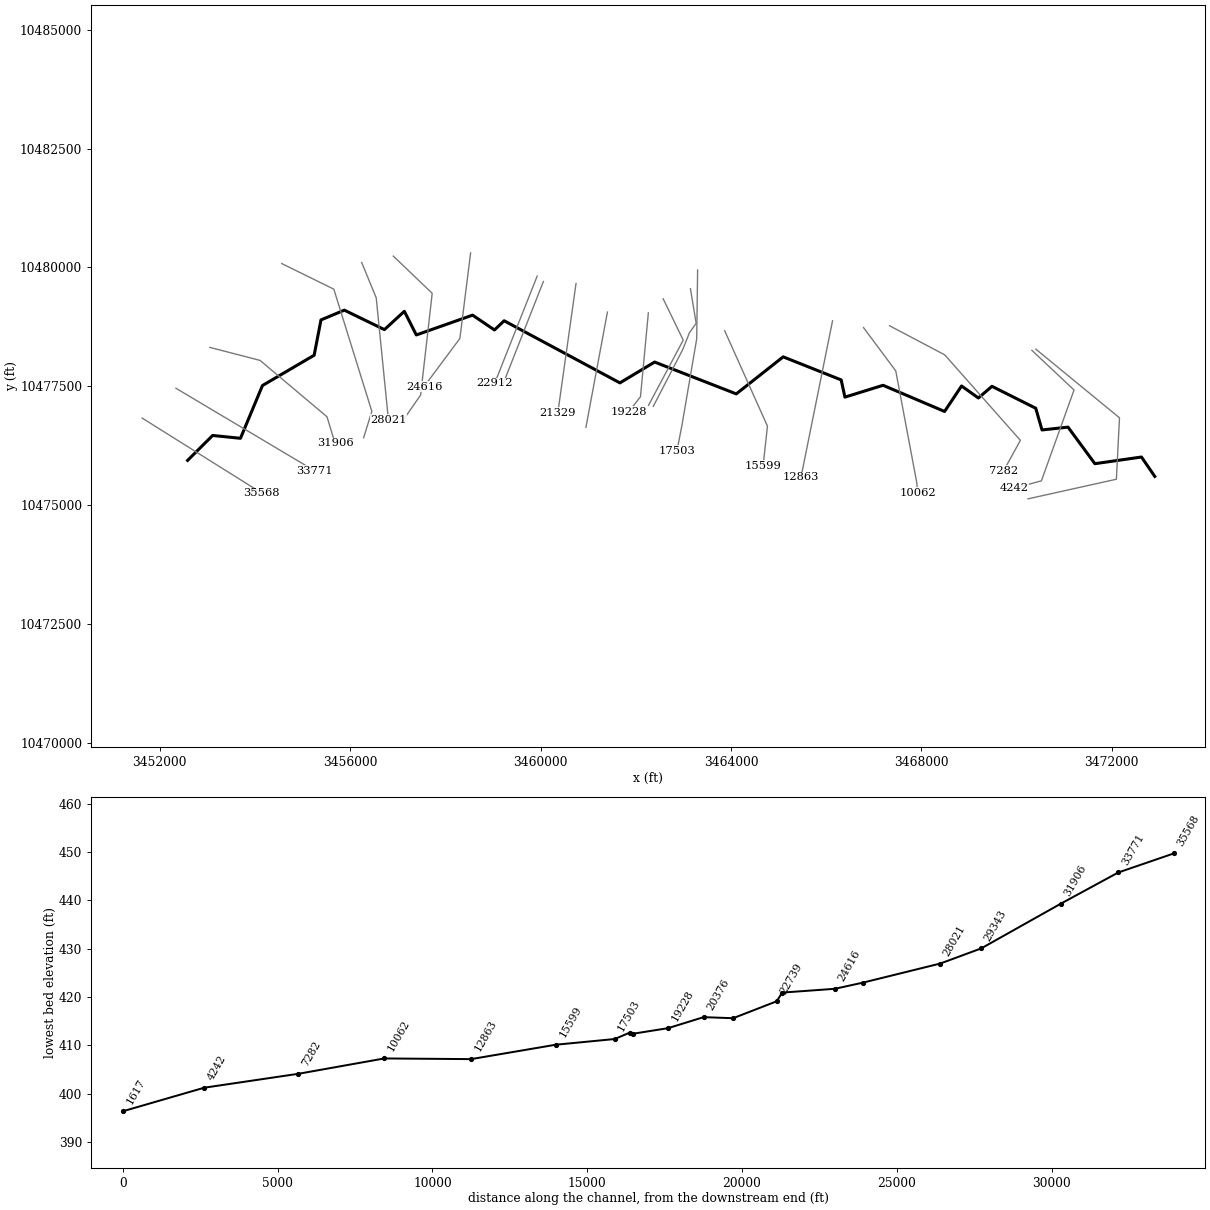
--- BIG ELM CREEK.prj (project) ---

Proj Title=BIG ELM CREEK Base Level Engineering
Current Plan=p01
Default Exp/Contr=0.3,0.1
English Units
Geom File=g01
Flow File=f01
Plan File=p01
Y Axis Title=Elevation
X Axis Title(PF)=Main Channel Distance
X Axis Title(XS)=Station
BEGIN DESCRIPTION:
BIG ELM CREEK
END DESCRIPTION:
DSS Export Rating Curves= 0
DSS Export Rating Curve Sorted= 0
DSS Export Volume Flow Curves= 0
DXF OffsetX= 0
DXF OffsetY= 0
DXF ScaleX= 1
DXF ScaleY= 10

--- BIG ELM CREEK.p01 (plan) ---

Plan Title=Multiple Run
Short Identifier=Multiple
Geom File=g01
Flow File=f01
Subcritical Flow
K Sum by GR= 0
Std Step Tol= 0.01
Critical Tol= 0.01
Num of Std Step Trials= 20
Max Error Tol= 0.3
Flow Tol Ratio= 0.001
Split Flow NTrial= 30
Split Flow Tol= 0.02
Split Flow Ratio= 0.02
Log Output Level= 0
Friction Slope Method= 1
Unsteady Friction Slope Method= 2
Unsteady Bridges Friction Slope Method= 1
Parabolic Critical Depth
Global Vel Dist=  1 , 1 , 1
Global Log Level= 0
CheckData=True
Encroach Param= -1, 0, 0, 0
BEGIN DESCRIPTION:
Multiple Run
END DESCRIPTION:

--- BIG ELM CREEK.f01 (steady flow) ---

Flow Title=Multiple
Program Version=4.10
Number of Profiles= 7
Profile Names=10-year,25-year,50-year,1pct_min,100-year,1pct_plu,500-year
River Rch & RM=BIG ELM CREEK,Reach-1         ,35568
    1176    1621    1987    1775    2400    3246    3494
River Rch & RM=BIG ELM CREEK,Reach-1         ,29343
    2725    3923    4951    4540    6140    8303    9432
River Rch & RM=BIG ELM CREEK,Reach-1         ,22912
    3077    4433    5599    5134    6943    9389   10665
River Rch & RM=BIG ELM CREEK,Reach-1         ,12863
    3352    4819    6075    5557    7515   10163   11488
Boundary for River Rch & Prof#=BIG ELM CREEK,Reach-1         , 1
Up Type= 0
Dn Type= 3
Dn Slope=0.001
Boundary for River Rch & Prof#=BIG ELM CREEK,Reach-1         , 2
Up Type= 0
Dn Type= 3
Dn Slope=0.001
Boundary for River Rch & Prof#=BIG ELM CREEK,Reach-1         , 3
Up Type= 0
Dn Type= 3
Dn Slope=0.001
Boundary for River Rch & Prof#=BIG ELM CREEK,Reach-1         , 4
Up Type= 0
Dn Type= 3
Dn Slope=0.001
Boundary for River Rch & Prof#=BIG ELM CREEK,Reach-1         , 5
Up Type= 0
Dn Type= 3
Dn Slope=0.001
Boundary for River Rch & Prof#=BIG ELM CREEK,Reach-1         , 6
Up Type= 0
Dn Type= 3
Dn Slope=0.001
Boundary for River Rch & Prof#=BIG ELM CREEK,Reach-1         , 7
Up Type= 0
Dn Type= 3
Dn Slope=0.001
DSS Import GetInterval= 0
DSS Import GetPeak= 0
DSS Import FillOption= 0

--- BIG ELM CREEK.g01 (geometry) ---

Geom Title=Existing Conditions
Program Version=4.10

River Reach=BIG ELM CREEK   ,Reach-1
Reach XY= 30
      3452588.04     10475944.53      3453113.73     10476468.44
      3453698.41      10476409.1      3454159.92     10477517.93
      3455245.52     10478154.88      3455389.51     10478897.53
      3455879.67     10479102.55      3456722.14     10478693.52
      3457140.42     10479078.38      3457391.45      10478581.3
      3458573.16     10478997.98      3459033.02     10478686.06
      3459236.17     10478879.64       3461667.6     10477573.83
      3462397.09     10478011.74      3464111.42     10477342.33
      3465096.78     10478121.05      3466314.96     10477636.08
      3466393.63     10477274.27      3467195.08     10477523.35
      3468486.67     10476973.06      3468843.27     10477508.77
      3469197.12     10477256.29      3469482.11     10477501.64
      3470401.52     10477040.75      3470532.68      10476584.6
      3471078.96     10476643.86      3471643.84      10475875.3
      3472622.24     10476015.53      3472901.59     10475607.73

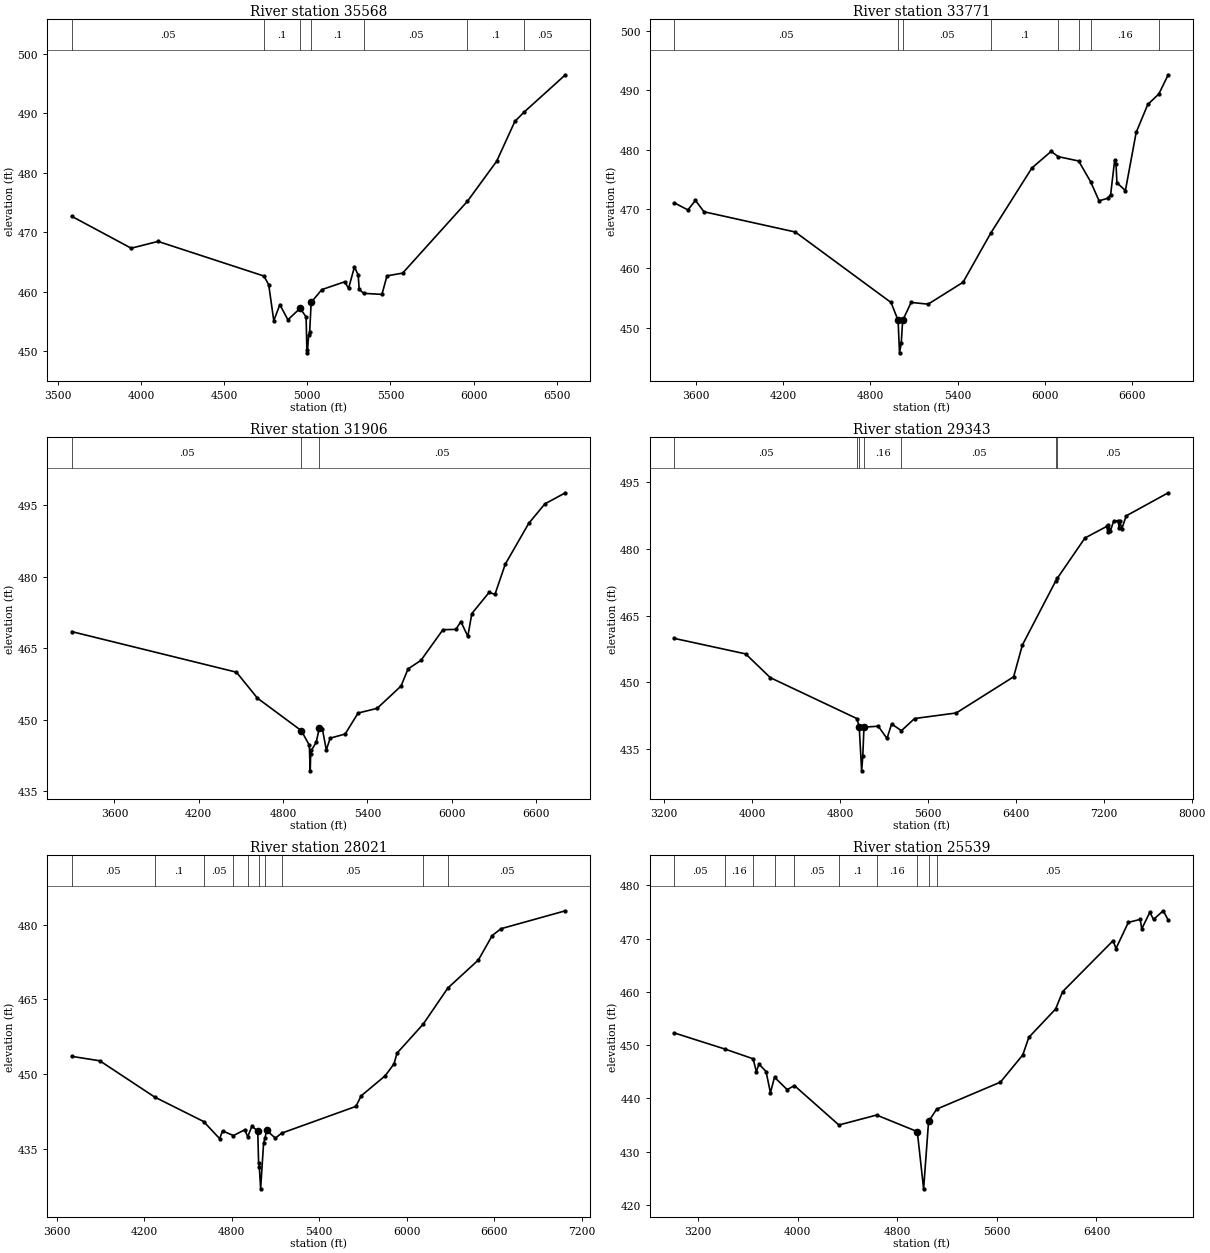
Type RM Length L Ch R = 1 ,35568   ,1797,1797,1797
BEGIN DESCRIPTION:
BIG ELM CREEK 32.0
END DESCRIPTION:
XS GIS Cut Line= 2
      3451631.22     10476835.47      3454147.02     10475256.59
#Sta/Elev= 30
  3582.1   472.7  3940.3  467.33  4101.7  468.47  4738.4  462.65  4767.4  461.19
    4798  455.13  4834.5  457.84  4882.8  455.29  4955.9  457.21  4992.4  455.79
  4996.9  450.23  4999.6  449.73  5007.7  452.74  5013.6  453.17    5023  458.22
  5086.7  460.36  5224.2  461.68  5247.8  460.58  5283.2  464.17  5305.8  462.82
  5311.7   460.4  5338.8  459.74  5448.5  459.56    5479  462.68  5573.2  463.14
  5962.7  475.22  6138.8  481.96  6248.3  488.66  6301.8  490.17  6552.3   496.5
#Mann= 7 ,-1 , 0
  3582.1     .05       0  4738.4      .1       0  4955.9     .07       0
    5023      .1       0  5338.8     .05       0  5962.7      .1       0
  6301.8     .05       0
#XS Ineff= 2 , 0
       0                  5283.2       0  461.75
Permanent Ineff=
       F       F
Bank Sta=4955.9,5023
XS Rating Curve= 0 ,0
Exp/Cntr=0.3,0.1

Type RM Length L Ch R = 1 ,33771   ,1865,1865,1865
BEGIN DESCRIPTION:
BIG ELM CREEK 28.0
END DESCRIPTION:
XS GIS Cut Line= 2
      3452343.07     10477460.45      3455258.39     10475725.13
#Sta/Elev= 30
  3453.6  471.03  3545.6  469.85  3597.9  471.45  3656.3  469.54  4283.4  466.13
  4941.6  454.26  4990.2  451.24  4999.8  445.78  5011.9  447.43  5021.4  451.23
  5079.8  454.27  5196.7  453.98  5436.2  457.66  5627.3  465.96  5909.4  476.91
  6041.8  479.71  6090.6  478.82  6230.8  478.09  6313.2  474.59  6370.9  471.39
  6429.3   471.8  6450.7  472.44  6478.2  478.22  6487.7  477.56  6493.6  474.43
    6552  473.11    6626   482.9  6705.8  487.61  6781.5  489.37  6846.3  492.61
#Mann= 8 ,-1 , 0
  3453.6     .05       0  4990.2    .035       0  5021.4     .05       0
  5627.3      .1       0  6090.6     .16       0  6230.8     .05       0
  6313.2     .16       0  6781.5     .05       0
Bank Sta=4990.2,5021.4
XS Rating Curve= 0 ,0
Exp/Cntr=0.3,0.1

Type RM Length L Ch R = 1 ,31906   ,2563,2563,2563
BEGIN DESCRIPTION:
Mapping XS a841b724
END DESCRIPTION:
XS GIS Cut Line= 4
      3453054.89     10478319.82      3454109.55     10478046.39
       3455515.8     10476861.49      3455685.06     10476301.64
#Sta/Elev= 30
  3295.7  468.48    4468  459.97  4617.5  454.53  4929.6  447.72  4986.8  444.67
  4993.1  439.29  4996.4  442.74  5001.1  443.56  5036.3   445.3  5057.1  448.21
  5079.1  448.15  5107.7  443.67  5135.1  446.14  5241.7  447.01  5334.1  451.41
  5469.3  452.39  5639.6  457.07  5689.1  460.65  5781.4  462.46  5937.5  468.88
  6029.8  468.94  6064.9  470.59  6114.7  467.48  6142.9  472.25  6267.1  476.73
  6307.5  476.26  6380.7  482.59  6547.8  491.16  6662.7  495.25    6809  497.58
#Mann= 3 , 0 , 0
  3295.7     .05       0  4929.6    .035       0  5057.1     .05       0
#XS Ineff= 2 , 0
       0                  5064.8       0  447.76
Permanent Ineff=
       F       F
Bank Sta=4929.6,5057.1
XS Rating Curve= 0 ,0
Exp/Cntr=0.3,0.1

Type RM Length L Ch R = 1 ,29343   ,1322,1322,1322
BEGIN DESCRIPTION:
Mapping XS 016b55db
END DESCRIPTION:
XS GIS Cut Line= 4
      3454565.32     10480081.96      3455659.03     10479543.78
      3456457.64     10476974.34      3456284.03     10476418.78
#Sta/Elev= 30
  3295.1  459.85  3942.4  456.37  4167.1  451.02  4953.4  441.83  4975.5     440
  4997.8  430.06  5008.1  433.34  5018.9  439.89  5148.8   440.1  5228.4  437.34
  5270.3  440.61  5359.4  439.09  5479.6  441.83  5858.6  443.08  6380.3  451.22
  6460.3  458.38  6761.4  472.68  6777.6  473.37  7029.4  482.45  7228.5  485.07
  7236.9  483.74  7242.2  485.45    7260  484.03  7291.4  486.28  7333.3  486.27
  7339.6  484.67  7344.8  486.37  7364.7  484.51  7404.6  487.43  7786.8  492.62
#Mann= 7 ,-1 , 0
  3295.1     .05       0  4953.4     .16       0  4975.5     .07       0
  5018.9     .16       0  5359.4     .05       0  6761.4      .1       0
  6777.6     .05       0
Bank Sta=4975.5,5018.9
XS Rating Curve= 0 ,0
Exp/Cntr=0.3,0.1

Type RM Length L Ch R = 1 ,28021   ,2482,2482,2482
BEGIN DESCRIPTION:
Mapping XS d6174aaa
END DESCRIPTION:
XS GIS Cut Line= 3
      3456243.87     10480104.87      3456549.42     10479361.82
      3456806.37     10476792.35
#Sta/Elev= 30
  3703.3  453.54  3895.9  452.65  4272.8  445.36  4608.2  440.45  4717.9  437.01
    4738  438.56  4812.4  437.63  4889.6  438.78  4910.7   437.4    4939  439.47
  4979.2  438.59  4985.1  432.22  4990.1  431.37  4999.1  426.93  5019.4  436.13
  5029.5  437.14  5039.5  438.69  5099.8  437.12  5143.7  438.12  5652.6  443.49
  5688.6  445.61  5853.6  449.65  5913.9  452.04    5934  454.17  6115.2  460.06
  6282.7  467.26  6492.6  472.91  6587.2  477.81  6647.5  479.18    7089  482.78
#Mann= 10 ,-1 , 0
  3703.3     .05       0  4272.8      .1       0  4608.2     .05       0
  4812.4      .1       0  4910.7     .16       0  4985.1     .07       0
  5029.5     .16       0  5143.7     .05       0  6115.2      .1       0
  6282.7     .05       0
Bank Sta=4979.2,5039.5
XS Rating Curve= 0 ,0
Exp/Cntr=0.3,0.1

Type RM Length L Ch R = 1 ,25539   ,923,923,923
BEGIN DESCRIPTION:
BIG ELM CREEK 31.0
END DESCRIPTION:
XS GIS Cut Line= 4
        3456909.     10480238.26      3457725.01     10479456.98
      3457481.95     10477317.22      3457091.34     10476757.35
#Sta/Elev= 30
  3010.7  452.27  3412.8  449.28  3642.2  447.43  3668.2  445.02  3689.5  446.43
  3746.2  445.03  3781.4  441.06  3814.1  443.96  3915.7  441.64  3974.1  442.39
  4331.5  434.99  4634.1  436.86    4961  433.75  5011.8     423  5051.6  435.66
  5116.7  437.97  5629.2  443.05  5808.3  448.15  5856.7  451.45  6072.1  456.78
  6128.5  460.04  6534.1  469.62  6556.8  468.13  6656.2  473.05  6751.3  473.61
  6764.1  471.84  6828.9  474.94  6858.6  473.61  6936.2  475.23  6976.6   473.5
#Mann= 10 ,-1 , 0
  3010.7     .05       0  3412.8     .16       0  3642.2     .05       0
  3814.1      .1       0  3974.1     .05       0  4331.5      .1       0
  4634.1     .16       0    4961     .07       0  5051.6     .16       0
  5116.7     .05       0
Bank Sta=4961,5051.6
XS Rating Curve= 0 ,0
Exp/Cntr=0.3,0.1

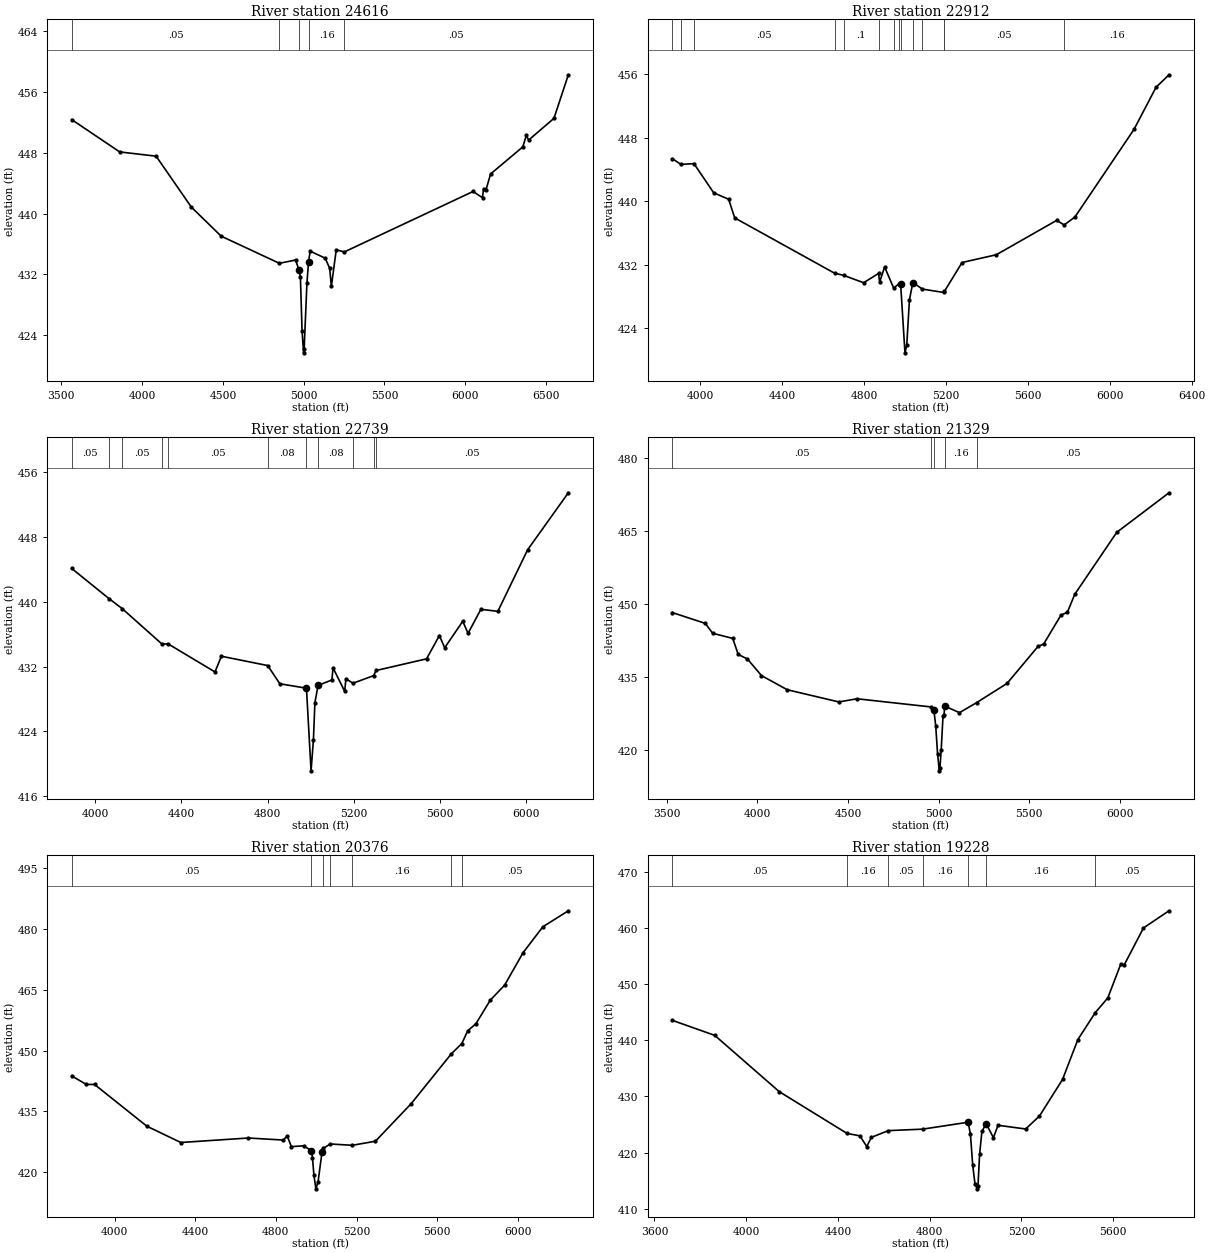
Type RM Length L Ch R = 1 ,24616   ,1704,1704,1704
BEGIN DESCRIPTION:
BIG ELM CREEK 31.1
END DESCRIPTION:
XS GIS Cut Line= 4
        3458532.     10480306.53       3458306.4     10478507.51
      3457731.85     10477734.81       3457553.8     10477495.36
#Sta/Elev= 30
  3563.9  452.36  3861.1  448.11  4086.6  447.55  4304.5  440.86  4489.1  437.04
  4849.5  433.47  4949.6   433.9  4972.1  432.54  4979.8  431.62  4989.9   424.6
  4999.7   421.7  5002.9   422.2  5020.1  430.85  5030.2  433.69  5040.3  435.07
  5133.1  434.14  5161.2  432.81  5171.3  430.43  5201.5  435.23  5252.1  434.97
  6048.6  442.91    6107  442.09  6113.3  443.28  6127.9  443.07  6156.9  445.21
  6356.3  448.77  6378.2  450.27  6392.8  449.67  6549.2  452.52  6638.3  458.25
#Mann= 5 ,-1 , 0
  3563.9     .05       0  4849.5     .16       0  4972.1     .07       0
  5030.2     .16       0  5252.1     .05       0
Bank Sta=4972.1,5030.2
XS Rating Curve= 0 ,0
Exp/Cntr=0.3,0.1

Type RM Length L Ch R = 1 ,22912   ,173,173,173
BEGIN DESCRIPTION:
BIG ELM CREEK 30.0
END DESCRIPTION:
XS GIS Cut Line= 2
      3459929.88     10479818.11      3459036.44     10477562.84
#Sta/Elev= 30
  3863.3  445.37    3905  444.65  3968.7  444.75  4065.1  441.07  4138.1  440.26
  4167.8  437.91  4655.7  430.94  4700.2  430.67  4797.3  429.74  4870.2  430.91
  4875.7  429.84    4900  431.73    4944  429.08  4972.5  429.64  4978.1  429.62
  4999.4  420.91  5008.1  421.87  5021.2  427.58  5037.8  429.77  5084.7  428.94
  5187.9  428.52  5191.9  428.65  5278.3  432.29  5445.8  433.27  5740.4   437.6
  5776.8  437.02  5829.5  438.02  6118.3  449.07  6225.8  454.37  6289.1  455.94
#Mann= 14 ,-1 , 0
  3863.3     .05       0    3905     .08       0  3968.7     .05       0
  4655.7     .08       0  4700.2      .1       0  4870.2     .08       0
    4944      .1       0  4972.5     .16       0  4978.1     .07       0
  5037.8     .16       0  5084.7     .05       0  5187.9     .16       0
  5191.9     .05       0  5776.8     .16       0
Bank Sta=4978.1,5037.8
XS Rating Curve= 0 ,0
Exp/Cntr=0.3,0.1

Type RM Length L Ch R = 1 ,22739   ,1410,1410,1410
BEGIN DESCRIPTION:
BIG ELM CREEK 29.0
END DESCRIPTION:
XS GIS Cut Line= 2
      3460060.07     10479705.22      3459218.06     10477561.13
#Sta/Elev= 30
  3890.9  444.13  4063.7  440.41    4125  439.17  4309.1   434.8  4339.2  434.79
  4555.5  431.34  4585.3  433.28  4800.1  432.13  4856.4  429.88  4979.8  429.33
  5001.1  419.12  5012.1  422.95    5019  427.55  5033.6  429.68  5097.7  430.35
  5103.1  431.84  5157.3  428.94  5162.6  430.49    5196  429.95    5291  430.88
  5303.1  431.52  5536.8  432.96  5596.4  435.84  5620.8  434.33  5704.8   437.6
  5729.2  436.11  5788.8  439.08  5867.4  438.83  6005.7  446.44  6194.4  453.48
#Mann= 11 ,-1 , 0
  3890.9     .05       0  4063.7     .08       0    4125     .05       0
  4309.1     .08       0  4339.2     .05       0  4800.1     .08       0
  4979.8     .07       0  5033.6     .08       0    5196     .05       0
    5291     .08       0  5303.1     .05       0
Bank Sta=4979.8,5033.6
XS Rating Curve= 0 ,0
Exp/Cntr=0.3,0.1

Type RM Length L Ch R = 1 ,21329   ,953,953,953
BEGIN DESCRIPTION:
BIG ELM CREEK 27.0
END DESCRIPTION:
XS GIS Cut Line= 2
      3460745.84     10479661.85      3460364.03     10476945.75
#Sta/Elev= 30
    3530   448.2    3712  445.97  3752.4  443.94  3863.5  442.88  3893.7  439.57
  3944.2  438.66  4021.9  435.23  4164.4  432.31  4449.2   429.8  4550.1  430.45
  4958.4  428.77  4974.3  428.05  4984.4   424.9  4994.5  419.12  5004.3  415.61
  5007.6  416.11  5014.7  419.99  5024.6  426.86  5029.6  427.11  5034.9  428.93
  5115.6  427.59    5210  429.65  5378.2  433.61  5549.9  441.25  5580.2  441.71
    5676  447.67  5711.4  448.26  5752.4  451.98  5984.1  464.72  6272.8  472.87
#Mann= 5 ,-1 , 0
    3530     .05       0  4958.4     .16       0  4974.3     .07       0
  5034.9     .16       0    5210     .05       0
Bank Sta=4974.3,5034.9
XS Rating Curve= 0 ,0
Exp/Cntr=0.3,0.1

Type RM Length L Ch R = 1 ,20376   ,1148,1148,1148
BEGIN DESCRIPTION:
BIG ELM CREEK 24.0
END DESCRIPTION:
XS GIS Cut Line= 2
      3461405.56     10479062.88      3460954.17     10476640.99
#Sta/Elev= 30
  3787.2  443.73  3859.7  441.63  3900.4  441.63  4160.3   431.3  4328.6  427.28
  4663.3  428.39  4836.2  427.89  4856.5  428.88  4876.9  426.27  4937.9  426.45
  4976.5  425.26  4981.6  423.56  4988.8  419.18  4998.7  415.83  5009.1  417.49
  5029.2  424.98  5034.3   425.8  5070.2  426.91  5179.1  426.59    5294   427.6
  5471.3  436.88  5670.7  449.21  5722.5  451.74  5751.7  454.89  5792.4  456.62
  5863.6  462.46  5934.8  466.16  6026.3  474.18  6124.3  480.58  6250.8  484.54
#Mann= 7 ,-1 , 0
  3787.2     .05       0  4976.5    .035       0  5034.3     .05       0
  5070.2     .12       0  5179.1     .16       0  5670.7     .12       0
  5722.5     .05       0
Bank Sta=4976.5,5029.2
XS Rating Curve= 0 ,0
Exp/Cntr=0.3,0.1

Type RM Length L Ch R = 1 ,19228   ,1138,1138,1138
BEGIN DESCRIPTION:
BIG ELM CREEK 21.0
END DESCRIPTION:
XS GIS Cut Line= 3
      3462264.94     10479045.55      3462100.01     10477283.37
        3461857.     10476970.93
#Sta/Elev= 30
  3678.1  443.53  3862.8  440.86    4144  430.85  4439.7  423.41  4495.6  422.98
  4525.7  421.08  4545.8  422.71  4619.9  423.91  4769.1  424.17  4967.6   425.4
  4977.7  423.33  4987.7  417.79  4997.8  414.36  5007.5  413.55  5010.8  414.05
  5017.8   419.7  5027.9  423.78  5046.4  425.12  5078.1  422.66  5098.2  424.86
  5218.7   424.2    5279  426.51  5379.4  433.01  5446.3  440.11  5522.4  444.92
  5576.8  447.52  5632.9  453.49  5647.4  453.32  5732.4  459.97  5843.8  463.03
#Mann= 7 ,-1 , 0
  3678.1     .05       0  4439.7     .16       0  4619.9     .05       0
  4769.1     .16       0  4967.6     .07       0  5046.4     .16       0
  5522.4     .05       0
Bank Sta=4967.6,5046.4
XS Rating Curve= 0 ,0
Exp/Cntr=0.3,0.1

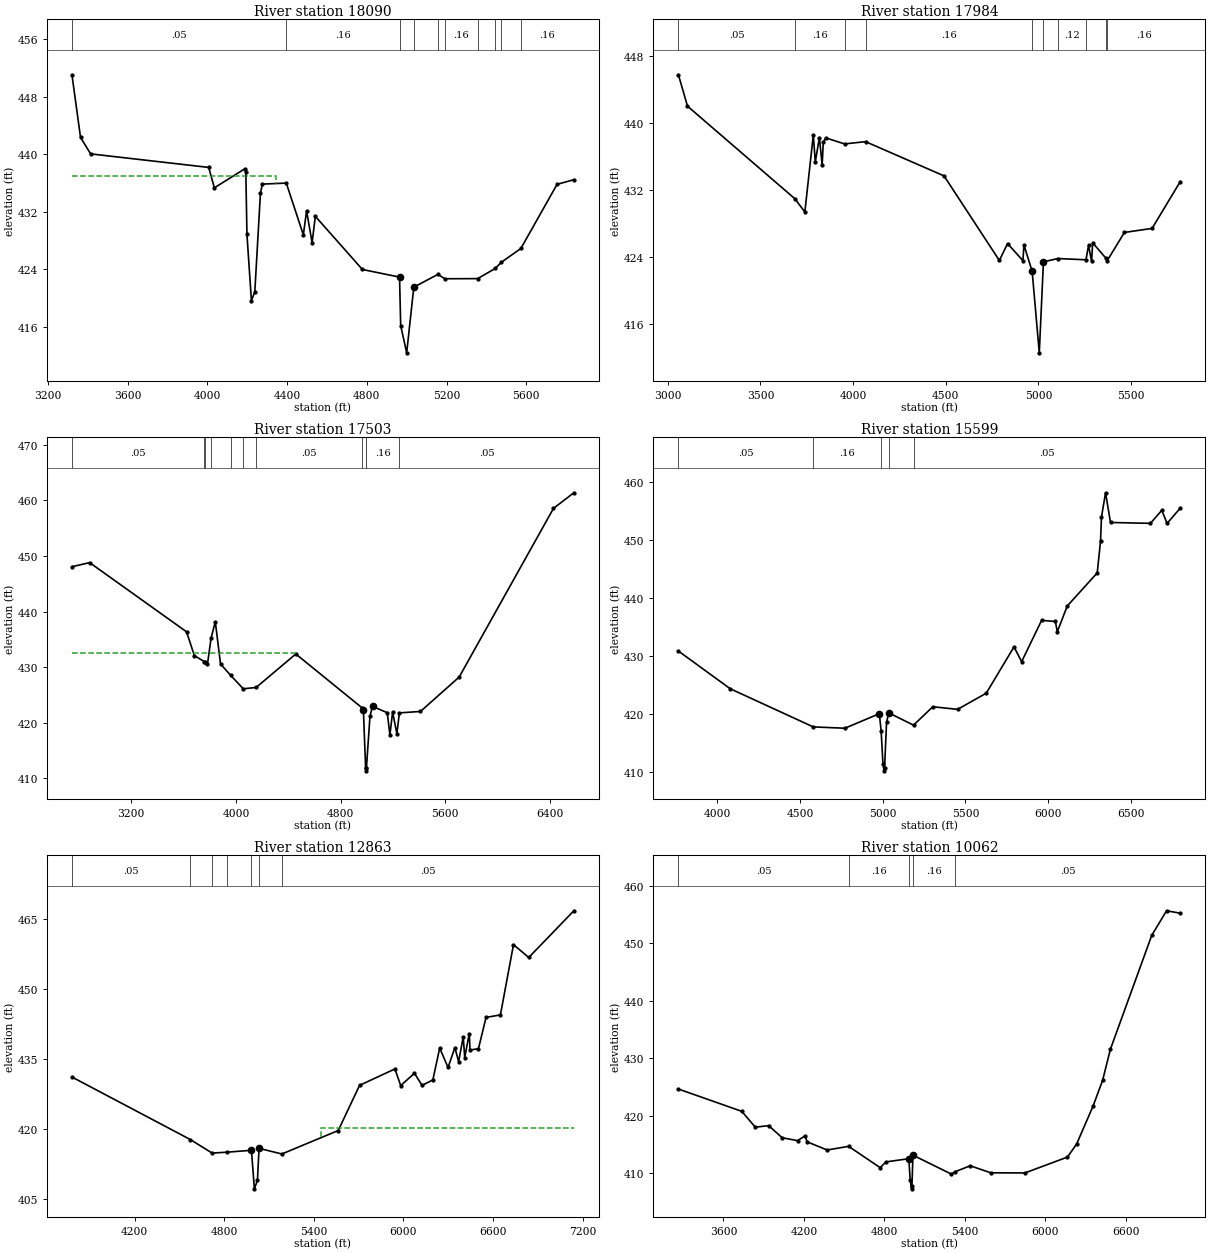
Type RM Length L Ch R = 1 ,18090   ,106,106,106
BEGIN DESCRIPTION:
BIG ELM CREEK 19.0
END DESCRIPTION:
XS GIS Cut Line= 3
      3462576.22     10479341.22      3462997.36      10478472.6
      3462268.21     10477101.11
#Sta/Elev= 30
  3320.2  451.05  3363.3  442.33  3414.1  440.05  4006.5  438.17  4034.7  435.33
  4186.6  437.96  4192.7  437.57  4198.3  428.87  4220.8  419.66  4237.8  420.87
    4266  434.55  4275.5  435.85  4395.8  435.99  4481.3   428.8  4497.6  432.13
  4525.3  427.71  4541.6  431.37  4777.6  423.98  4964.1  422.92  4969.8  416.18
  4999.9  412.39  5035.7  421.52  5156.6   423.3  5191.3  422.69  5356.4  422.71
  5444.7  424.13  5474.9  424.98  5572.9   426.9  5754.6  435.82  5838.8  436.46
#Mann= 10 ,-1 , 0
  3320.2     .05       0  4395.8     .16       0  4964.1     .07       0
  5035.7     .16       0  5156.6     .12       0  5191.3     .16       0
  5356.4     .12       0  5444.7     .16       0  5474.9     .12       0
  5572.9     .16       0
#XS Ineff= 2 , 0
         4343.18  436.97
Permanent Ineff=
       F       F
Bank Sta=4964.1,5035.7
XS Rating Curve= 0 ,0
Exp/Cntr=0.3,0.1

Type RM Length L Ch R = 1 ,17984   ,481,481,481
BEGIN DESCRIPTION:
BIG ELM CREEK 18.0
END DESCRIPTION:
XS GIS Cut Line= 5
      3463149.12     10479554.83      3463268.92     10478825.63
      3463128.29     10478627.71      3462984.34     10478268.61
      3462368.02     10477079.37
#Sta/Elev= 30
  3057.6  445.75  3106.6  442.01  3685.7  430.98  3739.8   429.4  3785.4  438.58
  3796.1  435.36  3818.4  438.27  3833.2  434.97  3839.3  437.73  3854.1  438.22
  3953.9  437.51  4067.3  437.78  4490.7   433.7  4789.3  423.62  4833.5  425.63
  4916.4   423.6  4922.1  425.46  4966.3  422.32  5004.7  412.61  5027.1  423.45
  5104.7  423.85  5256.7   423.7  5270.5  425.41    5287   423.5  5292.6  425.73
  5364.5  423.88  5369.5  423.53    5464  426.96  5613.3  427.44  5765.7  433.03
#Mann= 10 ,-1 , 0
  3057.6     .05       0  3685.7     .16       0  3953.9     .12       0
  4067.3     .16       0  4966.3     .07       0  5027.1     .16       0
  5104.7     .12       0  5256.7     .16       0  5364.5     .12       0
  5369.5     .16       0
Bank Sta=4966.3,5027.1
XS Rating Curve= 0 ,0
Exp/Cntr=0.3,0.1

Type RM Length L Ch R = 1 ,17503   ,1904,1904,1904
BEGIN DESCRIPTION:
BIG ELM CREEK 17.0
END DESCRIPTION:
XS GIS Cut Line= 4
      3463299.73     10479946.74      3463280.56     10478498.64
      3462968.06     10476667.05       3462865.7     10476148.95
#Sta/Elev= 30
  2747.4  448.07  2882.5  448.81  3622.6  436.35  3682.6  432.06  3758.7  430.98
  3761.8  430.87  3782.6  430.51  3810.3   435.2  3842.6  438.15  3882.6  430.55
  3960.6  428.48  4056.4  426.08  4154.6  426.32  4457.7  432.35  4966.4   422.6
  4973.7  422.34  4991.1   411.8  4993.8   411.3  4997.1   411.8  5024.4  421.21
  5044.1  422.91  5156.3  421.77  5176.6  417.74  5196.9  421.88  5229.7  418.01
    5249  421.74  5410.2     422  5705.9   428.2  6426.2  458.58  6581.8  461.39
#Mann= 11 ,-1 , 0
  2747.4     .05       0  3758.7     .16       0  3761.8     .12       0
  3810.3     .16       0  3960.6     .12       0  4056.4     .16       0
  4154.6     .05       0  4966.4     .16       0  4991.1     .07       0
  4997.1     .16       0    5249     .05       0
#XS Ineff= 2 , 0
         4457.39  432.53
Permanent Ineff=
       F       F
Bank Sta=4973.7,5044.1
XS Rating Curve= 0 ,0
Exp/Cntr=0.3,0.1

Type RM Length L Ch R = 1 ,15599   ,2736,2736,2736
BEGIN DESCRIPTION:
BIG ELM CREEK 14.0
END DESCRIPTION:
XS GIS Cut Line= 3
      3463868.01     10478670.53      3464766.46     10476665.31
      3464675.31     10475831.97
#Sta/Elev= 30
  3764.1  430.81  4077.5   424.3  4579.6  417.71    4771  417.48  4979.2  419.99
  4990.2  417.04  5001.1  411.34  5007.6  410.12  5010.9  410.62    5023  418.53
  5036.6  420.13    5186  418.01  5302.6  421.19  5452.6  420.74  5625.9  423.53
  5793.7  431.53    5840  428.98  5960.7  436.11    6044  435.92  6055.6  434.14
    6116   438.6  6297.1  444.31  6317.2  449.82  6322.8  453.93  6347.4  458.15
  6377.5  453.02    6619  452.87  6687.8  455.13  6719.6  452.85  6799.7  455.52
#Mann= 5 ,-1 , 0
  3764.1     .05       0  4579.6     .16       0  4990.2     .07       0
  5036.6     .16       0    5186     .05       0
Bank Sta=4979.2,5036.6
XS Rating Curve= 0 ,0
Exp/Cntr=0.3,0.1

Type RM Length L Ch R = 1 ,12863   ,2801,2801,2801
BEGIN DESCRIPTION:
BIG ELM CREEK 9.0
END DESCRIPTION:
XS GIS Cut Line= 2
      3466133.63      10478878.8       3465469.8     10475585.65
#Sta/Elev= 30
  3781.2  431.13  4573.2  417.72  4719.5  414.81  4821.6  415.01  4982.7  415.41
  5002.2  407.14  5022.8  408.97  5033.5  415.82  5186.4  414.62  5563.5  419.65
  5706.3  429.34  5942.9  432.86  5981.8  429.28  6073.6  431.95  6124.6  429.33
  6196.9  430.51  6242.6  437.34  6298.5  433.18  6344.2  437.44  6369.4  434.43
  6400.1  439.74  6410.2  435.31  6440.7  440.46  6445.8  436.92    6502  437.21
    6553  443.92    6649  444.45  6736.6  459.53  6838.7  456.77  7140.6  466.79
#Mann= 7 ,-1 , 0
  3781.2     .05       0  4573.2      .1       0  4719.5     .05       0
  4821.6     .16       0  4982.7     .07       0  5033.5     .16       0
  5186.4     .05       0
#XS Ineff= 2 , 0
                         5451.45          420.25
Permanent Ineff=
       F       F
Bank Sta=4982.7,5033.5
XS Rating Curve= 0 ,0
Exp/Cntr=0.3,0.1

Type RM Length L Ch R = 1 ,10062   ,2780,2780,2780
BEGIN DESCRIPTION:
BIG ELM CREEK 6.0
END DESCRIPTION:
XS GIS Cut Line= 4
       3466784.7      10478735.6      3467461.77     10477824.16
      3467904.48     10475467.39      3467917.49      10475259.1
#Sta/Elev= 30
  3264.4  424.63  3737.2  420.75  3837.4     418  3937.5  418.27  4037.6  416.17
  4152.4  415.66  4208.7  416.49  4223.3  415.46  4373.5  414.03  4533.3  414.67
  4768.7  410.96  4811.2  411.96  4982.3  412.52  4992.5  408.77  5002.4  407.28
  5005.7  407.78  5012.9  413.13  5299.1  409.85  5328.3  410.26  5440.2  411.29
  5592.8  410.07  5847.2  410.04  6164.9   412.8  6233.9   415.1    6356  421.66
  6427.2  426.15  6485.1  431.54  6793.1  451.33  6903.8  455.62  7006.5   455.2
#Mann= 5 ,-1 , 0
  3264.4     .05       0  4533.3     .16       0  4982.3     .07       0
  5012.9     .16       0  5328.3     .05       0
Bank Sta=4982.3,5012.9
XS Rating Curve= 0 ,0
Exp/Cntr=0.3,0.1

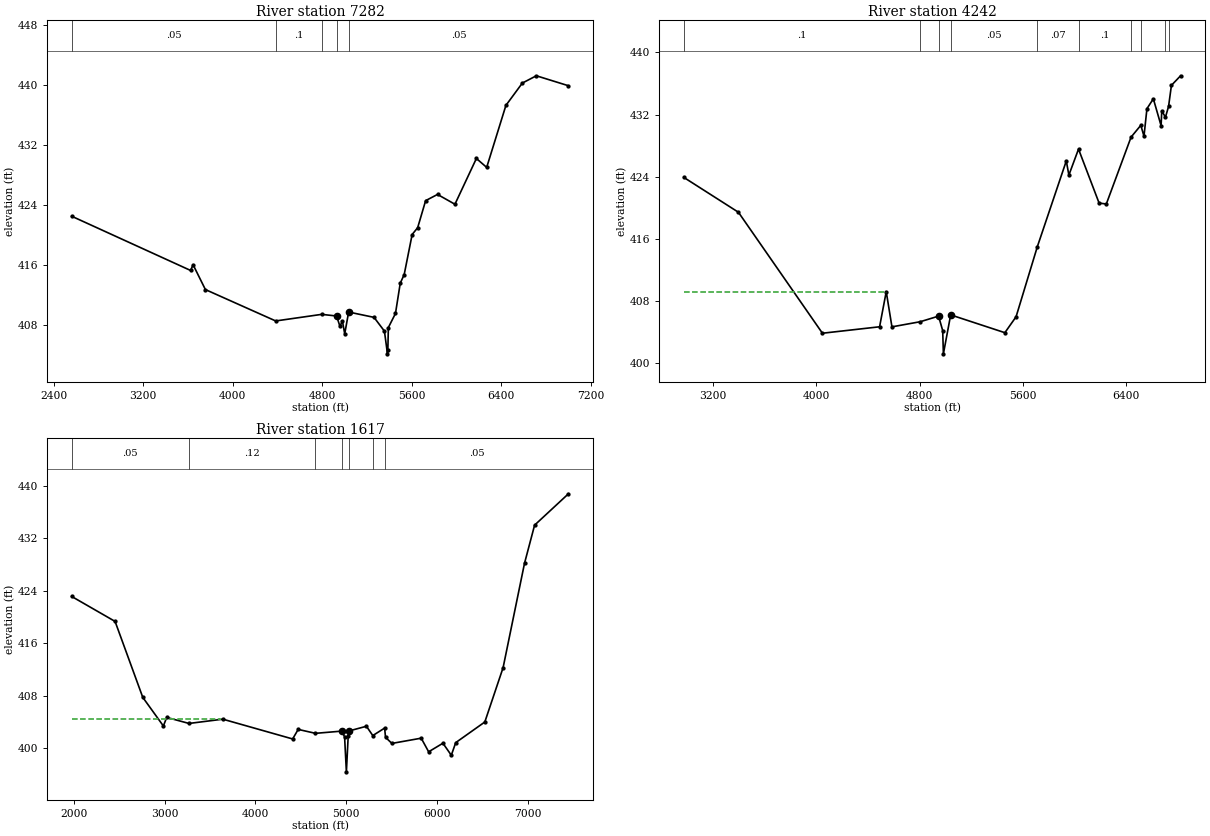
Type RM Length L Ch R = 1 ,7282    ,3040,3040,3040
BEGIN DESCRIPTION:
BIG ELM CREEK 4.0
END DESCRIPTION:
XS GIS Cut Line= 4
       3467331.6     10478774.66      3468490.41     10478162.71
      3470078.96     10476365.83       3469727.4     10475727.83
#Sta/Elev= 30
    2562  422.47  3624.2  415.23  3646.2     416  3756.3  412.68  4384.2  408.49
    4795  409.37 4928.13  409.15  4958.1  407.77  4979.9  408.49  5000.8  406.77
  5035.9  409.68  5262.6  408.97  5355.5  407.13  5382.8   404.1  5386.1   404.6
  5390.6  407.61  5454.2  409.49  5496.8  413.53    5532  414.68  5603.1  420.03
  5652.4  420.94  5723.5  424.55  5829.8  425.38  5985.3  424.07  6176.9  430.18
  6268.9  428.99  6440.8  437.27  6587.6  440.25  6712.5  441.22  6999.3  439.89
#Mann= 5 ,-1 , 0
    2562     .05       0  4384.2      .1       0    4795     .05       0
 4928.13    .035       0  5035.9     .05       0
Bank Sta=4928.13,5035.9
XS Rating Curve= 0 ,0
Exp/Cntr=0.3,0.1

Type RM Length L Ch R = 1 ,4242    ,2625,2625,2625
BEGIN DESCRIPTION:
Mapping XS e3d02ca1
END DESCRIPTION:
XS GIS Cut Line= 4
      3470320.41     10478257.57       3471205.8     10477424.26
      3470520.04     10475514.54      3469938.44     10475358.29
#Sta/Elev= 30
  2973.8  423.91  3396.6  419.43  4047.3  403.87    4490   404.7 4541.45  409.22
  4585.6  404.69  4804.7  405.35  4946.8  406.07  4978.7  404.21  4984.1  401.22
  5040.5  406.23  5460.2  403.94    5547  405.99  5711.9  415.01  5935.9  426.03
    5956  424.21  6030.6  427.55    6190  420.61  6245.9  420.49  6437.5  429.09
    6513  430.61  6537.6  429.21  6560.5  432.75  6610.1  434.02  6670.1  430.56
  6675.3  432.47  6703.9  431.65    6728  433.04  6750.1  435.75    6821  436.98
#Mann= 10 ,-1 , 0
  2973.8      .1       0  4804.7     .05       0  4946.8    .035       0
  5040.5     .05       0  5711.9     .07       0  6030.6      .1       0
  6437.5     .05       0    6513      .1       0  6703.9     .05       0
    6728      .1       0
#XS Ineff= 2 , 0
       0  4539.3  409.23  5064.4       0  406.04
Permanent Ineff=
       F       T
Bank Sta=4946.8,5040.5
XS Rating Curve= 0 ,0
Exp/Cntr=0.3,0.1

Type RM Length L Ch R = 1 ,1617    ,0,0,0
BEGIN DESCRIPTION:
BIG ELM CREEK 1.0
END DESCRIPTION:
XS GIS Cut Line= 4
       3470402.5     10478283.23       3472160.3      10476840.1
      3472095.19     10475548.87      3470239.93     10475136.59
#Sta/Elev= 30
    1977  423.13  2454.5  419.32  2759.4  407.72  2986.2  403.35  3022.8  404.66
    3268  403.74  3640.6  404.39    4409  401.37    4470  402.83  4660.3  402.23
  4950.7  402.57  4980.7  401.69  5000.5  396.35  5020.7  401.88  5030.8   402.6
    5221  403.31  5291.1  401.89  5421.3  403.03  5431.3  401.62  5501.3  400.69
  5823.9  401.49  5905.9  399.41  6063.1  400.72  6155.3  398.88  6203.9  400.81
  6524.1  403.96  6725.4  412.26    6961  428.19  7072.1  434.02  7444.7  438.81
#Mann= 7 ,-1 , 0
    1977     .05       0    3268     .12       0  4660.3     .16       0
  4950.7     .07       0  5030.8     .16       0  5291.1     .12       0
  5421.3     .05       0
#XS Ineff= 2 , 0
       0 3612.58   404.4               0
Permanent Ineff=
       F       F
Bank Sta=4950.7,5030.8
XS Rating Curve= 0 ,0
Exp/Cntr=0.3,0.1

Chan Stop Cuts=-1
Use User Specified Reach Order=0
Composite Channel Slope=5