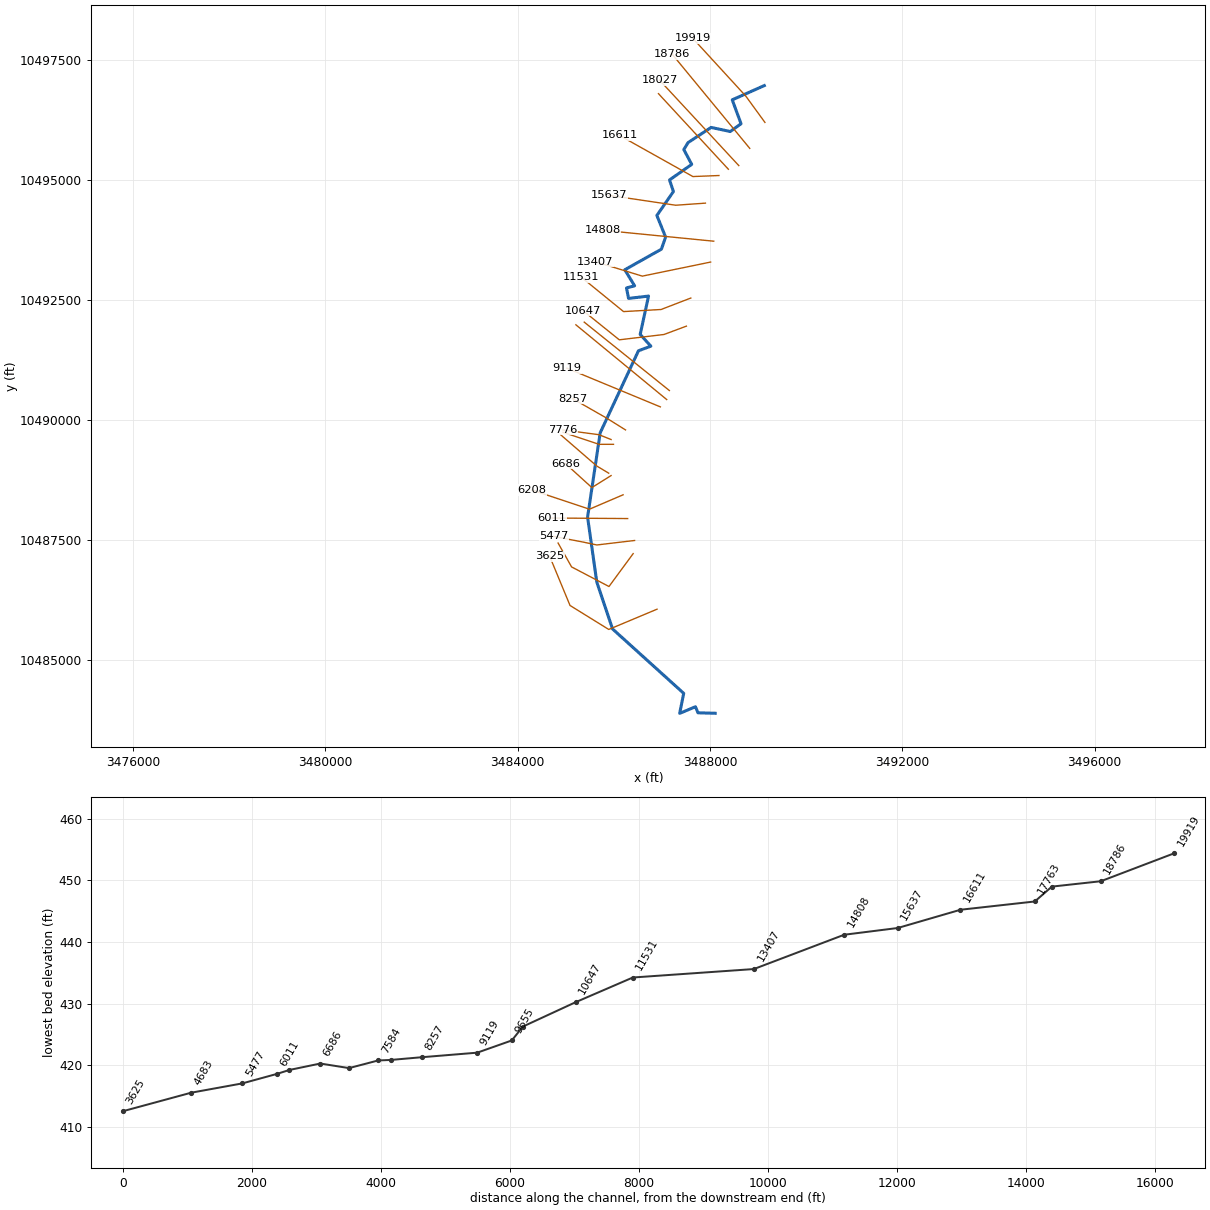
--- BRIER CREEK.prj (project) ---

Proj Title=BRIER CREEK Base Level Engineering
Current Plan=p01
Default Exp/Contr=0.3,0.1
English Units
Geom File=g01
Flow File=f01
Plan File=p01
BEGIN DESCRIPTION:
BRIER CREEK
END DESCRIPTION:

--- BRIER CREEK.p01 (plan) ---

Plan Title=Multiple Run
Short Identifier=Multiple
Geom File=g01
Flow File=f01
Subcritical Flow
K Sum by GR= 0
Std Step Tol= 0.01
Critical Tol= 0.01
Num of Std Step Trials= 20
Max Error Tol= 0.3
Flow Tol Ratio= 0.001
Split Flow NTrial= 30
Split Flow Tol= 0.02
Split Flow Ratio= 0.02
Log Output Level= 0
Friction Slope Method= 1
Unsteady Friction Slope Method= 2
Unsteady Bridges Friction Slope Method= 1
Parabolic Critical Depth
Global Vel Dist=  1 , 1 , 1
Global Log Level= 0
CheckData=True
Encroach Param= -1, 0, 0, 0
BEGIN DESCRIPTION:
Multiple Run
END DESCRIPTION:

--- BRIER CREEK.f01 (steady flow) ---

Flow Title=Multiple
Number of Profiles=7
Profile Names=10-year,25-year,50-year,1pct_min,100-year,1pct_plu,500-year
River Rch & RM= BRIER CREEK,Reach-1,19919
    1522    2143    2667    2418    3270    4423    4908
River Rch & RM= BRIER CREEK,Reach-1,17763
    1873    2659    3327    3030    4097    5541    6204
River Rch & RM= BRIER CREEK,Reach-1,13407
    2077    2945    3680    3344    4522    6116    6819
Boundary for River Rch & Prof#=BRIER CREEK,Reach-1,1
Up Type=0
Dn Type=3
Dn Slope=0.005
Boundary for River Rch & Prof#=BRIER CREEK,Reach-1,2
Up Type=0
Dn Type=3
Dn Slope=0.005
Boundary for River Rch & Prof#=BRIER CREEK,Reach-1,3
Up Type=0
Dn Type=3
Dn Slope=0.005
Boundary for River Rch & Prof#=BRIER CREEK,Reach-1,4
Up Type=0
Dn Type=3
Dn Slope=0.005
Boundary for River Rch & Prof#=BRIER CREEK,Reach-1,5
Up Type=0
Dn Type=3
Dn Slope=0.005
Boundary for River Rch & Prof#=BRIER CREEK,Reach-1,6
Up Type=0
Dn Type=3
Dn Slope=0.005
Boundary for River Rch & Prof#=BRIER CREEK,Reach-1,7
Up Type=0
Dn Type=3
Dn Slope=0.005

--- BRIER CREEK.g01 (geometry) ---

Geom Title=Existing Conditions

River Reach=BRIER CREEK,Reach-1
Reach XY= 30
      3489129.11     10496958.41      3488462.11     10496661.64
      3488645.06     10496164.14      3488421.62     10496002.31
      3488022.53     10496087.24      3487542.82     10495771.46
      3487454.42     10495627.02      3487619.16     10495318.08
      3487157.28     10494994.10      3487238.38     10494753.25
      3486894.36     10494255.24      3487075.71     10493805.47
      3486988.41     10493553.25      3486226.30     10493124.60
      3486431.81     10492790.70      3486262.00     10492747.05
      3486305.56     10492528.23      3486720.94     10492577.48
      3486547.43     10491779.68      3486768.78     10491534.89
      3486510.97     10491438.54      3485715.03     10489730.44
      3485452.79     10487976.71      3485644.07     10486626.94
      3485972.06     10485649.58      3487452.69     10484309.13
      3487368.49     10483892.12      3487696.18     10484029.92
      3487749.35     10483904.06      3488107.01     10483894.32

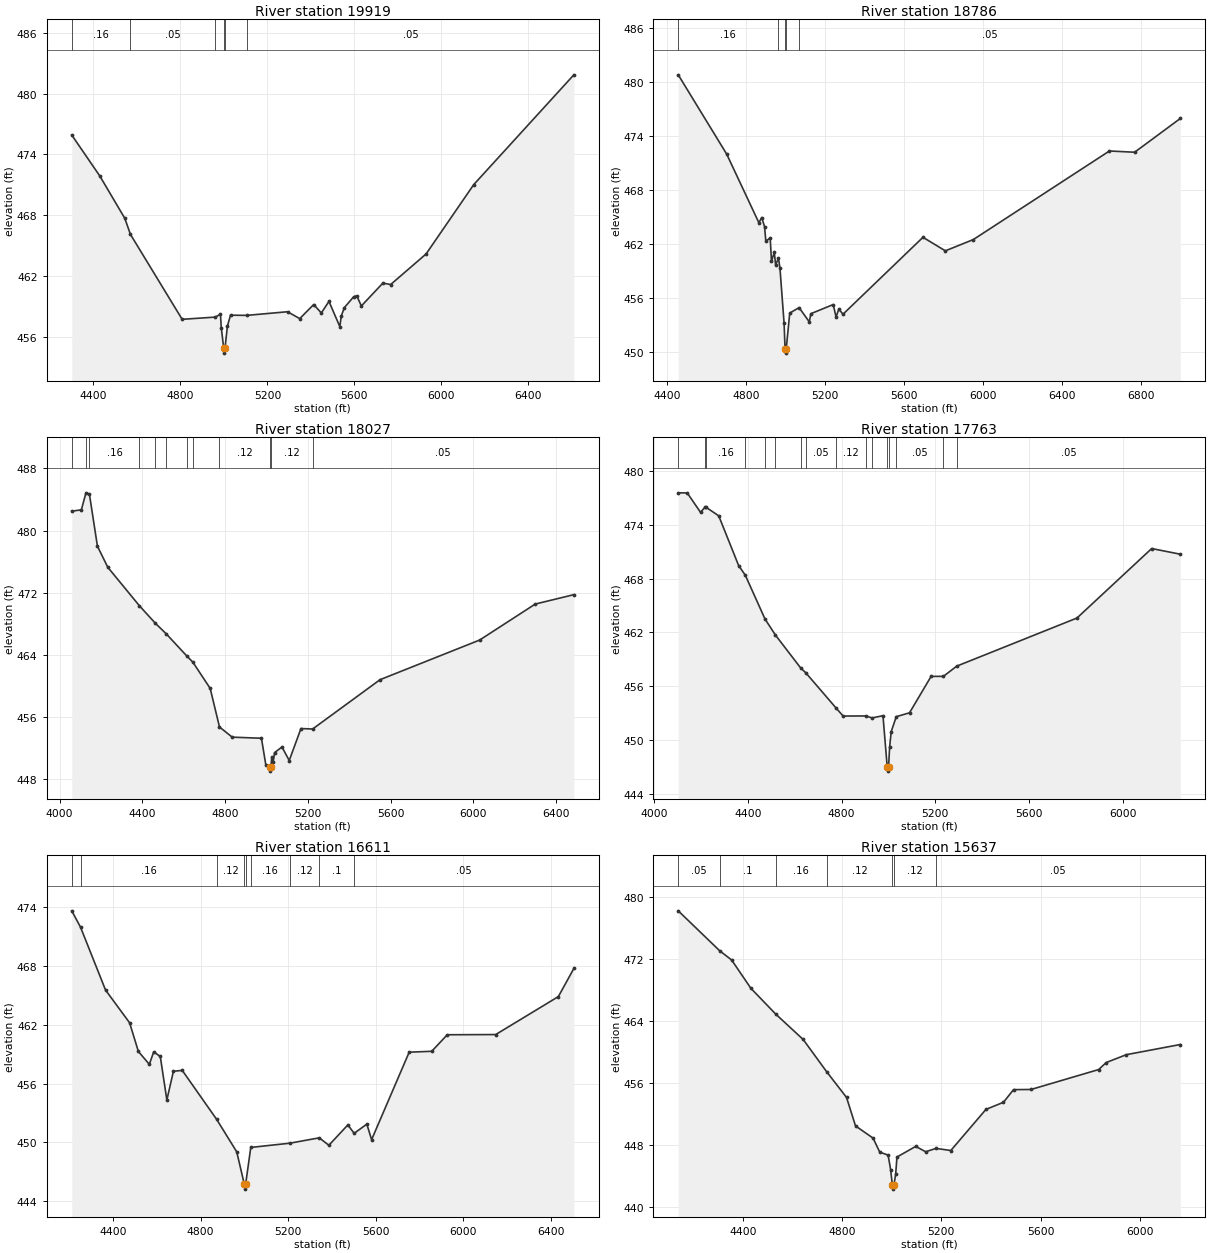
Type RM Length L Ch R = 1,19919,1133,1133,1133
BEGIN DESCRIPTION:
BRIER CREEK 31.0
END DESCRIPTION:
XS GIS Cut Line= 3
      3489142.11     10496191.64      3488742.11     10496741.64
      3487642.08     10497941.67
#Sta/Elev= 30
  4300.7  475.91  4429.4  471.87  4544.5  467.68  4570.5  466.09  4808.1  457.70
  4960.1  457.92  4984.2  458.20  4987.9  456.89  4999.1  454.86  5001.8  454.36
  5005.1  454.86  5016.2  457.03  5030.4  458.11  5105.4  458.09  5292.5  458.45
  5348.6  457.77  5412.7  459.16  5447.9  458.33  5483.0  459.47  5533.0  456.98
  5539.7  458.04  5553.9  458.86  5596.5  459.93  5610.7  460.03  5631.9  459.02
  5730.9  461.28  5766.7  461.14  5929.5  464.16  6148.4  471.01  6608.7  481.86
#Mann=6,-1,0
  4300.7    0.16       0  4570.5    0.05       0  4960.1     0.1       0
  4999.1    0.07       0  5005.1     0.1       0  5105.4    0.05       0
Bank Sta=4999.1,5005.1
Exp/Cntr=0.3,0.1

Type RM Length L Ch R = 1,18786,759,759,759
BEGIN DESCRIPTION:
BRIER CREEK 30.0
END DESCRIPTION:
XS GIS Cut Line= 2
      3488826.56     10495650.86      3487209.76     10497614.89
#Sta/Elev= 30
  4456.5  480.84  4702.3  472.00  4865.1  464.37  4879.5  464.95  4893.8  463.94
  4900.3  462.32  4922.5  462.67  4929.0  460.06  4943.3  461.10  4949.8  459.66
  4964.5  460.43  4972.0  459.29  4992.8  453.19  4997.7  450.35  5000.4  449.85
  5003.7  450.35  5021.5  454.31  5068.8  454.92  5120.5  453.33  5128.4  454.24
  5241.7  455.26  5256.1  453.88  5270.4  454.76  5291.2  454.18  5696.6  462.75
  5809.9  461.24  5952.0  462.50  6641.3  472.36  6769.0  472.22  7000.4  475.98
#Mann=5,-1,0
  4456.5    0.16       0  4964.5    0.12       0  4997.7    0.07       0
  5003.7    0.12       0  5068.8    0.05       0
Bank Sta=4997.7,5003.7
Exp/Cntr=0.3,0.1

Type RM Length L Ch R = 1,18027,264,264,264
BEGIN DESCRIPTION:
BRIER CREEK 28.0
END DESCRIPTION:
XS GIS Cut Line= 2
      3488598.68     10495292.81      3486949.37     10497072.33
#Sta/Elev= 30
  4059.1  482.49  4105.4  482.67  4127.8  484.86  4144.3  484.70  4183.1  477.98
  4233.0  475.27  4385.9  470.30  4463.2  468.04  4514.9  466.70  4615.1  463.82
  4644.0  463.04  4727.9  459.65  4773.0  454.67  4834.5  453.36  4975.7  453.22
  4997.2  449.73  5015.2  449.48  5017.9  448.98  5021.2  449.48  5025.5  450.76
  5032.4  450.19  5039.2  451.37  5074.9  452.09  5110.0  450.35  5166.7  454.47
  5223.0  454.41  5548.9  460.77  6030.2  465.88  6298.9  470.52  6485.4  471.73
#Mann=12,-1,0
  4059.1     0.1       0  4127.8    0.05       0  4144.3    0.16       0
  4385.9    0.05       0  4463.2    0.16       0  4514.9    0.05       0
  4615.1    0.16       0  4644.0    0.05       0  4773.0    0.12       0
  5015.2    0.07       0  5021.2    0.12       0  5223.0    0.05       0
Bank Sta=5015.2,5021.2
Exp/Cntr=0.3,0.1

Type RM Length L Ch R = 1,17763,1152,1152,1152
BEGIN DESCRIPTION:
BRIER CREEK 27.0
END DESCRIPTION:
XS GIS Cut Line= 2
      3488381.68     10495216.84      3486927.70     10496790.18
#Sta/Elev= 30
  4103.3  477.54  4141.7  477.53  4198.4  475.37  4217.2  475.93  4220.9  475.95
  4276.1  474.98  4361.1  469.44  4389.3  468.38  4473.7  463.49  4518.1  461.71
  4626.0  458.04  4647.0  457.53  4778.2  453.55  4806.8  452.70  4904.8  452.71
  4930.4  452.49  4976.9  452.74  4994.9  447.07  4997.6  446.57  5000.9  447.07
  5005.3  449.25  5012.1  450.97  5033.6  452.63  5090.2  453.06  5182.2  457.11
  5234.9  457.12  5291.4  458.25  5804.8  463.61  6123.4  471.34  6245.6  470.71
#Mann=16,-1,0
  4103.3    0.16       0  4217.2    0.05       0  4220.9    0.16       0
  4389.3    0.05       0  4473.7    0.16       0  4518.1    0.05       0
  4626.0    0.16       0  4647.0    0.05       0  4778.2    0.12       0
  4904.8    0.05       0  4930.4    0.16       0  4994.9    0.07       0
  5000.9    0.16       0  5033.6    0.05       0  5234.9    0.16       0
  5291.4    0.05       0
Bank Sta=4994.9,5000.9
Exp/Cntr=0.3,0.1

Type RM Length L Ch R = 1,16611,974,974,974
BEGIN DESCRIPTION:
BRIER CREEK 26.0
END DESCRIPTION:
XS GIS Cut Line= 3
      3488186.33     10495086.64      3487643.82     10495064.94
      3486115.50     10495921.24
#Sta/Elev= 30
  4211.1  473.66  4251.1  471.99  4365.4  465.57  4475.5  462.22  4515.6  459.29
  4565.6  457.98  4585.6  459.25  4615.7  458.78  4645.7  454.34  4675.7  457.27
  4716.1  457.36  4873.2  452.36  4965.1  449.04  4999.7  445.73  5002.5  445.23
  5005.7  445.73  5029.3  449.49  5207.2  449.92  5342.4  450.47  5386.2  449.71
  5473.0  451.79  5501.8  450.93  5559.8  451.87  5581.5  450.28  5753.3  459.22
  5856.4  459.31  5927.3  461.00  6148.7  461.02  6435.2  464.90  6505.9  467.77
#Mann=9,-1,0
  4211.1     0.1       0  4251.1    0.16       0  4873.2    0.12       0
  4999.7    0.07       0  5005.7    0.12       0  5029.3    0.16       0
  5207.2    0.12       0  5342.4     0.1       0  5501.8    0.05       0
Bank Sta=4999.7,5005.7
Exp/Cntr=0.3,0.1

Type RM Length L Ch R = 1,15637,829,829,829
BEGIN DESCRIPTION:
BRIER CREEK 24.0
END DESCRIPTION:
XS GIS Cut Line= 3
      3487904.22     10494511.56      3487285.75     10494468.15
      3485896.96     10494674.30
#Sta/Elev= 30
  4139.3  478.16  4306.4  473.01  4354.6  471.82  4432.1  468.17  4533.0  464.82
  4642.9  461.57  4737.9  457.40  4817.8  454.09  4854.0  450.42  4924.7  448.85
  4951.7  447.04  4985.4  446.66  4995.5  444.79  5002.6  442.77  5005.4  442.27
  5008.6  442.77  5015.7  444.16  5021.1  446.41  5096.6  447.78  5137.0  447.09
  5178.2  447.52  5238.1  447.25  5379.7  452.55  5450.4  453.47  5490.9  455.10
  5561.4  455.12  5834.1  457.69  5864.9  458.60  5945.8  459.61  6163.3  460.92
#Mann=7,-1,0
  4139.3    0.05       0  4306.4     0.1       0  4533.0    0.16       0
  4737.9    0.12       0  5002.6    0.07       0  5008.6    0.12       0
  5178.2    0.05       0
Bank Sta=5002.6,5008.6
Exp/Cntr=0.3,0.1

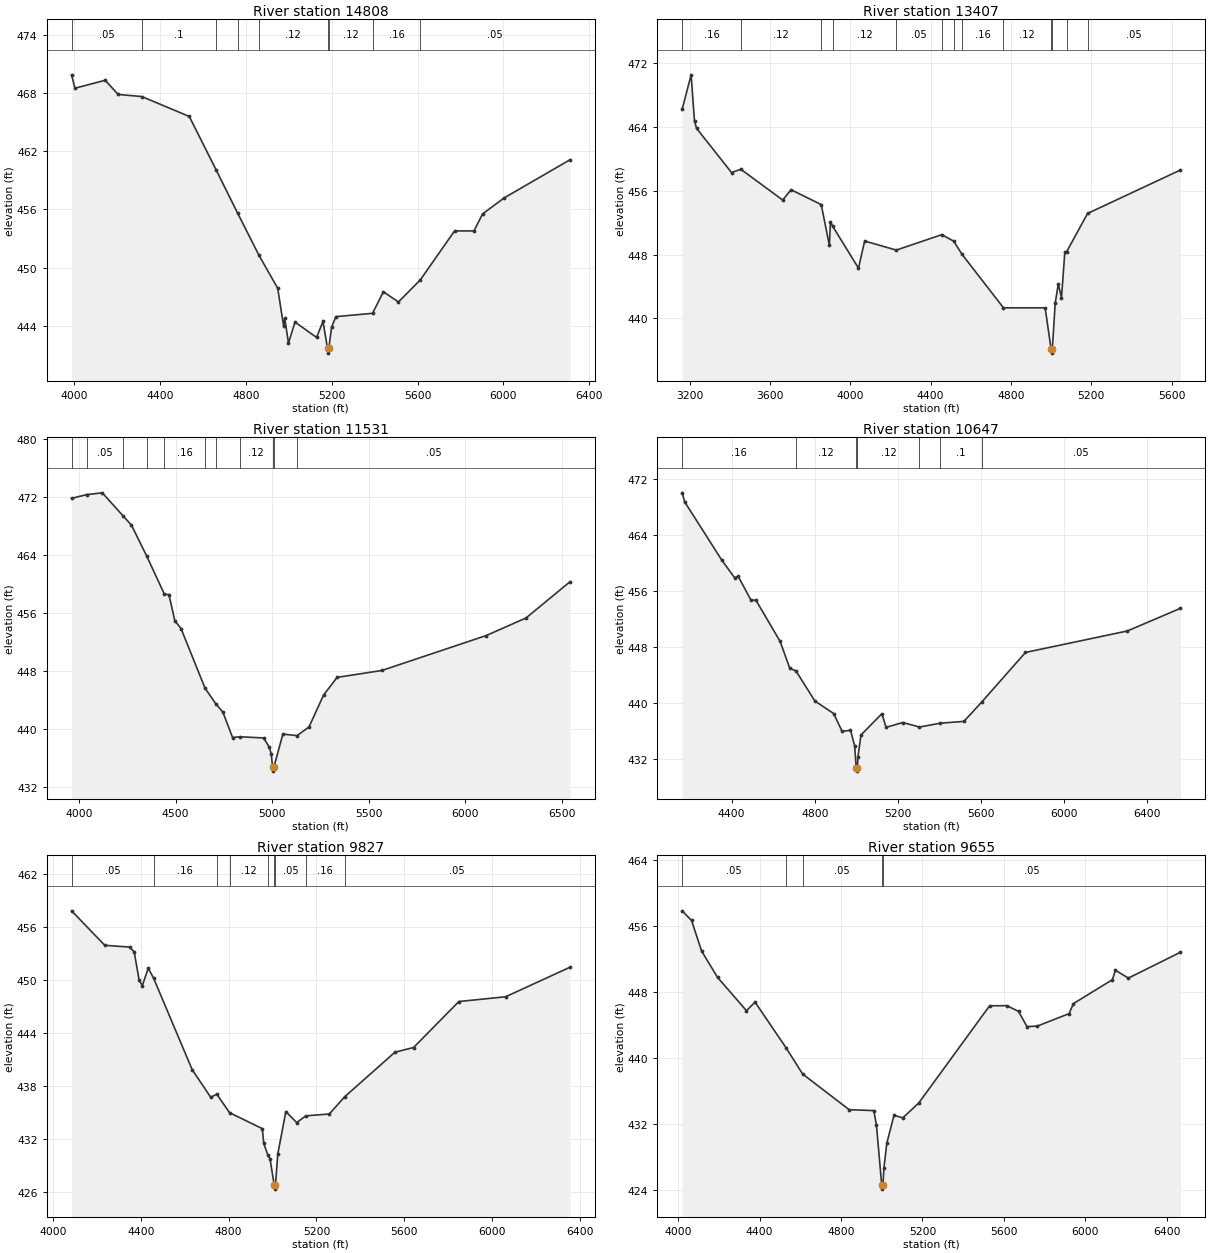
Type RM Length L Ch R = 1,14808,1401,1401,1401
BEGIN DESCRIPTION:
BRIER CREEK 22.0
END DESCRIPTION:
XS GIS Cut Line= 2
      3488077.88     10493719.45      3485766.88     10493947.30
#Sta/Elev= 30
  3988.1  469.85  4003.9  468.47  4144.6  469.29  4204.9  467.83  4315.6  467.61
  4536.5  465.56  4662.1  460.03  4761.8  455.60  4861.6  451.24  4948.5  447.86
  4976.1  443.95  4981.2  444.79  4998.7  442.21  5028.9  444.38  5129.4  442.80
  5159.5  444.44  5180.6  441.68  5183.3  441.18  5186.6  441.68  5199.7  443.86
  5219.8  444.94  5390.3  445.28  5440.9  447.50  5511.2  446.45  5613.4  448.74
  5772.5  453.77  5862.9  453.77  5903.1  455.52  6003.6  457.17  6310.3  461.10
#Mann=9,-1,0
  3988.1    0.05       0  4315.6     0.1       0  4662.1    0.05       0
  4761.8    0.16       0  4861.6    0.12       0  5180.6    0.07       0
  5186.6    0.12       0  5390.3    0.16       0  5613.4    0.05       0
Bank Sta=5180.6,5186.6
Exp/Cntr=0.3,0.1

Type RM Length L Ch R = 1,13407,1876,1876,1876
BEGIN DESCRIPTION:
BRIER CREEK 20.0
END DESCRIPTION:
XS GIS Cut Line= 3
      3488012.70     10493285.42      3486591.30     10492992.46
      3485605.48     10493295.79
#Sta/Elev= 30
  3162.1  466.22  3207.1  470.57  3224.0  464.74  3234.2  463.85  3408.3  458.30
  3454.8  458.71  3663.0  454.85  3705.0  456.14  3855.3  454.27  3895.9  449.14
  3901.0  452.13  3912.8  451.53  4040.8  446.29  4071.4  449.70  4229.1  448.56
  4456.0  450.50  4515.0  449.68  4556.2  448.04  4763.0  441.31  4970.6  441.31
  5000.3  436.12  5003.0  435.62  5006.3  436.12  5020.6  441.87  5036.0  444.31
  5052.0  442.59  5068.6  448.29  5077.2  448.33  5181.9  453.16  5644.8  458.62
#Mann=13,-1,0
  3162.1    0.16       0  3454.8    0.12       0  3855.3     0.1       0
  3912.8    0.12       0  4229.1    0.05       0  4456.0    0.16       0
  4515.0    0.05       0  4556.2    0.16       0  4763.0    0.12       0
  5000.3    0.07       0  5006.3    0.12       0  5077.2    0.16       0
  5181.9    0.05       0
Bank Sta=5000.3,5006.3
Exp/Cntr=0.3,0.1

Type RM Length L Ch R = 1,11531,884,884,884
BEGIN DESCRIPTION:
BRIER CREEK 17.0
END DESCRIPTION:
XS GIS Cut Line= 4
      3487600.38     10492536.72      3486981.93     10492298.02
      3486200.68     10492254.61      3485321.78     10492970.76
#Sta/Elev= 30
  3961.6  471.81  4038.8  472.32  4120.5  472.57  4227.2  469.42  4271.6  468.12
  4350.9  463.83  4442.4  458.58  4465.3  458.57  4495.7  454.97  4527.9  453.88
  4652.2  445.67  4707.7  443.53  4744.5  442.37  4794.6  438.88  4832.9  438.98
  4954.9  438.82  4984.9  437.55  4994.9  436.61  5001.9  434.75  5004.6  434.25
  5007.9  434.75  5055.0  439.35  5128.4  439.14  5190.2  440.33  5265.3  444.71
  5335.4  447.16  5567.4  448.11  6107.4  452.92  6313.5  455.34  6540.7  460.33
#Mann=11,-1,0
  3961.6    0.16       0  4038.8    0.05       0  4227.2    0.16       0
  4350.9    0.05       0  4442.4    0.16       0  4652.2     0.1       0
  4707.7    0.16       0  4832.9    0.12       0  5001.9    0.07       0
  5007.9    0.12       0  5128.4    0.05       0
Bank Sta=5001.9,5007.9
Exp/Cntr=0.3,0.1

Type RM Length L Ch R = 1,10647,820,820,820
BEGIN DESCRIPTION:
BRIER CREEK 16.0
END DESCRIPTION:
XS GIS Cut Line= 4
      3487508.40     10491951.66      3487043.13     10491778.05
      3486112.57     10491666.94      3485362.54     10492271.13
#Sta/Elev= 30
  4161.9  469.98  4175.1  468.65  4351.6  460.43  4414.1  457.87  4431.9  458.05
  4492.5  454.70  4517.5  454.63  4633.4  448.77  4679.7  444.94  4709.6  444.56
  4800.5  440.27  4891.2  438.47  4931.5  435.92  4971.7  436.11  4991.9  433.86
  4999.0  430.76  5001.7  430.26  5005.0  430.76  5007.4  432.24  5022.1  435.42
  5122.8  438.45  5142.9  436.51  5223.5  437.20  5303.6  436.55  5402.7  437.10
  5517.2  437.36  5602.6  440.11  5813.3  447.20  6302.8  450.26  6558.8  453.50
#Mann=7,-1,0
  4161.9    0.16       0  4709.6    0.12       0  4999.0    0.07       0
  5005.0    0.12       0  5303.6    0.16       0  5402.7     0.1       0
  5602.6    0.05       0
Bank Sta=4999,5005
Exp/Cntr=0.3,0.1

Type RM Length L Ch R = 1,9827,172,172,172
BEGIN DESCRIPTION:
BRIER CREEK 14.0
END DESCRIPTION:
XS GIS Cut Line= 2
      3487154.27     10490611.36      3485383.38     10492035.02
#Sta/Elev= 30
  4083.9  457.78  4235.1  453.88  4348.7  453.68  4369.5  453.12  4391.9  449.94
  4406.3  449.31  4433.5  451.30  4457.6  450.17  4633.5  439.82  4718.3  436.69
  4746.0  437.04  4803.9  434.95  4953.5  433.14  4959.9  431.49  4979.0  430.14
  4988.7  429.71  5007.5  426.80  5010.2  426.30  5013.5  426.80  5023.9  430.26
  5060.7  435.07  5110.3  433.83  5151.8  434.59  5259.1  434.80  5328.5  436.74
  5558.2  441.79  5643.1  442.32  5849.4  447.52  6062.6  448.06  6356.1  451.40
#Mann=9,-1,0
  4083.9    0.05       0  4457.6    0.16       0  4746.0    0.05       0
  4803.9    0.12       0  4979.0    0.05       0  5007.5    0.04       0
  5013.5    0.05       0  5151.8    0.16       0  5328.5    0.05       0
Bank Sta=5007.5,5013.5
Exp/Cntr=0.3,0.1

Type RM Length L Ch R = 1,9655,536,536,536
BEGIN DESCRIPTION:
BRIER CREEK 13.0
END DESCRIPTION:
XS GIS Cut Line= 2
      3487098.69     10490423.88      3485209.78     10491979.45
#Sta/Elev= 30
  4019.7  457.86  4065.9  456.70  4115.4  452.98  4193.6  449.78  4335.7  445.73
  4378.0  446.77  4529.3  441.25  4611.3  438.04  4840.0  433.70  4961.0  433.59
  4974.1  431.79  4999.8  424.55  5002.6  424.05  5005.8  424.55  5010.7  426.66
  5025.0  429.66  5060.2  433.02  5103.2  432.71  5181.2  434.50  5529.3  446.32
  5614.0  446.34  5671.4  445.65  5713.0  443.79  5763.9  443.86  5919.6  445.37
  5941.1  446.59  6132.6  449.50  6147.0  450.64  6210.8  449.69  6466.7  452.83
#Mann=5,-1,0
  4019.7    0.05       0  4529.3    0.16       0  4611.3    0.05       0
  4999.8    0.04       0  5005.8    0.05       0
Bank Sta=4999.8,5005.8
Exp/Cntr=0.3,0.1

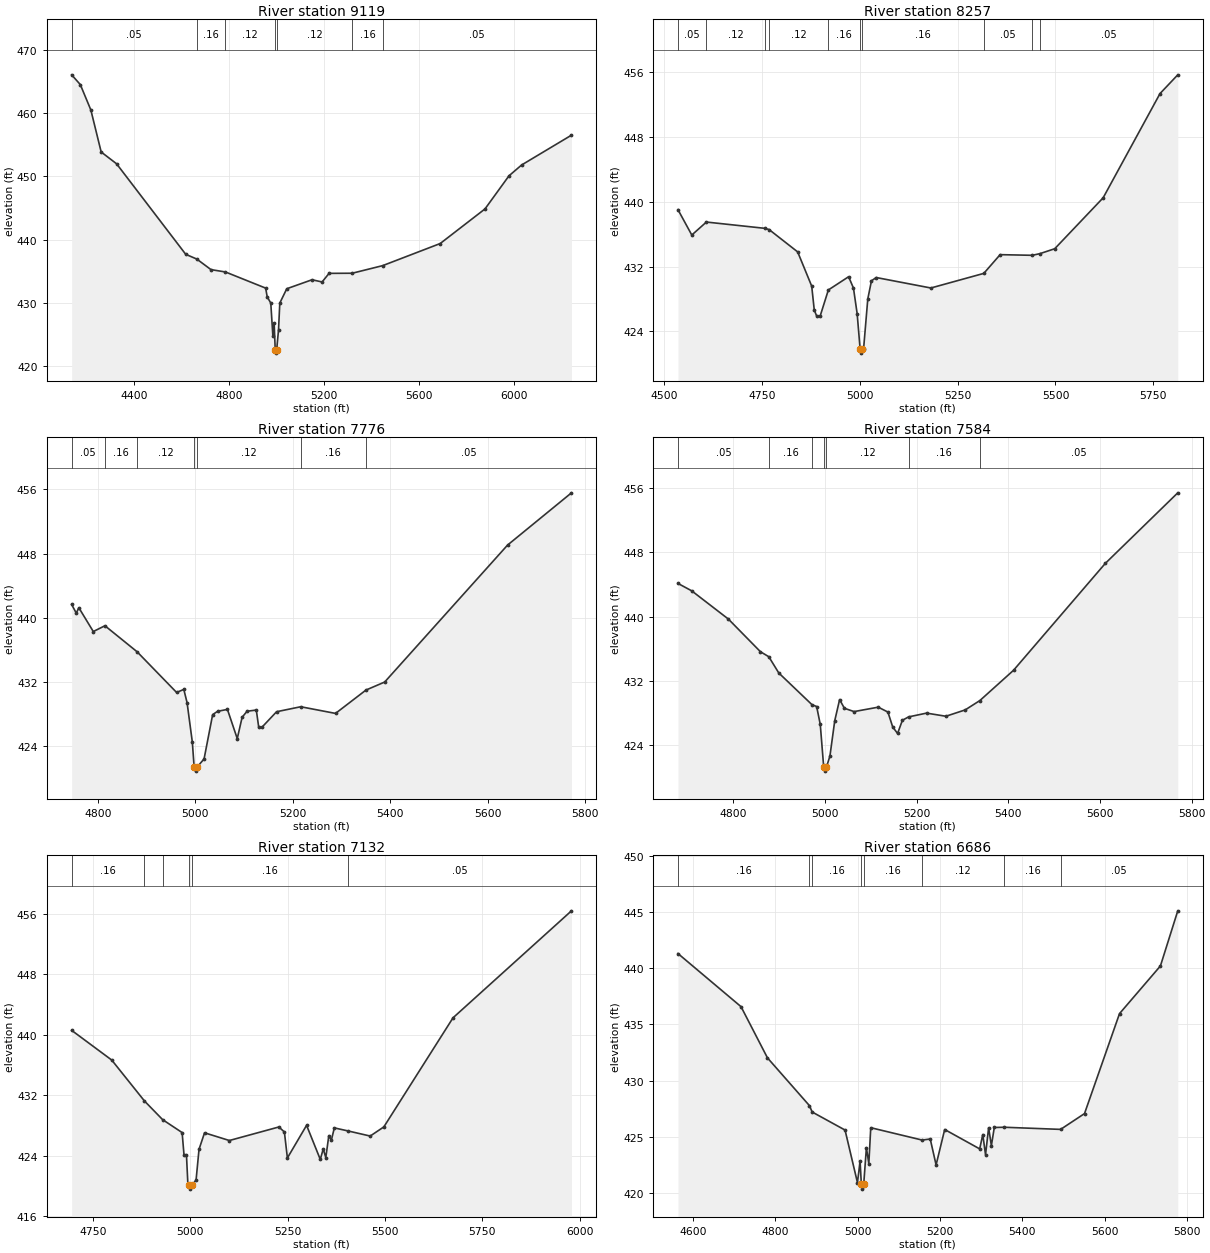
Type RM Length L Ch R = 1,9119,862,862,862
BEGIN DESCRIPTION:
BRIER CREEK 12.0
END DESCRIPTION:
XS GIS Cut Line= 2
      3486966.77     10490271.09      3485022.33     10491076.65
#Sta/Elev= 30
  4138.3  466.03  4174.7  464.49  4219.1  460.48  4262.6  453.84  4327.4  451.98
  4618.6  437.68  4665.2  436.93  4725.0  435.26  4785.8  434.89  4955.2  432.34
  4961.7  430.96  4976.8  429.98  4985.5  424.83  4991.0  426.83  4995.5  422.57
  4998.2  422.07  5001.5  422.57  5009.3  425.69  5014.8  429.98  5044.1  432.24
  5150.5  433.66  5192.9  433.31  5222.2  434.67  5319.6  434.69  5447.9  435.89
  5690.1  439.38  5878.9  444.85  5979.9  450.08  6033.1  451.79  6243.0  456.50
#Mann=7,-1,0
  4138.3    0.05       0  4665.2    0.16       0  4785.8    0.12       0
  4995.5    0.07       0  5001.5    0.12       0  5319.6    0.16       0
  5447.9    0.05       0
Bank Sta=4995.5,5001.5
Exp/Cntr=0.3,0.1

Type RM Length L Ch R = 1,8257,481,481,481
BEGIN DESCRIPTION:
BRIER CREEK 11.0
END DESCRIPTION:
XS GIS Cut Line= 3
      3486242.15     10489791.62      3485842.11     10490041.64
      3485142.08     10490441.66
#Sta/Elev= 30
  4534.7  439.02  4570.1  435.89  4607.4  437.49  4756.0  436.72  4767.6  436.57
  4840.8  433.81  4876.7  429.59  4883.2  426.66  4889.1  425.93  4898.5  425.93
  4919.3  429.12  4971.1  430.75  4983.5  429.34  4992.9  426.20  5000.5  421.83
  5003.2  421.33  5006.5  421.83  5009.3  421.83  5020.1  428.01  5029.5  430.25
  5041.7  430.65  5181.4  429.36  5316.7  431.16  5358.5  433.47  5440.6  433.39
  5459.9  433.59  5498.1  434.20  5621.9  440.48  5767.3  453.33  5812.7  455.64
#Mann=10,-1,0
  4534.7    0.05       0  4607.4    0.12       0  4756.0    0.16       0
  4767.6    0.12       0  4919.3    0.16       0  5000.5    0.07       0
  5006.5    0.16       0  5316.7    0.05       0  5440.6    0.16       0
  5459.9    0.05       0
Bank Sta=5000.5,5006.5
Exp/Cntr=0.3,0.1

Type RM Length L Ch R = 1,7776,192,192,192
BEGIN DESCRIPTION:
BRIER CREEK 10.0
END DESCRIPTION:
XS GIS Cut Line= 3
      3485942.09     10489591.65      3485692.11     10489691.64
      3484942.08     10489791.65
#Sta/Elev= 30
  4746.4  441.65  4755.8  440.58  4761.2  441.24  4790.8  438.28  4814.7  439.00
  4880.7  435.76  4961.8  430.69  4976.6  431.07  4983.3  429.42  4994.1  424.50
  4997.8  421.39  5000.6  420.89  5003.8  421.39  5018.2  422.41  5035.8  427.93
  5045.9  428.34  5066.1  428.58  5086.3  424.94  5096.3  427.60  5106.4  428.35
  5125.4  428.50  5130.4  426.34  5136.7  426.34  5167.0  428.29  5216.6  428.91
  5288.0  428.08  5350.5  430.99  5388.9  431.99  5641.1  449.05  5772.3  455.56
#Mann=7,-1,0
  4746.4    0.05       0  4814.7    0.16       0  4880.7    0.12       0
  4997.8    0.07       0  5003.8    0.12       0  5216.6    0.16       0
  5350.5    0.05       0
Bank Sta=4997.8,5003.8
Exp/Cntr=0.3,0.1

Type RM Length L Ch R = 1,7584,452,452,452
BEGIN DESCRIPTION:
BRIER CREEK 9.0
END DESCRIPTION:
XS GIS Cut Line= 3
      3485992.07     10489491.64      3485692.11     10489491.64
      3484942.14     10489741.63
#Sta/Elev= 30
  4679.3  444.14  4709.3  443.22  4789.3  439.71  4859.3  435.65  4877.5  435.03
  4899.3  433.01  4971.7  429.07  4981.9  428.84  4989.8  426.62  4997.3  421.31
  5000.1  420.81  5003.3  421.31  5010.9  422.69  5021.4  427.08  5032.0  429.70
  5042.5  428.62  5063.6  428.21  5116.3  428.76  5137.4  428.15  5147.9  426.29
  5158.5  425.49  5169.0  427.13  5182.4  427.55  5221.7  428.02  5263.9  427.63
  5306.0  428.42  5338.0  429.58  5411.4  433.34  5611.7  446.63  5769.8  455.40
#Mann=7,-1,0
  4679.3    0.05       0  4877.5    0.16       0  4971.7    0.12       0
  4997.3    0.07       0  5003.3    0.12       0  5182.4    0.16       0
  5338.0    0.05       0
Bank Sta=4997.3,5003.3
Exp/Cntr=0.3,0.1

Type RM Length L Ch R = 1,7132,446,446,446
BEGIN DESCRIPTION:
BRIER CREEK 8.0
END DESCRIPTION:
XS GIS Cut Line= 3
      3485892.11     10488891.64      3485642.11     10489041.64
      3484892.13     10489691.62
#Sta/Elev= 30
  4695.2  440.57  4798.2  436.64  4882.2  431.23  4928.9  428.76  4979.0  427.05
  4983.8  424.11  4990.1  424.11  4993.9  420.10  4997.5  420.07  5000.2  419.57
  5003.5  420.07  5014.8  420.76  5022.4  424.84  5036.6  427.02  5100.3  426.00
  5227.5  427.79  5241.7  427.13  5249.4  423.69  5298.7  428.01  5333.9  423.50
  5341.5  424.88  5348.1  423.75  5355.8  426.64  5362.4  426.05  5370.0  427.67
  5405.7  427.26  5462.1  426.59  5497.2  427.80  5674.9  442.23  5979.2  456.38
#Mann=6,-1,0
  4695.2    0.16       0  4882.2    0.12       0  4928.9    0.16       0
  4997.5    0.07       0  5003.5    0.16       0  5405.7    0.05       0
Bank Sta=4997.5,5003.5
Exp/Cntr=0.3,0.1

Type RM Length L Ch R = 1,6686,478,478,478
BEGIN DESCRIPTION:
BRIER CREEK 7.0
END DESCRIPTION:
XS GIS Cut Line= 3
      3485942.10     10488841.64      3485542.11     10488591.64
      3484992.10     10489091.64
#Sta/Elev= 30
  4563.1  441.33  4716.4  436.59  4780.7  432.02  4882.7  427.76  4889.4  427.19
  4969.3  425.58  4999.4  420.90  5005.9  422.78  5008.8  420.81  5011.5  420.31
  5014.8  420.81  5021.2  424.01  5027.1  422.59  5031.8  425.79  5156.4  424.69
  5176.4  424.78  5190.6  422.47  5211.5  425.63  5296.6  423.90  5304.1  425.18
  5310.8  423.38  5318.3  425.79  5325.0  424.19  5332.1  425.81  5356.8  425.83
  5493.3  425.64  5551.4  427.05  5636.5  435.97  5735.9  440.22  5778.1  445.14
#Mann=8,-1,0
  4563.1    0.16       0  4882.7    0.12       0  4889.4    0.16       0
  5008.8    0.07       0  5014.8    0.16       0  5156.4    0.12       0
  5356.8    0.16       0  5493.3    0.05       0
Bank Sta=5008.8,5014.8
Exp/Cntr=0.3,0.1

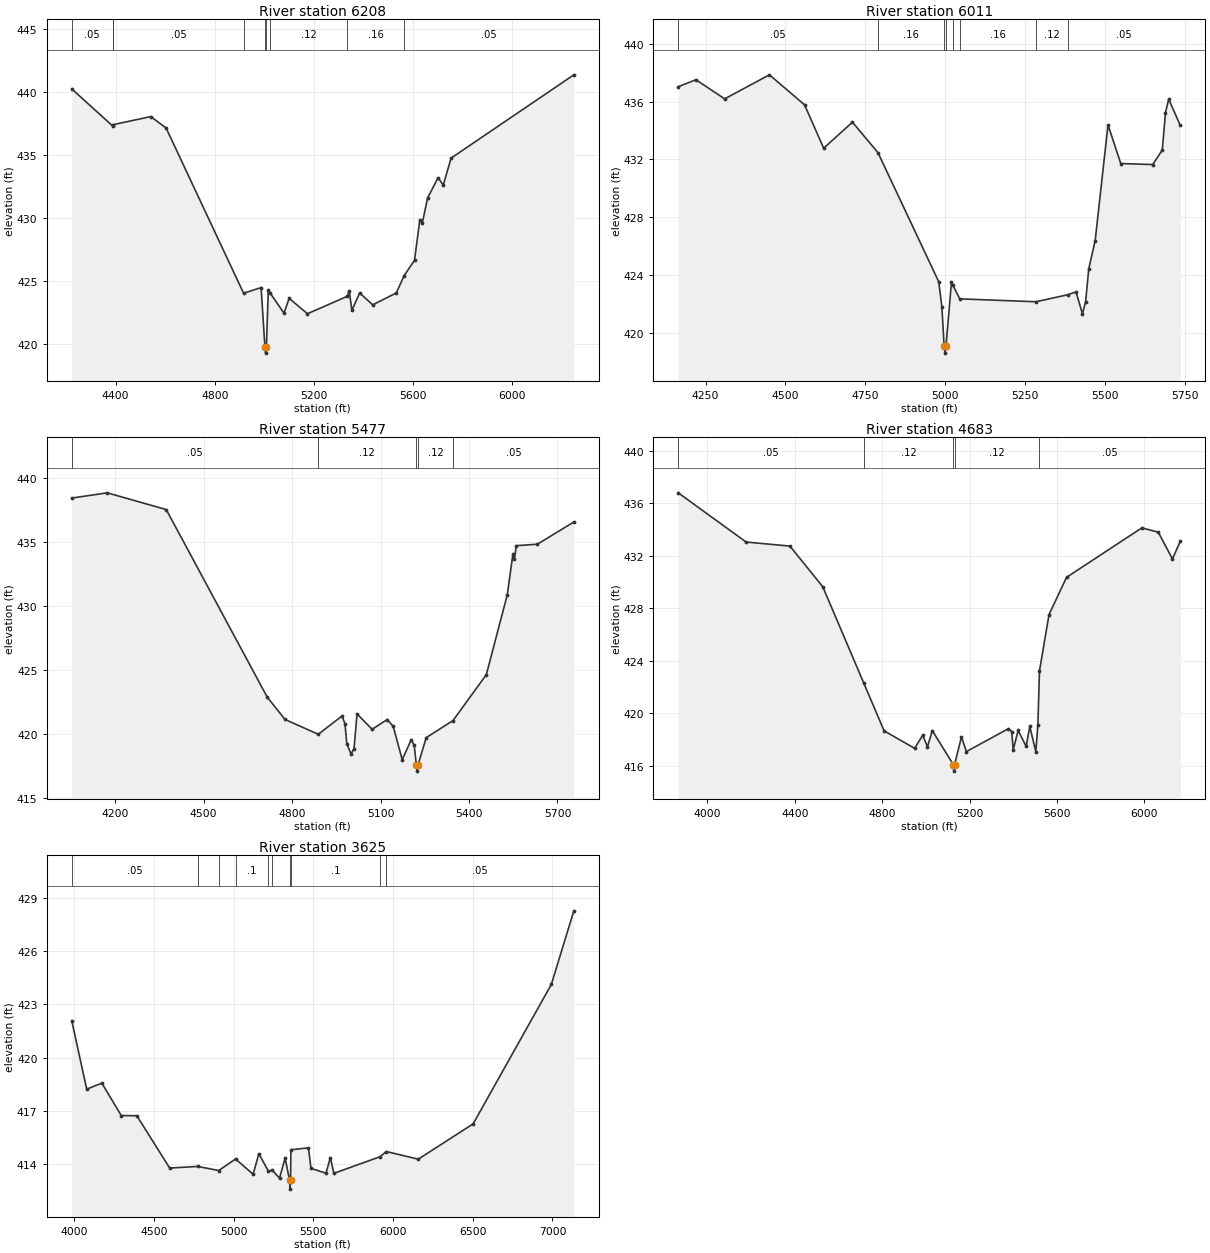
Type RM Length L Ch R = 1,6208,197,197,197
BEGIN DESCRIPTION:
BRIER CREEK 6.0
END DESCRIPTION:
XS GIS Cut Line= 3
      3486192.09     10488441.64      3485492.11     10488141.64
      3484292.08     10488541.65
#Sta/Elev= 30
  4223.1  440.27  4387.9  437.33  4390.2  437.43  4542.2  438.07  4603.9  437.16
  4916.7  424.03  4987.3  424.48  5002.7  419.77  5005.5  419.27  5008.7  419.77
  5016.3  424.28  5023.4  424.06  5079.5  422.45  5100.6  423.62  5174.4  422.40
  5335.6  423.79  5343.1  424.24  5353.6  422.67  5385.2  424.05  5437.9  423.11
  5532.8  424.05  5564.9  425.44  5606.6  426.65  5627.7  429.84  5638.2  429.63
  5659.3  431.60  5701.4  433.21  5722.5  432.63  5754.2  434.77  6249.6  441.39
#Mann=9,-1,0
  4223.1    0.05       0  4387.9    0.16       0  4390.2    0.05       0
  4916.7    0.16       0  5002.7    0.07       0  5008.7    0.16       0
  5023.4    0.12       0  5335.6    0.16       0  5564.9    0.05       0
Bank Sta=5002.7,5008.7
Exp/Cntr=0.3,0.1

Type RM Length L Ch R = 1,6011,534,534,534
BEGIN DESCRIPTION:
BRIER CREEK 5.0
END DESCRIPTION:
XS GIS Cut Line= 2
      3486287.52     10487946.89      3484715.66     10487957.73
#Sta/Elev= 30
  4164.4  437.03  4219.8  437.51  4309.8  436.19  4449.8  437.85  4559.8  435.78
  4619.8  432.78  4709.8  434.58  4789.8  432.47  4979.8  423.56  4989.8  421.83
  4996.8  419.12  4999.6  418.62  5002.8  419.12  5019.8  423.51  5023.3  423.34
  5045.9  422.37  5284.3  422.17  5383.2  422.65  5409.8  422.85  5429.8  421.34
  5439.8  422.17  5449.8  424.46  5469.8  426.40  5509.9  434.39  5549.9  431.72
  5649.9  431.65  5679.9  432.65  5689.9  435.24  5699.9  436.17  5736.3  434.35
#Mann=8,-1,0
  4164.4    0.05       0  4789.8    0.16       0  4996.8    0.07       0
  5002.8    0.16       0  5023.3    0.12       0  5045.9    0.16       0
  5284.3    0.12       0  5383.2    0.05       0
Bank Sta=4996.8,5002.8
Exp/Cntr=0.3,0.1

Type RM Length L Ch R = 1,5477,794,794,794
BEGIN DESCRIPTION:
Mapping XS 825173e0
END DESCRIPTION:
XS GIS Cut Line= 4
      3486430.24     10487490.42      3485644.66     10487397.11
      3485358.20     10487457.87      3484750.53     10487575.07
#Sta/Elev= 30
  4052.8  438.44  4173.2  438.85  4373.2  437.54  4715.6  422.88  4776.0  421.13
  4888.8  419.97  4969.2  421.40  4979.4  420.80  4985.4  419.25  4999.9  418.43
  5010.1  418.85  5020.3  421.57  5071.4  420.36  5122.5  421.12  5142.9  420.60
  5173.5  417.98  5204.0  419.54  5214.2  419.12  5221.4  417.59  5224.2  417.09
  5227.4  417.59  5255.0  419.71  5345.6  421.04  5458.7  424.63  5529.9  430.88
  5549.0  434.08  5554.0  433.66  5560.5  434.72  5631.8  434.83  5755.6  436.57
#Mann=5,-1,0
  4052.8    0.05       0  4888.8    0.12       0  5221.4    0.07       0
  5227.4    0.12       0  5345.6    0.05       0
Bank Sta=5221.4,5227.4
Exp/Cntr=0.3,0.1

Type RM Length L Ch R = 1,4683,1058,1058,1058
BEGIN DESCRIPTION:
Mapping XS ad8b6c68
END DESCRIPTION:
XS GIS Cut Line= 4
      3486401.16     10487217.06      3485898.13     10486532.53
      3485120.36     10486940.51      3484839.14     10487437.50
#Sta/Elev= 30
  3866.2  436.79  4177.0  433.04  4377.6  432.73  4528.0  429.63  4716.5  422.26
  4808.9  418.65  4948.3  417.32  4985.4  418.31  5007.4  417.44  5029.5  418.67
  5125.5  416.08  5128.2  415.58  5131.5  416.08  5162.9  418.19  5185.5  417.07
  5377.4  418.81  5393.1  418.60  5400.0  417.21  5422.6  418.68  5459.3  417.46
  5475.7  418.99  5503.4  417.07  5512.9  419.10  5520.2  423.22  5563.9  427.51
  5644.1  430.35  5989.0  434.12  6064.1  433.79  6129.0  431.75  6165.0  433.10
#Mann=5,-1,0
  3866.2    0.05       0  4716.5    0.12       0  5125.5    0.07       0
  5131.5    0.12       0  5520.2    0.05       0
Bank Sta=5125.5,5131.5
Exp/Cntr=0.3,0.1

Type RM Length L Ch R = 1,3625,0,0,0
BEGIN DESCRIPTION:
BRIER CREEK 1.0
END DESCRIPTION:
XS GIS Cut Line= 4
      3486898.52     10486060.78      3485893.32     10485638.91
      3485087.92     10486137.82      3484662.61     10487165.64
#Sta/Elev= 30
  3984.1  422.08  4077.8  418.22  4172.8  418.56  4294.7  416.73  4392.3  416.72
  4598.4  413.77  4773.7  413.86  4906.3  413.63  5011.7  414.28  5121.9  413.42
  5158.0  414.58  5218.1  413.58  5242.0  413.65  5287.4  413.20  5322.7  414.33
  5350.4  413.08  5353.2  412.58  5356.4  413.08  5359.3  414.80  5469.2  414.91
  5484.6  413.75  5579.1  413.48  5606.3  414.36  5628.5  413.47  5918.6  414.41
  5957.4  414.70  6157.8  414.27  6502.0  416.26  6992.9  424.13  7134.0  428.28
#Mann=10,-1,0
  3984.1    0.05       0  4773.7     0.1       0  4906.3    0.05       0
  5011.7     0.1       0  5218.1    0.05       0  5242.0     0.1       0
  5350.4    0.03       0  5356.4     0.1       0  5918.6    0.12       0
  5957.4    0.05       0
Bank Sta=5350.4,5356.4
Exp/Cntr=0.3,0.1

Chan Stop Cuts=-1