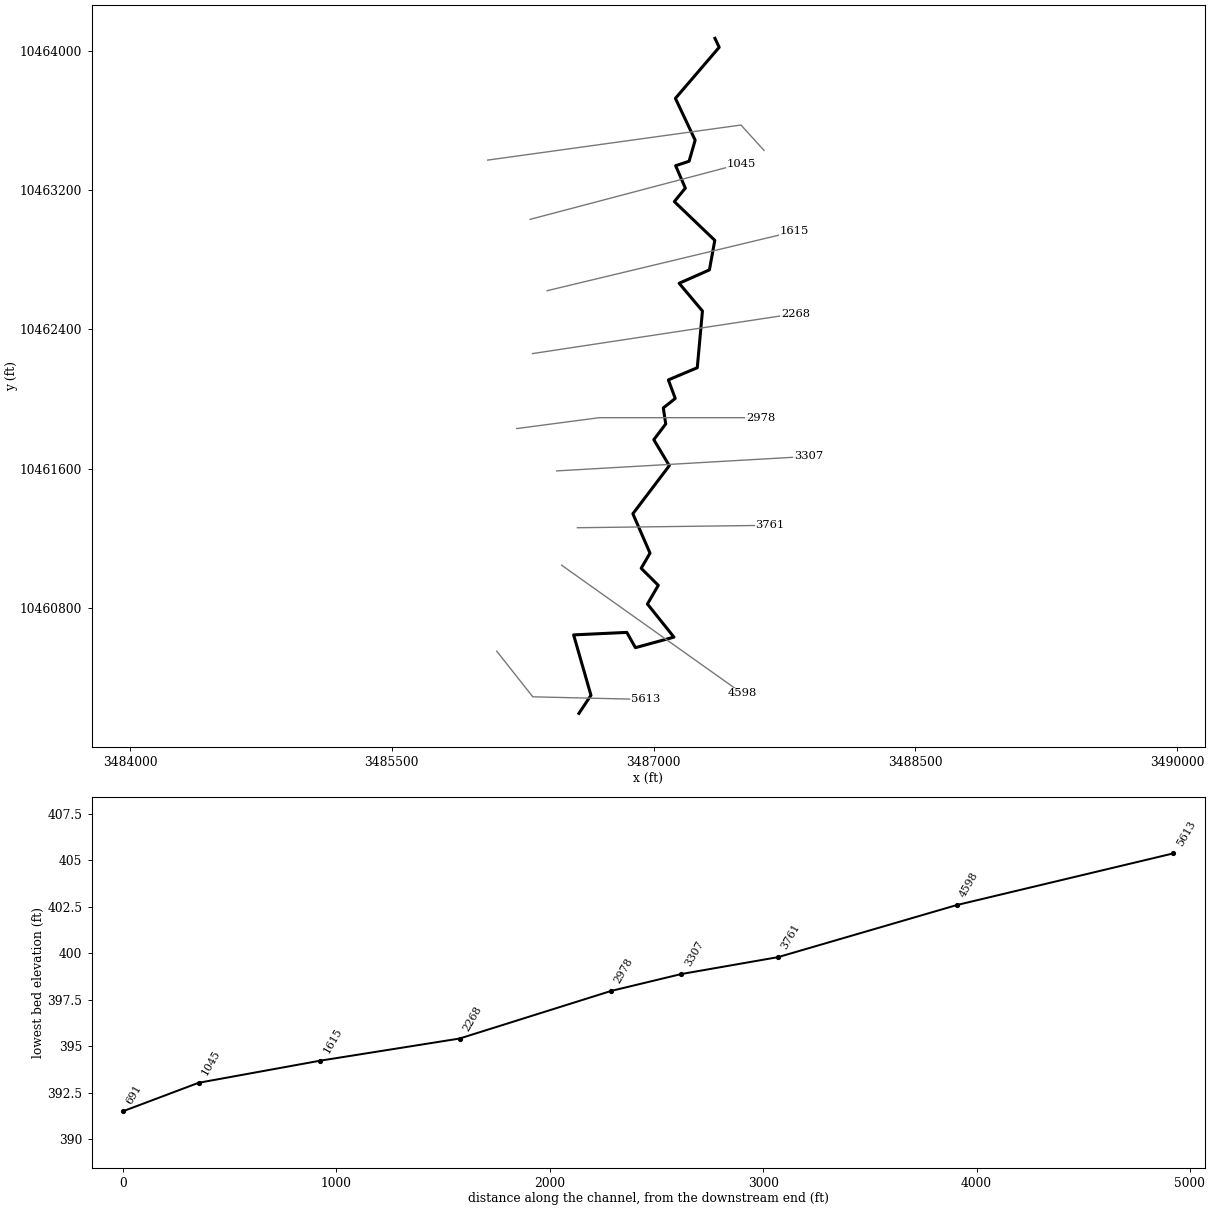
--- BUTLET BRANCH.prj (project) ---

Proj Title=BUTLET BRANCH Base Level Engineering
Current Plan=p01
Default Exp/Contr=0.3,0.1
English Units
Geom File=g01
Flow File=f01
Plan File=p01
BEGIN DESCRIPTION:
BUTLET BRANCH
END DESCRIPTION:

--- BUTLET BRANCH.p01 (plan) ---

Plan Title=Multiple Run
Short Identifier=Multiple
Geom File=g01
Flow File=f01
Subcritical Flow
K Sum by GR= 0
Std Step Tol= 0.01
Critical Tol= 0.01
Num of Std Step Trials= 20
Max Error Tol= 0.3
Flow Tol Ratio= 0.001
Split Flow NTrial= 30
Split Flow Tol= 0.02
Split Flow Ratio= 0.02
Log Output Level= 0
Friction Slope Method= 1
Unsteady Friction Slope Method= 2
Unsteady Bridges Friction Slope Method= 1
Parabolic Critical Depth
Global Vel Dist=  1 , 1 , 1
Global Log Level= 0
CheckData=True
Encroach Param= -1, 0, 0, 0
BEGIN DESCRIPTION:
Multiple Run
END DESCRIPTION:

--- BUTLET BRANCH.f01 (steady flow) ---

Flow Title=Multiple
Number of Profiles=7
Profile Names=10-year,25-year,50-year,1pct_min,100-year,1pct_plu,500-year
River Rch & RM= BUTLET BRANCH,Reach-1,5613
     998    1370    1676    1495    2021    2734    2934
Boundary for River Rch & Prof#=BUTLET BRANCH,Reach-1,1
Up Type=0
Dn Type=3
Dn Slope=0.005
Boundary for River Rch & Prof#=BUTLET BRANCH,Reach-1,2
Up Type=0
Dn Type=3
Dn Slope=0.005
Boundary for River Rch & Prof#=BUTLET BRANCH,Reach-1,3
Up Type=0
Dn Type=3
Dn Slope=0.005
Boundary for River Rch & Prof#=BUTLET BRANCH,Reach-1,4
Up Type=0
Dn Type=3
Dn Slope=0.005
Boundary for River Rch & Prof#=BUTLET BRANCH,Reach-1,5
Up Type=0
Dn Type=3
Dn Slope=0.005
Boundary for River Rch & Prof#=BUTLET BRANCH,Reach-1,6
Up Type=0
Dn Type=3
Dn Slope=0.005
Boundary for River Rch & Prof#=BUTLET BRANCH,Reach-1,7
Up Type=0
Dn Type=3
Dn Slope=0.005

--- BUTLET BRANCH.g01 (geometry) ---

Geom Title=Existing Conditions

River Reach=BUTLET BRANCH,Reach-1
Reach XY= 30
      3486572.54     10460195.29      3486641.64     10460299.11
      3486542.16     10460645.98      3486846.93     10460660.30
      3486896.37     10460572.61      3487117.07     10460633.19
      3486965.23     10460823.31      3487027.42     10460930.68
      3486929.38     10461028.35      3486979.95     10461115.45
      3486881.68     10461341.53      3487090.59     10461617.57
      3487001.68     10461766.96      3487070.06     10461857.18
      3487056.17     10461949.15      3487124.56     10462003.73
      3487085.23     10462110.29      3487250.72     10462180.10
      3487280.46     10462505.82      3487146.97     10462665.07
      3487320.39     10462741.95      3487351.16     10462911.59
      3487119.30     10463134.28      3487182.38     10463211.55
      3487126.84     10463340.28      3487203.90     10463365.92
      3487238.66     10463486.73      3487125.51     10463727.05
      3487376.39     10464020.10      3487352.11     10464071.64

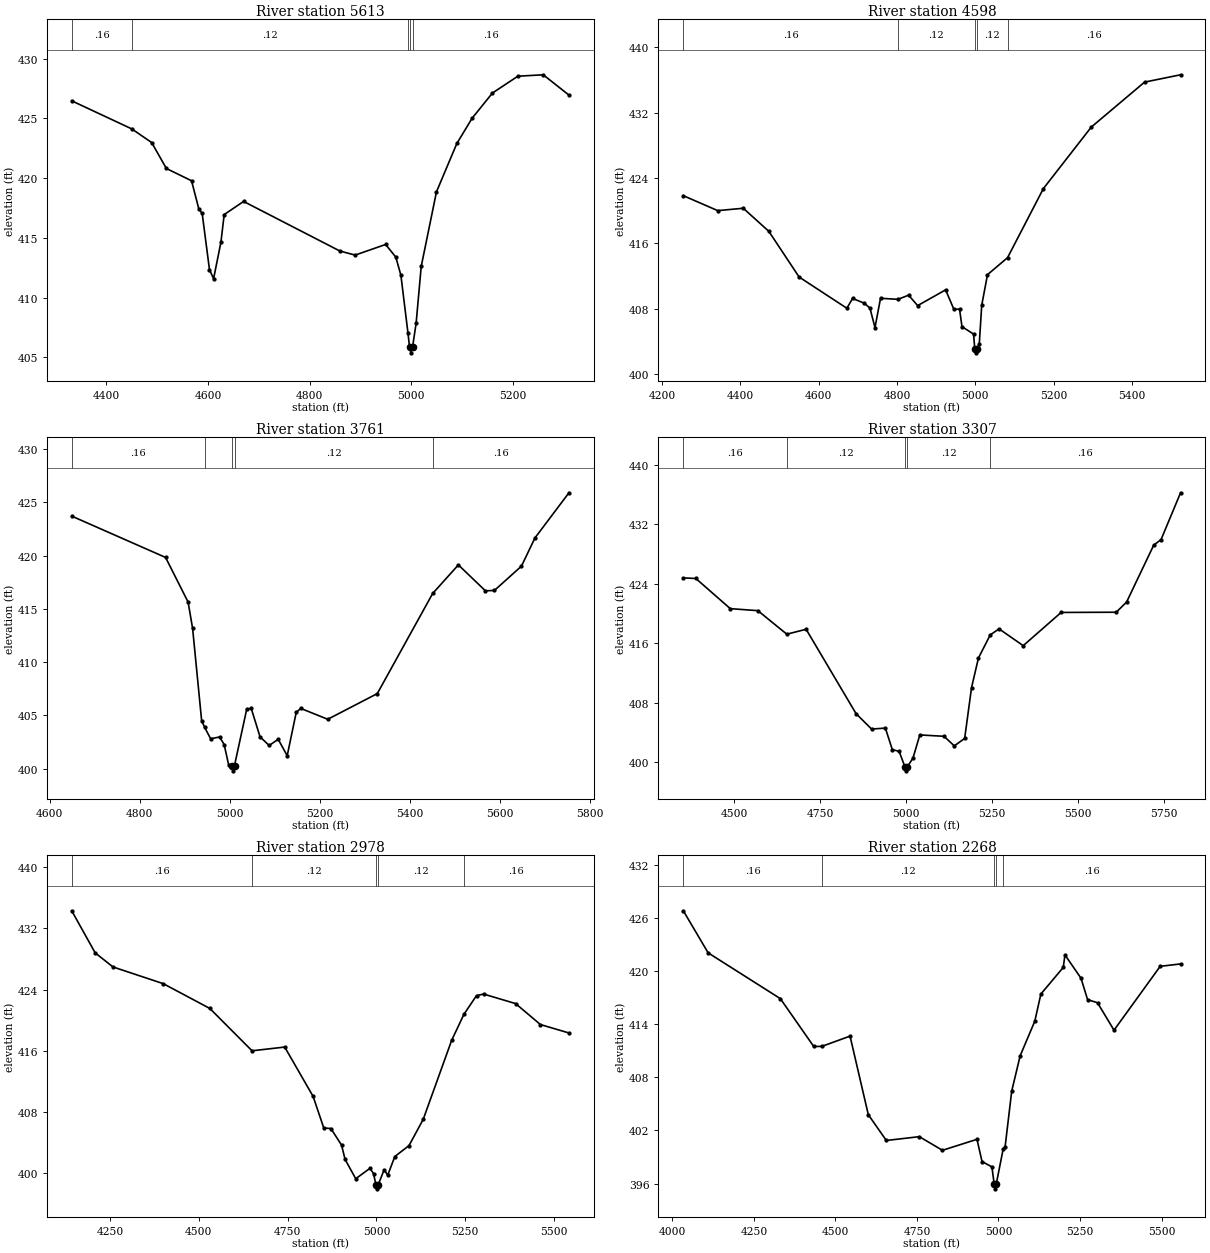
Type RM Length L Ch R = 1,5613,1015,1015,1015
BEGIN DESCRIPTION:
BUTLET BRANCH 10.0
END DESCRIPTION:
XS GIS Cut Line= 3
      3486101.65     10460552.55      3486308.27     10460290.38
      3486952.68     10460275.21
#Sta/Elev= 30
  4331.9  426.46  4450.1  424.11  4489.2  422.97  4518.1  420.80  4567.7  419.77
  4582.2  417.38  4588.6  417.04  4603.0  412.32  4611.1  411.58  4625.5  414.63
  4631.9  416.94  4670.1  418.04  4859.6  413.89  4889.6  413.55  4949.6  414.44
  4969.6  413.38  4979.6  411.87  4993.6  407.01  4996.6  405.87  4999.4  405.37
  5002.6  405.87  5009.6  407.85  5019.6  412.60  5049.6  418.84  5089.7  422.89
  5119.7  425.00  5159.7  427.11  5209.7  428.52  5259.7  428.64  5310.3  426.94
#Mann=5,-1,0
  4331.9    0.16       0  4450.1    0.12       0  4993.6    0.16       0
  4996.6    0.07       0  5002.6    0.16       0
Bank Sta=4996.6,5002.6
Exp/Cntr=0.3,0.1

Type RM Length L Ch R = 1,4598,837,837,837
BEGIN DESCRIPTION:
BUTLET BRANCH 9.0
END DESCRIPTION:
XS GIS Cut Line= 2
      3486473.50     10461046.07      3487507.70     10460310.33
#Sta/Elev= 30
  4254.6  421.83  4342.4  420.00  4407.6  420.29  4472.8  417.47  4550.2  411.87
  4672.0  408.05  4686.7  409.25  4716.2  408.67  4731.0  408.07  4743.8  405.68
  4758.0  409.27  4802.4  409.14  4829.7  409.65  4852.7  408.37  4924.1  410.30
  4945.0  407.94  4959.7  407.93  4965.9  405.79  4995.4  404.89  4998.5  403.09
  5001.3  402.59  5004.5  403.09  5010.1  403.72  5016.3  408.42  5031.0  412.16
  5082.2  414.24  5173.7  422.70  5296.0  430.23  5431.9  435.73  5523.8  436.63
#Mann=5,-1,0
  4254.6    0.16       0  4802.4    0.12       0  4998.5    0.07       0
  5004.5    0.12       0  5082.2    0.16       0
Bank Sta=4998.5,5004.5
Exp/Cntr=0.3,0.1

Type RM Length L Ch R = 1,3761,454,454,454
BEGIN DESCRIPTION:
BUTLET BRANCH 8.0
END DESCRIPTION:
XS GIS Cut Line= 2
      3486563.77     10461261.32      3487667.58     10461275.21
#Sta/Elev= 30
  4648.9  423.70  4857.3  419.82  4907.3  415.63  4917.3  413.16  4937.3  404.51
  4944.2  403.86  4957.3  402.80  4977.3  402.97  4987.3  402.26  4997.3  400.35
  5004.3  400.29  5007.0  399.79  5010.3  400.29  5037.3  405.55  5047.3  405.67
  5067.0  402.98  5087.3  402.17  5107.3  402.75  5127.3  401.21  5147.3  405.27
  5157.3  405.65  5217.3  404.63  5327.3  407.04  5450.3  416.44  5507.3  419.12
  5567.3  416.69  5587.3  416.72  5647.3  419.00  5677.3  421.65  5752.8  425.89
#Mann=5,-1,0
  4648.9    0.16       0  4944.2    0.12       0  5004.3    0.07       0
  5010.3    0.12       0  5450.3    0.16       0
Bank Sta=5004.3,5010.3
Exp/Cntr=0.3,0.1

Type RM Length L Ch R = 1,3307,329,329,329
BEGIN DESCRIPTION:
BUTLET BRANCH 7.0
END DESCRIPTION:
XS GIS Cut Line= 2
      3486445.80     10461587.71      3487888.60     10461670.95
#Sta/Elev= 30
  4352.9  424.79  4389.3  424.71  4489.4  420.66  4569.6  420.39  4653.7  417.23
  4709.8  417.89  4855.1  406.55  4900.1  404.49  4940.2  404.62  4960.2  401.74
  4980.2  401.49  4997.3  399.38  5000.0  398.88  5003.3  399.38  5020.3  400.58
  5040.3  403.70  5110.5  403.52  5140.5  402.23  5170.6  403.23  5190.6  410.05
  5210.6  414.02  5245.0  417.14  5270.7  417.94  5340.8  415.69  5451.0  420.15
  5611.3  420.18  5641.3  421.55  5719.9  429.17  5741.5  429.94  5798.1  436.22
#Mann=5,-1,0
  4352.9    0.16       0  4653.7    0.12       0  4997.3    0.07       0
  5003.3    0.12       0  5245.0    0.16       0
Bank Sta=4997.3,5003.3
Exp/Cntr=0.3,0.1

Type RM Length L Ch R = 1,2978,710,710,710
BEGIN DESCRIPTION:
BUTLET BRANCH 6.0
END DESCRIPTION:
XS GIS Cut Line= 3
      3486216.56     10461830.76      3486688.81     10461893.27
      3487612.44     10461893.27
#Sta/Elev= 30
  4142.2  434.29  4208.3  428.79  4258.5  426.95  4400.0  424.77  4531.1  421.53
  4649.9  416.00  4741.9  416.49  4821.9  410.04  4851.9  405.92  4871.9  405.85
  4901.9  403.69  4911.9  401.81  4941.9  399.29  4981.9  400.65  4991.9  399.97
  4998.9  398.47  5001.6  397.97  5004.9  398.47  5021.9  400.47  5031.9  399.74
  5051.9  402.19  5091.9  403.62  5131.9  407.05  5211.9  417.36  5246.3  420.75
  5281.9  423.21  5301.9  423.41  5391.9  422.17  5461.9  419.43  5542.2  418.33
#Mann=5,-1,0
  4142.2    0.16       0  4649.9    0.12       0  4998.9    0.07       0
  5004.9    0.12       0  5246.3    0.16       0
Bank Sta=4998.9,5004.9
Exp/Cntr=0.3,0.1

Type RM Length L Ch R = 1,2268,653,653,653
BEGIN DESCRIPTION:
BUTLET BRANCH 5.0
END DESCRIPTION:
XS GIS Cut Line= 2
      3486306.85     10462261.32      3487813.82     10462490.49
#Sta/Elev= 30
  4033.9  426.80  4110.0  422.05  4331.4  416.88  4433.7  411.48  4458.4  411.49
  4545.0  412.65  4601.0  403.78  4656.2  400.87  4757.4  401.30  4828.2  399.76
  4934.2  401.00  4949.6  398.49  4979.9  397.89  4987.0  395.91  4989.8  395.41
  4993.0  395.91  5014.6  399.94  5020.4  400.17  5040.6  406.44  5066.4  410.42
  5111.4  414.34  5130.0  417.40  5198.7  420.41  5203.8  421.82  5253.0  419.19
  5273.2  416.77  5303.6  416.42  5354.2  413.32  5495.8  420.53  5558.2  420.80
#Mann=5,-1,0
  4033.9    0.16       0  4458.4    0.12       0  4987.0    0.07       0
  4993.0    0.12       0  5014.6    0.16       0
Bank Sta=4987,4993
Exp/Cntr=0.3,0.1

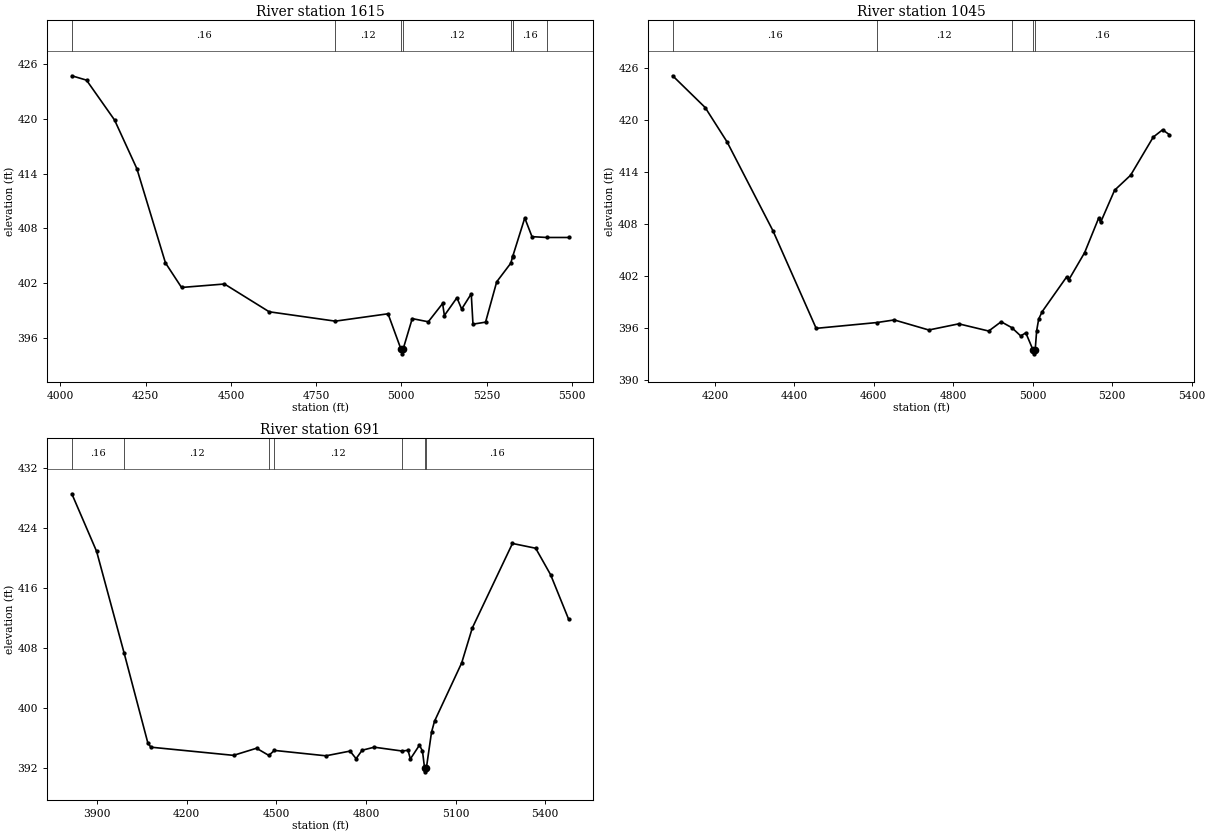
Type RM Length L Ch R = 1,1615,570,570,570
BEGIN DESCRIPTION:
BUTLET BRANCH 3.0
END DESCRIPTION:
XS GIS Cut Line= 2
      3486390.18     10462622.43      3487806.88     10462962.72
#Sta/Elev= 30
  4033.3  424.76  4076.4  424.28  4158.7  419.90  4224.1  414.56  4308.0  404.21
  4355.2  401.51  4481.1  401.89  4612.2  398.84  4806.3  397.81  4960.9  398.62
  4999.0  394.72  5001.8  394.22  5005.0  394.72  5031.9  398.09  5079.0  397.74
  5121.0  399.75  5126.2  398.43  5163.0  400.38  5176.9  399.14  5205.0  400.81
  5210.1  397.48  5247.0  397.70  5279.7  402.13  5320.9  404.17  5326.1  404.84
  5327.4  405.01  5362.0  409.14  5383.2  407.09  5426.7  407.00  5490.3  407.00
#Mann=8,-1,0
  4033.3    0.16       0  4806.3    0.12       0  4999.0    0.07       0
  5005.0    0.12       0  5320.9    0.16       0  5326.1    0.12       0
  5327.4    0.16       0  5426.7    0.12       0
Bank Sta=4999,5005
Exp/Cntr=0.3,0.1

Type RM Length L Ch R = 1,1045,354,354,354
BEGIN DESCRIPTION:
BUTLET BRANCH 2.0
END DESCRIPTION:
XS GIS Cut Line= 2
      3486293.02     10463032.17      3487501.30     10463351.60
#Sta/Elev= 30
  4093.9  425.10  4175.7  421.44  4230.7  417.48  4346.3  407.22  4455.0  395.97
  4607.9  396.64  4651.5  396.94  4738.4  395.78  4813.8  396.49  4889.1  395.66
  4920.4  396.73  4947.3  396.05  4969.6  395.10  4982.5  395.45  5000.2  393.53
  5002.9  393.03  5006.2  393.53  5009.8  395.70  5015.0  397.06  5023.9  397.91
  5085.2  401.90  5090.3  401.54  5130.6  404.71  5165.7  408.67  5170.8  408.20
  5205.9  411.90  5246.2  413.63  5303.2  418.03  5326.7  418.87  5343.7  418.31
#Mann=5,-1,0
  4093.9    0.16       0  4607.9    0.12       0  4947.3    0.16       0
  5000.2    0.07       0  5006.2    0.16       0
Bank Sta=5000.2,5006.2
Exp/Cntr=0.3,0.1

Type RM Length L Ch R = 1,691,0,0,0
BEGIN DESCRIPTION:
BUTLET BRANCH 1.0
END DESCRIPTION:
XS GIS Cut Line= 3
      3486049.91     10463372.43      3487501.31     10463573.82
      3487633.27     10463427.97
#Sta/Elev= 30
  3815.8  428.61  3898.8  420.92  3991.0  407.33  4070.4  395.33  4080.5  394.79
  4356.9  393.70  4433.9  394.65  4475.1  393.69  4493.6  394.36  4666.1  393.64
  4746.8  394.27  4767.0  393.26  4787.2  394.38  4827.6  394.79  4920.6  394.28
  4940.8  394.37  4948.7  393.22  4979.0  395.06  4989.1  394.29  4996.2  392.00
  4999.0  391.50  5002.2  392.00  5019.4  396.78  5029.5  398.26  5120.4  406.04
  5155.9  410.70  5290.3  421.98  5368.0  421.34  5418.0  417.80  5477.8  411.91
#Mann=7,-1,0
  3815.8    0.16       0  3991.0    0.12       0  4475.1    0.16       0
  4493.6    0.12       0  4920.6    0.16       0  4996.2    0.07       0
  5002.2    0.16       0
Bank Sta=4996.2,5002.2
Exp/Cntr=0.3,0.1

Chan Stop Cuts=-1