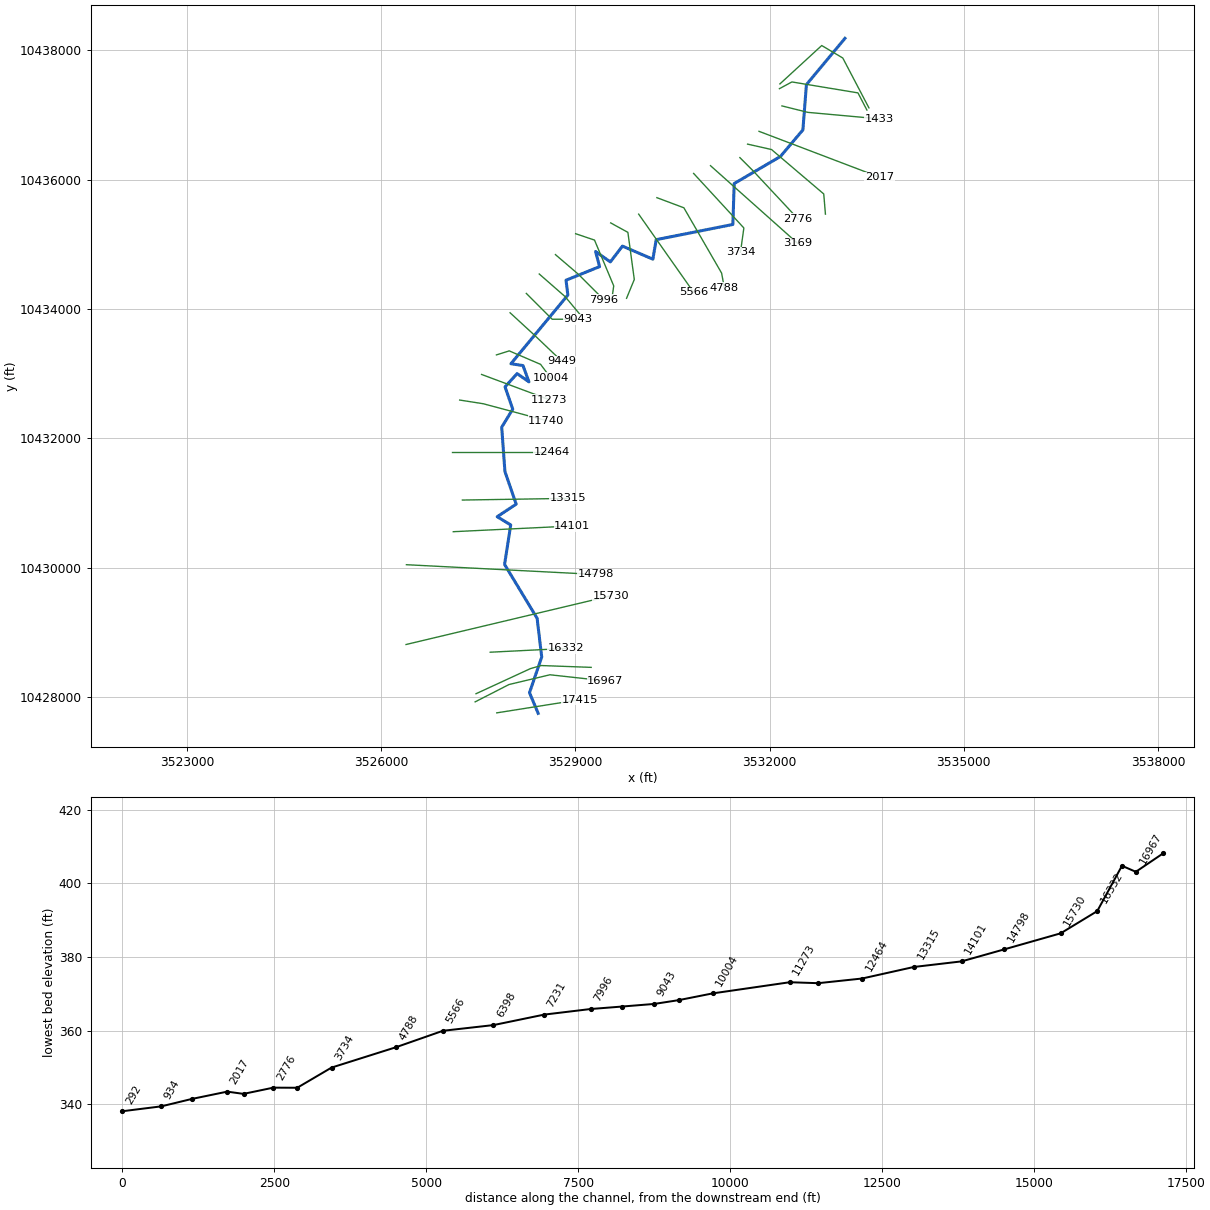
--- COLES BRANCH.prj (project) ---

Proj Title=COLES BRANCH Base Level Engineering
Current Plan=p01
Default Exp/Contr=0.3,0.1
English Units
Geom File=g01
Flow File=f01
Plan File=p01
Y Axis Title=Elevation
X Axis Title(PF)=Main Channel Distance
X Axis Title(XS)=Station
BEGIN DESCRIPTION:
COLES BRANCH
END DESCRIPTION:
DSS Export Rating Curves= 0
DSS Export Rating Curve Sorted= 0
DSS Export Volume Flow Curves= 0
DXF OffsetX= 0
DXF OffsetY= 0
DXF ScaleX= 1
DXF ScaleY= 10

--- COLES BRANCH.p01 (plan) ---

Plan Title=Multiple Run
Short Identifier=Multiple
Geom File=g01
Flow File=f01
Subcritical Flow
K Sum by GR= 0
Std Step Tol= 0.01
Critical Tol= 0.01
Num of Std Step Trials= 20
Max Error Tol= 0.3
Flow Tol Ratio= 0.001
Split Flow NTrial= 30
Split Flow Tol= 0.02
Split Flow Ratio= 0.02
Log Output Level= 0
Friction Slope Method= 1
Unsteady Friction Slope Method= 2
Unsteady Bridges Friction Slope Method= 1
Parabolic Critical Depth
Global Vel Dist=  1 , 1 , 1
Global Log Level= 0
CheckData=True
Encroach Param= -1, 0, 0, 0
BEGIN DESCRIPTION:
Multiple Run
END DESCRIPTION:

--- COLES BRANCH.f01 (steady flow) ---

Flow Title=Multiple
Program Version=4.10
Number of Profiles= 7
Profile Names=10-year,25-year,50-year,1pct_min,100-year,1pct_plu,500-year
River Rch & RM=COLES BRANCH,Reach-1         ,17415
     837    1169    1449    1315    1778    2405    2668
River Rch & RM=COLES BRANCH,Reach-1         ,16332
    1624    2341    2962    2735    3699    5003    5756
River Rch & RM=COLES BRANCH,Reach-1         ,9449
    1902    2743    3468    3197    4323    5847    6705
Boundary for River Rch & Prof#=COLES BRANCH,Reach-1         , 1
Up Type= 0
Dn Type= 3
Dn Slope=0.01
Boundary for River Rch & Prof#=COLES BRANCH,Reach-1         , 2
Up Type= 0
Dn Type= 3
Dn Slope=0.01
Boundary for River Rch & Prof#=COLES BRANCH,Reach-1         , 3
Up Type= 0
Dn Type= 3
Dn Slope=0.01
Boundary for River Rch & Prof#=COLES BRANCH,Reach-1         , 4
Up Type= 0
Dn Type= 3
Dn Slope=0.01
Boundary for River Rch & Prof#=COLES BRANCH,Reach-1         , 5
Up Type= 0
Dn Type= 3
Dn Slope=0.01
Boundary for River Rch & Prof#=COLES BRANCH,Reach-1         , 6
Up Type= 0
Dn Type= 3
Dn Slope=0.01
Boundary for River Rch & Prof#=COLES BRANCH,Reach-1         , 7
Up Type= 0
Dn Type= 3
Dn Slope=0.01
DSS Import GetInterval= 0
DSS Import GetPeak= 0
DSS Import FillOption= 0

--- COLES BRANCH.g01 (geometry) ---

Geom Title=Existing Conditions
Program Version=4.10

River Reach=COLES BRANCH    ,Reach-1
Reach XY= 30
      3528425.83      10427745.7      3528291.64     10428065.81
      3528480.32     10428617.01      3528409.41     10429216.24
      3527906.38      10430049.2       3528001.6     10430659.99
      3527792.31     10430787.48      3528085.88     10430981.99
      3527912.15     10431486.04      3527862.11     10432171.64
      3528032.65     10432451.58      3527913.98     10432795.64
      3528099.87     10433000.76      3528283.24     10432873.81
      3528191.01     10433125.54      3528004.69     10433153.58
      3528884.02     10434215.43      3528855.89     10434445.65
      3529374.73     10434655.95      3529312.68     10434889.42
       3529540.8     10434728.46      3529727.56     10434972.98
      3530197.66     10434770.83      3530249.17     10435072.69
      3531433.53     10435307.67      3531454.27      10435940.8
      3532168.68     10436359.46      3532515.65     10436770.67
      3532569.98     10437470.92      3533165.62      10438186.7

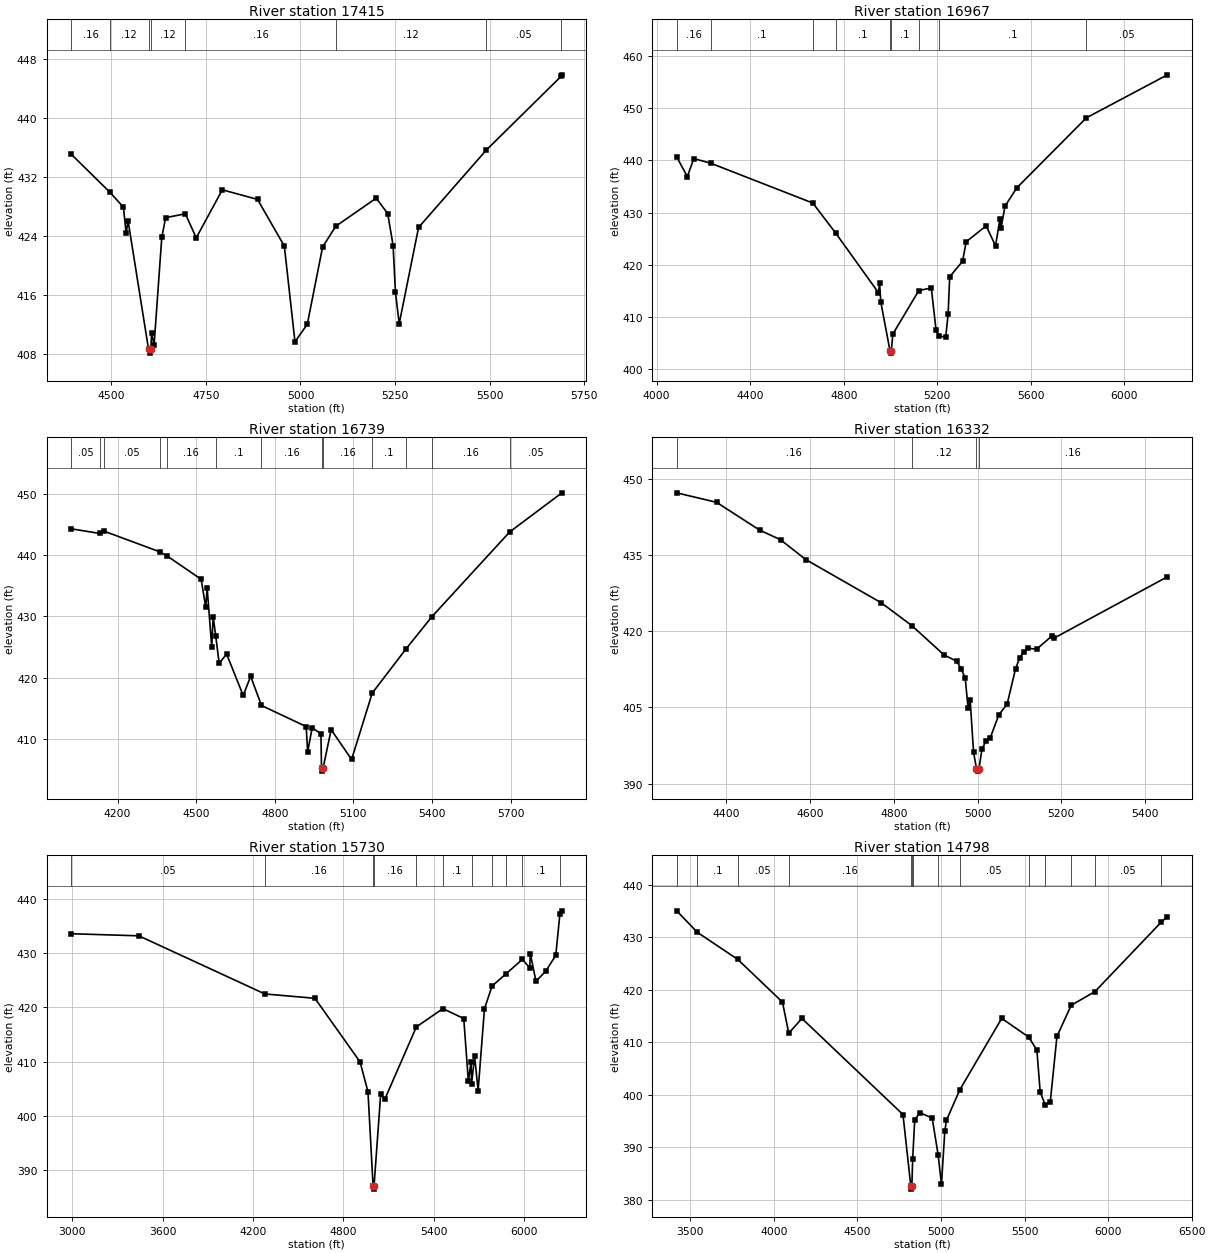
Type RM Length L Ch R = 1 ,17415   ,448,448,448
BEGIN DESCRIPTION:
COLES BRANCH 34.0
END DESCRIPTION:
XS GIS Cut Line= 2
       3527785.7     10427753.58       3529066.8     10427956.68
#Sta/Elev= 30
  4393.9  435.08  4496.8  429.89    4532  427.89  4539.1  424.35  4544.2  426.07
  4598.4  408.61  4601.2  408.11  4604.4  408.61  4606.5  410.85    4613   409.2
  4633.3  423.79  4643.4  426.47  4695.6     427  4724.4  423.74  4793.4  430.25
  4886.4  428.95  4957.3  422.62  4985.4  409.64    5018  412.03  5058.5  422.51
  5093.4  425.32  5200.2  429.12  5230.6  427.02  5244.8   422.7  5250.9  416.38
    5261  412.12  5312.1  425.15  5491.2  435.64    5689  445.64    5691  445.84
#Mann= 8 ,-1 , 0
  4393.9     .16       0  4496.8     .12       0  4598.4     .07       0
  4604.4     .12       0  4695.6     .16       0  5093.4     .12       0
  5491.2     .05       0    5689     .16       0
Bank Sta=4598.4,4604.4
XS Rating Curve= 0 ,0
Exp/Cntr=0.3,0.1

Type RM Length L Ch R = 1 ,16967   ,228,228,228
BEGIN DESCRIPTION:
COLES BRANCH 32.0
END DESCRIPTION:
XS GIS Cut Line= 4
      3527451.34      10427923.5      3527974.82     10428191.75
      3528607.63     10428342.79      3529462.84     10428248.37
#Sta/Elev= 30
  4085.6  440.66  4131.1  436.89  4158.9  440.34  4232.5  439.43  4667.9  431.83
  4766.8  426.02  4948.4   414.7  4953.5  416.45  4958.9  412.87  4997.8  403.62
  5000.5  403.12  5003.8  403.62  5010.3  406.78  5121.4  415.09  5174.8  415.59
  5195.3  407.45  5209.2  406.37  5236.5  406.19  5246.8  410.62  5253.4  417.72
  5308.4  420.68  5324.1  424.43  5409.4  427.46  5449.6  423.64  5468.2  428.75
  5473.2  427.08  5489.9  431.21  5540.2  434.72    5838  448.13  6184.8  456.36
#Mann= 9 ,-1 , 0
  4085.6     .16       0  4232.5      .1       0  4667.9     .12       0
  4766.8      .1       0  4997.8     .07       0  5003.8      .1       0
  5121.4     .12       0  5209.2      .1       0    5838     .05       0
Bank Sta=4997.8,5003.8
XS Rating Curve= 0 ,0
Exp/Cntr=0.3,0.1

Type RM Length L Ch R = 1 ,16739   ,407,407,407
BEGIN DESCRIPTION:
Mapping XS 7d42c5c0
END DESCRIPTION:
XS GIS Cut Line= 4
      3527465.28      10428049.4      3528305.11     10428437.85
      3528472.21     10428485.59      3529244.79     10428457.38
#Sta/Elev= 30
  4023.2  444.28  4132.8  443.52    4147  443.92  4360.9  440.53  4388.4  439.87
  4518.9  436.05  4536.4   431.5  4541.9   434.6  4559.3  425.03  4564.8  429.97
  4574.8  426.73  4587.7  422.34  4616.2  423.85  4679.4  417.09  4707.9  420.22
  4749.1  415.46  4919.7  412.02  4925.3   407.9  4942.7  411.84    4976  410.83
  4978.2  405.25  4980.9  404.75  4984.2  405.25    5015  411.52    5093  406.65
  5171.7  417.48  5300.1  424.66  5399.1  429.93  5696.2  443.77  5895.4  450.15
#Mann= 13 ,-1 , 0
  4023.2     .05       0  4132.8     .16       0    4147     .05       0
  4360.9      .1       0  4388.4     .16       0  4574.8      .1       0
  4749.1     .16       0  4978.2     .07       0  4984.2     .16       0
  5171.7      .1       0  5300.1     .05       0  5399.1     .16       0
  5696.2     .05       0
Bank Sta=4978.2,4984.2
XS Rating Curve= 0 ,0
Exp/Cntr=0.3,0.1

Type RM Length L Ch R = 1 ,16332   ,602,602,602
BEGIN DESCRIPTION:
Mapping XS d69090bd
END DESCRIPTION:
XS GIS Cut Line= 2
      3527684.47     10428691.75      3528854.11     10428750.34
#Sta/Elev= 30
  4282.1  447.19  4377.3  445.32    4480  439.86    4530  437.95  4590.1  434.07
  4770.3  425.56  4843.3  421.07  4920.5  415.28  4950.6  414.06  4960.6  412.63
  4970.6   410.8  4977.5  404.85  4982.5  406.39  4990.6  396.14  4997.6  392.95
  5000.4  392.45  5003.6  392.95  5010.6  396.76  5020.7  398.47  5030.7  399.05
  5050.7   403.5  5070.7  405.63  5090.7  412.56  5100.8  414.76  5110.8  415.97
  5120.8  416.64  5140.8  416.42  5177.6  419.03  5182.6   418.6  5453.2  430.68
#Mann= 4 ,-1 , 0
  4282.1     .16       0  4843.3     .12       0  4997.6     .07       0
  5003.6     .16       0
Bank Sta=4997.6,5003.6
XS Rating Curve= 0 ,0
Exp/Cntr=0.3,0.1

Type RM Length L Ch R = 1 ,15730   ,932,932,932
BEGIN DESCRIPTION:
COLES BRANCH 30.0
END DESCRIPTION:
XS GIS Cut Line= 2
      3526384.65     10428810.87      3529556.58     10429566.09
#Sta/Elev= 30
  2991.9  433.61  3441.6  433.22  4278.8  422.48  4611.3  421.68  4911.5  409.92
  4963.9  404.39  4997.9  386.92  5000.6  386.42  5003.9  386.92  5048.2  403.92
    5076  403.05  5285.3  416.39  5461.8  419.77  5600.3  417.94  5631.1  406.32
  5648.5  409.96  5652.2   405.8  5672.2  410.99  5695.8  404.64  5737.9  419.76
  5788.5  423.94  5877.9  426.13  5989.8  428.86  6038.1  427.33  6043.2  429.84
  6080.2  424.82  6145.1  426.69  6211.8  429.61  6239.3   437.3  6252.5  437.84
#Mann= 11 ,-1 , 0
  2991.9     .05       0  4278.8     .16       0  4997.9     .07       0
  5003.9     .16       0  5285.3     .05       0  5461.8      .1       0
  5652.2     .05       0  5788.5      .1       0  5877.9     .05       0
  5989.8      .1       0  6239.3     .05       0
Bank Sta=4997.9,5003.9
XS Rating Curve= 0 ,0
Exp/Cntr=0.3,0.1

Type RM Length L Ch R = 1 ,14798   ,697,697,697
BEGIN DESCRIPTION:
COLES BRANCH 28.0
END DESCRIPTION:
XS GIS Cut Line= 2
       3526389.9     10430045.25      3529322.21     10429894.21
#Sta/Elev= 30
  3418.6     435  3541.5  430.93  3784.6  425.74  4051.6  417.63  4089.1  411.72
    4168  414.52  4772.6  396.24  4819.7  382.55  4822.4  382.05  4825.7  382.55
  4830.6  387.79  4842.7  395.17  4872.7  396.61  4947.3  395.57  4982.9  388.59
  5002.9  382.97  5022.9  393.07  5032.9  395.16  5112.7  400.96  5363.4  414.53
  5524.8  410.98  5573.7  408.53  5593.7  400.53  5623.9  398.06  5653.8  398.57
  5693.8   411.1  5779.2  417.03  5921.4  419.64  6318.1  432.85  6354.8  433.92
#Mann= 14 ,-1 , 0
  3418.6     .16       0  3541.5      .1       0  3784.6     .05       0
  4089.1     .16       0  4819.7     .07       0  4825.7     .16       0
  4830.6     .12       0  4982.9     .16       0  5112.7     .05       0
  5524.8     .16       0  5623.9     .05       0  5779.2     .16       0
  5921.4     .05       0  6318.1      .1       0
Bank Sta=4819.7,4825.7
XS Rating Curve= 0 ,0
Exp/Cntr=0.3,0.1

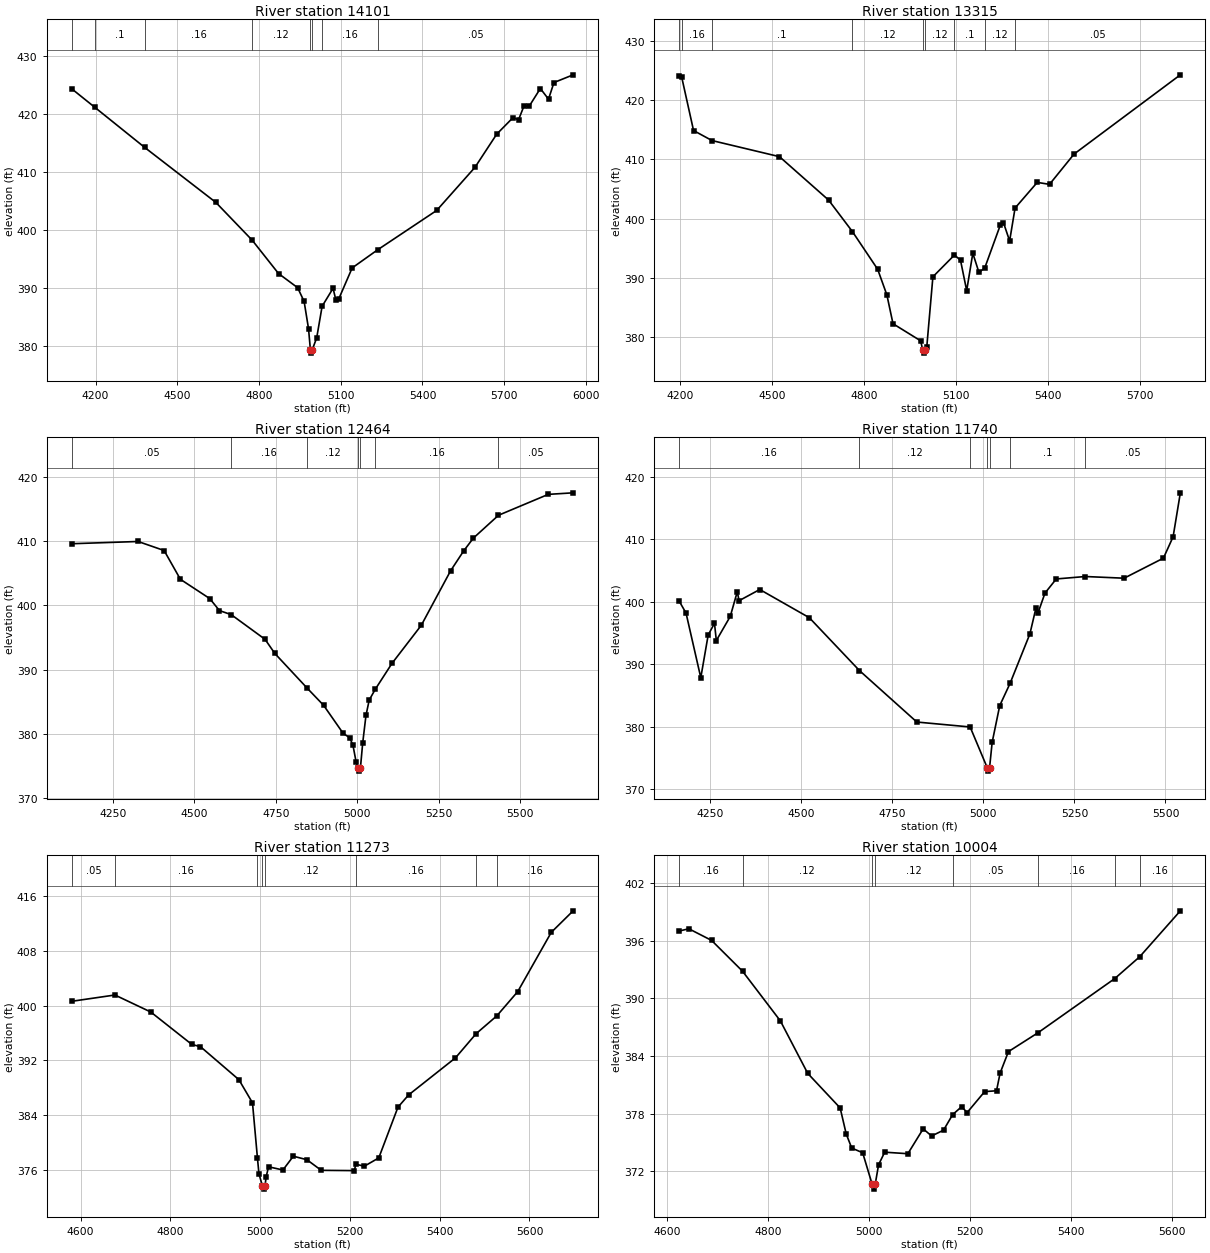
Type RM Length L Ch R = 1 ,14101   ,786,786,786
BEGIN DESCRIPTION:
COLES BRANCH 26.0
END DESCRIPTION:
XS GIS Cut Line= 2
      3527113.81     10430555.66      3528952.38     10430644.21
#Sta/Elev= 30
  4112.4  424.38  4197.3  421.18    4380  414.28  4641.3   404.8    4775  398.27
  4871.6  392.53  4941.7  390.09  4965.5  387.72  4981.7  383.02  4988.7  379.31
  4991.5  378.81  4994.7  379.31  5011.7  381.45  5031.6  386.89  5071.8  389.99
  5081.8  388.01  5091.8  388.06  5141.9   393.5  5235.6  396.63  5452.2  403.41
  5592.7  410.84  5672.5  416.56  5732.6  419.42  5752.6  419.04  5772.6  421.41
  5791.7  421.37  5832.7  424.43  5862.7   422.6  5882.7  425.46  5953.1  426.79
#Mann= 8 ,-1 , 0
  4112.4     .05       0  4197.3      .1       0    4380     .16       0
    4775     .12       0  4988.7     .07       0  4994.7     .12       0
  5031.6     .16       0  5235.6     .05       0
Bank Sta=4988.7,4994.7
XS Rating Curve= 0 ,0
Exp/Cntr=0.3,0.1

Type RM Length L Ch R = 1 ,13315   ,851,851,851
BEGIN DESCRIPTION:
COLES BRANCH 25.0
END DESCRIPTION:
XS GIS Cut Line= 2
      3527254.47     10431045.25      3528888.47     10431071.27
#Sta/Elev= 30
  4195.9  423.98  4204.8  423.88  4243.5  414.85  4303.6  413.16  4523.6  410.44
  4683.6  403.12  4761.4  397.79  4843.6  391.44  4873.6  387.11  4893.6  382.25
  4983.6  379.37  4990.6  377.79  4993.4  377.29  4996.6  377.79  5003.6   378.3
  5023.6  390.17  5093.9  393.85  5113.6  392.96  5133.7  387.84  5153.7  394.14
  5173.7  390.91  5192.6  391.66  5243.7  398.95  5253.7  399.29  5273.7  396.22
  5291.4  401.77  5363.7   406.1  5403.7  405.77  5483.7  410.88  5830.1  424.25
#Mann= 9 ,-1 , 0
  4195.9     .05       0  4204.8     .16       0  4303.6      .1       0
  4761.4     .12       0  4990.6     .07       0  4996.6     .12       0
  5093.9      .1       0  5192.6     .12       0  5291.4     .05       0
Bank Sta=4990.6,4996.6
XS Rating Curve= 0 ,0
Exp/Cntr=0.3,0.1

Type RM Length L Ch R = 1 ,12464   ,724,724,724
BEGIN DESCRIPTION:
COLES BRANCH 23.0
END DESCRIPTION:
XS GIS Cut Line= 2
      3527098.27     10431790.04      3528638.47     10431790.04
#Sta/Elev= 30
  4123.2  409.63    4327  409.98    4407  408.57    4457  404.08    4547  401.08
    4577   399.2  4613.1  398.57    4717  394.72    4747  392.52  4847.4  387.05
    4897  384.42    4957  380.05    4977  379.37    4987  378.21    4997  375.52
    5004  374.66  5006.8  374.16    5010  374.66    5017  378.56    5027  382.84
    5037  385.25    5056  386.96    5107  390.97    5197  396.91    5287  405.41
    5327   408.5    5357  410.51  5434.1  414.07    5587  417.33  5663.4  417.57
#Mann= 7 ,-1 , 0
  4123.2     .05       0  4613.1     .16       0  4847.4     .12       0
    5004     .07       0    5010     .12       0    5056     .16       0
  5434.1     .05       0
Bank Sta=5004,5010
XS Rating Curve= 0 ,0
Exp/Cntr=0.3,0.1

Type RM Length L Ch R = 1 ,11740   ,467,467,467
BEGIN DESCRIPTION:
COLES BRANCH 22.0
END DESCRIPTION:
XS GIS Cut Line= 3
      3527212.81     10432592.13       3527577.4     10432534.83
      3528551.32     10432274.42
#Sta/Elev= 30
  4163.7  400.18  4183.2  398.19  4223.7  387.85    4244  394.69  4261.3  396.56
  4266.4   393.8  4304.7  397.67  4323.9  401.61  4328.9  400.18  4385.7  401.97
  4521.7  397.46  4659.5  388.99  4817.1  380.75  4963.5  379.96  5010.8  373.39
  5013.5  372.89  5016.8  373.39    5024   377.5  5044.8  383.38  5073.1  386.93
  5127.7  394.87  5144.2  398.98  5149.4  398.13  5169.1   401.4  5200.1  403.66
  5279.9  404.05  5386.4  403.78  5494.4  406.99    5521  410.41  5540.9  417.45
#Mann= 7 ,-1 , 0
  4163.7     .16       0  4659.5     .12       0  4963.5     .16       0
  5010.8     .07       0  5016.8     .16       0  5073.1      .1       0
  5279.9     .05       0
Bank Sta=5010.8,5016.8
XS Rating Curve= 0 ,0
Exp/Cntr=0.3,0.1

Type RM Length L Ch R = 1 ,11273   ,1269,1269,1269
BEGIN DESCRIPTION:
COLES BRANCH 20.0
END DESCRIPTION:
XS GIS Cut Line= 2
      3527551.38     10432987.95      3528597.71     10432597.53
#Sta/Elev= 30
  4580.4  400.64  4676.6  401.56  4756.5  399.07    4848  394.32  4867.1     394
  4952.7  389.17    4983  385.78  4994.1  377.65  4997.4  375.39    5005  373.65
  5007.7  373.15    5011  373.65  5013.3  374.92  5018.8  376.42  5050.8  375.95
    5074  377.97  5104.3  377.45  5136.2   375.9  5209.5  375.86  5213.5  376.78
  5232.3  376.51  5264.3  377.72    5307  385.14  5330.8  386.94  5435.1  392.36
  5481.1   395.9  5527.1   398.5  5573.8  402.06  5648.5  410.73  5697.2  413.88
#Mann= 8 ,-1 , 0
  4580.4     .05       0  4676.6     .16       0  4994.1     .12       0
    5005     .07       0    5011     .12       0  5213.5     .16       0
  5481.1      .1       0  5527.1     .16       0
Bank Sta=5005,5011
XS Rating Curve= 0 ,0
Exp/Cntr=0.3,0.1

Type RM Length L Ch R = 1 ,10004   ,555,555,555
BEGIN DESCRIPTION:
COLES BRANCH 19.0
END DESCRIPTION:
XS GIS Cut Line= 4
      3527780.53     10433290.04      3527978.44     10433352.54
      3528462.81     10433144.21      3528617.78     10432937.58
#Sta/Elev= 30
  4622.9  397.01  4642.5  397.25  4687.5  396.04  4748.8  392.83  4823.8  387.65
    4878  382.18  4942.2  378.58  4954.2  375.87  4965.1   374.4  4986.8  373.91
  5005.6  370.62  5008.4  370.12  5011.6  370.62  5018.3  372.66  5030.4  373.97
  5076.3  373.81  5106.6   376.4  5123.3  375.66  5146.9  376.26  5165.1  377.89
  5182.8  378.71  5193.7   378.1  5228.4  380.28  5251.9  380.37    5259  382.21
  5275.5  384.45  5334.2  386.42  5486.1  392.06  5535.6  394.34    5616  399.12
#Mann= 8 ,-1 , 0
  4622.9     .16       0  4748.8     .12       0  5005.6     .07       0
  5011.6     .12       0  5165.1     .05       0  5334.2     .16       0
  5486.1     .05       0  5535.6     .16       0
Bank Sta=5005.6,5011.6
XS Rating Curve= 0 ,0
Exp/Cntr=0.3,0.1

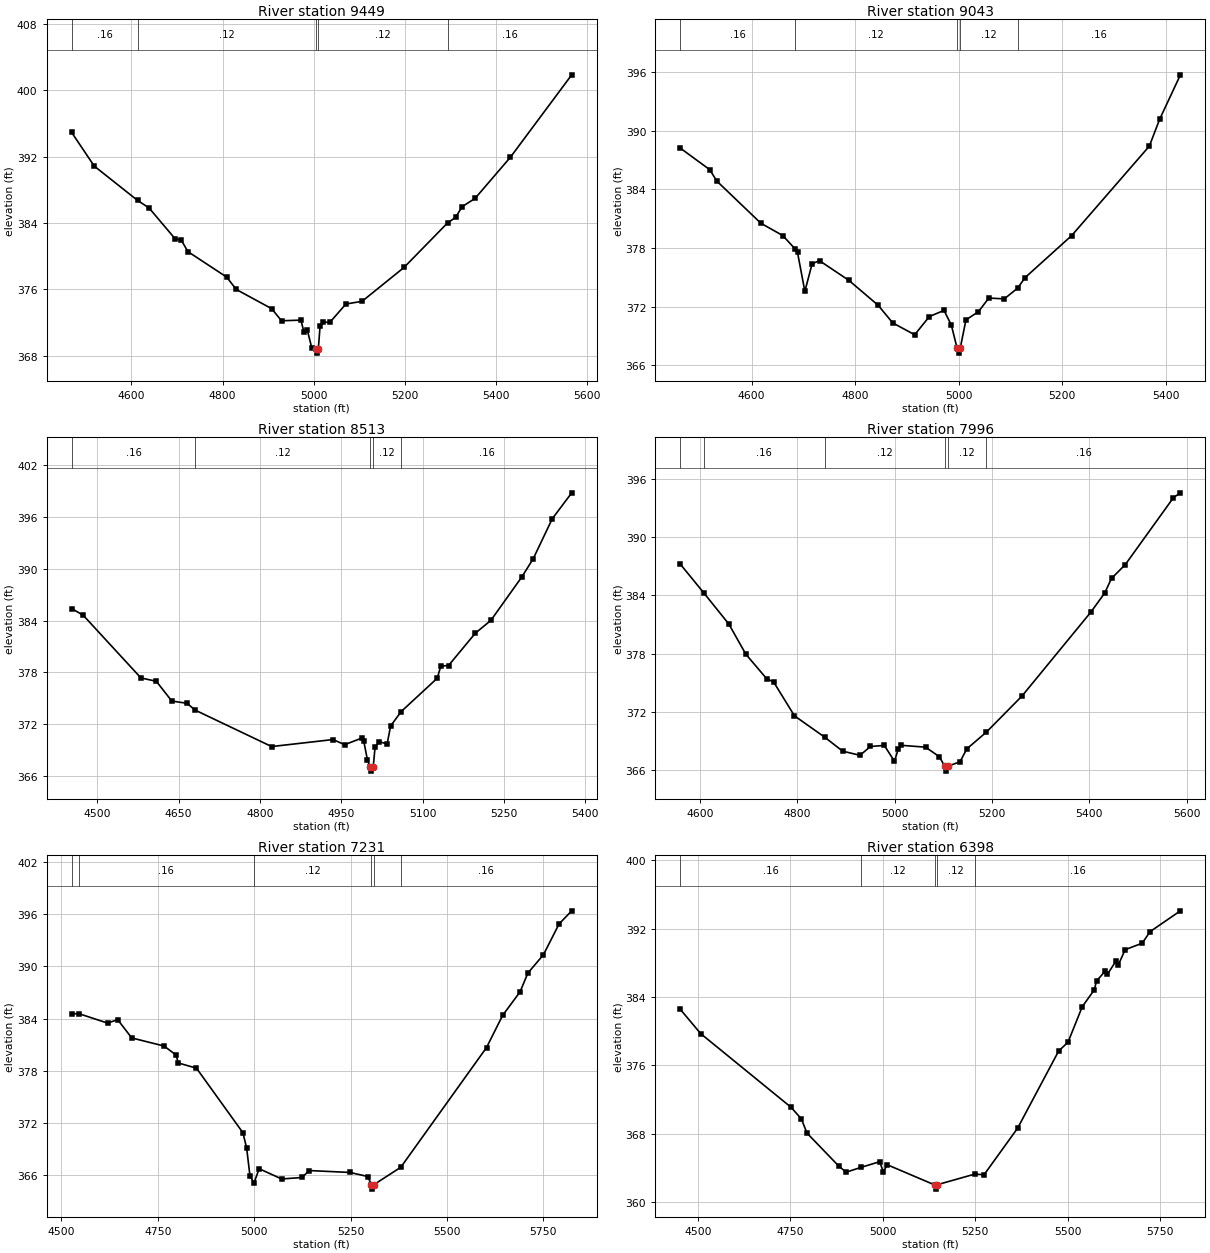
Type RM Length L Ch R = 1 ,9449    ,406,406,406
BEGIN DESCRIPTION:
COLES BRANCH 18.0
END DESCRIPTION:
XS GIS Cut Line= 3
      3527992.11     10433941.63      3528379.61     10433584.66
       3528792.1     10433191.65
#Sta/Elev= 30
    4469  394.91  4518.6  390.85  4613.4  386.72  4638.8   385.8  4695.5  382.11
  4709.7   381.9  4723.9  380.54  4808.9  377.47  4829.9  375.98  4907.6  373.66
  4929.2   372.2  4971.7  372.28  4978.5  370.82  4985.7  371.07  4995.9  368.86
  5003.9   368.8  5006.6   368.3  5009.9   368.8  5013.8  371.62    5021  372.03
  5035.2  372.01  5070.4  374.22  5105.9  374.55  5197.8  378.63  5293.5  384.01
    5311  384.67  5325.2  385.96  5353.5  386.95  5431.1  391.92  5565.6  401.86
#Mann= 5 ,-1 , 0
    4469     .16       0  4613.4     .12       0  5003.9     .07       0
  5009.9     .12       0  5293.5     .16       0
Bank Sta=5003.9,5009.9
XS Rating Curve= 0 ,0
Exp/Cntr=0.3,0.1

Type RM Length L Ch R = 1 ,9043    ,530,530,530
BEGIN DESCRIPTION:
COLES BRANCH 17.0
END DESCRIPTION:
XS GIS Cut Line= 3
      3528242.14     10434241.61      3528642.11     10433841.64
      3529042.06     10433841.64
#Sta/Elev= 30
  4462.4  388.22  4518.9  386.03  4533.1  384.84  4617.9  380.54  4660.3  379.28
  4683.9  377.92  4688.6  377.56  4702.8  373.58  4716.9  376.41  4731.1  376.71
  4787.6  374.71  4844.2  372.16  4872.5  370.35  4914.9  369.14  4943.2     371
  4971.5  371.63  4985.6  370.14  4996.8  367.76  4999.5  367.26  5002.8  367.76
  5013.9  370.66    5038   371.5    5058  372.89    5088  372.81  5113.9  373.92
    5128  374.98    5218  379.28    5368  388.43    5388  391.19    5428  395.72
#Mann= 5 ,-1 , 0
  4462.4     .16       0  4683.9     .12       0  4996.8     .07       0
  5002.8     .12       0  5113.9     .16       0
Bank Sta=4996.8,5002.8
XS Rating Curve= 0 ,0
Exp/Cntr=0.3,0.1

Type RM Length L Ch R = 1 ,8513    ,517,517,517
BEGIN DESCRIPTION:
COLES BRANCH 16.0
END DESCRIPTION:
XS GIS Cut Line= 3
       3528442.1     10434541.65      3528842.11     10434191.64
      3529092.09     10433891.66
#Sta/Elev= 30
  4452.8  385.41  4474.2  384.62  4580.5  377.36  4608.9  376.97  4637.4  374.68
  4665.4  374.42  4680.4  373.63  4821.5   369.4  4934.5  370.21  4956.3  369.62
  4987.6  370.38  4991.5  369.99    4998  367.89  5002.8  367.05  5005.5  366.55
  5008.8  367.05  5012.3  369.37  5020.1  369.97  5034.4  369.69  5040.9  371.79
  5060.4  373.46  5126.9  377.33  5133.4  378.73  5147.7   378.8  5197.1  382.55
  5225.8  384.04  5283.1   389.1  5303.9   391.2    5339  395.83  5374.8  398.83
#Mann= 5 ,-1 , 0
  4452.8     .16       0  4680.4     .12       0  5002.8     .07       0
  5008.8     .12       0  5060.4     .16       0
Bank Sta=5002.8,5008.8
XS Rating Curve= 0 ,0
Exp/Cntr=0.3,0.1

Type RM Length L Ch R = 1 ,7996    ,765,765,765
BEGIN DESCRIPTION:
COLES BRANCH 15.0
END DESCRIPTION:
XS GIS Cut Line= 3
      3528692.09     10434841.65      3529042.11     10434541.64
      3529442.12     10434141.63
#Sta/Elev= 30
  4560.2  387.21  4607.9  384.28  4659.5  381.06  4694.7  377.93  4737.5   375.4
  4751.7  375.07  4794.5  371.58  4856.8  369.37  4893.3  367.94    4929  367.51
  4950.4  368.42  4978.9  368.53  4999.8   366.9  5007.5  368.14  5014.1  368.54
  5063.6  368.35  5091.9  367.37    5103  366.38  5105.8  365.88    5109  366.38
  5134.3  366.84  5148.5  368.18  5188.7  369.91  5261.6  373.62    5403  382.27
  5431.3  384.23  5445.5  385.75  5473.7  387.17  5572.7  394.08  5586.9  394.57
#Mann= 6 ,-1 , 0
  4560.2     .05       0  4607.9     .16       0  4856.8     .12       0
    5103     .07       0    5109     .12       0  5188.7     .16       0
Bank Sta=5103,5109
XS Rating Curve= 0 ,0
Exp/Cntr=0.3,0.1

Type RM Length L Ch R = 1 ,7231    ,833,833,833
BEGIN DESCRIPTION:
COLES BRANCH 14.0
END DESCRIPTION:
XS GIS Cut Line= 4
      3529004.45     10435165.05      3529296.15     10435066.08
      3529593.02     10434357.75      3529561.77     10434139.03
#Sta/Elev= 30
  4526.6  384.52  4544.5  384.58  4619.7  383.48  4645.9  383.88  4682.5  381.77
  4766.2  380.84  4797.6   379.8  4802.9  378.89  4850.3  378.29  4970.7  370.86
  4980.4  369.11  4989.1  365.86  4999.5  365.07  5012.9  366.71  5071.3  365.53
  5124.2   365.7  5142.6   366.5  5248.5  366.28  5294.8  365.81  5303.9  364.86
  5306.7  364.36  5309.9  364.86  5380.3  366.88  5602.7  380.67  5644.3  384.36
  5689.6  387.08  5709.8  389.24  5750.2  391.35  5790.8   394.9  5823.6  396.41
#Mann= 6 ,-1 , 0
  4526.6     .05       0  4544.5     .16       0  4999.5     .12       0
  5303.9     .07       0  5309.9     .12       0  5380.3     .16       0
Bank Sta=5303.9,5309.9
XS Rating Curve= 0 ,0
Exp/Cntr=0.3,0.1

Type RM Length L Ch R = 1 ,6398    ,832,832,832
BEGIN DESCRIPTION:
COLES BRANCH 13.0
END DESCRIPTION:
XS GIS Cut Line= 4
      3529546.13     10435331.72      3529811.77     10435185.87
      3529910.73     10434456.71      3529791.28     10434165.88
#Sta/Elev= 30
  4452.2  382.56  4507.3  379.72  4751.8   371.1  4779.7  369.74  4794.9  368.08
  4880.6  364.23  4900.8   363.5  4940.5  364.06  4991.6  364.73  5001.7  363.53
  5011.8  364.38    5140  362.02  5142.8  361.52    5146  362.02  5248.3  363.27
  5274.2  363.21    5365  368.66    5476  377.69  5501.3  378.72  5539.8  382.87
  5572.2  384.84  5578.6  385.89  5602.6  387.08    5608  386.67    5632  388.28
  5637.4  387.76  5655.9  389.55    5702  390.31  5723.6  391.67  5805.5   394.1
#Mann= 5 ,-1 , 0
  4452.2     .16       0  4940.5     .12       0    5140     .07       0
    5146     .12       0  5248.3     .16       0
Bank Sta=5140,5146
XS Rating Curve= 0 ,0
Exp/Cntr=0.3,0.1

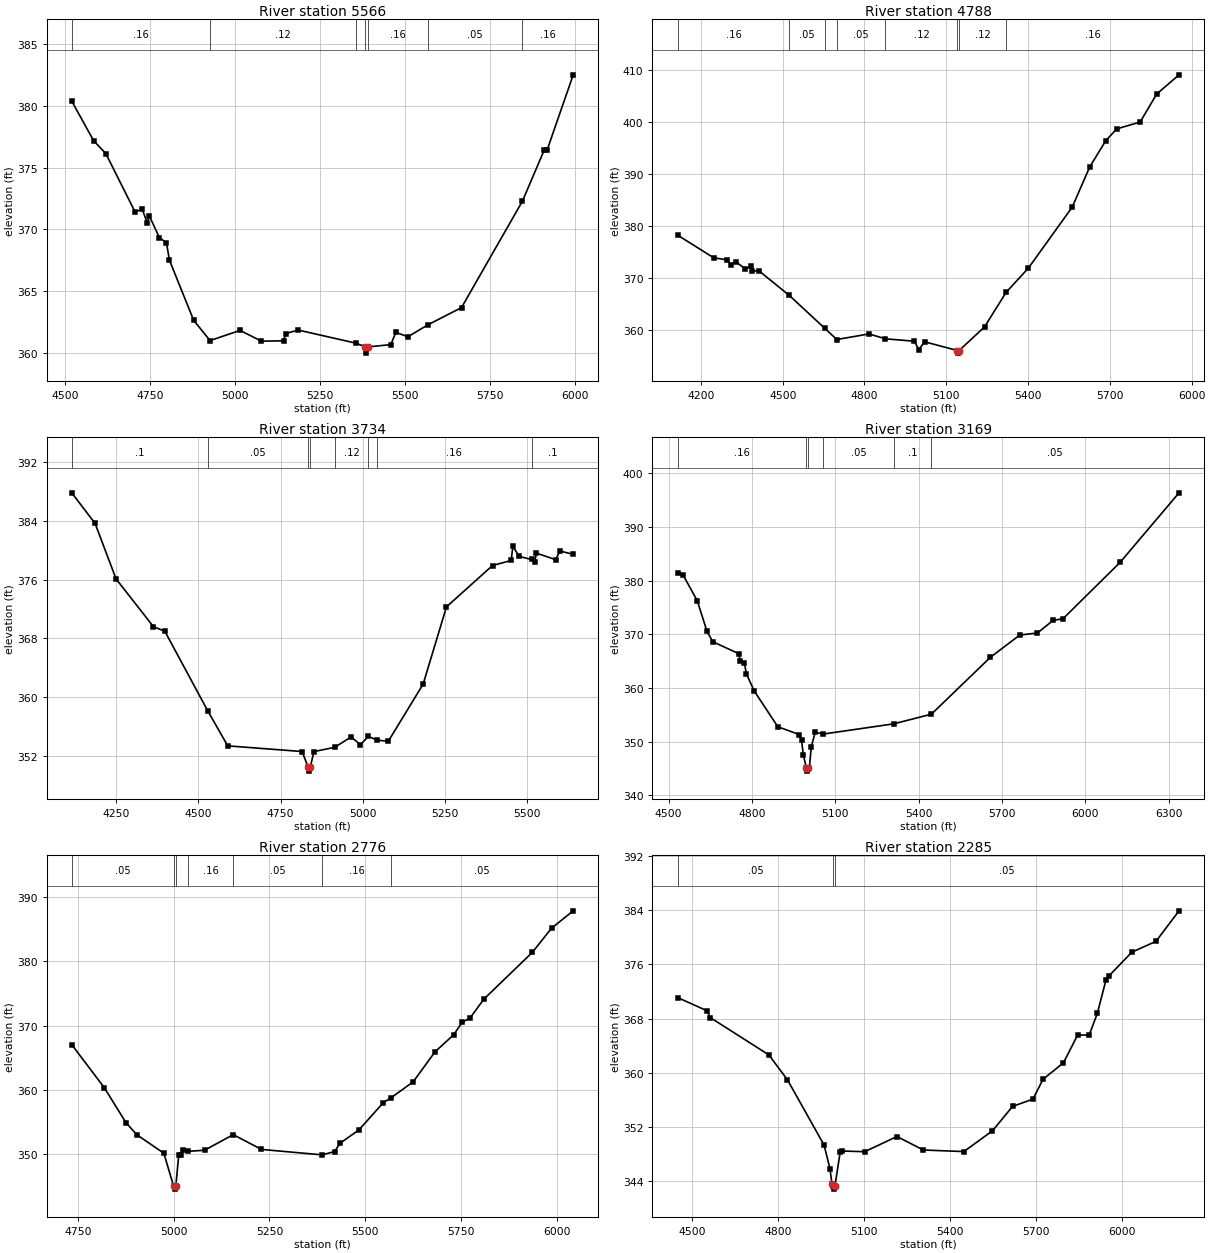
Type RM Length L Ch R = 1 ,5566    ,778,778,778
BEGIN DESCRIPTION:
COLES BRANCH 12.0
END DESCRIPTION:
XS GIS Cut Line= 2
      3529978.41     10435467.16      3530827.22     10434259.04
#Sta/Elev= 30
  4519.6   380.4  4584.1  377.19  4619.9  376.15  4706.1  371.41    4727  371.64
  4741.8  370.54    4748   371.1  4777.6  369.34  4798.5  368.91  4807.2  367.51
  4878.6  362.63  4926.8  360.99  5015.2  361.81  5078.2  360.94  5143.5  360.97
  5149.6  361.56  5186.3  361.84  5356.1  360.78  5384.5  360.47  5387.3  359.97
  5390.5  360.47    5459  360.66  5473.8  361.65  5509.5   361.3  5568.6  362.27
  5667.2  363.66  5846.6  372.29  5911.2  376.46  5919.6  376.46  5996.1  382.53
#Mann= 7 ,-1 , 0
  4519.6     .16       0  4926.8     .12       0  5356.1     .16       0
  5384.5     .07       0  5390.5     .16       0  5568.6     .05       0
  5846.6     .16       0
Bank Sta=5384.5,5390.5
XS Rating Curve= 0 ,0
Exp/Cntr=0.3,0.1

Type RM Length L Ch R = 1 ,4788    ,1054,1054,1054
BEGIN DESCRIPTION:
COLES BRANCH 10.0
END DESCRIPTION:
XS GIS Cut Line= 4
       3530259.7     10435722.33      3530676.35     10435566.08
      3531259.69     10434555.67      3531301.35     10434331.71
#Sta/Elev= 30
  4114.2  378.21  4247.3  373.83  4297.1  373.44    4309  372.54  4327.4   373.1
    4363   371.7  4382.6  372.19  4387.9   371.3  4412.8  371.33    4524   366.6
  4654.6  360.24  4698.4   358.1  4816.6  359.18  4876.2  358.24  4983.2  357.77
    4999  356.15  5020.6  357.66  5141.1  355.98  5143.8  355.48  5147.1  355.98
  5240.3  360.53  5319.4  367.18  5401.1  371.85  5561.9   383.6  5626.6  391.38
  5685.4  396.42  5725.3  398.66  5811.4     400  5871.6  405.37  5953.7  409.08
#Mann= 8 ,-1 , 0
  4114.2     .16       0    4524     .05       0  4654.6     .16       0
  4698.4     .05       0  4876.2     .12       0  5141.1     .07       0
  5147.1     .12       0  5319.4     .16       0
Bank Sta=5141.1,5147.1
XS Rating Curve= 0 ,0
Exp/Cntr=0.3,0.1

Type RM Length L Ch R = 1 ,3734    ,565,565,565
BEGIN DESCRIPTION:
COLES BRANCH 8.0
END DESCRIPTION:
XS GIS Cut Line= 3
       3530827.4     10436097.33      3531603.44     10435253.58
      3531551.35     10434878.54
#Sta/Elev= 30
  4114.7  387.77  4185.8  383.61  4249.4  376.09  4362.8  369.62  4397.9  368.97
  4528.1  358.19  4589.1  353.42  4815.3  352.65  4833.9  350.49  4836.7  349.99
  4839.9  350.49  4851.1  352.64  4914.1  353.22  4964.5  354.63  4992.3  353.58
  5017.1  354.71  5042.8   354.2  5077.4  354.04  5183.4  361.81  5254.3  372.29
  5394.3   377.9  5451.1  378.59  5456.2  380.53    5475  379.14  5513.2  378.72
  5522.8  378.44  5527.9  379.58  5586.1   378.7  5599.5  379.88  5639.7  379.41
#Mann= 8 ,-1 , 0
  4114.7      .1       0  4528.1     .05       0  4833.9     .07       0
  4839.9     .05       0  4914.1     .12       0  5017.1      .1       0
  5042.8     .16       0  5513.2      .1       0
Bank Sta=4833.9,4839.9
XS Rating Curve= 0 ,0
Exp/Cntr=0.3,0.1

Type RM Length L Ch R = 1 ,3169    ,393,393,393
BEGIN DESCRIPTION:
COLES BRANCH 7.0
END DESCRIPTION:
XS GIS Cut Line= 2
      3531087.78     10436217.16      3532435.29     10435015.32
#Sta/Elev= 30
    4532  381.34  4552.8  380.95    4603  376.24  4638.1  370.52    4659   368.6
  4751.8   366.4  4758.5  364.94  4772.7  364.69  4779.4  362.68  4807.8  359.46
  4893.1  352.77  4970.9  351.31  4978.4  350.26  4985.1  347.49  4996.3  345.01
    4999  344.51  5002.3  345.01  5006.8  345.14  5013.5  349.04  5027.7  351.74
  5057.3  351.42  5309.9  353.31    5446  355.11  5658.1  365.69  5764.3  369.85
  5827.8  370.23  5884.7   372.6  5919.8  372.88  6125.5  383.38  6337.6  396.33
#Mann= 6 ,-1 , 0
    4532     .16       0  4996.3     .07       0  5002.3     .16       0
  5057.3     .05       0  5309.9      .1       0    5446     .05       0
Bank Sta=4996.3,5002.3
XS Rating Curve= 0 ,0
Exp/Cntr=0.3,0.1

Type RM Length L Ch R = 1 ,2776    ,491,491,491
BEGIN DESCRIPTION:
COLES BRANCH 6.0
END DESCRIPTION:
XS GIS Cut Line= 3
       3531542.1     10436341.65      3531742.11     10436141.64
      3532442.13     10435391.62
#Sta/Elev= 30
    4734  367.03  4818.9  360.33  4875.4   354.9  4903.7  353.01  4974.4  350.13
  4999.7  345.04  5002.5  344.54  5005.7  345.04  5013.3  349.89  5020.3  349.89
  5023.9  350.61  5036.7  350.42  5080.6  350.59  5155.5  353.02  5229.1  350.72
  5387.7  349.87  5420.1  350.39  5434.3  351.68  5483.6  353.76  5547.6  358.02
  5567.8  358.77  5625.3  361.25    5682   365.9  5731.3  368.59  5752.8   370.5
  5773.8  371.18  5809.5   374.1  5936.5  381.41  5986.3  385.15  6042.8  387.85
#Mann= 7 ,-1 , 0
    4734     .05       0  4999.7     .03       0  5005.7     .05       0
  5036.7     .16       0  5155.5     .05       0  5387.7     .16       0
  5567.8     .05       0
Bank Sta=4999.7,5005.7
XS Rating Curve= 0 ,0
Exp/Cntr=0.3,0.1

Type RM Length L Ch R = 1 ,2285    ,268,268,268
BEGIN DESCRIPTION:
COLES BRANCH 5.0
END DESCRIPTION:
XS GIS Cut Line= 4
       3531660.7     10436550.46      3532030.52     10436467.12
      3532837.81     10435779.62      3532863.85     10435467.17
#Sta/Elev= 30
  4447.8  371.11  4551.4  369.15    4562  368.16    4767  362.65  4831.6     359
  4960.1  349.35  4980.9   345.8  4987.5  343.62  4992.2  343.35    4995  342.85
  4998.2  343.35  5016.1  348.26  5023.8  348.47  5101.8  348.37  5214.8  350.61
  5307.1  348.62  5448.7  348.39  5548.7  351.45  5618.9  355.05  5690.3  356.13
  5725.5  359.06  5796.9  361.49  5846.3  365.57  5886.8  365.58  5915.3  368.78
  5945.4  373.69  5955.5  374.28  6035.8   377.8  6120.3   379.4  6200.8   383.9
#Mann= 3 ,-1 , 0
  4447.8     .05       0  4992.2     .03       0  4998.2     .05       0
Bank Sta=4987.5,4998.2
XS Rating Curve= 0 ,0
Exp/Cntr=0.3,0.1

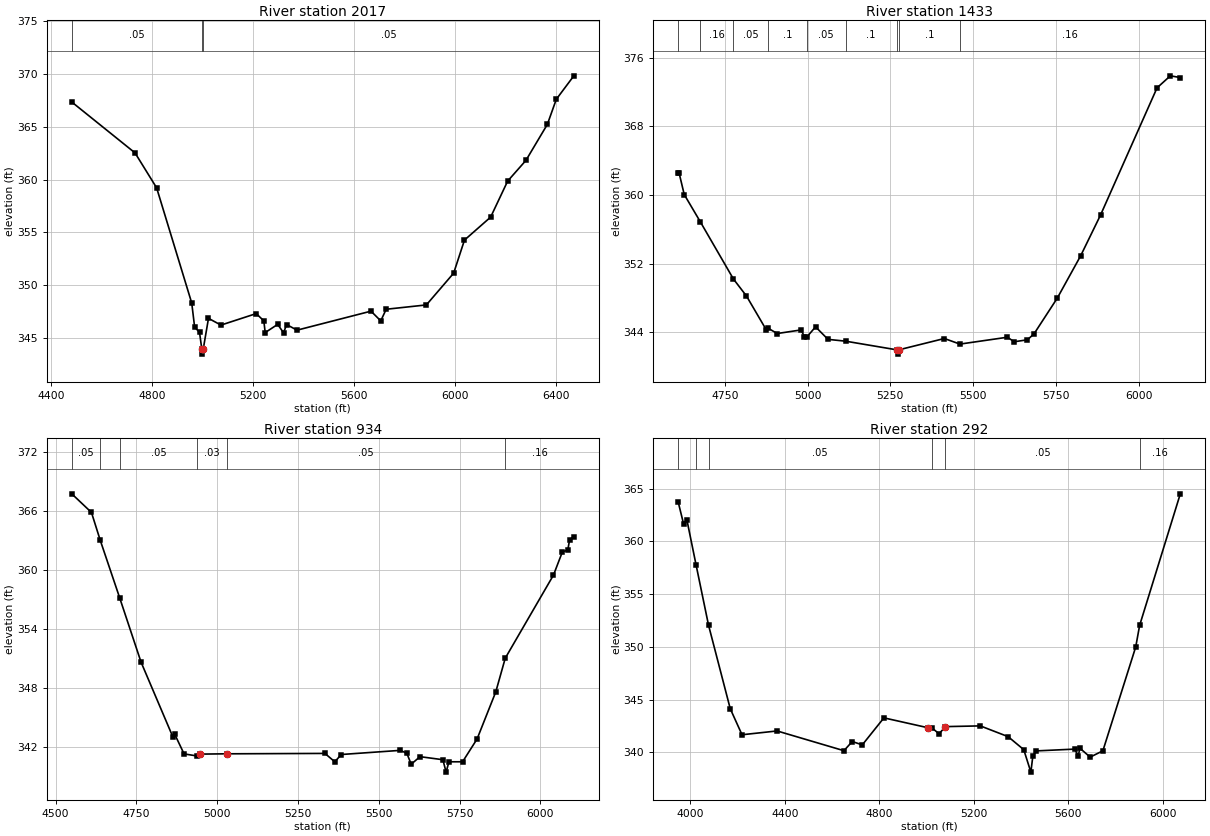
Type RM Length L Ch R = 1 ,2017    ,584,584,584
BEGIN DESCRIPTION:
COLES BRANCH 4.0
END DESCRIPTION:
XS GIS Cut Line= 2
      3531837.84     10436748.36      3533697.19     10436040.04
#Sta/Elev= 30
  4481.6  367.34  4732.3  362.52  4817.9  359.21    4957   348.3  4968.5  346.02
  4987.9  345.52  4996.8  343.96  4999.6  343.46  5002.8  343.96  5023.4  346.85
  5072.8  346.21  5212.6   347.3  5242.7  346.61  5248.1   345.5  5297.6  346.28
  5320.8  345.48    5333  346.26  5374.3  345.73  5667.4  347.53  5706.1  346.61
  5727.6  347.71  5886.8  348.12    5995  351.13  6037.8  354.26  6141.6  356.44
    6209  359.85  6281.4  361.81  6366.3  365.22  6401.8   367.6  6471.3  369.82
#Mann= 3 ,-1 , 0
  4481.6     .05       0  4996.8     .03       0  5002.8     .05       0
Bank Sta=4996.8,5002.8
XS Rating Curve= 0 ,0
Exp/Cntr=0.3,0.1

Type RM Length L Ch R = 1 ,1433    ,499,499,499
BEGIN DESCRIPTION:
COLES BRANCH 3.0
END DESCRIPTION:
XS GIS Cut Line= 3
      3532192.06     10437141.65      3532592.11     10437041.64
      3533692.12     10436941.64
#Sta/Elev= 30
  4609.2  362.58  4611.8  362.58  4627.3  360.07  4675.6  356.91    4776  350.22
  4815.4  348.24  4874.7  344.33  4880.3   344.5  4908.2  343.87  4980.3  344.29
  4990.6  343.49  4998.5   343.5  5024.1  344.65  5061.7  343.19  5114.6  342.98
  5269.6  341.97  5272.3  341.47  5275.6  341.97  5413.2  343.29  5460.3  342.64
  5603.9  343.44    5624  342.91  5664.2  343.14  5684.3  343.84  5754.6  348.01
  5824.9  352.92  5885.1  357.68  6055.8   372.5    6096   373.9  6126.1   373.7
#Mann= 9 ,-1 , 0
  4609.2     .05       0  4675.6     .16       0    4776     .05       0
  4880.3      .1       0  4998.5     .05       0  5114.6      .1       0
  5269.6     .03       0  5275.6      .1       0  5460.3     .16       0
Bank Sta=5269.6,5275.6
XS Rating Curve= 0 ,0
Exp/Cntr=0.3,0.1

Type RM Length L Ch R = 1 ,934     ,642,642,642
BEGIN DESCRIPTION:
COLES BRANCH 1.1
END DESCRIPTION:
XS GIS Cut Line= 4
      3532152.83     10437408.08      3532345.56     10437512.25
      3533366.39     10437342.98      3533504.42     10437077.35
#Sta/Elev= 30
  4550.3  367.73  4611.2  365.84  4638.2  363.03  4698.7  357.15  4764.6  350.64
  4863.5  343.01  4868.6  343.33  4897.7  341.32  4938.2  341.11  4948.3   341.3
  5029.4  341.33  5333.5  341.37  5363.9  340.52  5384.2  341.26  5566.7  341.68
  5586.9  341.38  5600.3  340.27  5627.5  341.04  5698.4  340.73  5708.3  339.47
  5717.1  340.52  5759.3  340.52  5804.2  342.84    5862  347.62  5891.3  351.04
  6040.5  359.48  6068.2  361.85  6084.7  362.01  6090.3  363.05  6103.5  363.39
#Mann= 6 ,-1 , 0
  4550.3     .05       0  4638.2      .1       0  4698.7     .05       0
  4938.2     .03       0  5029.4     .05       0  5891.3     .16       0
Bank Sta=4948.3,5029.4
XS Rating Curve= 0 ,0
Exp/Cntr=0.3,0.1

Type RM Length L Ch R = 1 ,292     ,0,0,0
BEGIN DESCRIPTION:
COLES BRANCH 1.0
END DESCRIPTION:
XS GIS Cut Line= 4
      3532160.51     10437481.72      3532806.32     10438075.45
      3533132.02     10437882.05      3533535.68     10437111.19
#Sta/Elev= 30
  3948.8  363.71  3971.1  361.68  3985.3  362.05  4024.6  357.74  4077.1  352.06
    4169  344.15  4218.9  341.68  4367.5  342.04  4650.5  340.17  4685.7  341.04
  4728.2  340.72  4819.8  343.28  5007.2  342.34  5022.1  342.35  5053.3  341.77
  5080.6  342.45  5227.9  342.52  5345.8   341.5    5412  340.27  5442.1  338.14
  5450.5  339.66  5464.9  340.15    5627  340.32  5643.4  339.68  5649.1  340.42
  5693.2  339.56  5747.1  340.16  5886.2     350  5902.6  352.03    6075   364.5
#Mann= 6 ,-1 , 0
  3948.8     .05       0  4024.6      .1       0  4077.1     .05       0
  5022.1     .03       0  5080.6     .05       0  5902.6     .16       0
Bank Sta=5007.2,5080.6
XS Rating Curve= 0 ,0
Exp/Cntr=0.3,0.1

Chan Stop Cuts=-1
Use User Specified Reach Order=0
Composite Channel Slope=5