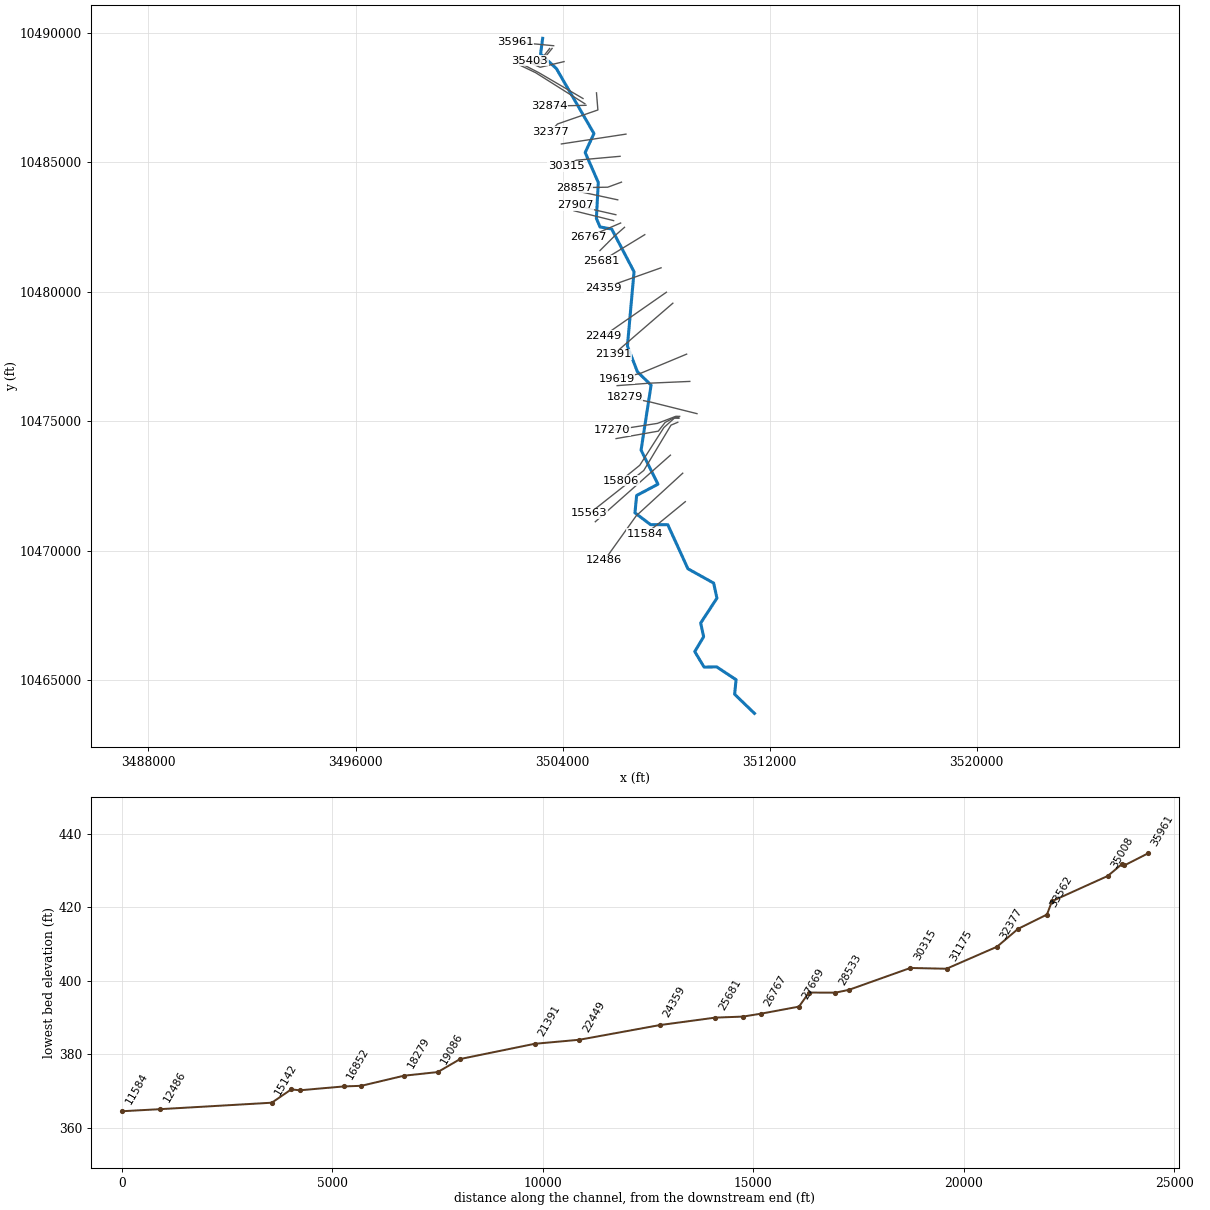
--- COX CREEK.prj (project) ---

Proj Title=COX CREEK Base Level Engineering
Current Plan=p01
Default Exp/Contr=0.3,0.1
English Units
Geom File=g01
Flow File=f01
Plan File=p01
Y Axis Title=Elevation
X Axis Title(PF)=Main Channel Distance
X Axis Title(XS)=Station
BEGIN DESCRIPTION:
COX CREEK
END DESCRIPTION:
DSS Export Rating Curves= 0
DSS Export Rating Curve Sorted= 0
DSS Export Volume Flow Curves= 0
DXF OffsetX= 0
DXF OffsetY= 0
DXF ScaleX= 1
DXF ScaleY= 10

--- COX CREEK.p01 (plan) ---

Plan Title=Multiple Run
Short Identifier=Multiple
Geom File=g01
Flow File=f01
Subcritical Flow
K Sum by GR= 0
Std Step Tol= 0.01
Critical Tol= 0.01
Num of Std Step Trials= 20
Max Error Tol= 0.3
Flow Tol Ratio= 0.001
Split Flow NTrial= 30
Split Flow Tol= 0.02
Split Flow Ratio= 0.02
Log Output Level= 0
Friction Slope Method= 1
Unsteady Friction Slope Method= 2
Unsteady Bridges Friction Slope Method= 1
Parabolic Critical Depth
Global Vel Dist=  1 , 1 , 1
Global Log Level= 0
CheckData=True
Encroach Param= -1, 0, 0, 0
BEGIN DESCRIPTION:
Multiple Run
END DESCRIPTION:

--- COX CREEK.f01 (steady flow) ---

Flow Title=Multiple
Program Version=4.10
Number of Profiles= 7
Profile Names=10-year,25-year,50-year,1pct_min,100-year,1pct_plu,500-year
River Rch & RM=COX CREEK,Reach-1         ,35961
     902    1237    1512    1350    1825    2468    2651
River Rch & RM=COX CREEK,Reach-1         ,33681
    1554    2197    2740    2491    3369    4557    5083
River Rch & RM=COX CREEK,Reach-1         ,31175
    2619    3789    4801    4425    5984    8093    9283
River Rch & RM=COX CREEK,Reach-1         ,26767
    2899    4199    5324    4906    6635    8973   10293
River Rch & RM=COX CREEK,Reach-1         ,19619
    3219    4666    5918    5453    7374    9973   11432
River Rch & RM=COX CREEK,Reach-1         ,12486
    3370    4866    6156    5653    7645   10339   11776
River Rch & RM=COX CREEK,Reach-1         ,8832
    3680    5334    6764    6225    8418   11385   13025
Boundary for River Rch & Prof#=COX CREEK,Reach-1         , 1
Up Type= 0
Dn Type= 3
Dn Slope=0.0015
Boundary for River Rch & Prof#=COX CREEK,Reach-1         , 2
Up Type= 0
Dn Type= 3
Dn Slope=0.0015
Boundary for River Rch & Prof#=COX CREEK,Reach-1         , 3
Up Type= 0
Dn Type= 3
Dn Slope=0.0015
Boundary for River Rch & Prof#=COX CREEK,Reach-1         , 4
Up Type= 0
Dn Type= 3
Dn Slope=0.0015
Boundary for River Rch & Prof#=COX CREEK,Reach-1         , 5
Up Type= 0
Dn Type= 3
Dn Slope=0.0015
Boundary for River Rch & Prof#=COX CREEK,Reach-1         , 6
Up Type= 0
Dn Type= 3
Dn Slope=0.0015
Boundary for River Rch & Prof#=COX CREEK,Reach-1         , 7
Up Type= 0
Dn Type= 3
Dn Slope=0.0015
DSS Import GetInterval= 0
DSS Import GetPeak= 0
DSS Import FillOption= 0

--- COX CREEK.g01 (geometry) ---

Geom Title=Existing Conditions
Program Version=4.10

River Reach=COX CREEK       ,Reach-1
Reach XY= 30
      3503229.49     10489792.72      3503149.85     10489191.95
      3503761.48     10488622.51        3505212.     10486112.96
      3504872.27     10485381.77      3505379.62       10484223.
      3505304.71     10482837.68      3505446.05     10482505.79
      3505897.12      10482424.3      3506760.04     10480775.79
      3506504.65     10477907.55      3506888.85     10476912.36
      3507418.57     10476393.11      3507032.05     10473882.91
      3507684.57     10472566.38      3506859.74     10472129.23
      3506796.38     10471457.73      3507399.12     10471003.31
      3508064.48     10471000.27      3508841.31      10469299.2
      3509836.21     10468745.57      3509962.95     10468162.24
      3509335.27     10467202.74      3509448.99     10466673.23
      3509106.97     10466097.71      3509466.02     10465499.64
      3509954.95     10465507.37      3510701.55     10465013.01
      3510647.48     10464448.99      3511412.11     10463711.64

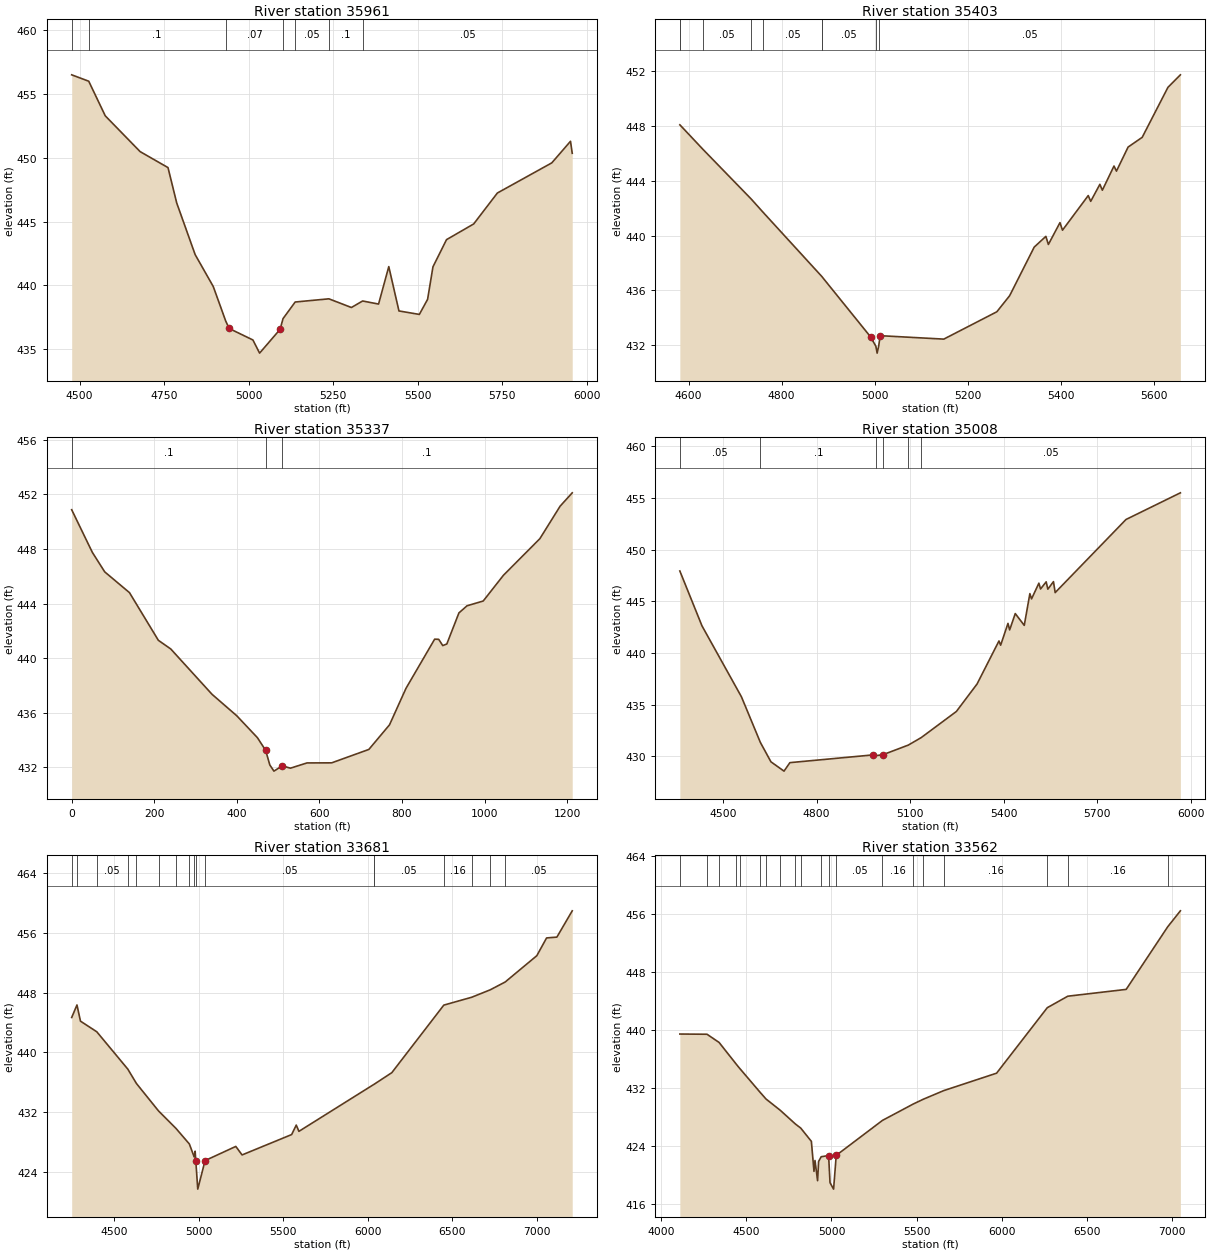
Type RM Length L Ch R = 1 ,35961   ,558,558,558
BEGIN DESCRIPTION:
COX CREEK 72.0
END DESCRIPTION:
XS GIS Cut Line= 2
      3503655.58     10489507.23      3502182.01     10489647.12
#Sta/Elev= 30
  4476.6  456.48    4527  455.98  4575.9  453.27    4679  450.47  4761.4  449.22
  4787.2  446.45  4841.7  442.41  4895.3  439.91  4932.1  437.21  4942.2  436.63
  5012.5  435.73  5032.3   434.7  5092.8  436.56  5101.6   437.4  5137.5   438.7
  5237.2  438.95  5303.8  438.27  5336.9  438.78  5384.1  438.54  5414.3  441.47
  5444.4     438  5504.7  437.73  5529.1  438.91  5544.9  441.45    5585  443.58
  5665.4  444.81  5735.4  447.23  5896.4  449.59  5951.7  451.28  5956.8  450.34
#Mann= 7 ,-1 , 0
  4476.6     .08       0    4527      .1       0  4932.1     .07       0
  5101.6      .1       0  5137.5     .05       0  5237.2      .1       0
  5336.9     .05       0
#XS Ineff= 2 , 0
                         5414.55          441.41
Permanent Ineff=
       F       F
Bank Sta=4942.2,5092.8
XS Rating Curve= 0 ,0
Exp/Cntr=0.3,0.1

Type RM Length L Ch R = 1 ,35403   ,66,66,66
BEGIN DESCRIPTION:
Mapping XS 34797936
END DESCRIPTION:
XS GIS Cut Line= 3
        3503499.     10489399.71      3503038.93     10488811.18
      3502731.62     10488925.77
#Sta/Elev= 30
  4581.3  448.06  4581.7  448.05  4630.5  446.29  4734.5  442.66  4759.1  441.73
  4887.3  436.98  4887.6  436.96  4990.8  432.63  5002.3  431.94    5005  431.44
  5008.3  431.94  5011.6  432.71  5148.2  432.46  5262.1  434.45  5289.6  435.62
  5342.4  439.16  5367.4  439.94  5372.8  439.35  5397.7  440.94  5403.1  440.39
  5458.4  442.91  5463.7  442.49  5483.4  443.73  5488.7   443.3  5513.7  445.06
    5519  444.69    5544  446.44  5574.3  447.15  5629.6  450.79  5656.3   451.7
#Mann= 9 ,-1 , 0
  4581.3  .05012       0  4581.7      .1       0  4630.5     .05       0
  4734.5      .1       0  4759.1     .05       0  4887.3      .1       0
  4887.6     .05       0  5002.3     .04       0  5008.3     .05       0
Bank Sta=4990.8,5011.6
XS Rating Curve= 0 ,0
Exp/Cntr=0.3,0.1

Type RM Length L Ch R = 1 ,35337   ,329,329,329
XS GIS Cut Line= 3
      3503594.78    10489403.805     3503059.841    10488740.827
     3502722.384    10488886.227
#Sta/Elev= 30
       0 450.87949.98077447.757779.96924446.3281139.9462444.8052209.9192 441.312
239.9077440.6799339.8693437.3582399.8462435.7838449.8269434.1802469.8192433.2473
479.8154 432.184489.8116  431.73509.8039432.1148529.7962431.9464569.7808432.3301
629.7578432.3373719.7231 433.319769.7039435.1201809.6885437.7964879.0734 441.397
888.8735441.3851898.6735440.9265908.4736441.0406937.8739  443.32957.4741443.8421
996.6744444.19151045.675446.07761133.876448.75751182.876451.13581212.276452.1169
#Mann= 3 , 0 , 0
       0      .1       0469.8192     .07       0509.8039      .1       0
Bank Sta=469.8192,509.8039
XS Rating Curve= 0 ,0
Exp/Cntr=0.3,0.1

Type RM Length L Ch R = 1 ,35008   ,1327,1327,1327
BEGIN DESCRIPTION:
Mapping XS 14d30faa
END DESCRIPTION:
XS GIS Cut Line= 3
      3504055.74     10488893.17      3503133.83     10488674.42
      3502529.49     10488937.43
#Sta/Elev= 30
  4360.9  447.93    4432  442.62  4558.6  435.76  4619.3  431.35  4653.3  429.47
  4695.3  428.57  4714.1  429.39  4981.3  430.14    4991  430.07  5012.1  430.15
  5094.3  431.09  5135.5  431.81  5248.5  434.34  5314.9     437  5385.2  441.16
  5390.6  440.75  5414.1  442.86  5419.5  442.23  5437.5  443.81  5466.4  442.67
  5484.4  445.74  5489.8  445.23  5513.3  446.75  5518.7  446.19  5536.7  446.88
  5542.1  446.17  5560.1   446.9  5565.6  445.84  5792.9  452.91  5967.5  455.49
#Mann= 6 ,-1 , 0
  4360.9     .05       0  4619.3      .1       0    4991     .07       0
  5012.1      .1       0  5094.3     .12       0  5135.5     .05       0
Bank Sta=4981.3,5012.1
XS Rating Curve= 0 ,0
Exp/Cntr=0.3,0.1

Type RM Length L Ch R = 1 ,33681   ,119,119,119
BEGIN DESCRIPTION:
COX CREEK 69.0
END DESCRIPTION:
XS GIS Cut Line= 3
       3504788.1     10487468.16      3503071.94     10488470.77
      3502205.91     10488918.09
#Sta/Elev= 30
  4246.9  444.68  4278.1  446.36  4298.9  444.19  4395.3  442.77  4578.9  437.77
  4629.8  435.85    4761  432.16  4864.2  429.82  4943.2  427.74  4971.7  426.01
  4977.5  426.77  4981.4  425.49    4993  421.69  5036.2  425.51  5218.1  427.41
  5255.3  426.27  5548.7     429    5576  430.27  5591.7  429.43  6036.1  435.73
  6036.4  435.73  6141.4  437.29  6449.2  446.34    6614  447.39  6724.1  448.39
  6812.6  449.44  6999.6  452.96  7057.5  455.34  7118.4  455.45  7209.2  458.97
#Mann= 17 ,-1 , 0
  4246.9     .05       0  4278.1      .1       0  4395.3     .05       0
  4578.9     .16       0  4629.8     .05       0    4761     .16       0
  4864.2     .05       0  4943.2     .16       0  4971.7     .05       0
  4981.4     .04       0  5036.2     .05       0  6036.1     .16       0
  6036.4     .05       0  6449.2     .16       0    6614     .05       0
  6724.1     .16       0  6812.6     .05       0
Bank Sta=4981.4,5036.2
XS Rating Curve= 0 ,0
Exp/Cntr=0.3,0.1

Type RM Length L Ch R = 1 ,33562   ,688,688,688
BEGIN DESCRIPTION:
COX CREEK 66.0
END DESCRIPTION:
XS GIS Cut Line= 3
      3504860.99     10487265.05      3502957.35     10488465.56
      3502336.08     10488761.91
#Sta/Elev= 30
  4109.7  439.46  4269.2  439.43  4340.1   438.3  4442.3  435.26    4460  434.75
  4579.9  431.45  4615.4   430.5  4699.7  428.93  4788.4  427.04  4819.6  426.48
    4882  424.65  4897.3  420.51  4903.2  422.01  4918.5  419.22  4924.4  421.87
  4939.5  422.53  4983.2  422.69  4991.5  418.95  5012.4  418.06  5027.9  422.72
  5299.2  427.54  5480.7  429.81  5538.9  430.46  5658.8  431.65  5969.5  434.06
  6266.9  443.09  6387.5  444.68  6730.3  445.62  6974.3  454.26  7048.6  456.46
#Mann= 20 ,-1 , 0
  4109.7      .1       0  4269.2     .05       0  4340.1      .1       0
  4442.3     .05       0    4460     .16       0  4579.9      .1       0
  4615.4     .05       0  4699.7     .16       0  4788.4     .05       0
  4819.6     .16       0  4939.5     .05       0  4983.2    .035       0
  5027.9     .05       0  5299.2     .16       0  5480.7     .05       0
  5538.9     .16       0  5658.8     .16       0  6266.9     .05       0
  6387.5     .16       0  6974.3     .05       0
Bank Sta=4983.2,5027.9
XS Rating Curve= 0 ,0
Exp/Cntr=0.3,0.1

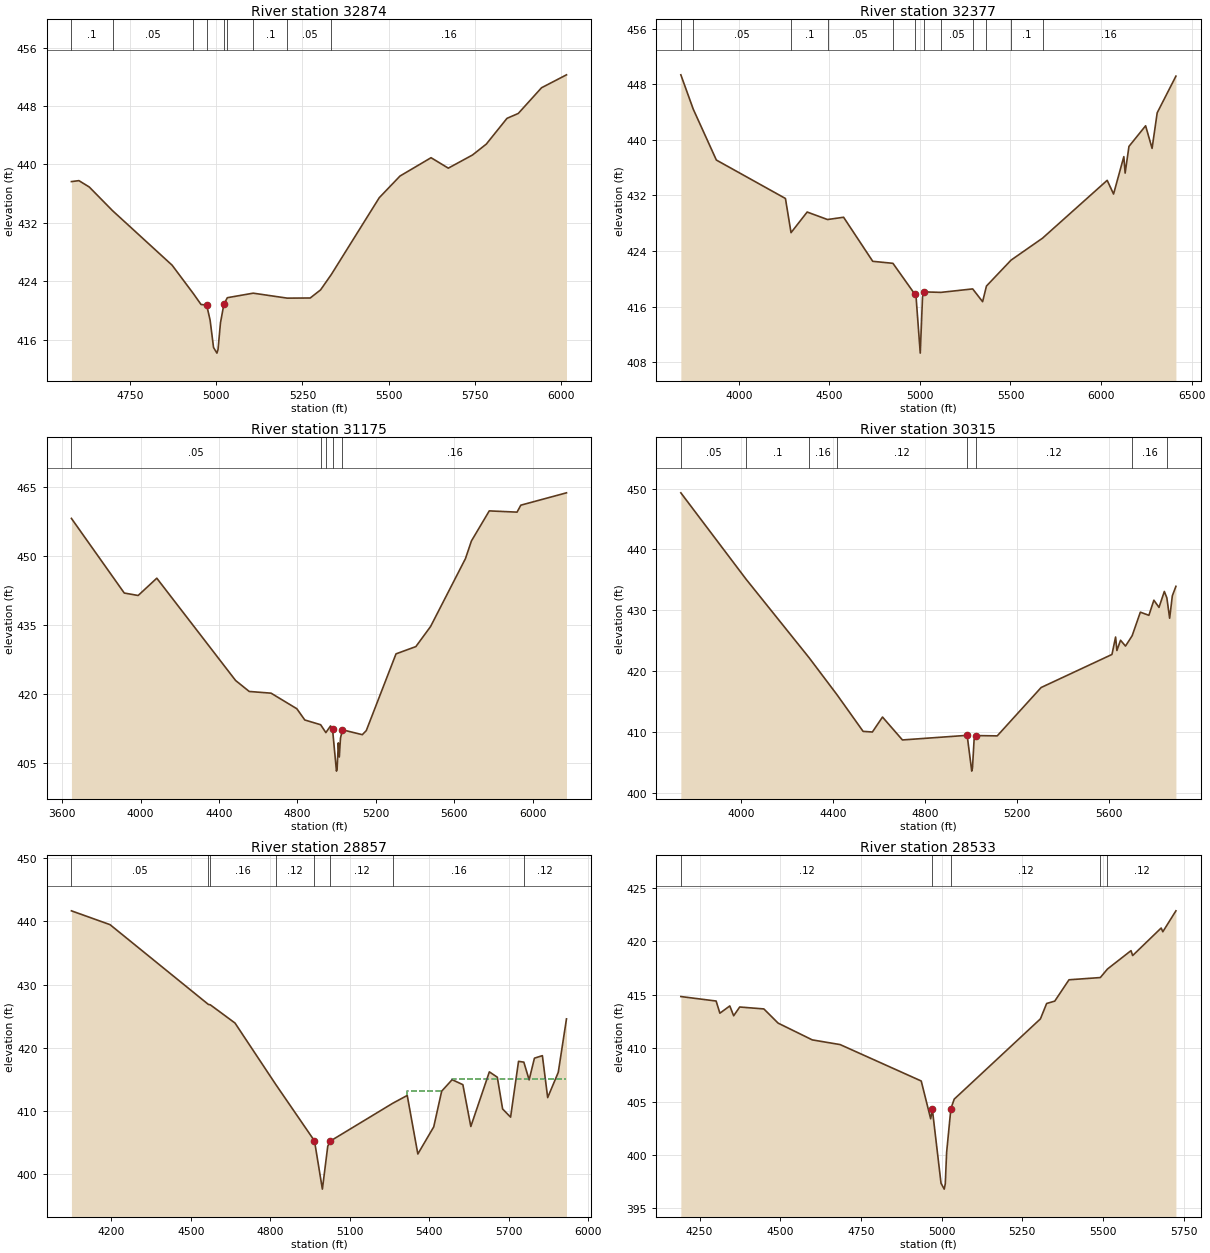
Type RM Length L Ch R = 1 ,32874   ,497,497,497
BEGIN DESCRIPTION:
Mapping XS 6256e9c8
END DESCRIPTION:
XS GIS Cut Line= 2
      3504903.84      10487204.8      3503469.78     10487173.55
#Sta/Elev= 30
  4580.6  437.65  4602.3  437.78  4632.3  436.91  4699.7  433.67  4872.4   426.2
  4934.1   422.3  4956.2  420.82  4972.4  420.74  4982.4  418.69  4992.4  414.93
  5002.2  414.16  5005.4  414.66  5012.4  418.29  5022.4  420.87  5032.4  421.75
  5107.3  422.37  5206.1  421.69  5272.5  421.71  5302.5  422.82  5333.8  424.94
  5472.5  435.44  5532.6  438.41  5622.6  440.92  5672.6  439.49  5742.6  441.29
  5782.6  442.78  5842.6  446.31  5875.3  446.98  5942.7   450.5    6015  452.27
#Mann= 9 ,-1 , 0
  4580.6      .1       0  4699.7     .05       0  4934.1     .16       0
  4972.4     .07       0  5022.4     .16       0  5032.4     .05       0
  5107.3      .1       0  5206.1     .05       0  5333.8     .16       0
Bank Sta=4972.4,5022.4
XS Rating Curve= 0 ,0
Exp/Cntr=0.3,0.1

Type RM Length L Ch R = 1 ,32377   ,1202,1202,1202
BEGIN DESCRIPTION:
COX CREEK 63.0
END DESCRIPTION:
XS GIS Cut Line= 4
      3505309.17     10487687.02      3505363.42     10487025.17
      3503800.92     10486482.63       3503518.8     10486178.81
#Sta/Elev= 30
  3680.5  449.35  3749.1   444.4  3876.5  437.09  4257.8  431.56  4288.7  426.64
  4377.7  429.61    4490  428.53  4578.8  428.86  4739.7  422.52  4851.2  422.23
  4970.5  417.85  4978.1  417.67    5002  409.31  5014.5  417.39  5023.5  418.12
  5116.3  418.05  5291.3  418.55  5346.2  416.71  5367.3  418.96  5503.2  422.69
    5677  425.85  6033.8  434.17    6069   432.2  6125.7  437.58    6133  435.21
    6154  439.05  6245.9  442.02  6281.6  438.77  6309.9  443.89  6413.2  449.16
#Mann= 12 ,-1 , 0
  3680.5     .16       0  3749.1     .05       0  4288.7      .1       0
    4490     .05       0  4851.2      .1       0  4970.5     .07       0
  5023.5      .1       0  5116.3     .05       0  5291.3      .1       0
  5367.3     .05       0  5503.2      .1       0    5677     .16       0
Bank Sta=4970.5,5023.5
XS Rating Curve= 0 ,0
Exp/Cntr=0.3,0.1

Type RM Length L Ch R = 1 ,31175   ,860,860,860
BEGIN DESCRIPTION:
COX CREEK 60.0
END DESCRIPTION:
XS GIS Cut Line= 2
      3506448.52     10486092.01      3503952.85     10485712.24
#Sta/Elev= 30
  3647.6  458.16  3917.1  441.96  3987.9  441.43    4083  445.18  4484.8  422.98
  4554.3   420.6  4665.6  420.23  4797.1  416.85  4837.6  414.41  4918.5  413.38
    4945  411.67    4969  413.12  4979.2  412.35  4999.1  403.31  5002.4  403.81
  5008.6  409.44  5013.6  406.37  5019.6  410.47  5029.7  412.28  5130.9  411.22
  5151.1   412.1  5302.8  428.76    5404  430.34  5478.9  434.69  5656.9  449.44
  5687.2  453.26  5778.3  459.79  5919.9  459.52  5939.2  461.03    6172  463.71
#Mann= 5 ,-1 , 0
  3647.6     .05       0  4918.5     .12       0    4945     .16       0
  4979.2     .07       0  5029.7     .16       0
Bank Sta=4979.2,5029.7
XS Rating Curve= 0 ,0
Exp/Cntr=0.3,0.1

Type RM Length L Ch R = 1 ,30315   ,1458,1458,1458
BEGIN DESCRIPTION:
COX CREEK 57.0
END DESCRIPTION:
XS GIS Cut Line= 3
      3506220.67     10485234.81      3504527.92     10485082.89
      3504138.66     10484855.83
#Sta/Elev= 30
    3739  449.32  4021.8  435.13  4296.3  422.17  4417.5  416.08  4530.7  410.06
  4570.9  409.96  4614.8  412.42  4701.4  408.65  4982.5  409.41  5002.4  403.52
  5005.6  404.02  5012.7  408.74  5022.7  409.37  5113.1  409.32  5303.8  417.28
  5611.4  422.72  5627.2  425.59  5632.9  423.37  5648.7  425.06  5670.2   424.1
  5699.1   425.8  5734.7  429.68  5771.9  429.16  5793.4  431.65  5815.8  430.47
  5838.9  433.09  5849.8  432.04    5862  428.68  5873.6  432.37  5889.2  433.93
#Mann= 8 ,-1 , 0
    3739     .05       0  4021.8      .1       0  4296.3     .16       0
  4417.5     .12       0  4982.5     .07       0  5022.7     .12       0
  5699.1     .16       0  5849.8      .1       0
Bank Sta=4982.5,5022.7
XS Rating Curve= 0 ,0
Exp/Cntr=0.3,0.1

Type RM Length L Ch R = 1 ,28857   ,324,324,324
BEGIN DESCRIPTION:
COX CREEK 56.0
END DESCRIPTION:
XS GIS Cut Line= 3
      3506274.87     10484236.53       3505743.2     10484041.23
      3504441.08     10484019.53
#Sta/Elev= 30
  4049.5  441.69  4195.2   439.5  4566.5  426.85  4573.8  426.79    4667   423.9
  4820.4  414.19    4967  405.22  4996.8  397.57  5017.1  404.38  5027.1   405.2
  5263.1   411.2  5317.1  412.42  5357.1  403.14  5417.1  407.44  5447.1   413.1
  5486.6  414.92  5527.1  414.13  5557.1   407.5  5627.1  416.16  5657.1  415.31
  5677.1  410.28  5707.2  408.98  5737.2  417.83  5757.2   417.7  5777.2  414.89
  5797.2  418.33  5827.2  418.73  5847.2  412.08  5887.2  416.09  5918.2  424.56
#Mann= 8 ,-1 , 0
  4049.5     .05       0  4566.5      .1       0  4573.8     .16       0
  4820.4     .12       0    4967     .07       0  5027.1     .12       0
  5263.1     .16       0  5757.2     .12       0
#XS Ineff= 2 ,-1
 5317.05 5445.45  413.13  5487.5  5918.2  415.08
Permanent Ineff=
       F       F
Bank Sta=4967,5027.1
XS Rating Curve= 0 ,0
Exp/Cntr=0.3,0.1

Type RM Length L Ch R = 1 ,28533   ,626,626,626
BEGIN DESCRIPTION:
Mapping XS 87dad147
END DESCRIPTION:
XS GIS Cut Line= 2
       3506130.4     10483552.88      3504630.37      10483875.8
#Sta/Elev= 30
  4191.9  414.84  4301.2  414.42  4312.9  413.28  4343.6  413.96  4355.6  413.04
  4374.3  413.86  4449.2  413.68  4493.4  412.35  4599.3  410.78  4685.6  410.34
  4936.9  406.93  4966.2  403.39  4971.4  404.27  4998.3  397.35  5008.2   396.8
  5011.5   397.3  5015.6  400.23  5028.9  404.35  5039.2  405.23  5306.4  412.75
  5325.6  414.19  5350.7  414.41  5394.9  416.41    5492  416.62  5514.2  417.42
  5587.1  419.14  5592.2  418.68  5680.6  421.26  5685.7  420.91  5726.3  422.87
#Mann= 5 ,-1 , 0
  4191.9     .12       0  4971.4     .07       0  5028.9     .12       0
    5492     .16       0  5514.2     .12       0
Bank Sta=4971.4,5028.9
XS Rating Curve= 0 ,0
Exp/Cntr=0.3,0.1

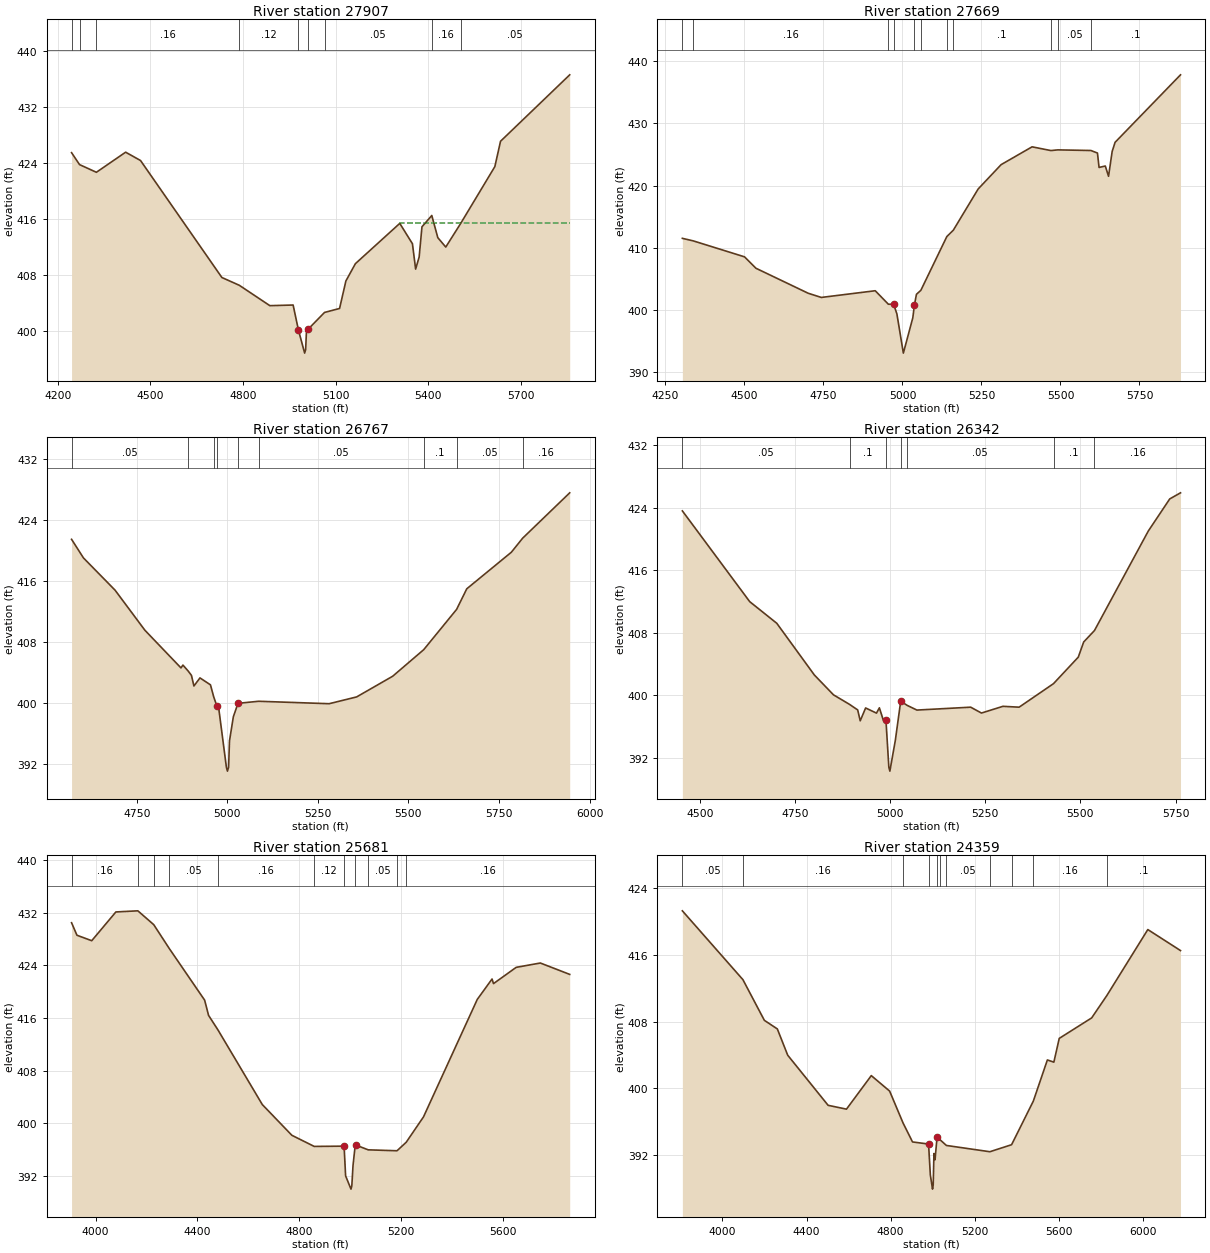
Type RM Length L Ch R = 1 ,27907   ,238,238,238
BEGIN DESCRIPTION:
COX CREEK 51.0
END DESCRIPTION:
XS GIS Cut Line= 2
       3506057.9     10482977.85       3504485.8     10483335.64
#Sta/Elev= 30
    4245  425.46  4270.7  423.76  4325.3  422.66    4420  425.53  4468.2  424.34
  4731.5  407.63  4787.9  406.52  4886.8  403.61  4962.1   403.7  4979.1  400.16
  4999.4  396.83  5002.6  397.33  5005.2   399.9  5010.3  400.23  5063.7  402.64
  5112.4  403.21  5132.9  407.14  5163.7  409.61  5307.3  415.36  5348.3  412.45
  5358.6  408.83    5370  410.56  5379.1  414.87  5410.9  416.49  5430.4  413.32
  5456.1  411.98  5504.1  415.33    5615  423.47  5633.4  427.09  5857.3  436.58
#Mann= 9 ,-1 , 0
    4245     .16       0  4270.7     .05       0  4325.3     .16       0
  4787.9     .12       0  4979.1     .07       0  5010.3     .12       0
  5063.7     .05       0  5410.9     .16       0  5504.1     .05       0
#XS Ineff= 2 , 0
                         5306.59          415.41
Permanent Ineff=
       F       F
Bank Sta=4979.1,5010.3
XS Rating Curve= 0 ,0
Exp/Cntr=0.3,0.1

Type RM Length L Ch R = 1 ,27669   ,902,902,902
BEGIN DESCRIPTION:
COX CREEK 55.0
END DESCRIPTION:
XS GIS Cut Line= 2
      3505971.03       10482750.      3504441.16     10483129.76
#Sta/Elev= 30
  4303.6  411.49  4338.2  411.08  4500.3  408.51  4536.5  406.67    4702  402.64
  4743.3  401.97  4913.9  403.05  4955.4  400.88  4972.2  400.87  4982.5  399.31
  5002.9     393  5032.8  398.69    5038  400.78  5044.3  402.47  5058.3  403.12
  5140.4  411.77  5161.2  412.82  5239.6  419.44  5312.2  423.36  5410.2  426.23
  5469.8  425.63  5491.7  425.74  5596.4  425.64  5617.1  425.23  5622.2  422.91
  5641.9  423.14  5652.2  421.49  5663.6  425.48  5672.9  426.96  5879.9  437.83
#Mann= 11 ,-1 , 0
  4303.6     .05       0  4338.2     .16       0  4955.4     .12       0
  4972.2     .07       0    5038     .12       0  5058.3      .1       0
  5140.4     .05       0  5161.2      .1       0  5469.8     .16       0
  5491.7     .05       0  5596.4      .1       0
Bank Sta=4972.2,5038
XS Rating Curve= 0 ,0
Exp/Cntr=0.3,0.1

Type RM Length L Ch R = 1 ,26767   ,425,425,425
BEGIN DESCRIPTION:
Mapping XS 5ff501bc
END DESCRIPTION:
XS GIS Cut Line= 2
      3506242.36     10482657.07      3504979.34      10482112.8
#Sta/Elev= 30
    4570  421.44  4602.9     419  4690.1  414.78  4772.5  409.53    4872   404.6
  4877.5  404.97  4892.1  404.18    4901  403.62  4907.8  402.23  4924.5  403.29
  4953.5  402.38  4962.3  400.83  4971.5  399.55    4977  399.06  4997.5  391.58
  5000.3  391.08  5003.5  391.58    5006  395.04  5016.7  398.21  5029.5  399.96
  5086.4  400.23  5281.1  399.91  5357.1   400.8  5456.6  403.51  5542.3  406.99
    5633  412.26  5661.1  414.96  5784.2  419.75  5815.4  421.59  5945.3  427.53
#Mann= 9 ,-1 , 0
    4570     .05       0  4892.1      .1       0  4962.3     .12       0
  4971.5     .07       0  5029.5     .12       0  5086.4     .05       0
  5542.3      .1       0    5633     .05       0  5815.4     .16       0
Bank Sta=4971.5,5029.5
XS Rating Curve= 0 ,0
Exp/Cntr=0.3,0.1

Type RM Length L Ch R = 1 ,26342   ,661,661,661
BEGIN DESCRIPTION:
COX CREEK 50.0
END DESCRIPTION:
XS GIS Cut Line= 3
      3506392.11     10482491.65      3505992.11     10482141.64
      3505442.13     10481591.67
#Sta/Elev= 30
  4453.8  423.58  4630.8  411.97    4702   409.2  4800.7  402.59    4851  400.05
  4893.1  398.83  4914.6  398.12  4921.3  396.73  4935.5  398.37    4964  397.71
  4971.6  398.39    4982  396.81  4988.9  396.81  4996.5  390.79  4999.2  390.29
  5013.6  394.24  5027.7  399.24  5044.4  398.71  5070.2   398.1  5211.6  398.47
  5239.9  397.72  5296.4  398.58  5338.9  398.47  5429.3  401.48  5494.4  404.87
  5508.6  406.81  5536.9  408.27  5678.3  420.99  5734.8  425.11  5763.1  425.89
#Mann= 7 ,-1 , 0
  4453.8     .05       0  4893.1      .1       0  4988.9     .07       0
  5027.7      .1       0  5044.4     .05       0  5429.3      .1       0
  5536.9     .16       0
Bank Sta=4988.9,5027.7
XS Rating Curve= 0 ,0
Exp/Cntr=0.3,0.1

Type RM Length L Ch R = 1 ,25681   ,1322,1322,1322
BEGIN DESCRIPTION:
COX CREEK 48.0
END DESCRIPTION:
XS GIS Cut Line= 2
      3507175.46     10482207.44      3505505.82     10481188.31
#Sta/Elev= 30
  3905.9  430.49    3927  428.59  3985.1  427.76  4079.9  432.13  4166.2   432.3
  4228.5   430.2  4289.6  426.57  4428.4  418.73  4443.9  416.41  4480.8   414.2
  4654.9  402.86    4771  398.19  4858.8   396.5    4976  396.54    4982  392.03
  5003.1  390.01  5006.4  390.51  5011.1  393.61  5018.8  396.35  5024.7  396.67
  5070.8  395.98  5183.9  395.84  5219.9  397.13  5287.9  400.99  5498.9  418.83
    5557  421.94  5562.8  421.24  5651.8  423.71  5746.7  424.37    5862  422.64
#Mann= 11 ,-1 , 0
  3905.9     .16       0  4166.2     .05       0  4228.5     .16       0
  4289.6     .05       0  4480.8     .16       0  4858.8     .12       0
    4976     .07       0  5018.8     .12       0  5070.8     .05       0
  5183.9      .1       0  5219.9     .16       0
Bank Sta=4976,5024.7
XS Rating Curve= 0 ,0
Exp/Cntr=0.3,0.1

Type RM Length L Ch R = 1 ,24359   ,1910,1910,1910
BEGIN DESCRIPTION:
COX CREEK 46.0
END DESCRIPTION:
XS GIS Cut Line= 2
       3507804.8     10480927.07       3505569.6     10480134.98
#Sta/Elev= 30
    3809  421.24  4097.3  413.01  4199.3  408.15  4261.1  407.12  4310.5  403.98
  4502.8  397.99  4590.2  397.53  4708.4  401.54  4795.7  399.69  4859.2   395.9
  4904.6  393.61    4981  393.36  4989.5  389.66  4999.9  387.97  5003.1  388.47
  5006.6  392.23  5011.9  391.48  5021.3  394.16  5037.5  393.83    5066  393.19
  5272.9  392.44  5376.3  393.28  5479.7  398.49  5546.6  403.41  5577.5  403.15
  5603.1  405.99  5757.5  408.44  5829.9  411.12  6024.8     419  6180.4  416.49
#Mann= 11 ,-1 , 0
    3809     .05       0  4097.3     .16       0  4859.2     .12       0
    4981     .07       0  5021.3     .12       0  5037.5     .16       0
    5066     .05       0  5272.9      .1       0  5376.3     .05       0
  5479.7     .16       0  5829.9      .1       0
#XS Ineff= 2 , 0
         4708.52  401.52
Permanent Ineff=
       F       F
Bank Sta=4981,5021.3
XS Rating Curve= 0 ,0
Exp/Cntr=0.3,0.1

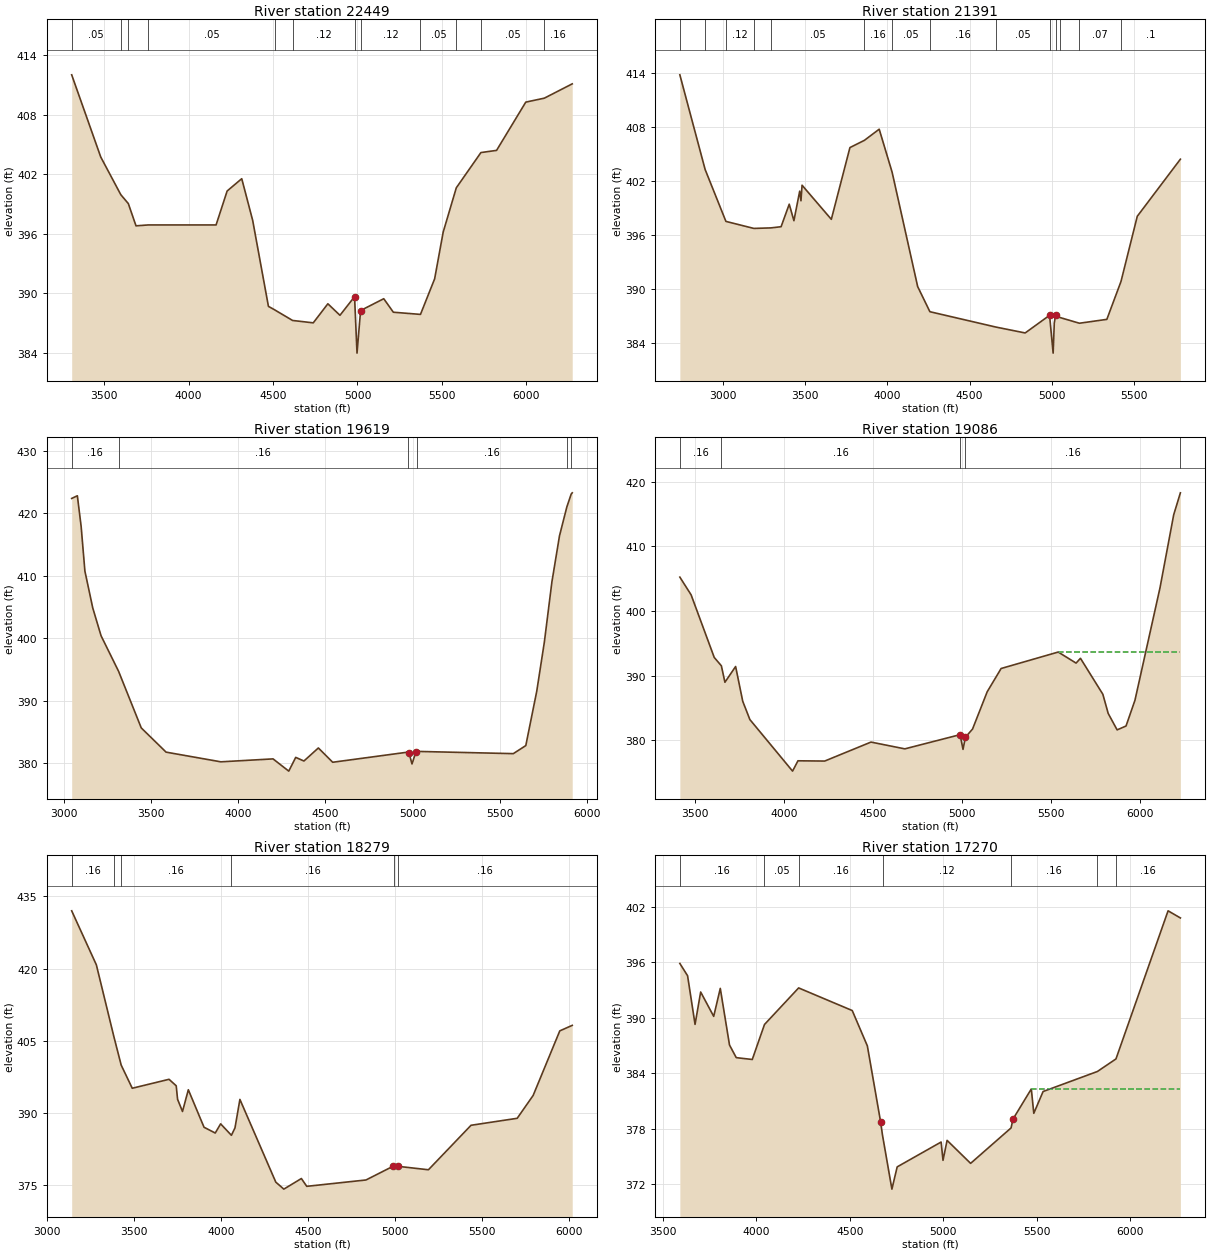
Type RM Length L Ch R = 1 ,22449   ,1058,1058,1058
BEGIN DESCRIPTION:
COX CREEK 42.0
END DESCRIPTION:
XS GIS Cut Line= 2
      3508010.96     10479983.04       3505580.4     10478290.34
#Sta/Elev= 30
  3308.8  412.01  3480.8  403.73  3599.4  399.94    3644  399.04  3689.4   396.8
  3761.3  396.89  4163.2  396.89  4228.7  400.31  4315.1  401.55  4379.8  397.35
    4473  388.69  4509.7  388.34  4615.8  387.27  4738.3  387.03  4824.7  388.95
  4896.3  387.79  4982.7  389.67  4997.2  383.98  5018.4  388.27  5155.4  389.46
  5212.2   388.1  5372.7  387.88  5456.5  391.46  5507.1  396.17  5584.7  400.63
  5730.4  404.18    5823   404.4  5995.8  409.26  6105.8  409.66  6270.7   411.1
#Mann= 12 ,-1 , 0
  3308.8     .05       0  3599.4      .1       0    3644     .12       0
  3761.3     .05       0  4509.7     .16       0  4615.8     .12       0
  4982.7     .07       0  5018.4     .12       0  5372.7     .05       0
  5584.7      .1       0  5730.4     .05       0  6105.8     .16       0
Bank Sta=4982.7,5018.4
XS Rating Curve= 0 ,0
Exp/Cntr=0.3,0.1

Type RM Length L Ch R = 1 ,21391   ,1772,1772,1772
BEGIN DESCRIPTION:
COX CREEK 41.0
END DESCRIPTION:
XS GIS Cut Line= 3
      3508260.57      10479559.9      3506198.93     10477780.38
      3505950.34     10477585.83
#Sta/Elev= 30
  2740.7   413.8  2894.1  403.29  3020.4  397.52  3190.2  396.74  3293.7   396.8
  3355.4  396.93  3404.8  399.43  3433.3   397.6  3468.4  400.88  3476.1  399.81
  3482.7  401.54  3660.4  397.75  3773.4  405.72  3861.7  406.53  3951.1  407.76
  4029.6  402.98  4184.7  390.28  4258.9  387.49  4658.4  385.79  4837.4  385.13
  4985.5  387.09  5007.2  382.89  5014.1  386.22  5021.7  387.07  5047.7  386.85
  5166.8  386.21  5333.3  386.64  5419.4  390.86  5518.1  398.09  5779.8  404.43
#Mann= 14 ,-1 , 0
  2740.7     .05       0  2894.1      .1       0  3020.4     .12       0
  3190.2      .1       0  3293.7     .05       0  3861.7     .16       0
  4029.6     .05       0  4258.9     .16       0  4658.4     .05       0
  4985.5    .035       0  5021.7     .05       0  5047.7      .1       0
  5166.8     .07       0  5419.4      .1       0
Bank Sta=4985.5,5021.7
XS Rating Curve= 0 ,0
Exp/Cntr=0.3,0.1

Type RM Length L Ch R = 1 ,19619   ,533,533,533
BEGIN DESCRIPTION:
COX CREEK 39.0
END DESCRIPTION:
XS GIS Cut Line= 3
       3508792.1     10477591.64      3506992.11     10476841.64
      3506092.06     10476641.63
#Sta/Elev= 30
    3044  422.41  3076.5  422.84  3098.2  417.93  3119.8  410.77  3164.8  404.88
  3212.5  400.42  3313.2  394.72  3443.2  385.66  3585.7  381.78  3899.8  380.23
  4199.4   380.7  4289.6  378.74  4329.4  380.94  4376.5  380.36  4459.4  382.45
  4541.6  380.16  4972.3  381.78  4979.4  381.66  4996.6  379.89  5018.3  381.74
  5024.7   381.9  5577.9  381.54  5649.6  382.83  5712.4  391.53  5755.9  399.37
  5799.4  409.05    5843  416.43  5885.2  421.06  5910.1  423.11    5916  423.31
#Mann= 6 ,-1 , 0
    3044     .16       0  3313.2     .16       0  4972.3     .12       0
  5024.7     .16       0  5885.2     .05       0  5910.1     .16       0
Bank Sta=4979.4,5018.3
XS Rating Curve= 0 ,0
Exp/Cntr=0.3,0.1

Type RM Length L Ch R = 1 ,19086   ,807,807,807
BEGIN DESCRIPTION:
Mapping XS af6a6b47
END DESCRIPTION:
XS GIS Cut Line= 3
       3508915.2     10476537.41      3507369.61     10476470.11
      3506107.62     10476373.96
#Sta/Elev= 30
  3413.1  405.25  3476.3  402.51  3606.4   392.8  3646.4  391.51  3666.4  388.96
  3726.5   391.4  3766.5  386.01  3806.6  383.18  4046.5  375.19  4076.8  376.79
    4227  376.75  4487.2  379.69  4677.4  378.64  4987.7  380.84  5004.3  378.56
  5017.8  380.44  5057.9  381.71  5140.3  387.49  5218.4  391.09  5539.3  393.64
  5639.6  391.93  5664.3  392.67  5790.1   387.1  5820.1  384.13  5870.3  381.58
  5920.4  382.18  5970.6  386.18    6111  403.56  6188.3  414.92  6225.8  418.31
#Mann= 5 ,-1 , 0
  3413.1     .16       0  3646.4     .16       0  4987.7     .12       0
  5017.8     .16       0  6225.8     .05       0
#XS Ineff= 2 , 0
       0                 5543.47       0  393.72
Permanent Ineff=
       F       T
Bank Sta=4987.7,5017.8
XS Rating Curve= 0 ,0
Exp/Cntr=0.3,0.1

Type RM Length L Ch R = 1 ,18279   ,1009,1009,1009
BEGIN DESCRIPTION:
COX CREEK 36.0
END DESCRIPTION:
XS GIS Cut Line= 3
       3509192.1     10475291.64      3507392.11     10475741.64
       3506392.1     10475941.64
#Sta/Elev= 30
  3140.6  431.99  3282.3  420.77  3382.8  405.88  3424.8  399.96  3488.5  395.14
  3699.8     397    3741  395.65  3748.8  392.85  3777.1  390.32  3810.6  394.83
  3900.8  387.04  3965.2  385.84  3996.1  387.75    4058  385.37  4078.6  386.91
  4106.9  392.82  4313.1  375.64  4359.2  374.19    4460  376.39  4490.9  374.77
  4831.1  376.09  4985.7  378.92  4993.4  378.61  5016.4  378.92  5189.8  378.21
  5434.5  387.45  5699.7   388.9  5791.4  393.65  5944.4  407.06  6015.8   408.2
#Mann= 6 ,-1 , 0
  3140.6     .16       0  3382.8     .05       0  3424.8     .16       0
    4058     .16       0  4993.4     .12       0  5016.4     .16       0
Bank Sta=4985.7,5016.4
XS Rating Curve= 0 ,0
Exp/Cntr=0.3,0.1

Type RM Length L Ch R = 1 ,17270   ,418,418,418
BEGIN DESCRIPTION:
COX CREEK 34.0
END DESCRIPTION:
XS GIS Cut Line= 4
      3508523.46     10475186.69      3508377.59     10475190.16
      3507663.77     10474915.79      3505916.95     10474644.55
#Sta/Elev= 30
  3591.1  395.89  3632.5  394.56  3672.5  389.29  3702.5   392.8  3772.2  390.16
  3807.5  393.19  3856.8  387.06  3892.9  385.69  3978.6  385.49    4044  389.28
  4226.7  393.24  4513.6  390.79  4594.5  386.96  4665.3  378.75  4675.5  377.29
  4725.8  371.45  4754.1  373.86  4989.2  376.55  4999.3  374.57  5021.1  376.73
    5147  374.24  5363.6  378.08  5373.7  379.03  5471.8   382.3  5485.1  379.66
  5534.8  382.02  5825.4  384.19  5924.8  385.55  6203.6  401.59  6269.5  400.82
#Mann= 7 ,-1 , 0
  3591.1     .16       0    4044     .05       0  4226.7     .16       0
  4675.5     .12       0  5363.6     .16       0  5825.4     .12       0
  5924.8     .16       0
#XS Ineff= 2 , 0
       0                 5470.45       0  382.31
Permanent Ineff=
       F       T
Bank Sta=4665.3,5373.7
XS Rating Curve= 0 ,0
Exp/Cntr=0.3,0.1

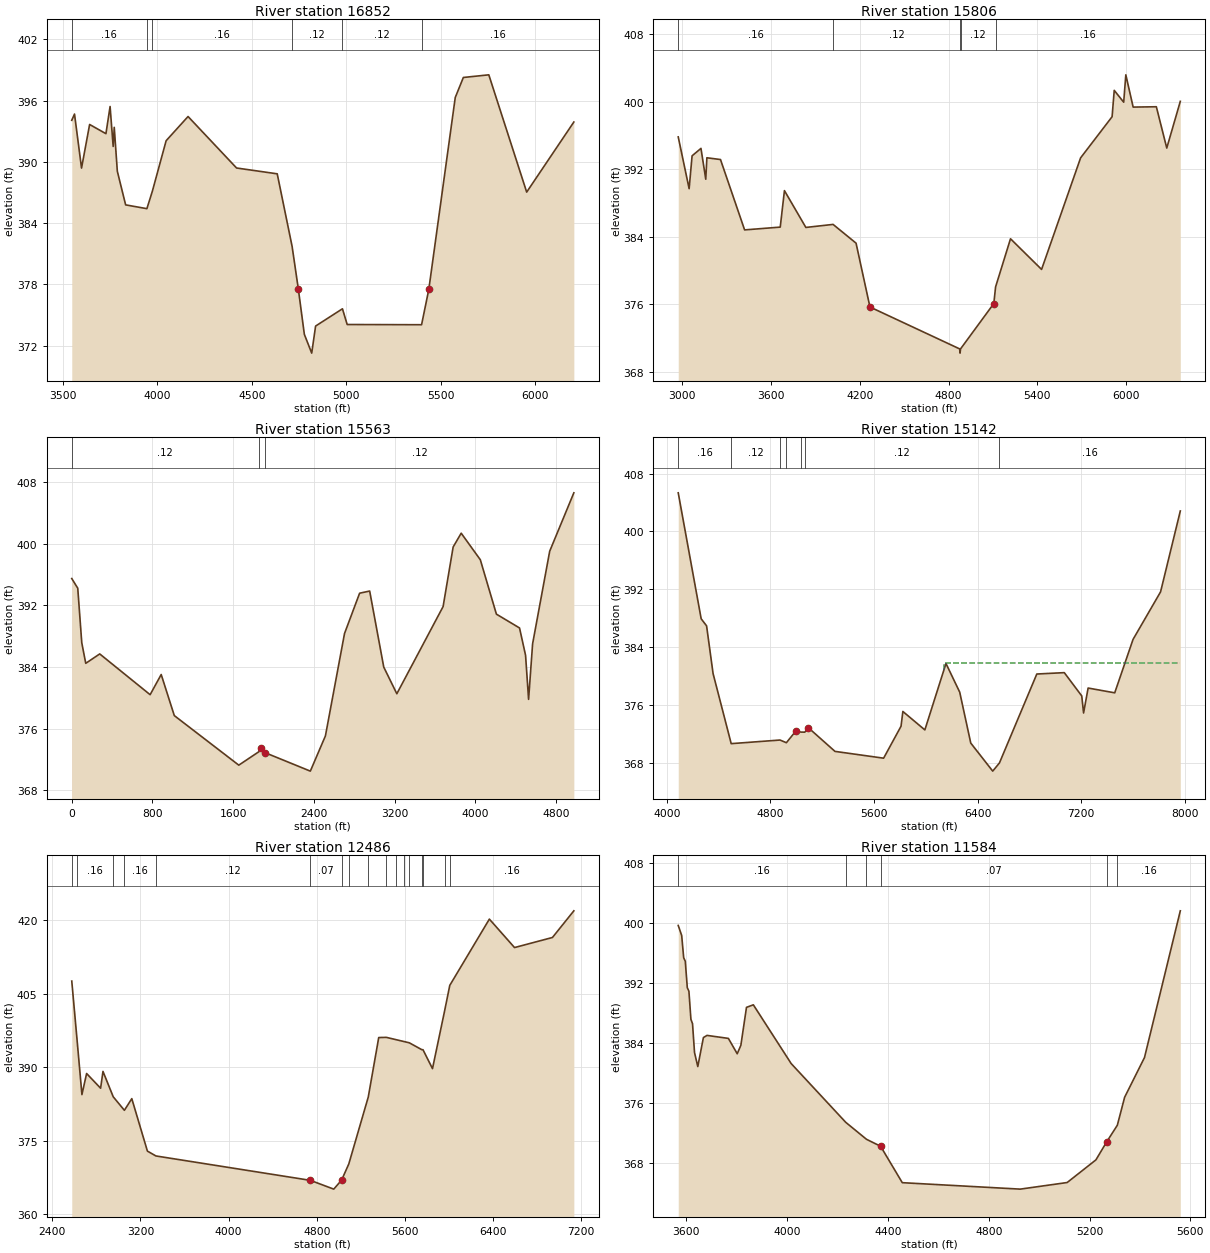
Type RM Length L Ch R = 1 ,16852   ,1046,1046,1046
BEGIN DESCRIPTION:
Mapping XS 8dbc1a70
END DESCRIPTION:
XS GIS Cut Line= 5
      3508486.56     10475148.06       3508321.6     10475143.72
       3507961.3     10474952.83      3507697.42     10474616.03
      3506066.29     10474327.98
#Sta/Elev= 30
  3547.4  394.07  3561.9  394.68  3599.1  389.39  3641.9  393.66  3728.2  392.76
  3750.2  395.42  3766.5  391.51  3772.2  393.38  3788.5  389.08  3832.5  385.79
    3945  385.42  3974.1  387.14  4046.8  392.07  4162.8  394.44  4419.5   389.4
  4634.7  388.83  4713.6  381.71  4746.4  377.55  4778.2  373.12  4817.2  371.28
  4837.8  373.93  4979.9  375.62  5004.9  374.08  5398.6  374.06  5436.9  377.52
  5576.8   396.3  5619.7  398.26  5754.4  398.52  5954.8  387.04  6204.4   393.9
#Mann= 6 ,-1 , 0
  3547.4     .16       0    3945     .05       0  3974.1     .16       0
  4713.6     .12       0  4979.9     .12       0  5398.6     .16       0
Bank Sta=4746.4,5436.9
XS Rating Curve= 0 ,0
Exp/Cntr=0.3,0.1

Type RM Length L Ch R = 1 ,15806   ,203,203,203
BEGIN DESCRIPTION:
COX CREEK 31.0
END DESCRIPTION:
XS GIS Cut Line= 5
      3508495.66     10475113.77      3508317.26     10475117.68
      3507912.11     10474753.12      3506981.56     10473298.26
      3506250.23     10472705.58
#Sta/Elev= 30
  2974.1  395.83  3047.7   389.7  3067.7  393.59  3127.7  394.47  3160.1  390.82
  3167.6  393.36  3259.6  393.15  3422.5  384.82  3663.2  385.15  3691.6  389.47
  3836.3  385.11  4020.2  385.47  4175.4  383.25  4269.3  375.69  4875.3  370.73
    4878  370.23  4881.3  370.73    5106   376.1    5118  378.07  5218.8  383.77
  5428.7  380.14  5692.4  393.35  5905.1  398.22  5919.5  401.34  5983.4  399.94
  5997.8  403.18  6047.3  399.36    6204   399.4  6274.4  394.51  6365.9  400.04
#Mann= 5 ,-1 , 0
  2974.1     .16       0  4020.2     .12       0  4875.3     .07       0
  4881.3     .12       0    5118     .16       0
Bank Sta=4269.3,5106
XS Rating Curve= 0 ,0
Exp/Cntr=0.3,0.1

Type RM Length L Ch R = 1 ,15563   ,461,461,461
XS GIS Cut Line= 4
     3508450.075    10474958.282     3508189.659    10474848.907
     3507135.839    10473096.014     3505040.353    10471439.764
#Sta/Elev= 30
       0395.4764 59.4121394.218699.02016387.1489138.6282384.4672277.2565385.6887
776.8487380.3945 886.759383.01521016.653377.68011656.131371.24471855.968372.9965
1875.952373.44041915.919372.86972365.454370.46932515.039375.04362704.513388.3411
2854.097393.57392953.821393.85383093.433383.97893223.073380.51443681.799391.8335
3781.522399.5729  3861.3401.36644050.774397.92194210.331390.85474439.694 389.059
4499.528385.51114529.445379.78524569.334387.00214738.863399.02794978.199406.6077
#Mann= 3 ,-1 , 0
       0     .12       01855.968     .07       01915.919     .12       0
Bank Sta=1875.952,1915.919
XS Rating Curve= 0 ,0
Exp/Cntr=0.3,0.1

Type RM Length L Ch R = 1 ,15142   ,2656,2656,2656
BEGIN DESCRIPTION:
Mapping XS ac4d91be
END DESCRIPTION:
XS GIS Cut Line= 2
       3508165.3     10473688.08      3505262.96     10471115.45
#Sta/Elev= 30
  4087.6  405.34  4264.8  387.92  4306.6  386.94  4356.8  380.34  4496.8  370.65
  4873.7  371.15    4923  370.78  4994.1  372.35  5036.8  372.25  5065.2  372.24
  5093.6  372.84  5298.5  369.58  5674.1  368.64  5808.7  373.06  5822.9   375.1
  5992.7  372.55  6155.8  381.74    6262  377.77  6347.3  370.73  6516.9  366.85
  6568.8  367.98  6857.5  380.28  7069.9  380.47  7204.6  377.25  7218.8  374.89
  7253.9  378.34  7459.4  377.68    7601  385.07  7813.5  391.64    7966  402.83
#Mann= 7 ,-1 , 0
  4087.6     .16       0  4496.8     .12       0  4873.7     .16       0
    4923     .12       0  5036.8     .07       0  5065.2     .12       0
  6568.8     .16       0
#XS Ineff= 2 , 0
                         6140.91          381.78
Permanent Ineff=
       F       F
Bank Sta=4994.1,5093.6
XS Rating Curve= 0 ,0
Exp/Cntr=0.3,0.1

Type RM Length L Ch R = 1 ,12486   ,902,902,902
BEGIN DESCRIPTION:
COX CREEK 26.0
END DESCRIPTION:
XS GIS Cut Line= 3
       3508642.1     10472991.64      3506842.11     10471341.64
      3505612.96     10469620.62
#Sta/Elev= 30
  2576.3  407.56  2620.4  396.55  2668.5  384.39    2711  388.69  2838.1  385.69
  2859.6  389.12  2952.8  383.93  3053.9  381.18  3121.1  383.56  3262.9  372.85
  3340.2  371.86  4742.2  366.88    4954  365.09  5025.5  366.94  5090.6  370.23
  5267.3  383.89  5362.2  396.03  5431.4  396.07  5515.5  395.62  5592.6  395.21
  5639.6  394.96  5753.7  393.55  5763.7  393.55  5850.1  389.69  5959.7  401.43
    6007  406.68  6366.3  420.21  6594.8   414.4  6938.9  416.46    7133   421.9
#Mann= 17 ,-1 , 0
  2576.3      .1       0  2620.4     .16       0  2952.8     .12       0
  3053.9     .16       0  3340.2     .12       0  4742.2     .07       0
  5025.5     .12       0  5090.6     .16       0  5267.3     .05       0
  5431.4      .1       0  5515.5     .05       0  5592.6      .1       0
  5639.6     .05       0  5753.7      .1       0  5763.7     .16       0
  5959.7      .1       0    6007     .16       0
Bank Sta=4742.2,5025.5
XS Rating Curve= 0 ,0
Exp/Cntr=0.3,0.1

Type RM Length L Ch R = 1 ,11584   ,996,996,996
BEGIN DESCRIPTION:
COX CREEK 24.0
END DESCRIPTION:
XS GIS Cut Line= 3
      3508742.14     10471891.67      3507642.11     10470991.64
       3507192.1     10470641.64
#Sta/Elev= 30
  3568.6  399.71  3582.3  398.37  3590.2   395.4  3596.6  394.93  3604.5  391.41
    3611  390.93  3618.9  387.18  3625.3   386.6  3633.2  382.75  3646.2  380.88
  3668.4  384.75  3682.8  385.04  3767.5  384.64  3802.6  382.59    3817  383.72
  3839.3  388.78  3866.5  389.12  4016.6  381.28  4233.1  373.44  4315.2  371.18
  4371.2  370.25  4457.3  365.39  4925.1  364.53  5111.2  365.41  5225.2  368.43
  5268.6  370.87  5310.2  373.05  5339.2  376.79  5417.9  382.08    5560  401.66
#Mann= 6 ,-1 , 0
  3568.6     .16       0  4233.1     .12       0  4315.2     .07       0
  4371.2     .07       0  5268.6     .07       0  5310.2     .16       0
Bank Sta=4371.2,5268.6
XS Rating Curve= 0 ,0
Exp/Cntr=0.3,0.1