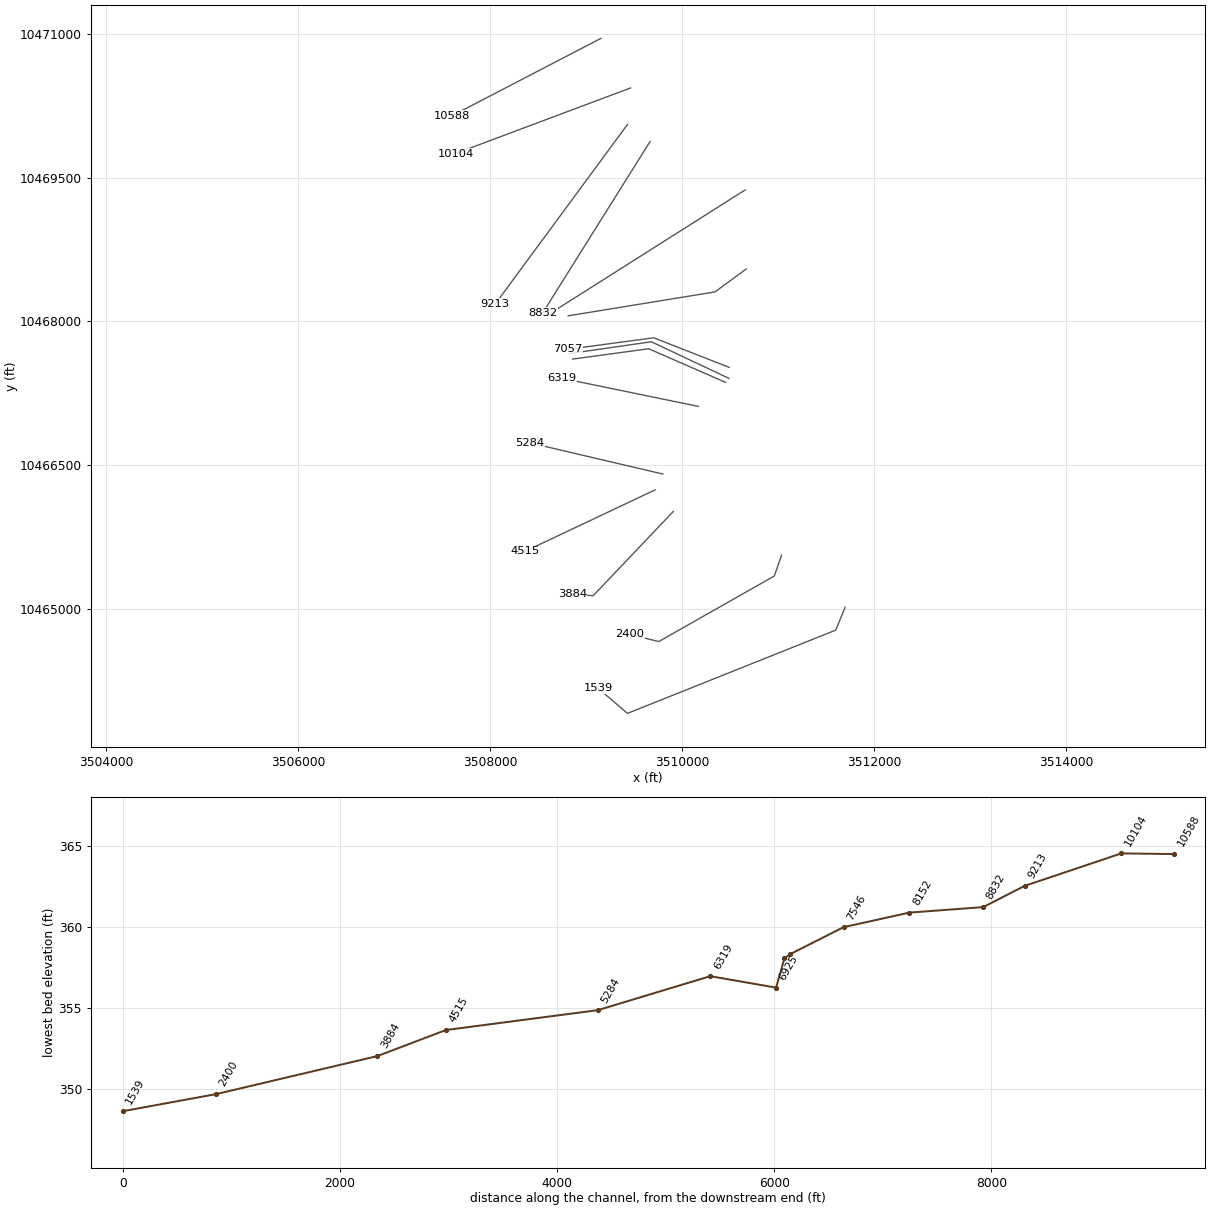
HEC-RAS study COX CREEK.prj: COX CREEK Base Level Engineering

--- COX CREEK.g01 (geometry) --- (continued)

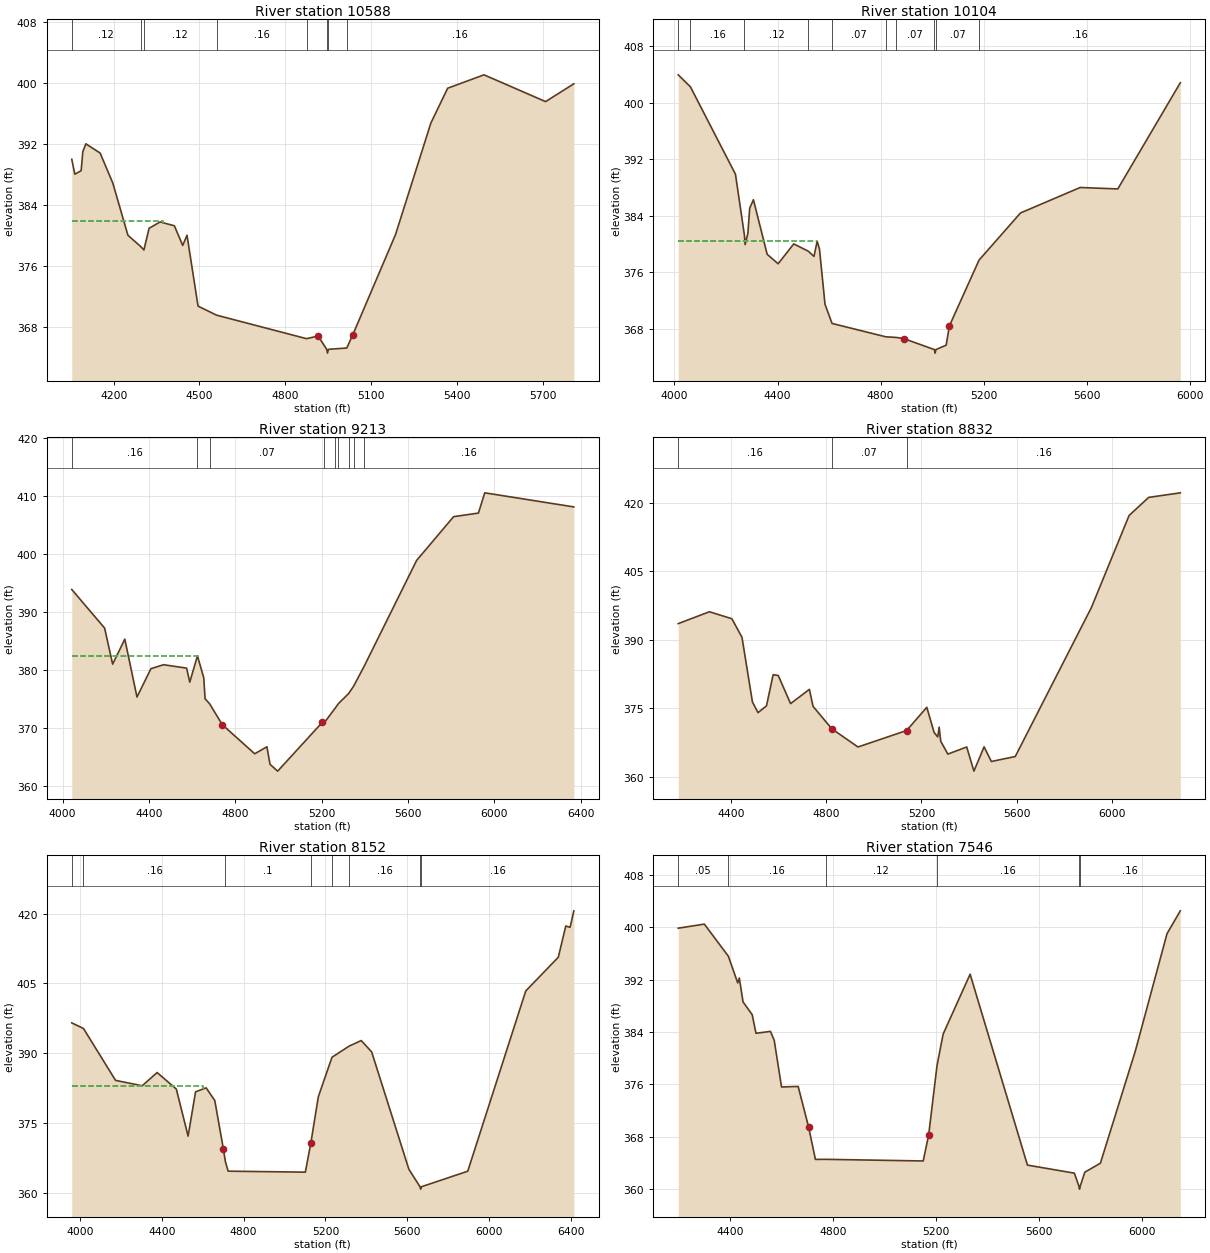
Type RM Length L Ch R = 1 ,10588   ,484,484,484
BEGIN DESCRIPTION:
COX CREEK 22.0
END DESCRIPTION:
XS GIS Cut Line= 2
      3509156.32     10470951.73      3507598.65     10470141.48
#Sta/Elev= 30
  4053.6     390  4064.3  388.04  4086.4   388.5  4092.2  390.99  4102.9  392.03
  4152.7  390.82    4197  386.89    4250  380.01  4294.2  378.55  4305.9  378.08
    4324  380.93  4362.5  381.76  4412.4  381.26  4441.6  378.67  4456.6  380.02
  4495.2   370.7    4560  369.51  4874.6  366.42  4915.2  366.76  4945.1  365.02
  4947.9  364.52  4951.1  365.02  5015.3  365.19  5036.6  366.95  5185.6  380.08
  5309.5  394.77  5368.2  399.34  5495.2   401.1  5710.6  397.58  5809.4  399.92
#Mann= 8 ,-1 , 0
  4053.6     .12       0  4294.2     .16       0  4305.9     .12       0
    4560     .16       0  4874.6     .07       0  4945.1     .07       0
  4951.1     .07       0  5015.3     .16       0
#XS Ineff= 2 , 0
         4374.36  381.85
Permanent Ineff=
       F       F
Bank Sta=4915.2,5036.6
XS Rating Curve= 0 ,0
Exp/Cntr=0.3,0.1

Type RM Length L Ch R = 1 ,10104   ,891,891,891
BEGIN DESCRIPTION:
COX CREEK 20.0
END DESCRIPTION:
XS GIS Cut Line= 2
      3509465.03     10470434.47      3507642.09     10469750.87
#Sta/Elev= 30
    4015  403.93  4062.1  402.24  4236.9  389.87  4271.9  381.18  4274.4  379.91
  4285.1   381.5    4292  385.04  4306.5  386.26  4359.9  378.54  4402.4   377.2
  4462.9  380.01  4519.3  378.98  4541.4  378.24  4553.7  380.39  4562.8  379.27
  4584.2  371.46  4611.5  368.76  4819.6  366.87  4860.1  366.78  4890.1  366.61
  5008.4  365.06  5011.1  364.56  5014.4  365.06  5054.1  365.69  5066.3   368.4
  5181.5  377.72  5342.2  384.39  5573.6  387.99  5719.6  387.79  5961.9  402.81
#Mann= 10 ,-1 , 0
    4015     .05       0  4062.1     .16       0  4271.9     .12       0
  4519.3     .16       0  4611.5     .07       0  4819.6     .16       0
  4860.1     .07       0  5008.4     .07       0  5014.4     .07       0
  5181.5     .16       0
#XS Ineff= 2 , 0
         4553.83  380.38
Permanent Ineff=
       F       F
Bank Sta=4890.1,5066.3
XS Rating Curve= 0 ,0
Exp/Cntr=0.3,0.1

Type RM Length L Ch R = 1 ,9213    ,381,381,381
BEGIN DESCRIPTION:
COX CREEK 19.0
END DESCRIPTION:
XS GIS Cut Line= 2
      3509433.02     10470054.12      3508054.68     10468181.37
#Sta/Elev= 30
  4042.5  393.87  4194.6  387.22  4231.8  380.99  4288.2  385.31  4344.5  375.33
  4409.3  380.22  4467.7   380.9  4574.4  380.31    4589  377.89  4624.5  382.43
  4653.8  378.64    4660  375.02  4680.9  374.17  4739.4  370.57  4889.8  365.54
  4946.2  366.75  4960.8  363.72  4996.1  362.55  5203.1  370.97  5211.5  370.88
  5261.7  373.37  5277.7   374.2  5324.5  375.92  5347.3  377.16  5397.4  380.68
  5639.7  398.89    5811  406.43  5925.9  407.05  5955.2  410.54  6367.8  408.11
#Mann= 9 ,-1 , 0
  4042.5     .16       0  4624.5     .12       0  4680.9     .07       0
  5211.5     .12       0  5261.7     .16       0  5277.7     .12       0
  5324.5     .16       0  5347.3     .12       0  5397.4     .16       0
#XS Ineff= 2 , 0
         4627.84  382.38
Permanent Ineff=
       F       F
Bank Sta=4739.4,5203.1
XS Rating Curve= 0 ,0
Exp/Cntr=0.3,0.1

Type RM Length L Ch R = 1 ,8832    ,680,680,680
BEGIN DESCRIPTION:
COX CREEK 18.0
END DESCRIPTION:
XS GIS Cut Line= 2
      3509667.75     10469875.59      3508549.62      10468089.4
#Sta/Elev= 30
    4179  393.55  4309.8  396.15  4404.1  394.62  4446.6  390.55  4490.4   376.4
  4513.8  374.05  4549.4  375.54  4577.4  382.37  4598.7  382.19  4650.5  376.03
  4729.5  379.15  4744.8  375.43  4823.8   370.5  4933.4  366.53  5137.4  370.13
  5222.3  375.22  5252.9  369.71  5268.2  368.73  5274.1  370.87  5280.8  367.78
  5310.7  364.97  5389.7  366.53  5420.1  361.24  5462.7  366.56  5493.2  363.35
  5593.6  364.44  5913.1  397.07  6071.3  417.23  6153.5   421.2  6286.3   422.2
#Mann= 3 , 0 , 0
    4179     .16       0  4823.8     .07       0  5137.4     .16       0
#XS Ineff= 2 , 0
         4578.12  382.34
Permanent Ineff=
       F       F
Bank Sta=4823.8,5137.4
XS Rating Curve= 0 ,0
Exp/Cntr=0.3,0.1

Type RM Length L Ch R = 1 ,8152    ,606,606,606
BEGIN DESCRIPTION:
COX CREEK 17.0
END DESCRIPTION:
XS GIS Cut Line= 2
      3510658.54     10469371.08      3508583.26     10468055.77
#Sta/Elev= 30
  3958.8  396.55  4016.1  395.35  4173.1  384.22  4303.6  383.07  4376.5   385.9
  4470.5  382.36  4528.1  372.27  4564.6  381.77  4616.3  382.62  4658.6  379.91
    4701  369.46  4710.3  366.85  4724.1  364.75  5101.8  364.54  5128.9  370.83
  5165.4  380.71  5232.3  389.18  5316.6  391.58  5375.3  392.76  5426.4  390.33
  5608.5  365.16  5663.2   361.4  5665.9   360.9  5669.2   361.4  5896.6  364.74
  6180.4  403.39  6339.8  410.63  6376.3  417.32  6397.4  417.04  6415.8  420.58
#Mann= 8 ,-1 , 0
  3958.8     .05       0  4016.1     .16       0  4710.3      .1       0
  5128.9     .16       0  5232.3     .12       0  5316.6     .16       0
  5663.2     .07       0  5669.2     .16       0
#XS Ineff= 2 , 0
         4602.84  383.04
Permanent Ineff=
       F       F
Bank Sta=4701,5128.9
XS Rating Curve= 0 ,0
Exp/Cntr=0.3,0.1

Type RM Length L Ch R = 1 ,7546    ,489,489,489
BEGIN DESCRIPTION:
COX CREEK 14.0
END DESCRIPTION:
XS GIS Cut Line= 3
      3510669.43     10468546.45      3510343.89     10468307.72
      3508815.48     10468058.41
#Sta/Elev= 30
  4196.9  399.85  4298.5  400.47  4391.8  395.57  4428.2  391.49  4434.4  392.24
    4449  388.58  4484.5  386.64  4499.2   383.8  4555.5  384.09  4570.2  382.71
  4598.6   375.6  4663.2  375.68  4703.7  369.51  4730.3  364.54  4769.9  364.55
  5149.5   364.3  5170.6  368.26  5203.2  378.87    5227  383.68  5331.9  392.82
  5554.8  363.67  5737.2  362.44  5754.5   360.5  5757.2     360  5760.5   360.5
  5777.7  362.58  5838.5  363.96  5974.6  381.13  6097.5  399.01  6149.2   402.5
#Mann= 6 ,-1 , 0
  4196.9     .05       0  4391.8     .16       0  4769.9     .12       0
  5203.2     .16       0  5754.5     .07       0  5760.5     .16       0
Bank Sta=4703.7,5170.6
XS Rating Curve= 0 ,0
Exp/Cntr=0.3,0.1

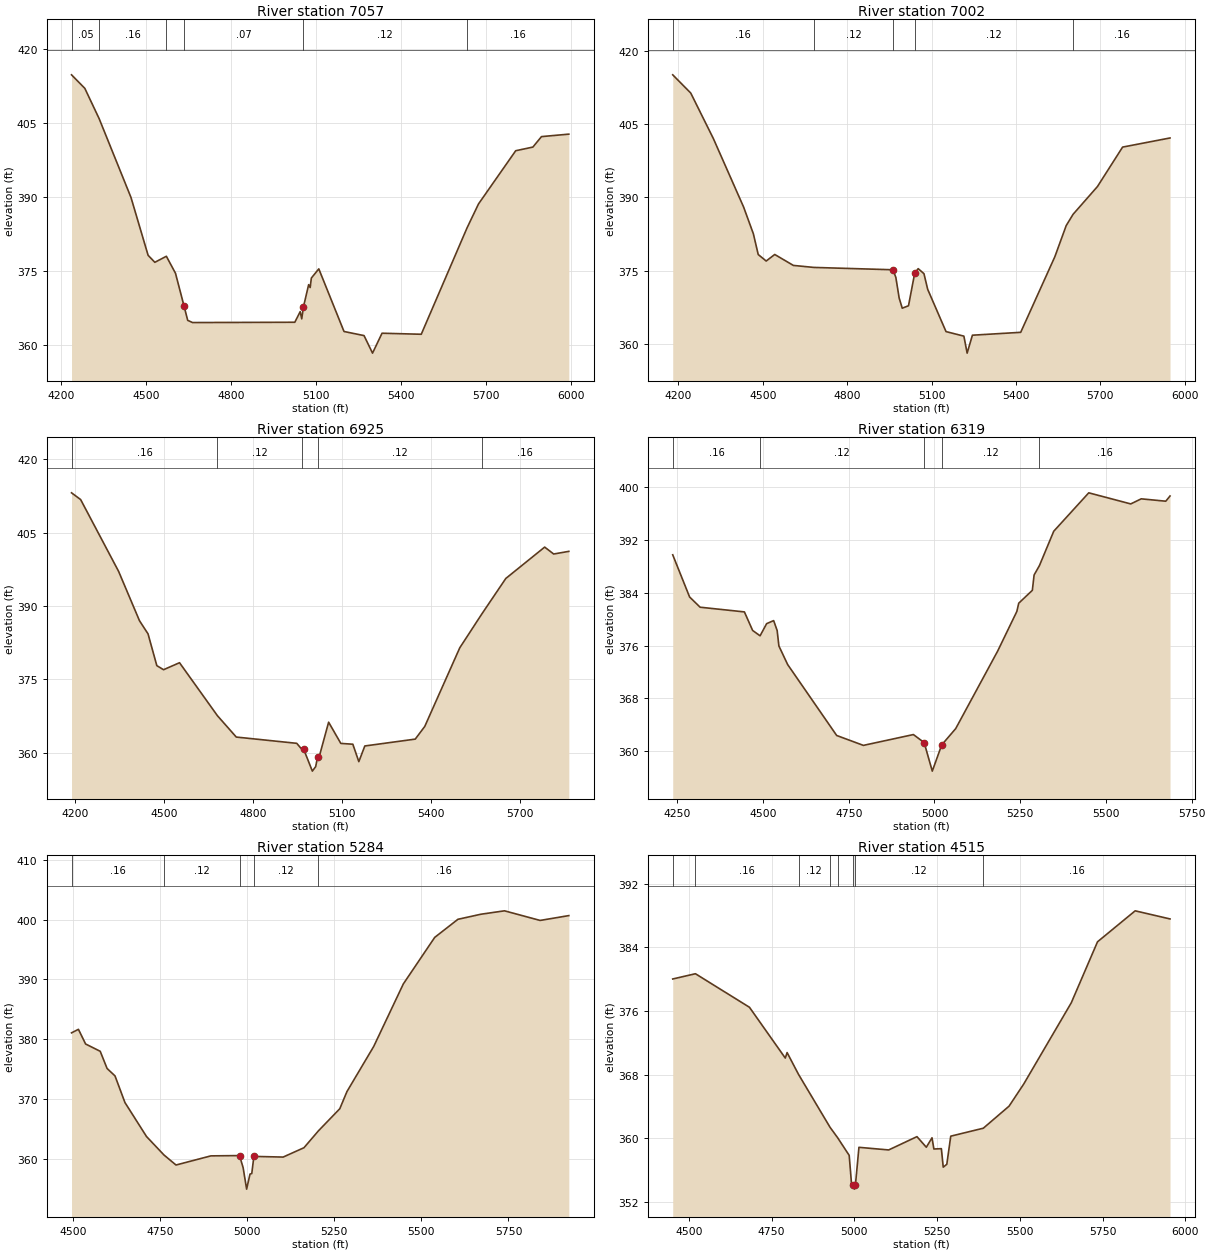
Type RM Length L Ch R = 1 ,7057    ,55,55,55
BEGIN DESCRIPTION:
Mapping XS 8fdaae13
END DESCRIPTION:
XS GIS Cut Line= 3
      3510493.45     10467520.61       3509705.3     10467829.62
      3508806.53     10467708.17
#Sta/Elev= 30
  4237.7  414.69  4284.6  411.95  4335.2   405.8  4447.3  389.87  4507.7  378.15
  4531.4  376.73  4572.1  377.95  4604.3  374.51  4634.5  367.86  4647.3  364.98
  4664.3  364.53    5025  364.59    5044  366.74  5049.4  365.28  5055.5  367.69
  5073.8   372.2  5079.2  371.62  5083.3  373.54  5109.6   375.4  5198.5  362.72
  5269.1  361.89  5299.1  358.34  5332.6  362.37  5470.9  362.16  5632.5  383.72
  5672.8  388.55  5803.9  399.32  5864.5  400.06  5894.8  402.18  5991.2  402.68
#Mann= 6 ,-1 , 0
  4237.7     .05       0  4335.2     .16       0  4572.1     .12       0
  4634.5     .07       0  5055.5     .12       0  5632.5     .16       0
Bank Sta=4634.5,5055.5
XS Rating Curve= 0 ,0
Exp/Cntr=0.3,0.1

Type RM Length L Ch R = 1 ,7002    ,77,77,77
BEGIN DESCRIPTION:
Mapping XS 476eff04
END DESCRIPTION:
XS GIS Cut Line= 3
      3510489.99     10467406.03      3509680.99     10467787.96
       3508816.8     10467663.01
#Sta/Elev= 30
  4179.9  415.07  4243.9  411.34  4324.4  402.01  4431.9  387.99  4466.5  382.53
  4483.8  378.27  4512.1  376.94  4542.5  378.28  4608.8  376.04  4681.6  375.63
  4962.7  375.15    4973   373.6  4984.8  369.37  4995.8  367.28    5018  367.78
  5040.1  374.45  5052.4  375.38    5073  374.35  5086.1  371.17  5151.4  362.49
  5214.9  361.56  5226.5  358.08  5245.2  361.75  5416.9  362.34  5538.2  377.81
  5578.6  384.19    5603   386.5  5689.7  392.19  5779.1  400.27  5947.7  402.14
#Mann= 5 ,-1 , 0
  4179.9     .16       0  4681.6     .12       0  4962.7     .07       0
  5040.1     .12       0    5603     .16       0
Bank Sta=4962.7,5040.1
XS Rating Curve= 0 ,0
Exp/Cntr=0.3,0.1

Type RM Length L Ch R = 1 ,6925    ,606,606,606
BEGIN DESCRIPTION:
Mapping XS a5ccdab9
END DESCRIPTION:
XS GIS Cut Line= 3
      3510455.25     10467364.36      3509653.21     10467715.04
      3508861.55      10467607.4
#Sta/Elev= 30
  4189.4  413.12  4220.1  411.74    4348  397.06  4418.2  386.99    4447   384.3
  4476.6  377.81  4499.3  376.98    4553  378.41  4680.4   367.6  4744.1  363.22
  4947.7  361.94  4965.6  360.66    4971  360.73  5000.2  356.26  5011.4  357.18
  5017.8  359.13  5023.3   359.2    5055  366.26  5096.1  361.92  5136.5  361.76
  5156.7   358.2  5176.9   361.4  5346.6   362.8  5378.7  365.39  5496.5  381.45
  5570.6  388.35  5651.5  395.62  5782.4  402.03  5812.7  400.62  5863.7  401.16
#Mann= 5 ,-1 , 0
  4189.4     .16       0  4680.4     .12       0  4965.6     .07       0
  5017.8     .12       0  5570.6     .16       0
Bank Sta=4971,5017.8
XS Rating Curve= 0 ,0
Exp/Cntr=0.3,0.1

Type RM Length L Ch R = 1 ,6319    ,1035,1035,1035
BEGIN DESCRIPTION:
COX CREEK 11.0
END DESCRIPTION:
XS GIS Cut Line= 2
      3510170.32     10467114.14      3508749.97     10467406.88
#Sta/Elev= 30
  4236.7  389.74  4285.9  383.35  4316.6   381.8  4445.7  381.09  4469.7  378.28
  4491.4  377.47  4510.5  379.31    4531  379.77  4541.2  378.27  4546.3  375.93
  4571.8  373.12  4714.8  362.37  4792.7  360.87  4938.5  362.51    4970  361.29
  4993.6  356.97  5021.1  360.94  5061.9  363.41  5184.4  375.17  5240.2  381.16
  5245.7  382.41  5285.4  384.36  5290.5  386.68  5306.1  388.11  5347.8  393.31
  5449.9  399.13  5572.4  397.45    5603  398.22  5674.5  397.86  5686.9  398.65
#Mann= 5 ,-1 , 0
  4236.7     .16       0  4491.4     .12       0    4970     .07       0
  5021.1     .12       0  5306.1     .16       0
Bank Sta=4970,5021.1
XS Rating Curve= 0 ,0
Exp/Cntr=0.3,0.1

Type RM Length L Ch R = 1 ,5284    ,1400,1400,1400
BEGIN DESCRIPTION:
COX CREEK 9.0
END DESCRIPTION:
XS GIS Cut Line= 2
      3509801.39     10466408.84      3508412.43     10466734.38
#Sta/Elev= 30
  4496.5  381.05  4516.3  381.64  4536.9  379.18  4578.8  377.96  4598.5  375.08
  4621.2  373.84  4649.8  369.37  4711.5  363.69  4761.7  360.59  4796.2  358.91
  4896.3  360.44  4978.5  360.49  4988.8  358.46  4998.8  354.87  5008.5  357.39
  5013.6  357.48  5019.6  360.35  5103.6  360.24  5163.4  361.81  5204.9  364.64
  5266.1  368.34  5286.6  371.21  5363.5  378.78  5448.4  389.25  5538.4  397.04
    5605  400.07  5670.9  400.92  5738.6  401.49  5840.8  399.88  5923.1  400.69
#Mann= 5 ,-1 , 0
  4496.5     .16       0  4761.7     .12       0  4978.5     .07       0
  5019.6     .12       0  5204.9     .16       0
Bank Sta=4978.5,5019.6
XS Rating Curve= 0 ,0
Exp/Cntr=0.3,0.1

Type RM Length L Ch R = 1 ,4515    ,631,631,631
BEGIN DESCRIPTION:
COX CREEK 8.0
END DESCRIPTION:
XS GIS Cut Line= 2
      3509720.83     10466243.76      3508362.35     10465601.41
#Sta/Elev= 30
    4451  380.03  4519.6  380.69  4682.8  376.48  4791.1   370.1  4796.6  370.79
  4831.1  368.05  4926.3  361.41  4948.9  360.12  4984.2  357.88  4991.6  354.14
    4997  354.14  4999.8  353.64    5003  354.14  5013.7  358.89  5103.5  358.56
    5189  360.23  5217.3   358.9  5234.5  360.09  5240.1  358.68  5262.8  358.72
  5268.4   356.4  5279.2  356.76  5291.1  360.29  5389.5  361.29  5467.3  364.06
  5511.5  366.83  5655.3  377.04  5734.6   384.7  5848.4  388.59  5953.7  387.57
#Mann= 8 ,-1 , 0
    4451     .05       0  4519.6     .16       0  4831.1     .12       0
  4926.3     .16       0  4948.9     .12       0    4997     .07       0
    5003     .12       0  5389.5     .16       0
Bank Sta=4997,5003
XS Rating Curve= 0 ,0
Exp/Cntr=0.3,0.1

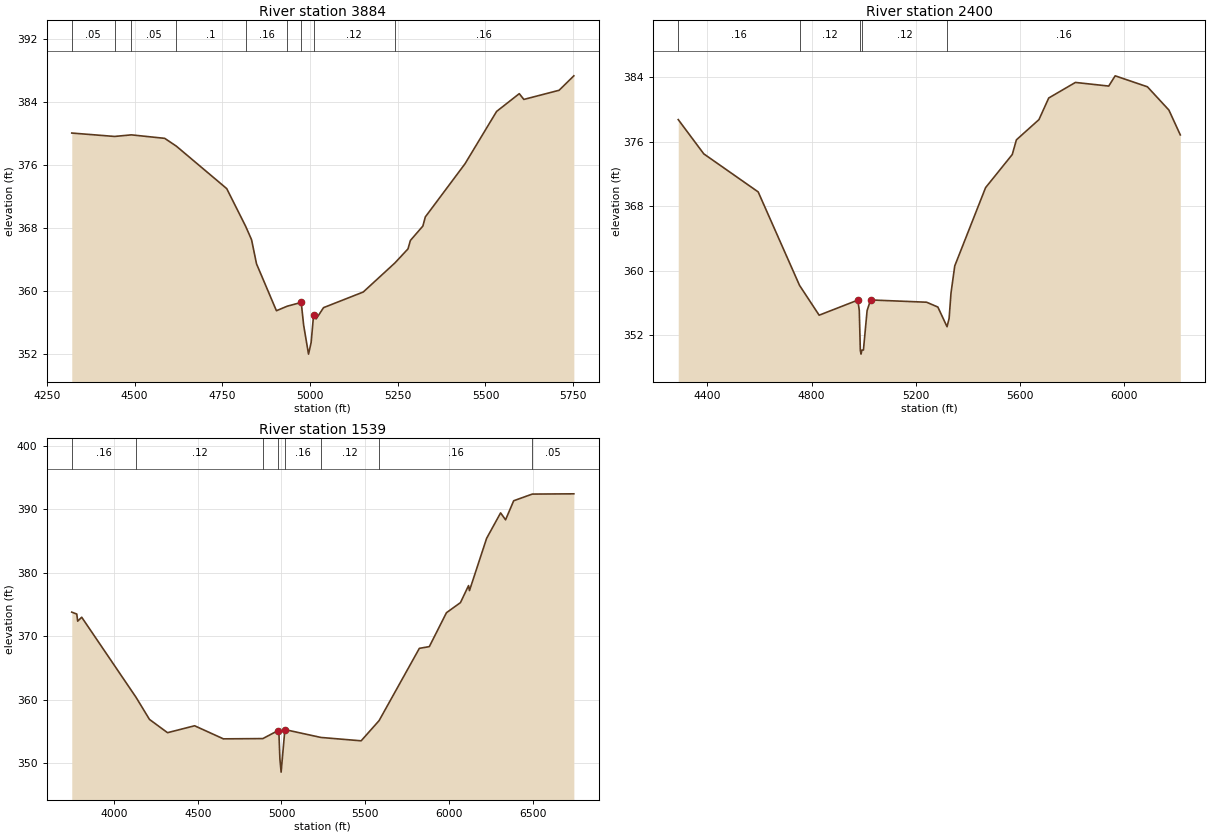
Type RM Length L Ch R = 1 ,3884    ,1484,1484,1484
BEGIN DESCRIPTION:
COX CREEK 6.0
END DESCRIPTION:
XS GIS Cut Line= 3
      3509909.89     10466018.25      3509074.36     10465139.32
      3508857.34     10465161.02
#Sta/Elev= 30
  4321.1  380.04    4443  379.61    4491  379.81  4585.9  379.37  4619.1  378.38
  4762.7     373  4816.7  368.22  4833.5  366.52  4847.6  363.47  4904.3  357.53
  4935.5  358.11    4975  358.58  4981.9   355.7  4995.8  352.03  5003.3  353.52
  5010.2  356.98  5017.5  356.49  5038.6  357.92  5151.8   359.9  5241.9  363.58
  5279.2  365.36  5286.1  366.43  5321.7  368.26  5328.6  369.41  5441.8  376.15
  5531.8  382.78  5596.4  385.03  5609.4   384.3  5709.9  385.46  5751.9  387.29
#Mann= 9 ,-1 , 0
  4321.1     .05       0    4443      .1       0    4491     .05       0
  4619.1      .1       0  4816.7     .16       0  4935.5     .12       0
    4975     .07       0  5010.2     .12       0  5241.9     .16       0
Bank Sta=4975,5010.2
XS Rating Curve= 0 ,0
Exp/Cntr=0.3,0.1

Type RM Length L Ch R = 1 ,2400    ,861,861,861
BEGIN DESCRIPTION:
COX CREEK 3.0
END DESCRIPTION:
XS GIS Cut Line= 4
      3511038.34      10465562.5      3510962.38     10465345.48
      3509757.96     10464661.89      3509455.59     10464737.48
#Sta/Elev= 30
  4288.2  378.77  4386.3  374.52    4595   369.8  4753.6  358.21  4828.9  354.51
  4977.2  356.38  4982.9  355.12  4986.9  350.18  4989.6  349.68  4992.9  350.18
  4998.8  350.19  5012.9  355.08  5026.2   356.4  5241.1  356.12  5284.4  355.52
  5319.6  353.08  5327.6  354.11  5334.8  357.25  5349.2  360.62  5467.5  370.33
  5569.9  374.44  5585.8  376.26  5672.3  378.77  5709.8  381.45  5812.2  383.38
    5940  382.93  5964.8   384.2  6088.5  382.84    6171  379.95  6214.7  376.87
#Mann= 5 ,-1 , 0
  4288.2     .16       0  4753.6     .12       0  4986.9     .07       0
  4992.9     .12       0  5319.6     .16       0
Bank Sta=4977.2,5026.2
XS Rating Curve= 0 ,0
Exp/Cntr=0.3,0.1

Type RM Length L Ch R = 1 ,1539    ,0,0,0
BEGIN DESCRIPTION:
COX CREEK 1.0
END DESCRIPTION:
XS GIS Cut Line= 4
      3511700.22     10465019.93      3511602.57     10464781.25
      3509432.43     10463913.19      3509128.65     10464173.58
#Sta/Elev= 30
  3748.8  373.81  3778.7  373.51  3784.1  372.39  3808.1  373.01  4132.7  360.38
  4212.4  356.92  4320.1  354.83  4481.6  355.92  4653.4  353.86  4888.7   353.9
  4976.5  355.12  4985.2  354.45  4990.5  350.71  4997.8  348.62  5020.2  355.32
  5235.2  354.08  5475.2  353.55  5582.2  356.73  5822.5  368.11  5881.8  368.38
  5984.1  373.72  6067.6  375.31    6116  377.99  6121.4   377.2  6223.7  385.43
  6307.2  389.44  6336.8  388.35  6385.3  391.35  6496.2   392.4  6744.1  392.44
#Mann= 8 ,-1 , 0
  3748.8     .16       0  4132.7     .12       0  4888.7     .16       0
  4976.5     .07       0  5020.2     .16       0  5235.2     .12       0
  5582.2     .16       0  6496.2     .05       0
Bank Sta=4976.5,5020.2
XS Rating Curve= 0 ,0
Exp/Cntr=0.3,0.1
Stream Node=COX CREEK       ,Reach-1         , 0 , 0 ,Upstream end
Stream Node=COX CREEK       ,Reach-1         , 0 , 1 ,Downstream end

Chan Stop Cuts=-1
Use User Specified Reach Order=0
Composite Channel Slope=5