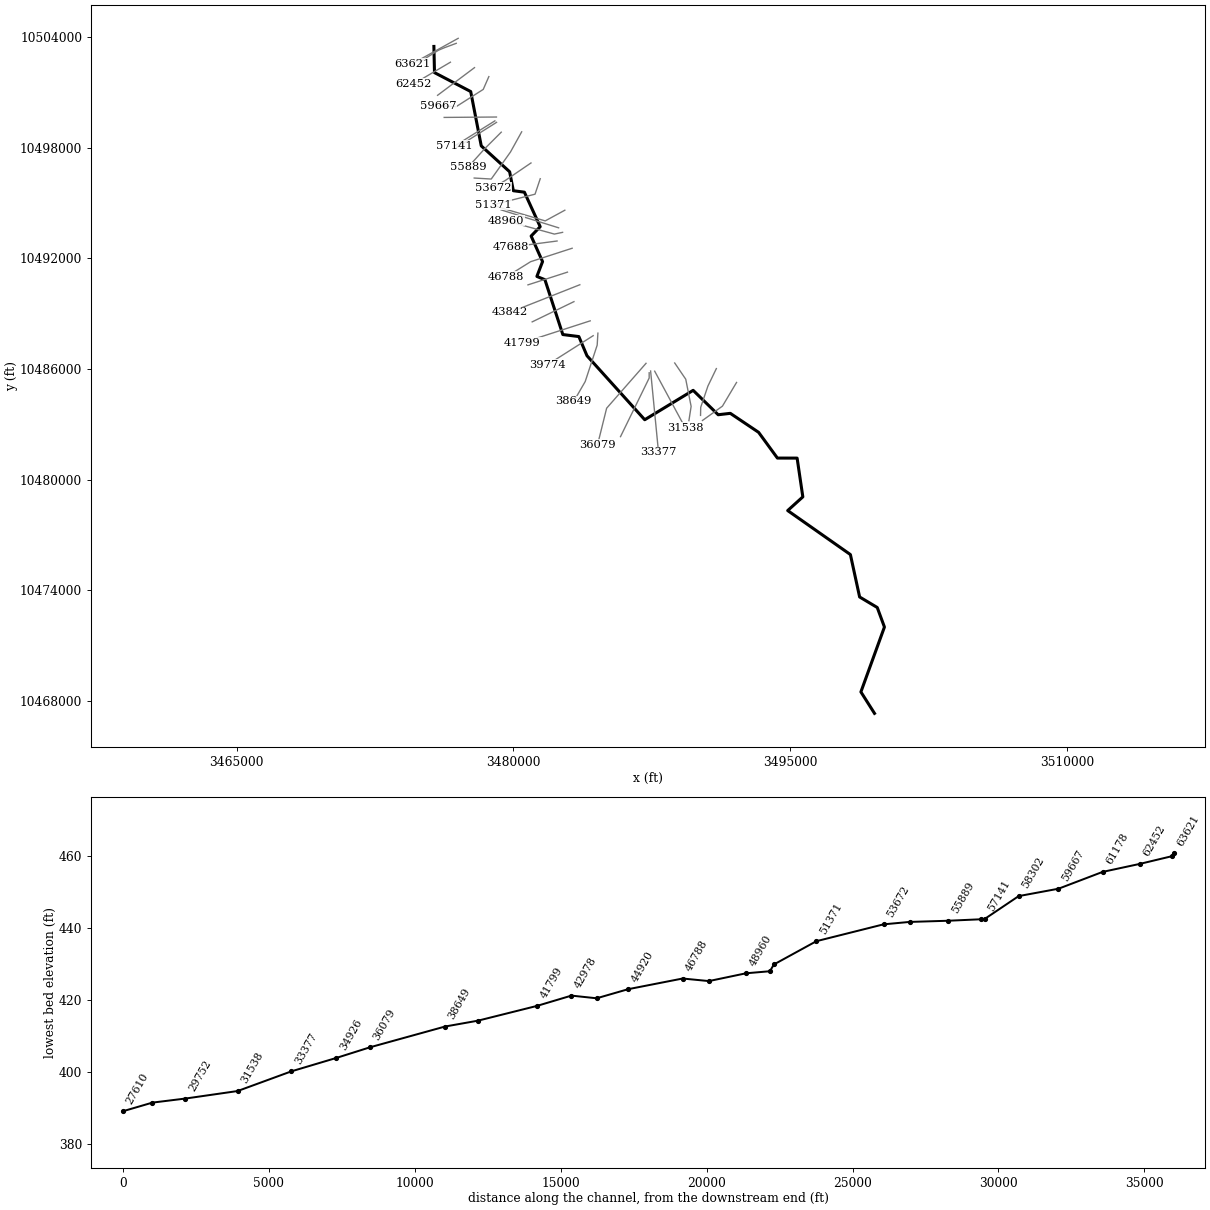
--- DAVIS CREEK.prj (project) ---

Proj Title=DAVIS CREEK Base Level Engineering
Current Plan=p01
Default Exp/Contr=0.3,0.1
English Units
Geom File=g01
Flow File=f01
Plan File=p01
Y Axis Title=Elevation
X Axis Title(PF)=Main Channel Distance
X Axis Title(XS)=Station
BEGIN DESCRIPTION:
DAVIS CREEK
END DESCRIPTION:
DSS Export Rating Curves= 0
DSS Export Rating Curve Sorted= 0
DSS Export Volume Flow Curves= 0
DXF OffsetX= 0
DXF OffsetY= 0
DXF ScaleX= 1
DXF ScaleY= 10

--- DAVIS CREEK.p01 (plan) ---

Plan Title=Multiple Run
Short Identifier=Multiple
Geom File=g01
Flow File=f01
Subcritical Flow
K Sum by GR= 0
Std Step Tol= 0.01
Critical Tol= 0.01
Num of Std Step Trials= 20
Max Error Tol= 0.3
Flow Tol Ratio= 0.001
Split Flow NTrial= 30
Split Flow Tol= 0.02
Split Flow Ratio= 0.02
Log Output Level= 0
Friction Slope Method= 1
Unsteady Friction Slope Method= 2
Unsteady Bridges Friction Slope Method= 1
Parabolic Critical Depth
Global Vel Dist=  1 , 1 , 1
Global Log Level= 0
CheckData=True
Encroach Param= -1, 0, 0, 0
BEGIN DESCRIPTION:
Multiple Run
END DESCRIPTION:

--- DAVIS CREEK.f01 (steady flow) ---

Flow Title=Multiple
Program Version=4.10
Number of Profiles= 7
Profile Names=10-year,25-year,50-year,1pct_min,100-year,1pct_plu,500-year
River Rch & RM=DAVIS CREEK,Reach-1         ,63621
    1485    2078    2574    2323    3142    4249    4670
River Rch & RM=DAVIS CREEK,Reach-1         ,62452
    1746    2457    3055    2765    3739    5056    5589
River Rch & RM=DAVIS CREEK,Reach-1         ,58302
    2584    3701    4657    4259    5759    7789    8795
River Rch & RM=DAVIS CREEK,Reach-1         ,54563
    2663    3806    4781    4363    5900    7980    8974
River Rch & RM=DAVIS CREEK,Reach-1         ,49914
    3035    4368    5512    5052    6833    9241   10484
River Rch & RM=DAVIS CREEK,Reach-1         ,47688
    3219    4631    5843    5352    7238    9788   11091
River Rch & RM=DAVIS CREEK,Reach-1         ,43842
    3356    4823    6080    5563    7523   10174   11500
River Rch & RM=DAVIS CREEK,Reach-1         ,36079
    4691    6828    8682    8006   10828   14643   16815
River Rch & RM=DAVIS CREEK,Reach-1         ,31538
    4691    6828    8682    8006   10828   14643   16815
River Rch & RM=DAVIS CREEK,Reach-1         ,28619
    5039    7339    9335    8608   11642   15744   18080
River Rch & RM=DAVIS CREEK,Reach-1         ,23565
    6021    8794   11208   10349   13996   18928   21792
River Rch & RM=DAVIS CREEK,Reach-1         ,17261
    6120    8947   11410   10543   14258   19282   22227
River Rch & RM=DAVIS CREEK,Reach-1         ,11386
    6305    9214   11748   10851   14675   19846   22858
River Rch & RM=DAVIS CREEK,Reach-1         ,7551
    6544    9555   12174   11235   15194   20548   23626
Boundary for River Rch & Prof#=DAVIS CREEK,Reach-1         , 1
Up Type= 0
Dn Type= 3
Dn Slope=0.0024
Boundary for River Rch & Prof#=DAVIS CREEK,Reach-1         , 2
Up Type= 0
Dn Type= 3
Dn Slope=0.0024
Boundary for River Rch & Prof#=DAVIS CREEK,Reach-1         , 3
Up Type= 0
Dn Type= 3
Dn Slope=0.0024
Boundary for River Rch & Prof#=DAVIS CREEK,Reach-1         , 4
Up Type= 0
Dn Type= 3
Dn Slope=0.0024
Boundary for River Rch & Prof#=DAVIS CREEK,Reach-1         , 5
Up Type= 0
Dn Type= 3
Dn Slope=0.0024
Boundary for River Rch & Prof#=DAVIS CREEK,Reach-1         , 6
Up Type= 0
Dn Type= 3
Dn Slope=0.0024
Boundary for River Rch & Prof#=DAVIS CREEK,Reach-1         , 7
Up Type= 0
Dn Type= 3
Dn Slope=0.0024
DSS Import GetInterval= 0
DSS Import GetPeak= 0
DSS Import FillOption= 0

--- DAVIS CREEK.g01 (geometry) ---

Geom Title=Existing Conditions
Program Version=4.10

River Reach=DAVIS CREEK     ,Reach-1
Reach XY= 30
      3475692.11     10503491.64      3475724.21     10502072.01
      3477687.01     10501044.62      3478258.12     10498098.87
       3479797.4     10496694.37      3479998.19     10495666.23
       3480597.3     10495587.06      3481452.83     10493715.92
      3480962.38     10493208.11      3481581.12     10491821.58
      3481273.31     10491017.35      3481709.26     10490840.68
      3482679.76     10487865.75      3483548.52     10487755.92
      3483989.76     10486715.24      3487118.95     10483245.25
      3489743.22     10484839.78      3491099.28     10483516.28
      3491757.29     10483592.11      3493290.62      10482562.4
      3494309.37     10481166.41      3495377.84     10481164.12
      3495687.61     10479062.46      3494867.27     10478319.16
      3498265.76     10475932.86      3498765.49     10473632.74
      3499720.79     10473061.78      3500110.55     10472002.75
      3498834.92     10468482.99      3499572.46     10467319.62

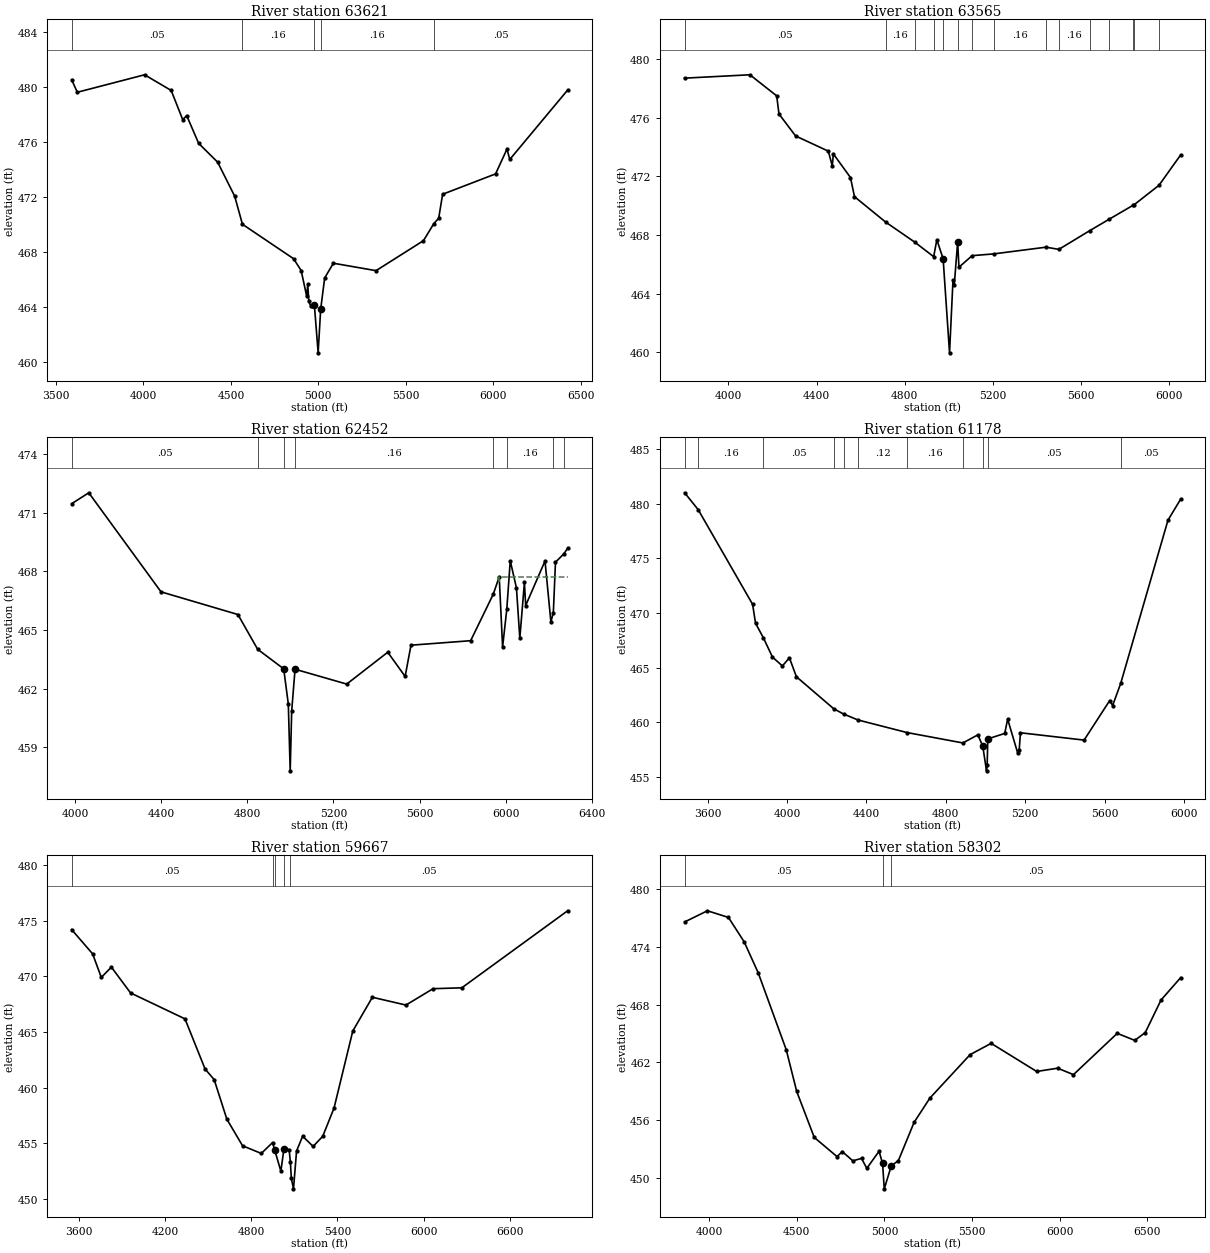
Type RM Length L Ch R = 1 ,63621   ,56,56,56
BEGIN DESCRIPTION:
DAVIS CREEK 98.0
END DESCRIPTION:
XS GIS Cut Line= 2
       3477007.7     10503930.99       3474526.7      10502556.9
#Sta/Elev= 30
  3589.4  480.54  3621.7  479.63  4006.4   480.9  4158.6  479.76  4224.5  477.64
  4247.4  477.93  4315.5  475.92  4424.3  474.55  4521.6  472.08    4566  470.04
  4858.2  467.54  4901.7  466.68  4933.3  464.82  4939.5  465.67  4945.2  464.46
  4955.5  464.13  4977.3  464.18  4998.8   460.7  5013.3  463.86  5036.1  466.14
    5086  467.21  5329.9  466.67  5601.2  468.85  5660.5  470.09  5688.2  470.48
  5710.6  472.22  6013.4   473.7  6078.6   475.5  6094.7  474.75  6425.5  479.79
#Mann= 5 ,-1 , 0
  3589.4     .05       0    4566     .16       0  4977.3     .07       0
  5013.3     .16       0  5660.5     .05       0
Bank Sta=4977.3,5013.3
XS Rating Curve= 0 ,0
Exp/Cntr=0.3,0.1

Type RM Length L Ch R = 1 ,63565   ,1113,1113,1113
BEGIN DESCRIPTION:
Mapping XS e23726f6
END DESCRIPTION:
XS GIS Cut Line= 4
      3476903.54     10503660.16      3476257.71     10503420.58
      3475945.21     10503288.64      3474907.04     10502642.82
#Sta/Elev= 30
  3801.6  478.72  4097.8  478.95  4219.3  477.51  4229.8  476.27  4305.1  474.77
  4453.7  473.73  4471.4  472.73  4476.7  473.54  4554.1  471.93  4572.4  470.62
  4713.3  468.89  4846.2  467.51  4931.7  466.52  4946.1  467.68  4974.6  466.38
  5003.7  459.95  5019.3   464.9  5025.2  464.59  5040.5  467.52  5046.4   465.8
  5106.2  466.59  5203.6  466.71  5441.5  467.17  5499.8  467.02    5640   468.3
    5727  469.07  5838.4  470.05  5840.6  470.06  5954.3   471.4  6052.3  473.47
#Mann= 15 ,-1 , 0
  3801.6     .05       0  4713.3     .16       0  4846.2     .05       0
  4931.7     .16       0  4974.6     .07       0  5040.5     .16       0
  5106.2     .05       0  5203.6     .16       0  5441.5     .05       0
  5499.8     .16       0    5640     .05       0    5727     .16       0
  5838.4     .05       0  5840.6     .16       0  5954.3     .05       0
Bank Sta=4974.6,5040.5
XS Rating Curve= 0 ,0
Exp/Cntr=0.3,0.1

Type RM Length L Ch R = 1 ,62452   ,1274,1274,1274
BEGIN DESCRIPTION:
DAVIS CREEK 97.0
END DESCRIPTION:
XS GIS Cut Line= 2
      3476586.54      10502636.5      3474602.57     10501465.63
#Sta/Elev= 30
  3984.2  471.46  4063.7  472.02  4399.3  466.95  4756.4  465.79  4848.2  464.01
  4969.1  463.01  4990.5  461.21  4999.3  457.79  5006.2  460.85  5021.8  462.99
  5261.8  462.23  5452.4  463.86  5533.1  462.62  5560.3  464.22  5837.4  464.45
  5942.5  466.83  5970.1  467.72  5985.8  464.13  6005.2  466.05  6021.4  468.54
  6050.1  467.15  6065.8  464.58  6087.2  467.43    6093  466.25  6182.8  468.53
  6210.1  465.41  6221.5  465.89  6231.5  468.47  6270.1  468.89  6287.9  469.18
#Mann= 8 ,-1 , 0
  3984.2     .05       0  4848.2     .16       0  4969.1     .07       0
  5021.8     .16       0  5942.5     .12       0  6005.2     .16       0
  6221.5     .12       0  6270.1     .16       0
#XS Ineff= 2 , 0
                         5971.36           467.7
Permanent Ineff=
       F       F
Bank Sta=4969.1,5021.8
XS Rating Curve= 0 ,0
Exp/Cntr=0.3,0.1

Type RM Length L Ch R = 1 ,61178   ,1511,1511,1511
BEGIN DESCRIPTION:
DAVIS CREEK 95.0
END DESCRIPTION:
XS GIS Cut Line= 3
       3477892.1     10502341.64      3476692.11     10501441.64
       3475892.1     10500841.64
#Sta/Elev= 30
  3483.3  480.99  3551.5  479.45    3826  470.79  3840.6  469.07  3880.5  467.72
    3926  465.97    3976  465.16  4011.4   465.9  4046.8  464.17  4235.2  461.24
    4285  460.76    4357  460.22  4604.2  459.07  4885.8  458.12  4961.4  458.86
 4986.17  457.82  5004.9  455.57  5008.2  456.07  5011.4  458.49  5096.8  458.99
  5111.4   460.3  5161.4  457.24  5169.7   457.5    5176  459.05  5496.8  458.38
    5626     462  5640.6  461.54  5681.3  463.56  5919.7  478.49  5983.3   480.4
#Mann= 11 ,-1 , 0
  3483.3     .05       0  3551.5     .16       0  3880.5     .05       0
  4235.2     .12       0    4285     .16       0    4357     .12       0
  4604.2     .16       0  4885.8     .05       0 4986.17    .035       0
  5011.4     .05       0  5681.3     .05       0
Bank Sta=4986.17,5011.4
XS Rating Curve= 0 ,0
Exp/Cntr=0.3,0.1

Type RM Length L Ch R = 1 ,59667   ,1365,1365,1365
BEGIN DESCRIPTION:
DAVIS CREEK 92.0
END DESCRIPTION:
XS GIS Cut Line= 4
       3478669.9     10501855.29      3478366.06     10501160.81
      3476901.22     10500227.65      3475946.76     10500271.03
#Sta/Elev= 30
  3551.6   474.2  3697.5  472.02  3757.8   469.9    3828  470.83  3961.3  468.51
    4340  466.18  4479.6  461.68  4543.1  460.72  4631.2  457.17  4740.4  454.78
  4870.7  454.09  4949.4  455.07  4964.7  454.37    5007   452.5  5028.2  454.49
  5064.6  454.43  5073.2   453.3  5079.8  451.85  5094.8  450.91  5116.2  454.31
  5158.5  455.64  5231.3  454.72  5298.2  455.63  5376.9  458.17  5507.3  465.09
  5643.5  468.12  5877.2  467.42  6065.6  468.89  6265.8  468.97  7001.9  475.89
#Mann= 5 ,-1 , 0
  3551.6     .05       0  4949.4     .16       0  4964.7     .07       0
  5028.2     .16       0  5073.2     .05       0
Bank Sta=4964.7,5028.2
XS Rating Curve= 0 ,0
Exp/Cntr=0.3,0.1

Type RM Length L Ch R = 1 ,58302   ,1161,1161,1161
BEGIN DESCRIPTION:
DAVIS CREEK 89.0
END DESCRIPTION:
XS GIS Cut Line= 2
      3479082.23     10499663.41      3476250.22     10499641.71
#Sta/Elev= 30
  3859.1  476.58  3989.2  477.74  4109.2  477.05  4199.2  474.51  4279.2   471.3
  4439.2  463.31  4499.2  458.97  4599.3   454.2  4729.3  452.21  4759.3  452.73
  4819.3  451.77  4869.3  452.02  4899.3  450.99  4969.3  452.76  4989.3  451.51
    4999  448.86  5039.3  451.26  5079.3  451.78  5169.3  455.76  5259.3  458.28
  5489.3   462.8  5609.3  463.97  5869.3  461.05  5989.3  461.39  6079.3  460.72
  6329.3  465.01  6429.3  464.28  6489.3  465.09  6579.3  468.47  6691.2  470.79
#Mann= 3 , 0 , 0
  3859.1     .05       0  4989.3    .035       0  5039.3     .05       0
Bank Sta=4989.3,5039.3
XS Rating Curve= 0 ,0
Exp/Cntr=0.3,0.1

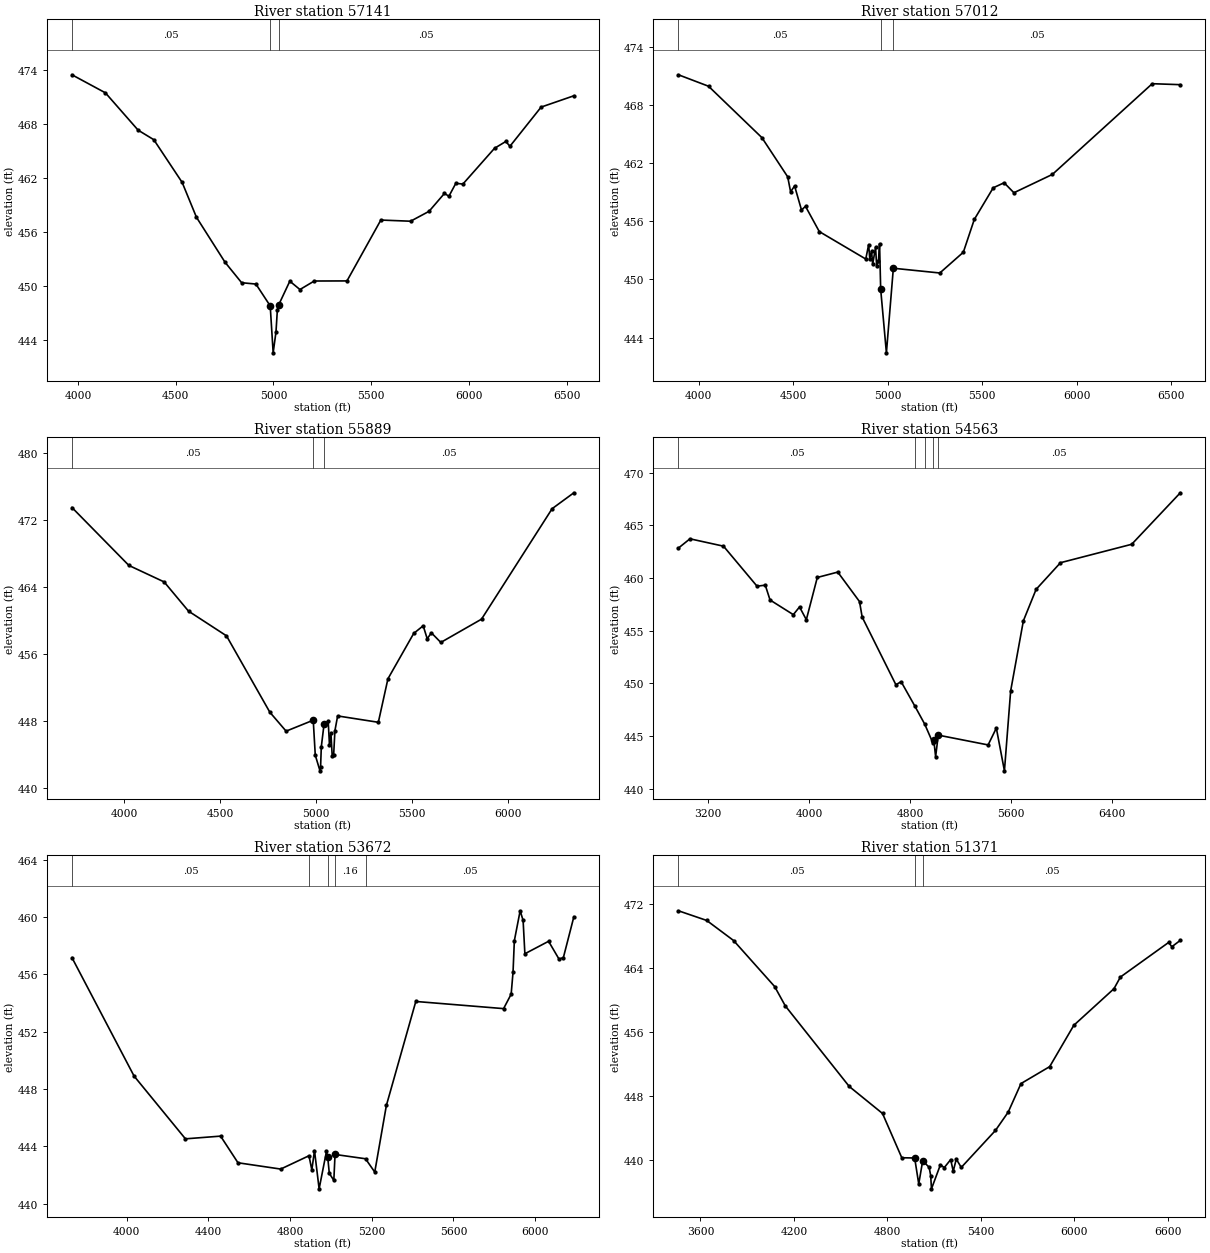
Type RM Length L Ch R = 1 ,57141   ,129,129,129
BEGIN DESCRIPTION:
Mapping XS f59d5a7c
END DESCRIPTION:
XS GIS Cut Line= 2
      3478997.14     10499454.29       3476820.1      10498093.2
#Sta/Elev= 30
    3969  473.51  4140.1   471.5  4307.6  467.34  4387.7  466.28  4532.8  461.52
  4605.9  457.64  4752.1  452.63    4837  450.35  4910.1   450.2  4983.2  447.77
  4998.3  442.54  5012.8  444.88  5019.8  447.33  5025.7  447.84  5083.5  450.52
  5135.3  449.59  5208.5  450.54  5375.9  450.55  5549.2  457.33  5701.3   457.2
  5795.7   458.3  5874.7   460.3  5897.3  459.98  5932.7  461.42    5969  461.34
  6130.6  465.32  6188.3  466.08  6209.6  465.55    6369  469.91  6536.5  471.17
#Mann= 3 , 0 , 0
    3969     .05       0  4983.2    .035       0  5025.7     .05       0
Bank Sta=4983.2,5025.7
XS Rating Curve= 0 ,0
Exp/Cntr=0.3,0.1

Type RM Length L Ch R = 1 ,57012   ,1123,1123,1123
BEGIN DESCRIPTION:
Mapping XS d3a28617
END DESCRIPTION:
XS GIS Cut Line= 2
       3479087.4     10499374.41      3476840.87     10497957.75
#Sta/Elev= 30
  3892.9   471.1  4052.2  469.92  4334.7  464.62  4471.2  460.58  4486.5  459.04
  4507.7  459.64  4544.2  457.16  4565.4  457.54  4638.3  454.94  4884.3  452.11
  4899.6   453.6  4905.5  452.12  4914.9  452.93  4920.8  451.57  4936.1  453.33
    4942  451.37  4951.3  451.87  4957.3  453.69  4963.2  448.99  4993.5  442.44
  5030.2  451.16  5276.2  450.67  5400.6  452.81  5458.6  456.19  5558.7  459.45
  5616.4  459.97  5668.2  458.94  5871.8  460.83  6400.2  470.18  6548.8  470.08
#Mann= 3 , 0 , 0
  3892.9     .05       0  4963.2    .035       0  5030.2     .05       0
Bank Sta=4963.2,5030.2
XS Rating Curve= 0 ,0
Exp/Cntr=0.3,0.1

Type RM Length L Ch R = 1 ,55889   ,1326,1326,1326
BEGIN DESCRIPTION:
DAVIS CREEK 86.0
END DESCRIPTION:
XS GIS Cut Line= 3
      3479342.12     10498841.65      3478442.11     10497941.64
      3477542.09     10496941.62
#Sta/Elev= 30
  3726.4  473.49  4023.4  466.57  4207.3   464.6  4334.5  461.11  4532.5  458.16
  4758.8  449.03  4843.6  446.77  4985.1  448.08  4995.7   443.9  5020.3  442.03
  5023.5  442.53  5027.2  444.91  5041.4  447.58  5063.1  447.97  5069.8  445.12
  5077.3  446.56    5084  443.81  5091.5  443.91  5098.2  446.83  5112.4  448.59
  5324.7  447.83  5374.8  453.03  5509.3  458.45  5558.7  459.36  5579.6  457.81
  5601.3  458.52  5650.6  457.37  5862.9  460.15  6231.3  473.35  6344.6  475.25
#Mann= 3 , 0 , 0
  3726.4     .05       0  4985.1    .035       0  5041.4     .05       0
Bank Sta=4985.1,5041.4
XS Rating Curve= 0 ,0
Exp/Cntr=0.3,0.1

Type RM Length L Ch R = 1 ,54563   ,891,891,891
BEGIN DESCRIPTION:
DAVIS CREEK 82.0
END DESCRIPTION:
XS GIS Cut Line= 4
      3480449.38     10498860.42      3479841.76     10497764.54
      3478800.09      10496299.7       3477877.8     10496353.95
#Sta/Elev= 30
  2965.1  462.85  3056.6  463.73  3322.1  463.03  3587.7  459.23  3652.9  459.33
  3690.7  457.92  3874.9  456.53  3924.2  457.26    3978  456.05  4064.9  460.06
    4227  460.57  4399.2  457.77  4420.1   456.3    4687  449.88  4728.8  450.16
  4835.8  447.88  4915.7  446.13  4980.9  444.33    4987  444.67  5001.8  443.04
  5022.7  445.09  5417.5  444.16  5482.6  445.76  5546.7   441.7    5596  449.29
  5696.6  455.94  5797.5  458.93  5990.5  461.46  6554.5  463.21  6939.5   468.1
#Mann= 5 ,-1 , 0
  2965.1     .05       0  4835.8     .16       0  4915.7     .05       0
  4980.9    .035       0  5022.7     .05       0
Bank Sta=4987,5022.7
XS Rating Curve= 0 ,0
Exp/Cntr=0.3,0.1

Type RM Length L Ch R = 1 ,53672   ,2301,2301,2301
BEGIN DESCRIPTION:
Mapping XS 771f5960
END DESCRIPTION:
XS GIS Cut Line= 3
      3480953.58     10497171.78      3479552.54     10496216.06
      3478895.41     10495829.05
#Sta/Elev= 30
  3731.3  457.17  4035.7   448.9  4287.2  444.52  4459.4  444.71  4544.6  442.85
  4753.9  442.41  4892.4  443.34  4906.4  442.35  4919.4   443.7  4942.1  441.03
  4978.2  443.65  4984.3  443.22    4992  442.11  5014.1  441.62 5020.06  443.43
  5169.3  443.13  5214.6   442.2  5271.5  446.85  5415.7  454.11  5845.7  453.61
  5882.8  454.62    5892  456.16  5898.4  458.35  5926.8  460.44  5941.3  459.77
    5950  457.44  6066.1  458.31  6117.1  457.07  6138.5  457.17  6189.9  460.02
#Mann= 5 ,-1 , 0
  3731.3     .05       0  4892.4     .16       0  4984.3     .07       0
 5020.06     .16       0  5169.3     .05       0
Bank Sta=4984.3,5020.06
XS Rating Curve= 0 ,0
Exp/Cntr=0.3,0.1

Type RM Length L Ch R = 1 ,51371   ,1457,1457,1457
BEGIN DESCRIPTION:
DAVIS CREEK 78.0
END DESCRIPTION:
XS GIS Cut Line= 3
      3481455.49     10496317.09      3481173.37     10495477.82
      3478909.46      10494904.9
#Sta/Elev= 30
  3458.6  471.15  3640.1  469.94  3812.5  467.43  4076.1  461.67  4144.4  459.25
  4554.7  449.17  4768.3  445.79    4892  440.25  4974.6  440.22  5000.7  436.98
  5026.1  439.86  5067.4  439.06  5077.5  438.02  5082.4  436.36  5139.6  439.36
  5164.7  439.02  5205.7  440.02  5222.1  438.56  5241.6  440.08  5273.7  439.04
  5492.8  443.66  5574.8  445.96  5656.8  449.53    5841  451.65  5995.8  456.82
  6253.6   461.4  6294.9  462.86  6604.4  467.19    6625  466.65  6679.3  467.45
#Mann= 3 , 0 , 0
  3458.6     .05       0  4974.6    .035       0  5026.1     .05       0
Bank Sta=4974.6,5026.1
XS Rating Curve= 0 ,0
Exp/Cntr=0.3,0.1

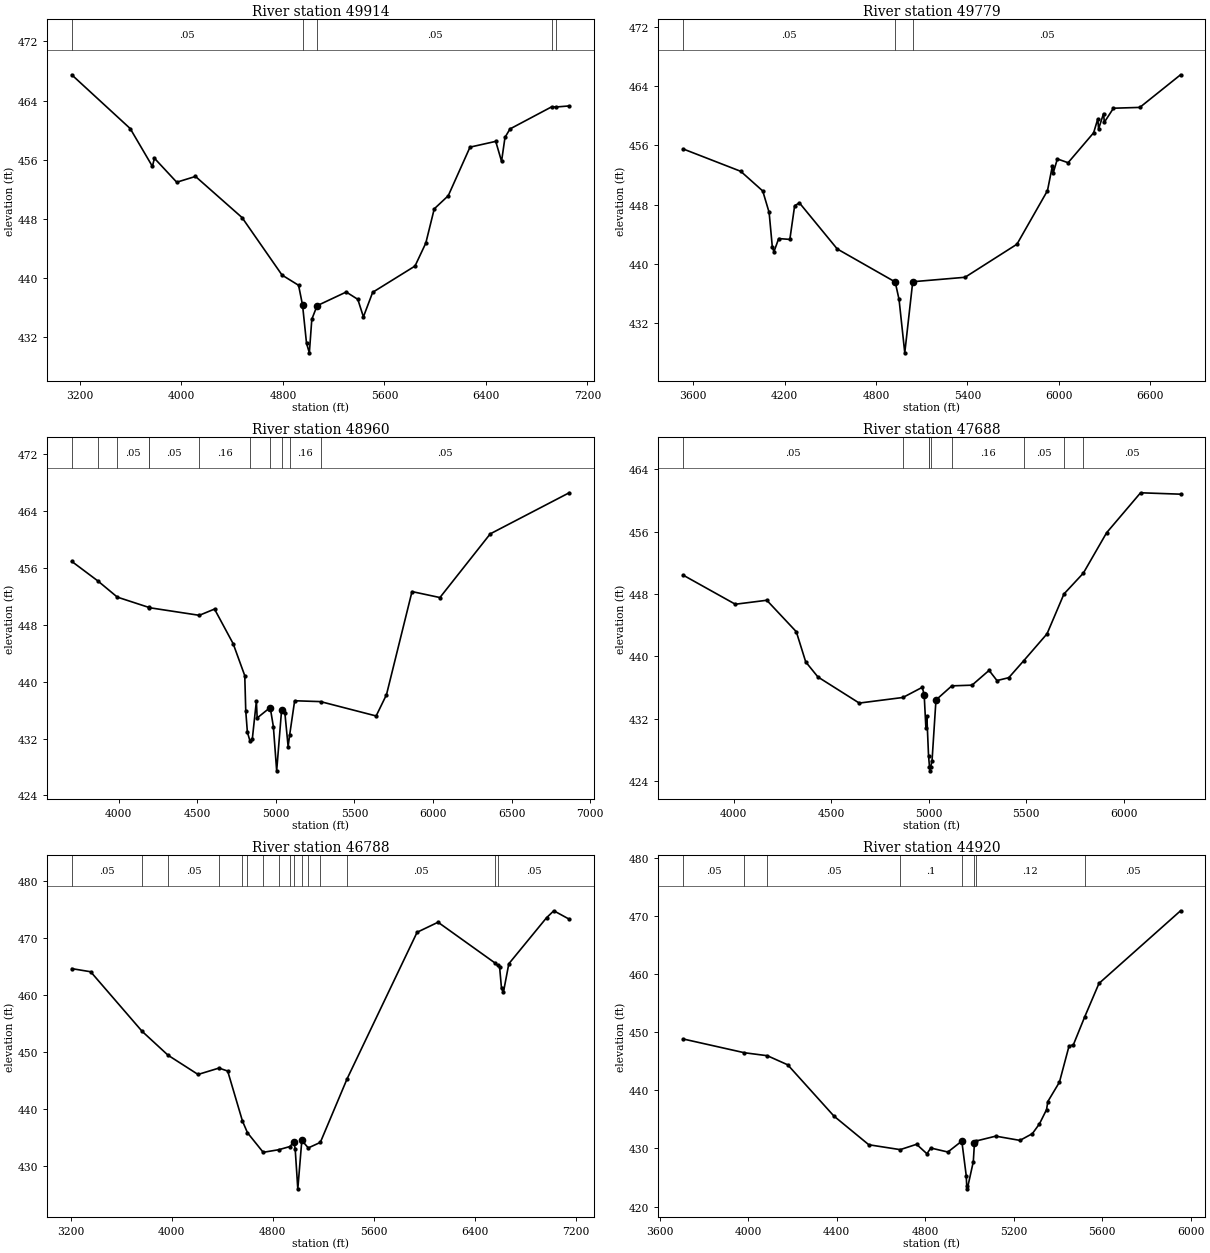
Type RM Length L Ch R = 1 ,49914   ,135,135,135
BEGIN DESCRIPTION:
DAVIS CREEK 73.0
END DESCRIPTION:
XS GIS Cut Line= 4
      3482788.78     10494608.71      3481725.45      10494029.9
      3479517.12     10494682.68      3479129.88     10494807.15
#Sta/Elev= 30
    3136  467.48  3596.9  460.21  3771.7   455.1  3787.8   456.2  3963.4  452.96
  4111.4  453.74  4478.4  448.18  4793.5  440.41  4923.7  439.03    4955  436.36
  4986.2  431.21  5008.6   429.9    5028  434.44  5069.7  436.27  5299.1  438.12
  5390.6  437.13  5434.6  434.76  5507.6  438.08  5841.3  441.63  5926.3  444.73
  5992.9  449.36  6103.1  451.13  6274.7   457.7  6477.4  458.48  6523.3  455.78
  6550.4  459.02  6589.9  460.16  6918.4  463.15  6955.5  463.13  7056.2  463.27
#Mann= 5 ,-1 , 0
    3136     .05       0    4955    .035       0  5069.7     .05       0
  6918.4     .08       0  6955.5     .05       0
Bank Sta=4955,5069.7
XS Rating Curve= 0 ,0
Exp/Cntr=0.3,0.1

Type RM Length L Ch R = 1 ,49779   ,819,819,819
BEGIN DESCRIPTION:
Mapping XS cfdedd8a
END DESCRIPTION:
XS GIS Cut Line= 2
      3482451.17     10493654.89      3479333.89     10494626.87
#Sta/Elev= 30
  3533.9  455.53  3912.3  452.51  4056.7  449.86  4098.6  446.97  4119.5  442.33
    4130  441.65  4161.4  443.44  4234.7  443.33  4266.2  447.88  4297.6  448.25
  4545.7  442.04  4926.1  437.59  4951.5  435.23    4989  428.03  5041.3  437.62
  5384.6  438.22  5725.4  442.68  5925.7   449.9  5958.2  453.26  5963.4  452.29
  5990.7  454.18    6061  453.67  6228.8  457.71    6256  459.59  6261.3  458.23
  6293.8   460.3    6299  459.13  6358.8  461.02  6531.8  461.13  6799.2  465.53
#Mann= 3 , 0 , 0
  3533.9     .05       0  4926.1     .04       0  5041.3     .05       0
#XS Ineff= 2 , 0
         4297.44  448.16
Permanent Ineff=
       F       F
Bank Sta=4926.1,5041.3
XS Rating Curve= 0 ,0
Exp/Cntr=0.3,0.1

Type RM Length L Ch R = 1 ,48960   ,1272,1272,1272
BEGIN DESCRIPTION:
Mapping XS d268b087
END DESCRIPTION:
XS GIS Cut Line= 3
      3482666.42     10493408.37      3482221.98     10493314.62
       3479607.8     10494036.73
#Sta/Elev= 30
  3700.6  456.93  3866.8  454.18  3990.9   451.9  4190.5  450.46  4192.6  450.42
  4512.6  449.34  4609.5  450.22  4728.1  445.35    4802  440.85  4808.3  435.88
  4818.7   432.9  4835.8  431.62  4849.8  431.89  4875.9  437.26    4881   434.9
  4963.9  436.37  4984.1  433.68  5005.1  427.46  5036.5  436.04  5057.3  435.61
    5078  430.87  5087.4  432.46  5119.5  437.32  5284.4   437.2  5638.2  435.18
    5704  438.17  5866.5  452.68  6044.2  451.84  6364.5   460.8  6866.9  466.58
#Mann= 11 ,-1 , 0
  3700.6     .05       0  3866.8      .1       0  3990.9     .05       0
  4190.5      .1       0  4192.6     .05       0  4512.6     .16       0
  4835.8     .12       0  4963.9     .07       0  5036.5     .12       0
  5087.4     .16       0  5284.4     .05       0
Bank Sta=4963.9,5036.5
XS Rating Curve= 0 ,0
Exp/Cntr=0.3,0.1

Type RM Length L Ch R = 1 ,47688   ,900,900,900
BEGIN DESCRIPTION:
Mapping XS 75c0fb7a
END DESCRIPTION:
XS GIS Cut Line= 2
       3482367.6     10492938.54      3479838.94     10492607.81
#Sta/Elev= 30
  3741.2  450.43    4009  446.69  4170.3   447.2  4321.6  443.16  4369.8  439.29
  4432.5  437.35  4644.3     434  4868.3  434.72  4967.1  436.02  4977.1  435.09
  4985.9   430.8  4990.9   432.3  4999.5  427.24  5004.4   425.8  5007.1   425.3
  5010.4   425.8  5017.5  426.62  5037.6   434.4  5118.8  436.21  5222.5   436.3
  5309.9   438.2  5350.3  436.89  5410.8  437.26  5488.3  439.46  5606.9  442.89
  5693.8  448.01    5793  450.68  5912.4  455.87  6086.5     461  6291.4  460.82
#Mann= 9 ,-1 , 0
  3741.2     .05       0  4868.3     .16       0  4999.5     .12       0
  5004.4     .07       0  5010.4     .12       0  5118.8     .16       0
  5488.3     .05       0  5693.8     .16       0    5793     .05       0
Bank Sta=4977.1,5037.6
XS Rating Curve= 0 ,0
Exp/Cntr=0.3,0.1

Type RM Length L Ch R = 1 ,46788   ,1868,1868,1868
BEGIN DESCRIPTION:
DAVIS CREEK 69.0
END DESCRIPTION:
XS GIS Cut Line= 4
      3483184.65     10492546.23      3482413.81     10492296.23
      3480934.64     10491817.06      3479601.34     10490983.75
#Sta/Elev= 30
  3208.3  464.65  3358.2   464.1  3765.3  453.65    3971  449.45  4208.2  446.08
  4373.9   447.2  4442.7  446.68  4559.8   437.9  4599.4  435.85  4723.9  432.42
  4846.1  432.87    4935  433.43  4966.5  434.25    4977  433.02  4997.8  426.01
  5029.6  434.51  5080.7  433.19  5176.1  434.16  5388.3  445.33  5942.1  471.03
  6107.8  472.79  6558.1  465.65  6580.3   465.2  6594.9  464.99  6610.2  461.17
  6625.5  460.53    6668   465.5  6966.3  473.57  7024.1   474.8  7145.8  473.33
#Mann= 16 ,-1 , 0
  3208.3     .05       0  3765.3      .1       0    3971     .05       0
  4373.9      .1       0  4559.8     .16       0  4599.4      .1       0
  4723.9     .16       0  4846.1      .1       0    4935     .16       0
  4966.5     .07       0  5029.6     .16       0  5080.7     .12       0
  5176.1     .16       0  5388.3     .05       0  6558.1     .16       0
  6580.3     .05       0
Bank Sta=4966.5,5029.6
XS Rating Curve= 0 ,0
Exp/Cntr=0.3,0.1

Type RM Length L Ch R = 1 ,44920   ,1078,1078,1078
BEGIN DESCRIPTION:
Mapping XS 5eb3fcd8
END DESCRIPTION:
XS GIS Cut Line= 2
      3482931.01     10491250.69      3480791.24     10490560.58
#Sta/Elev= 30
  3706.6  448.82  3983.9  446.45  4087.3  445.94  4179.7  444.37  4388.4  435.56
    4546  430.63  4687.9  429.79  4761.9  430.71  4808.7  429.08    4826  430.07
  4903.3  429.38  4966.3  431.26  4986.2  425.34  4988.5  423.55  4991.2  423.05
  5018.3  427.73  5023.5  430.98  5029.4  431.26  5119.7  432.11    5229  431.38
  5285.2  432.54  5317.2  434.22  5349.3  436.67  5355.1  438.06  5407.6   441.4
  5450.7  447.57  5470.7  447.84  5522.3  452.67  5586.2  458.37  5954.9  470.86
#Mann= 8 ,-1 , 0
  3706.6     .05       0  3983.9      .1       0  4087.3     .05       0
  4687.9      .1       0  4966.3     .07       0  5023.5      .1       0
  5029.4     .12       0  5522.3     .05       0
Bank Sta=4966.3,5023.5
XS Rating Curve= 0 ,0
Exp/Cntr=0.3,0.1

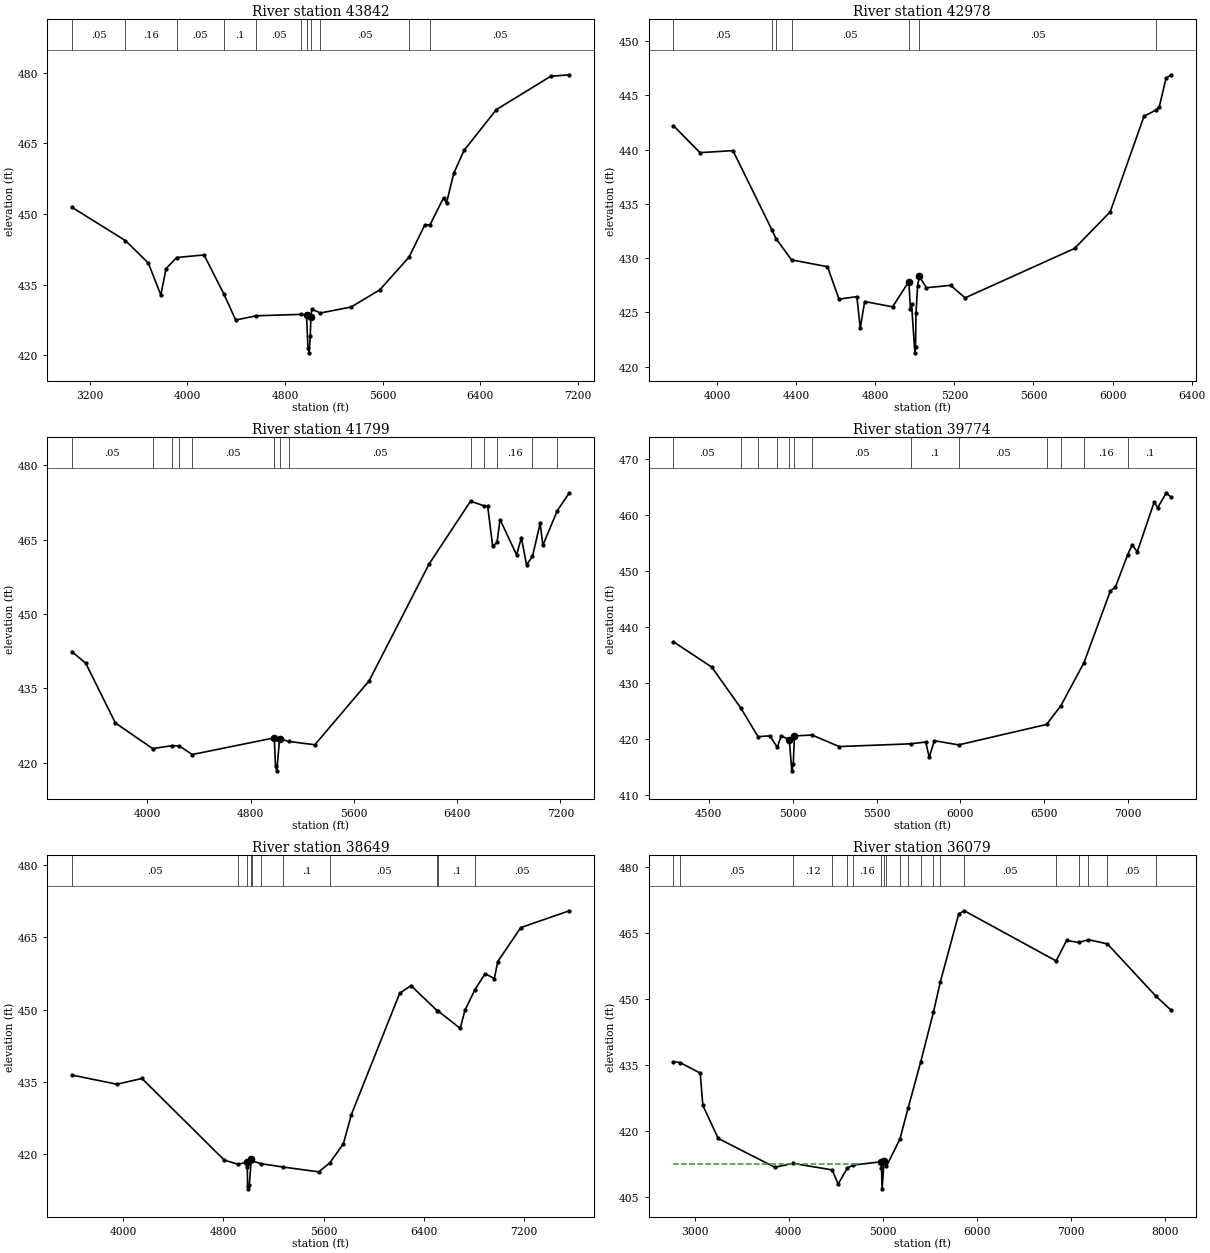
Type RM Length L Ch R = 1 ,43842   ,864,864,864
BEGIN DESCRIPTION:
DAVIS CREEK 65.0
END DESCRIPTION:
XS GIS Cut Line= 2
      3483601.31     10490567.06      3479809.64     10489067.06
#Sta/Elev= 30
  3051.6  451.47  3492.1  444.36  3678.9  439.61  3781.7  432.82    3825  438.43
  3910.8  440.77  4135.8  441.32  4297.5  433.07    4395   427.5  4564.7   428.4
    4933   428.7  4975.7  428.56  4987.3  421.65    4997  420.53  5006.3  424.01
  5011.7  428.21  5018.7   429.8    5089  428.99  5341.5  430.26  5576.7  433.92
  5815.8  440.86  5943.6  447.62  5988.1  447.76  6098.4  453.43  6122.8  452.35
  6182.2  458.64  6266.2  463.51    6531  472.17    6976  479.25  7129.2  479.58
#Mann= 11 ,-1 , 0
  3051.6     .05       0  3492.1     .16       0  3910.8     .05       0
  4297.5      .1       0  4564.7     .05       0    4933     .16       0
  4975.7     .07       0  5011.7     .16       0    5089     .05       0
  5815.8      .1       0  5988.1     .05       0
Bank Sta=4975.7,5011.7
XS Rating Curve= 0 ,0
Exp/Cntr=0.3,0.1

Type RM Length L Ch R = 1 ,42978   ,1179,1179,1179
BEGIN DESCRIPTION:
Mapping XS b4e84abc
END DESCRIPTION:
XS GIS Cut Line= 2
      3483282.96     10489650.51      3481019.14     10488553.32
#Sta/Elev= 30
  3779.6  442.21  3913.9  439.72  4080.6  439.91  4277.5   432.6  4298.6  431.79
  4376.6  429.84  4558.4  429.21  4616.7  426.22    4707  426.45  4724.1  423.56
  4746.6     426  4887.6  425.51  4969.6  427.84    4978  425.33  4983.5  425.76
  5000.3  421.27  5003.5  421.77  5006.1  424.95  5014.1  427.46  5023.1  428.31
  5058.5  427.27  5180.7  427.49  5254.4  426.34  5807.4  430.89    5988  434.27
  6158.6  443.07  6217.6  443.63  6236.3  443.97    6270  446.57  6295.3   446.9
#Mann= 7 ,-1 , 0
  3779.6     .05       0  4277.5     .16       0  4298.6      .1       0
  4376.6     .05       0  4969.6    .035       0  5023.1     .05       0
  6217.6     .16       0
Bank Sta=4969.6,5023.1
XS Rating Curve= 0 ,0
Exp/Cntr=0.3,0.1

Type RM Length L Ch R = 1 ,41799   ,2025,2025,2025
BEGIN DESCRIPTION:
DAVIS CREEK 59.0
END DESCRIPTION:
XS GIS Cut Line= 2
      3484163.78     10488608.72      3480497.18     10487421.24
#Sta/Elev= 30
    3415  442.44  3523.1  440.11  3753.1  428.06  4041.8   422.9  4193.3   423.5
  4246.9  423.43  4349.5  421.71  4979.7  425.04  4983.9  424.98  4993.5  419.35
  5003.7  418.42    5025  424.87  5096.5  424.34  5298.3  423.67  5718.7  436.55
  6183.5  460.09    6504  472.71  6606.6   471.8  6636.7  471.71  6675.3  463.69
  6709.2   464.4  6732.7  469.01  6860.7  461.92  6897.9  465.36  6938.1  459.89
  6983.9   461.6  7043.2  468.27  7064.2  463.84    7176   470.8  7269.1  474.41
#Mann= 14 ,-1 , 0
    3415     .05       0  4041.8      .1       0  4193.3     .05       0
  4246.9      .1       0  4349.5     .05       0  4979.7      .1       0
  4983.9     .07       0    5025      .1       0  5096.5     .05       0
    6504     .16       0  6606.6     .05       0  6709.2     .16       0
  6983.9      .1       0    7176     .05       0
Bank Sta=4983.9,5025
XS Rating Curve= 0 ,0
Exp/Cntr=0.3,0.1

Type RM Length L Ch R = 1 ,39774   ,1125,1125,1125
BEGIN DESCRIPTION:
Mapping XS dabc077a
END DESCRIPTION:
XS GIS Cut Line= 2
      3484324.82     10487803.98      3481822.21     10486212.83
#Sta/Elev= 30
  4289.1  437.34  4517.5  432.82  4689.5  425.57  4793.4  420.42  4864.5  420.56
  4907.7  418.51  4931.4  420.55  4979.6  419.88  4994.6  414.32  5003.3  415.46
  5010.1  420.55  5115.9   420.7  5276.9  418.65  5703.2  419.14  5792.6  419.46
  5813.8  416.74  5844.2  419.69  5988.9  418.95  6512.9  422.59    6598  425.92
  6735.8   433.6  6893.4  446.41    6923  447.06  6996.4  452.87  7023.8  454.64
  7053.4  453.37  7154.3  462.24  7175.4  461.26  7227.1  463.91  7254.7  463.11
#Mann= 13 ,-1 , 0
  4289.1     .05       0  4689.5      .1       0  4793.4     .16       0
  4907.7     .12       0  4979.6     .07       0  5010.1     .12       0
  5115.9     .05       0  5703.2      .1       0  5988.9     .05       0
  6512.9      .1       0    6598     .05       0  6735.8     .16       0
  6996.4      .1       0
Bank Sta=4979.6,5010.1
XS Rating Curve= 0 ,0
Exp/Cntr=0.3,0.1

Type RM Length L Ch R = 1 ,38649   ,2570,2570,2570
BEGIN DESCRIPTION:
DAVIS CREEK 54.0
END DESCRIPTION:
XS GIS Cut Line= 4
      3484580.47     10487942.03      3484542.11     10487291.64
      3483892.97     10485317.06       3483268.8     10484235.16
#Sta/Elev= 30
  3586.4  436.38  3947.4  434.46  4147.8  435.66  4806.3  418.68  4917.1   417.8
  4985.2  418.24  4990.5  417.16  4992.8   413.2  4995.6   412.7  5006.4  413.48
  5022.3  418.89    5030  418.51  5102.1  417.92  5278.4  417.23  5562.9  416.23
    5650  418.11  5758.9  422.07  5822.5  428.15  6209.4   453.4  6299.5  454.97
  6509.6  449.74  6514.5  449.73  6693.2  446.07  6730.5  449.84  6810.8  454.12
  6891.4  457.45    6966  456.45  6993.3  459.96    7177  467.04  7565.5  470.54
#Mann= 11 ,-1 , 0
  3586.4     .05       0  4917.1     .16       0  4985.2     .07       0
  5022.3     .16       0    5030     .12       0  5102.1     .05       0
  5278.4      .1       0    5650     .05       0  6509.6     .16       0
  6514.5      .1       0  6810.8     .05       0
Bank Sta=4985.2,5022.3
XS Rating Curve= 0 ,0
Exp/Cntr=0.3,0.1

Type RM Length L Ch R = 1 ,36079   ,1153,1153,1153
BEGIN DESCRIPTION:
DAVIS CREEK 52.0
END DESCRIPTION:
XS GIS Cut Line= 3
      3487189.87     10486305.75      3485054.43     10483870.84
      3484559.63     10481878.62
#Sta/Elev= 30
  2773.5  435.79  2843.8  435.61  3058.3  433.21  3086.3  425.87  3249.5  418.39
  3852.1  411.84  4045.9  412.72  4461.3  411.25  4524.9  408.03  4622.7  411.68
  4686.5  412.36  4978.5  413.08  4986.1  411.73  4992.5  406.95  5013.7  413.24
  5038.3  412.04  5181.7  418.25  5268.4  425.22  5403.6  435.79  5538.8  447.05
    5612  453.94  5807.9  469.36  5866.9  470.05  6842.9  458.67  6954.7  463.31
  7084.4  462.86  7186.5  463.49    7388  462.54  7901.3  450.74  8064.9   447.5
#Mann= 20 ,-1 , 0
  2773.5      .1       0  2843.8     .05       0  4045.9     .12       0
  4461.3     .16       0  4622.7     .12       0  4686.5     .16       0
  4978.5     .03       0  5013.7     .16       0  5038.3      .1       0
  5181.7      .1       0  5268.4     .05       0  5403.6     .16       0
  5538.8      .1       0    5612     .16       0  5866.9     .05       0
  6842.9     .16       0  7084.4     .05       0  7186.5      .1       0
    7388     .05       0  7901.3      .1       0
#XS Ineff= 2 , 0
       0 4746.91   412.6               0
Permanent Ineff=
       T       F
Bank Sta=4978.5,5013.7
XS Rating Curve= 0 ,0
Exp/Cntr=0.3,0.1

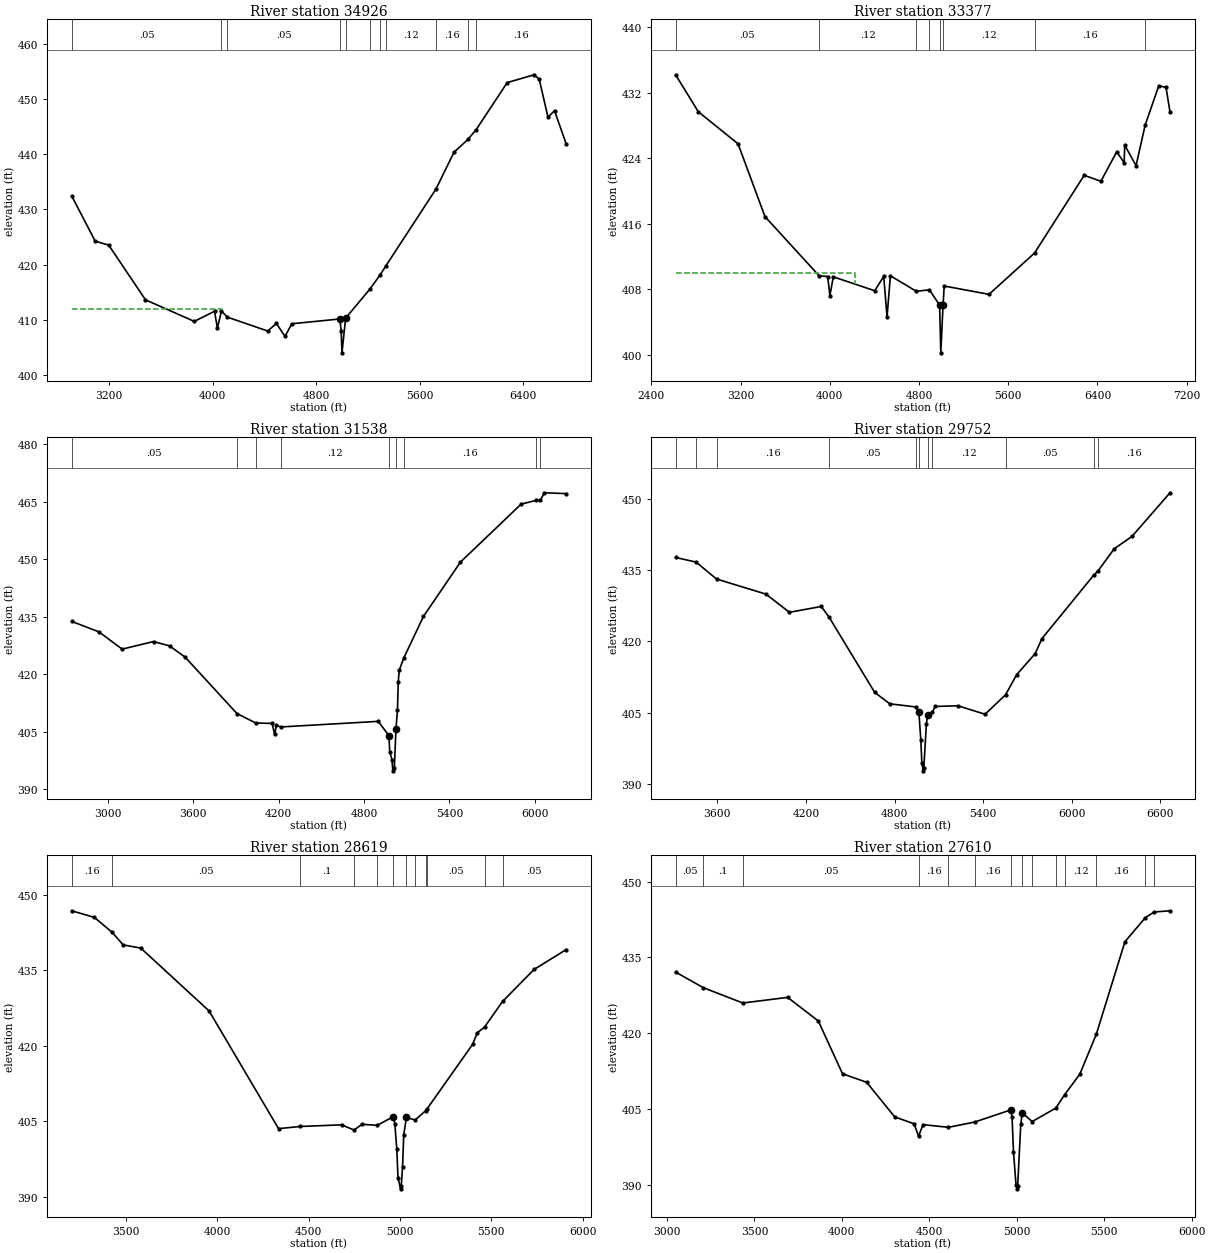
Type RM Length L Ch R = 1 ,34926   ,1549,1549,1549
BEGIN DESCRIPTION:
Mapping XS 84a04bad
END DESCRIPTION:
XS GIS Cut Line= 3
      3487359.62     10485793.21      3487359.62     10485506.74
      3485806.52     10482328.27
#Sta/Elev= 30
  2909.8  432.44  3091.4  424.24  3196.3  423.52  3480.5  413.61  3857.8   409.7
  4014.4  411.53  4036.7  408.47  4067.8  411.57  4113.8  410.47  4426.2  407.95
    4493  409.34  4559.8  406.98  4612.1  409.27  4983.5  410.14  4993.9  408.03
  5000.2     404  5028.5  410.29    5218  415.61  5293.1  418.06  5338.9  419.73
    5726  433.64  5867.3  440.38  5973.9  442.67  6037.8  444.45  6278.2  452.98
  6486.4   454.4  6525.9  453.59  6593.5  446.72  6644.1  447.89  6733.9   441.9
#Mann= 11 ,-1 , 0
  2909.8     .05       0  4067.8     .12       0  4113.8     .05       0
  4983.5    .035       0  5028.5     .05       0    5218     .12       0
  5293.1     .05       0  5338.9     .12       0    5726     .16       0
  5973.9      .1       0  6037.8     .16       0
#XS Ineff= 2 , 0
       0 4073.86  412.02               0
Permanent Ineff=
       T       F
Bank Sta=4983.5,5028.5
XS Rating Curve= 0 ,0
Exp/Cntr=0.3,0.1

Type RM Length L Ch R = 1 ,33377   ,1839,1839,1839
BEGIN DESCRIPTION:
DAVIS CREEK 51.0
END DESCRIPTION:
XS GIS Cut Line= 2
      3487437.24     10485889.11      3487866.85     10481475.87
#Sta/Elev= 30
  2616.8  434.21    2821  429.69  3176.9  425.78    3418   416.9  3903.6  409.67
  3980.7  409.58  4000.8  407.25  4030.9  409.54  4402.7  407.84    4483   409.6
  4513.2  404.68  4543.3  409.67  4775.8  407.77  4893.2  407.96  4984.8  406.08
  4995.2  400.26  5015.5  406.09  5025.6  408.42  5427.5   407.4  5835.6  412.44
  6281.5  421.94  6430.7   421.2  6572.9  424.81  6639.4  423.47  6644.5  425.62
  6746.3  423.12  6827.8  428.06    6950  432.87    7015  432.67  7050.9  429.66
#Mann= 8 ,-1 , 0
  2616.8     .05       0  3903.6     .12       0  4775.8     .05       0
  4893.2     .12       0  4984.8     .07       0  5015.5     .12       0
  5835.6     .16       0  6827.8     .12       0
#XS Ineff= 2 , 0
       0 4229.55  409.99               0
Permanent Ineff=
       T       F
Bank Sta=4984.8,5015.5
XS Rating Curve= 0 ,0
Exp/Cntr=0.3,0.1

Type RM Length L Ch R = 1 ,31538   ,1786,1786,1786
BEGIN DESCRIPTION:
DAVIS CREEK 49.0
END DESCRIPTION:
XS GIS Cut Line= 2
      3487658.59     10485878.24      3489307.52     10482819.04
#Sta/Elev= 30
    2745  433.77  2935.8  431.05  3099.6  426.54  3320.5  428.52  3432.9  427.38
  3542.4  424.45  3906.4  409.75  4038.2  407.29  4154.7  407.16  4170.9  404.29
  4183.9  406.65  4214.5  406.25  4899.6  407.71  4974.7  403.99  4980.4  399.78
  4996.6  397.69    5002  394.81  5012.8  395.66  5024.5  405.73  5034.7  410.64
  5040.4  418.03  5047.2  421.02  5080.1  424.31  5217.6  435.07  5477.5  449.23
  5904.1  464.34  6008.5  465.31  6038.7  465.33  6067.9   467.3  6220.3  467.08
#Mann= 9 ,-1 , 0
    2745     .05       0  3906.4      .1       0  4038.2     .16       0
  4214.5     .12       0  4974.7     .07       0  5024.5     .12       0
  5080.1     .16       0  6008.5     .05       0  6038.7     .16       0
Bank Sta=4974.7,5024.5
XS Rating Curve= 0 ,0
Exp/Cntr=0.3,0.1

Type RM Length L Ch R = 1 ,29752   ,1133,1133,1133
BEGIN DESCRIPTION:
DAVIS CREEK 47.0
END DESCRIPTION:
XS GIS Cut Line= 4
      3488743.66     10486323.11      3489342.11     10485441.64
      3489633.43     10483968.49      3489514.07     10483198.08
#Sta/Elev= 30
  3318.2  437.66  3457.1  436.68  3595.2  433.12    3930  429.94  4088.7  426.11
  4304.3  427.34  4357.3  425.08  4665.5  409.26  4768.1  406.84  4944.3  406.19
  4964.7  405.14  4978.2  399.18    4985   394.4    4995  392.73  4998.2  393.23
  5015.6  402.54  5024.3  404.55  5055.7  405.06  5075.6  406.29  5229.4  406.43
  5413.2  404.65  5551.9  408.76  5627.2     413  5752.1  417.41  5798.3  420.59
  6149.2  433.96  6176.3  434.78  6286.9  439.47  6408.3  442.12  6664.9  451.28
#Mann= 11 ,-1 , 0
  3318.2     .16       0  3457.1     .05       0  3595.2     .16       0
  4357.3     .05       0  4944.3     .16       0  4964.7     .07       0
  5024.3     .16       0  5055.7     .12       0  5551.9     .05       0
  6149.2      .1       0  6176.3     .16       0
Bank Sta=4964.7,5024.3
XS Rating Curve= 0 ,0
Exp/Cntr=0.3,0.1

Type RM Length L Ch R = 1 ,28619   ,1009,1009,1009
BEGIN DESCRIPTION:
DAVIS CREEK 45.0
END DESCRIPTION:
XS GIS Cut Line= 4
       3491000.6     10486019.25      3490544.79     10485074.96
      3490152.71     10483918.89      3490143.41     10483480.18
#Sta/Elev= 30
  3201.6  446.86  3325.6  445.55  3422.3  442.61  3483.9  440.07  3579.9  439.45
    3954  426.96  4334.6  403.56  4450.9  403.99  4680.1  404.32  4747.7  403.29
  4792.2  404.43  4875.8  404.22  4962.7  405.95  4971.7  404.43  4982.2  399.51
  4988.8  393.81  5003.1   391.6  5006.4   392.1  5013.9     396  5020.3  402.38
    5035  405.79  5083.1  405.28  5140.1  407.13    5148  407.49  5397.1  420.29
  5423.3  422.62  5463.1  423.76  5561.8  428.85  5734.2   435.2  5909.7  439.14
#Mann= 12 ,-1 , 0
  3201.6     .16       0  3422.3     .05       0  4450.9      .1       0
  4747.7     .05       0  4875.8      .1       0  4962.7     .07       0
    5035      .1       0  5083.1     .05       0  5140.1     .12       0
    5148     .05       0  5463.1      .1       0  5561.8     .05       0
Bank Sta=4962.7,5035
XS Rating Curve= 0 ,0
Exp/Cntr=0.3,0.1

Type RM Length L Ch R = 1 ,27610   ,965,965,965
BEGIN DESCRIPTION:
Mapping XS 0fd53941
END DESCRIPTION:
XS GIS Cut Line= 3
      3492094.61     10485267.28       3491330.7     10483982.53
      3490248.69      10483205.7
#Sta/Elev= 30
  3049.6  432.09  3207.3  429.01  3433.7  425.97  3690.3  427.08  3865.6  422.41
  4003.9  411.97  4142.2  410.28  4301.9  403.45    4413  402.07  4438.7  399.61
  4463.9  401.91  4609.8  401.38  4759.2  402.42  4966.6  404.83  4973.4  403.35
  4981.3  396.55  4996.1  389.91    5002  389.21  5005.2  389.71  5023.1  402.04
  5031.7  404.24  5088.2  402.52  5223.5  405.19    5274  407.84  5360.8   411.9
  5455.6  419.86  5618.6   438.1  5734.7  442.83  5785.4  443.97  5876.3  444.21
#Mann= 14 ,-1 , 0
  3049.6     .05       0  3207.3      .1       0  3433.7     .05       0
  4438.7     .16       0  4609.8     .12       0  4759.2     .16       0
  4966.6     .07       0  5031.7     .16       0  5088.2     .12       0
  5223.5     .16       0    5274     .12       0  5455.6     .16       0
  5734.7      .1       0  5785.4     .16       0
Bank Sta=4966.6,5031.7
XS Rating Curve= 0 ,0
Exp/Cntr=0.3,0.1