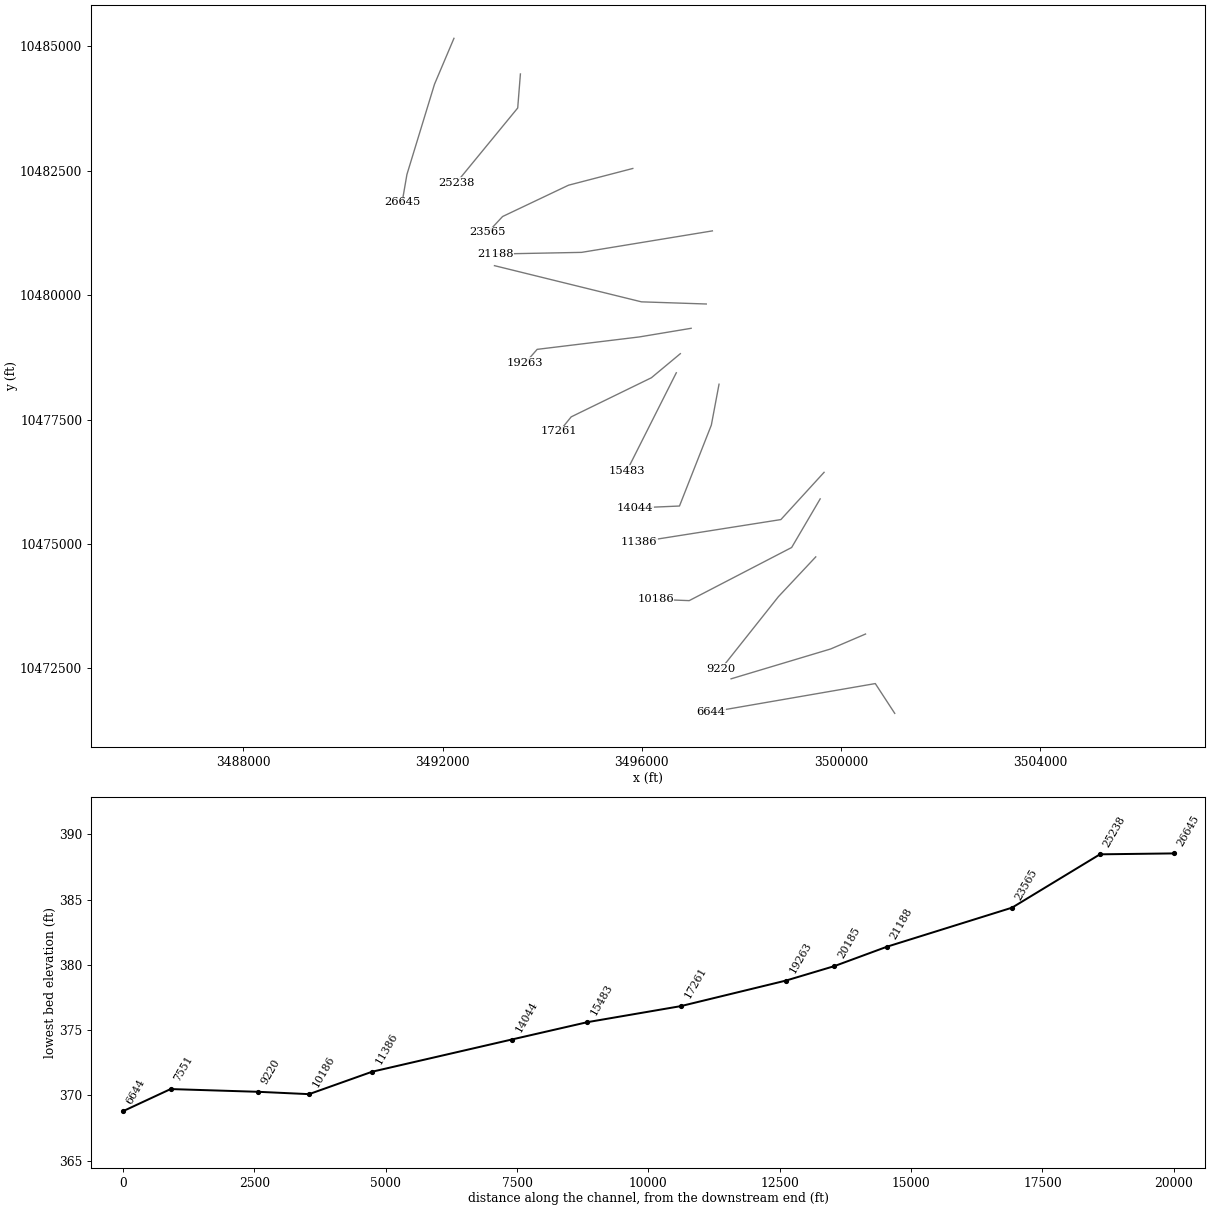
HEC-RAS study DAVIS CREEK.prj: DAVIS CREEK Base Level Engineering

--- DAVIS CREEK.g01 (geometry) --- (continued)

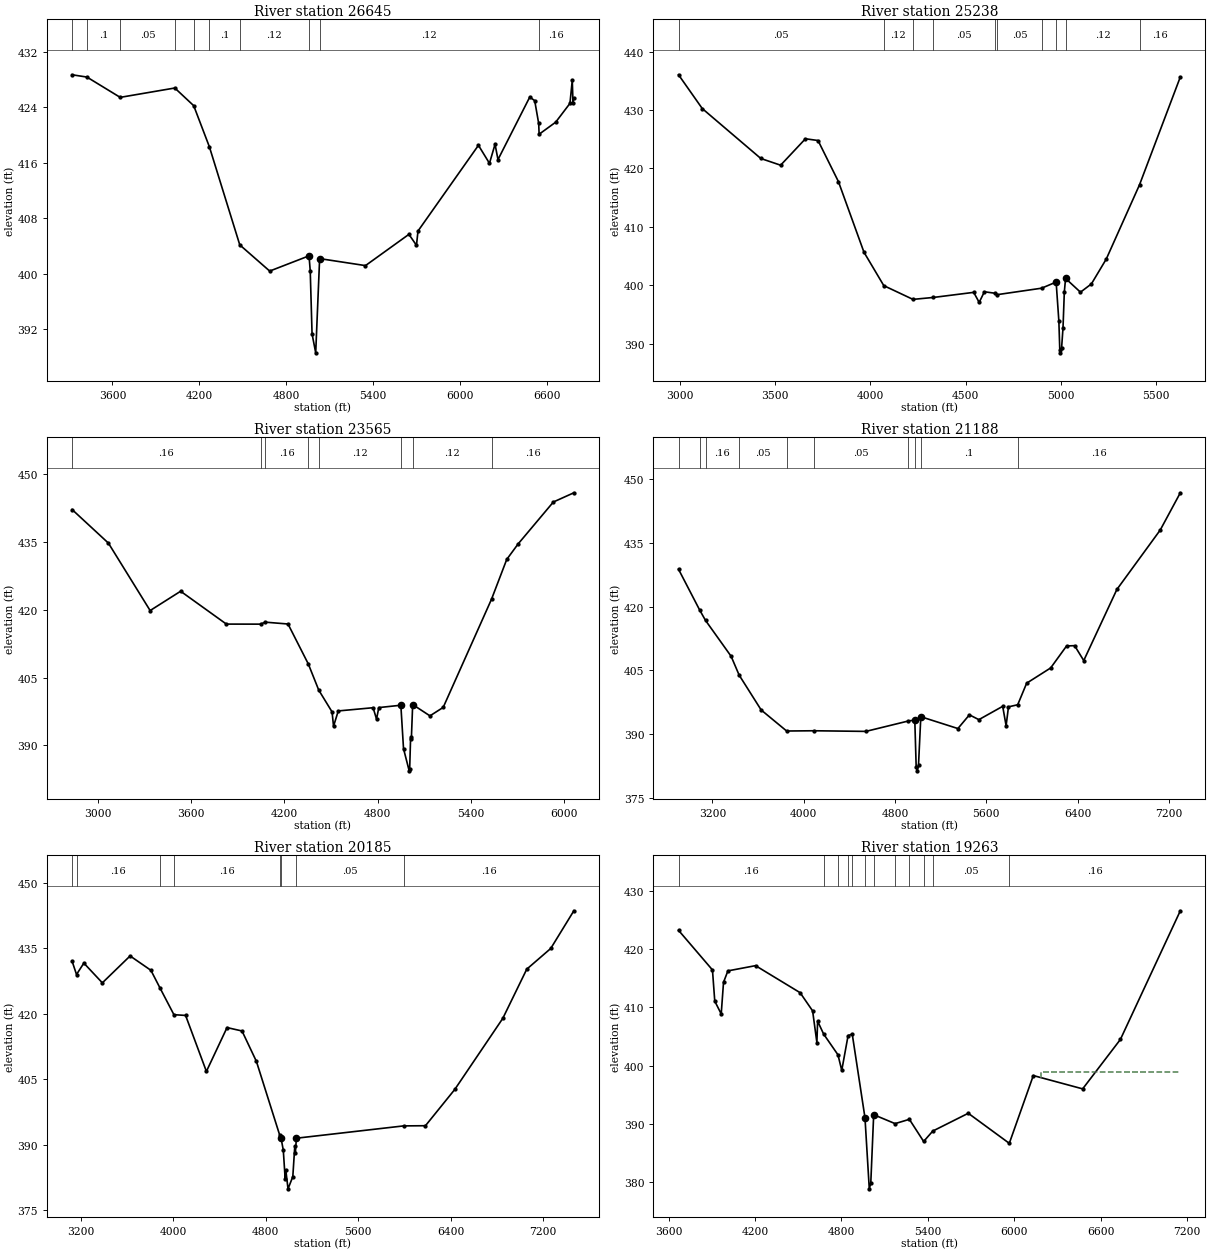
Type RM Length L Ch R = 1 ,26645   ,1407,1407,1407
BEGIN DESCRIPTION:
DAVIS CREEK 41.0
END DESCRIPTION:
XS GIS Cut Line= 4
      3492226.73     10485162.04      3491836.12     10484239.76
      3491282.73     10482427.69      3491185.35     10481865.03
#Sta/Elev= 30
  3321.1  428.68  3423.7  428.35  3653.6  425.42  4030.9  426.77  4161.6  424.22
    4270  418.28  4479.9  404.13  4686.7  400.35  4958.5  402.55  4966.8  400.38
  4979.4  391.29  5004.6  388.55  5031.7  402.15  5348.5  401.14  5648.6  405.65
  5700.9  404.07  5711.4  406.13  6129.1   418.5  6205.2   415.9  6243.8  418.65
  6264.1  416.44  6483.6  425.46  6517.8  424.95  6545.4  421.65  6548.4   420.1
  6662.9  421.84  6761.4  424.55  6777.4  427.89  6782.4  424.66  6788.4   425.3
#Mann= 10 ,-1 , 0
  3321.1     .05       0  3423.7      .1       0  3653.6     .05       0
  4030.9     .16       0  4161.6     .05       0    4270      .1       0
  4479.9     .12       0  4958.5     .07       0  5031.7     .12       0
  6545.4     .16       0
Bank Sta=4958.5,5031.7
XS Rating Curve= 0 ,0
Exp/Cntr=0.3,0.1

Type RM Length L Ch R = 1 ,25238   ,1673,1673,1673
BEGIN DESCRIPTION:
DAVIS CREEK 39.0
END DESCRIPTION:
XS GIS Cut Line= 3
      3493561.38     10484445.97      3493507.12     10483762.33
      3492271.17     10482255.33
#Sta/Elev= 30
  2992.7  436.02  3117.4  430.24  3424.7  421.71  3528.7  420.56  3659.1  425.08
  3725.2  424.78  3832.2  417.76  3966.4  405.68  4070.5  399.97  4223.7  397.62
  4330.8  397.95  4542.6  398.82  4571.3   397.1  4598.6  398.92  4654.6  398.67
  4666.3  398.43  4898.8  399.53  4975.4  400.58  4989.7  393.92  4994.6  388.98
  4997.4  388.48  5004.1  389.33  5011.5  392.75  5018.4  398.87  5024.9   401.2
  5103.1  398.85  5160.5  400.26  5238.7  404.52  5413.2  417.21  5627.5  435.65
#Mann= 10 ,-1 , 0
  2992.7     .05       0  4070.5     .12       0  4223.7     .16       0
  4330.8     .05       0  4654.6      .1       0  4666.3     .05       0
  4898.8     .12       0  4975.4     .07       0  5024.9     .12       0
  5413.2     .16       0
Bank Sta=4975.4,5024.9
XS Rating Curve= 0 ,0
Exp/Cntr=0.3,0.1

Type RM Length L Ch R = 1 ,23565   ,2377,2377,2377
BEGIN DESCRIPTION:
DAVIS CREEK 36.0
END DESCRIPTION:
XS GIS Cut Line= 4
      3495818.34     10482547.06      3494527.09     10482210.68
       3493203.3     10481581.34      3492910.31     10481266.64
#Sta/Elev= 30
  2832.8  442.14  3066.6  434.72  3335.3  419.81  3531.6  424.08  3826.1  416.82
  4046.6  416.81  4075.6  417.25  4222.8  416.84  4353.5  408.01  4420.7  402.23
  4506.5  397.41  4515.9  394.25  4546.4  397.63  4770.6  398.34  4792.7  395.82
  4807.4  398.37  4949.2  398.89  4966.4  389.29  5002.9  384.39  5006.1  384.89
  5011.8  391.52  5017.4  391.93  5025.3  399.04  5136.5  396.54  5221.8  398.41
    5533  422.33  5630.8  431.11  5704.2  434.54  5930.9   443.8  6062.9  445.84
#Mann= 8 ,-1 , 0
  2832.8     .16       0  4046.6      .1       0  4075.6     .16       0
  4353.5      .1       0  4420.7     .12       0  4949.2     .07       0
  5025.3     .12       0    5533     .16       0
Bank Sta=4949.2,5025.3
XS Rating Curve= 0 ,0
Exp/Cntr=0.3,0.1

Type RM Length L Ch R = 1 ,21188   ,1003,1003,1003
BEGIN DESCRIPTION:
DAVIS CREEK 33.0
END DESCRIPTION:
XS GIS Cut Line= 3
      3497416.52     10481292.77      3494789.05     10480860.95
      3493056.19      10480827.5
#Sta/Elev= 30
  2903.8  428.77  3088.2  419.23  3140.2  416.75  3364.3  408.33  3434.9  403.89
  3627.8   395.7  3850.9  390.76  4089.1  390.82  4544.9  390.67  4916.2  393.11
  4973.5  393.34  4985.8   382.2  4995.7   381.4    5006  382.72  5026.3  394.12
  5351.1  391.34  5451.9  394.56  5534.8  393.43  5743.5  396.56  5773.5     392
  5794.2  396.44  5875.1  396.93  5953.5     402  6163.6  405.58  6303.3  410.75
  6373.6  410.82  6453.6  407.32  6743.7  424.02  7123.8     438  7299.7  446.75
#Mann= 10 ,-1 , 0
  2903.8     .16       0  3088.2     .05       0  3140.2     .16       0
  3434.9     .05       0  3850.9     .16       0  4089.1     .05       0
  4916.2      .1       0  4973.5     .07       0  5026.3      .1       0
  5875.1     .16       0
Bank Sta=4973.5,5026.3
XS Rating Curve= 0 ,0
Exp/Cntr=0.3,0.1

Type RM Length L Ch R = 1 ,20185   ,922,922,922
BEGIN DESCRIPTION:
DAVIS CREEK 31.0
END DESCRIPTION:
XS GIS Cut Line= 3
        3497294.     10479823.53      3495991.93     10479866.93
      3493040.54     10480593.93
#Sta/Elev= 30
  3125.1  432.05  3163.6  428.98  3227.1  431.59  3387.1  427.07  3627.3  433.23
  3807.4  429.94  3885.7  425.91  4006.5  419.78  4107.5  419.61  4287.6  406.79
  4466.1  416.83  4595.8  416.05  4720.3  409.09  4922.1  392.19    4933  391.59
    4953  388.77  4969.3  382.15  4974.5  384.26  4993.9  379.91  5035.3  382.69
  5052.3  389.62  5057.5  388.15  5066.2   391.5  5994.3  394.32  6183.2  394.36
  6437.4  402.68  6852.4  418.93  7059.9   430.2  7267.4  434.94  7467.5  443.57
#Mann= 8 ,-1 , 0
  3125.1      .1       0  3163.6     .16       0  3885.7     .05       0
  4006.5     .16       0  4922.1     .05       0    4933    .035       0
  5066.2     .05       0  5994.3     .16       0
Bank Sta=4933,5066.2
XS Rating Curve= 0 ,0
Exp/Cntr=0.3,0.1

Type RM Length L Ch R = 1 ,19263   ,2002,2002,2002
BEGIN DESCRIPTION:
DAVIS CREEK 29.0
END DESCRIPTION:
XS GIS Cut Line= 4
      3496990.15     10479335.24      3495948.53     10479161.63
      3493897.75     10478912.07      3493659.06     10478640.83
#Sta/Elev= 30
  3669.2  423.28  3904.7  416.46  3920.7  411.09  3965.5  408.89  3981.5  414.34
  4011.9   416.3  4203.8   417.2    4513  412.55  4599.9  409.42  4629.6  403.97
  4634.6  407.65  4676.6  405.42  4775.9  401.86  4802.2  399.18  4846.2  405.17
    4875  405.42  4963.4  391.03  4993.3   378.8  5003.7   379.8  5023.8  391.56
  5172.4  390.02  5271.5  390.76  5370.6  386.95    5434  388.74  5680.4   391.8
  5965.2  386.63  6131.9  398.29  6474.4     396  6736.3   404.5  7152.4  426.64
#Mann= 12 ,-1 , 0
  3669.2     .16       0  4676.6     .05       0  4775.9     .16       0
  4846.2     .05       0    4875     .12       0  4963.4     .07       0
  5023.8     .12       0  5172.4     .16       0  5271.5     .05       0
  5370.6     .16       0    5434     .05       0  5965.2     .16       0
#XS Ineff= 2 , 0
                         6182.37          398.98
Permanent Ineff=
       F       F
Bank Sta=4963.4,5023.8
XS Rating Curve= 0 ,0
Exp/Cntr=0.3,0.1

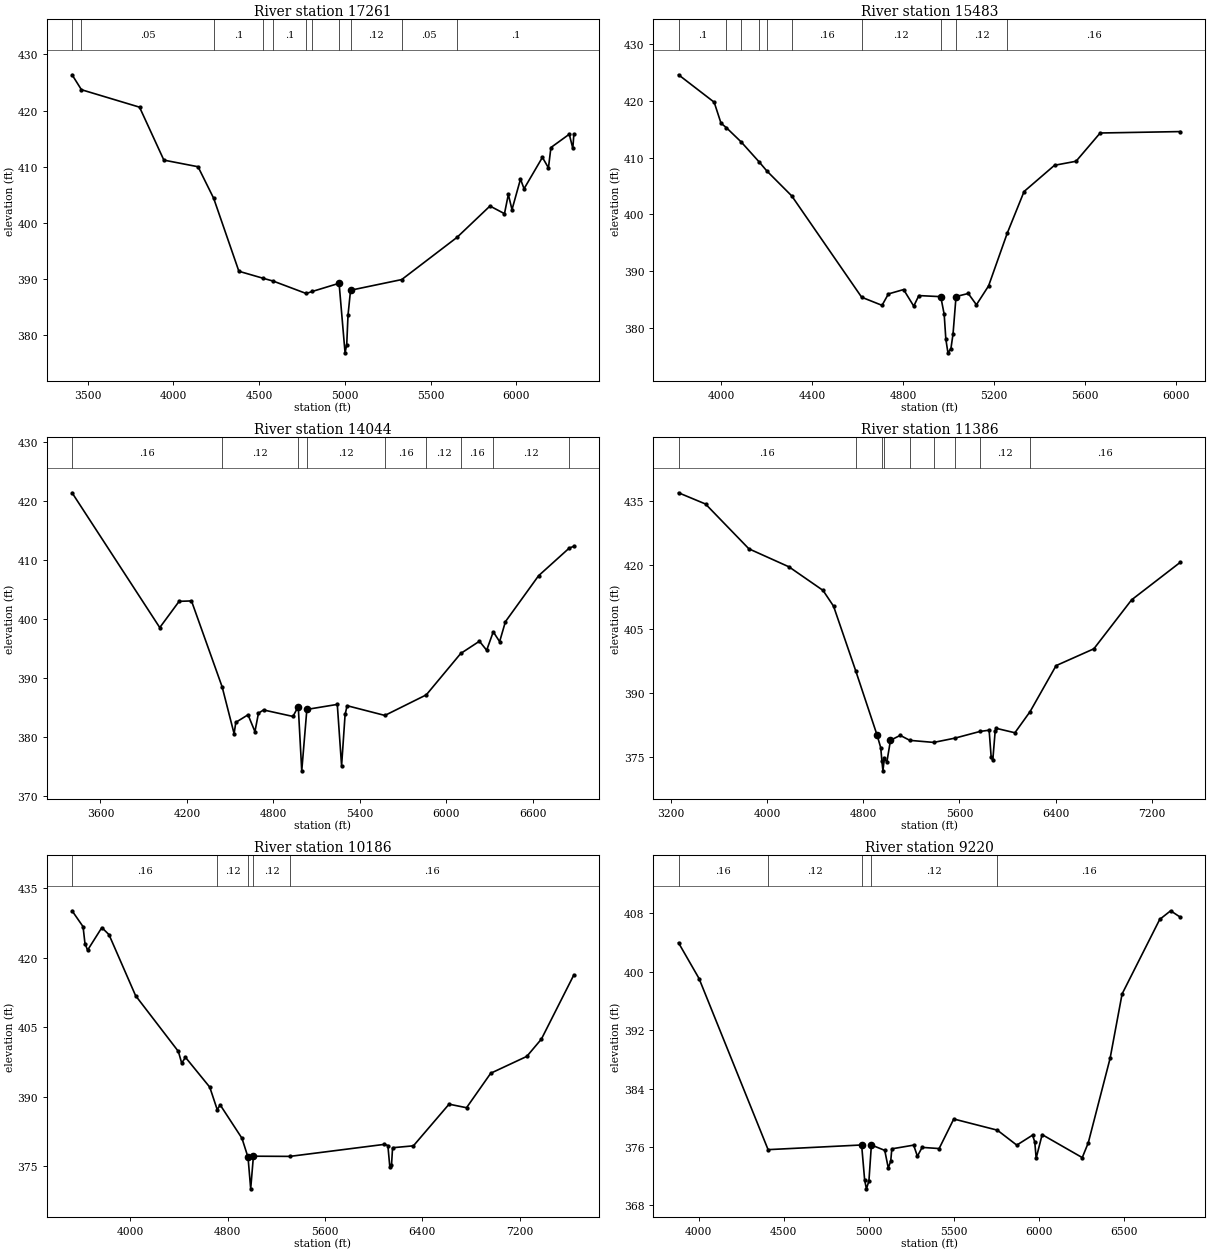
Type RM Length L Ch R = 1 ,17261   ,1778,1778,1778
BEGIN DESCRIPTION:
DAVIS CREEK 27.0
END DESCRIPTION:
XS GIS Cut Line= 4
      3496773.16     10478825.24      3496192.11     10478341.64
      3494581.34     10477555.73      3494342.65     10477262.79
#Sta/Elev= 30
  3409.6  426.37  3464.2  423.71    3803   420.6  3944.9  411.17  4144.1  409.99
  4235.3  404.37  4382.4  391.37  4525.1  390.11  4583.5  389.61  4774.8  387.41
  4810.1  387.77  4966.7  389.23  5001.5  376.84  5011.2   378.3  5018.8  383.58
  5033.5  387.99  5331.8  389.89  5654.4  397.41  5846.5  402.99  5931.1  401.63
  5953.6  405.05    5975  402.35  6024.5  407.79  6045.3  406.07  6152.3  411.66
  6187.5  409.79  6201.9  413.41  6308.9  415.78  6329.7  413.25  6335.7  415.78
#Mann= 11 ,-1 , 0
  3409.6     .16       0  3464.2     .05       0  4235.3      .1       0
  4525.1     .05       0  4583.5      .1       0  4774.8     .05       0
  4810.1     .12       0  4966.7     .07       0  5033.5     .12       0
  5331.8     .05       0  5654.4      .1       0
Bank Sta=4966.7,5033.5
XS Rating Curve= 0 ,0
Exp/Cntr=0.3,0.1

Type RM Length L Ch R = 1 ,15483   ,1439,1439,1439
BEGIN DESCRIPTION:
DAVIS CREEK 25.0
END DESCRIPTION:
XS GIS Cut Line= 2
      3496692.09     10478441.61      3495698.97     10476470.68
#Sta/Elev= 30
  3813.2  424.61  3969.9  419.78    4000  416.08  4023.8  415.28  4089.3  412.75
  4168.3  409.23  4201.4  407.67  4311.2  403.26  4618.6  385.41  4708.3  383.98
  4736.2  385.99  4803.1  386.76  4847.7  383.84  4870.1   385.7  4966.5  385.51
  4981.6   382.4  4988.9  378.01  4998.1  375.61  5011.3  376.36  5020.6  378.98
  5033.7  385.53  5087.5  386.07  5123.3  384.08  5176.8   387.4  5258.7  396.67
    5333  404.04  5466.8  408.66  5561.6  409.37  5667.6  414.35  6020.2   414.6
#Mann= 10 ,-1 , 0
  3813.2      .1       0  4023.8     .05       0  4089.3      .1       0
  4168.3     .05       0  4201.4      .1       0  4311.2     .16       0
  4618.6     .12       0  4966.5     .07       0  5033.7     .12       0
  5258.7     .16       0
Bank Sta=4966.5,5033.7
XS Rating Curve= 0 ,0
Exp/Cntr=0.3,0.1

Type RM Length L Ch R = 1 ,14044   ,2658,2658,2658
BEGIN DESCRIPTION:
DAVIS CREEK 20.0
END DESCRIPTION:
XS GIS Cut Line= 4
      3497550.09     10478211.83      3497395.73     10477390.51
      3496755.82     10475763.92      3495857.41     10475724.86
#Sta/Elev= 30
  3403.2  421.41  4011.9  398.56  4146.2  403.01  4232.1  403.08  4444.9  388.51
  4527.8  380.58  4539.8   382.5  4624.5  383.78  4672.5  380.93  4696.9  384.05
  4732.1   384.6  4936.2   383.5  4973.2  385.16  4997.4  374.28  5032.9  384.69
  5244.1  385.54  5273.9  375.13  5298.3  383.83  5312.3  385.32  5574.3  383.67
  5861.9  387.16  6100.7  394.17  6230.8  396.25  6280.8  394.72  6326.7  397.84
  6370.9  396.18    6411  399.56  6641.2  407.35  6854.7  412.05  6886.1  412.34
#Mann= 9 ,-1 , 0
  3403.2     .16       0  4444.9     .12       0  4973.2     .07       0
  5032.9     .12       0  5574.3     .16       0  5861.9     .12       0
  6100.7     .16       0  6326.7     .12       0  6854.7     .16       0
Bank Sta=4973.2,5032.9
XS Rating Curve= 0 ,0
Exp/Cntr=0.3,0.1

Type RM Length L Ch R = 1 ,11386   ,1200,1200,1200
BEGIN DESCRIPTION:
DAVIS CREEK 19.0
END DESCRIPTION:
XS GIS Cut Line= 3
      3499659.48     10476441.02      3498792.11     10475491.64
      3495942.15     10475041.65
#Sta/Elev= 30
  3265.2  436.95  3489.5  434.32  3850.2  423.82  4183.3   419.6  4466.3  414.08
  4553.7  410.39  4738.8  395.18  4915.6  380.18    4946  377.23  4956.1     374
  4964.3  371.81  4976.3  374.83  4996.6  373.81    5027  378.97    5108  380.12
  5187.8  378.95  5386.5  378.47    5564  379.48  5771.4  381.04    5847  381.33
  5863.9  375.07  5877.4  374.31  5897.6  381.19  5907.7  381.76  6061.3  380.73
  6187.8   385.7  6403.8  396.46  6717.7   400.4  7031.5  411.87  7436.4  420.67
#Mann= 9 ,-1 , 0
  3265.2     .16       0  4738.8     .12       0  4956.1     .07       0
  4976.3     .12       0  5187.8     .16       0  5386.5     .12       0
    5564     .16       0  5771.4     .12       0  6187.8     .16       0
Bank Sta=4915.6,5027
XS Rating Curve= 0 ,0
Exp/Cntr=0.3,0.1

Type RM Length L Ch R = 1 ,10186   ,966,966,966
BEGIN DESCRIPTION:
DAVIS CREEK 17.0
END DESCRIPTION:
XS GIS Cut Line= 4
      3499581.36     10475907.19      3499008.43     10474930.59
      3496951.13     10473862.88      3496275.55     10473888.86
#Sta/Elev= 30
  3520.3  430.15  3610.7  426.72  3626.4  423.08  3647.9  421.64  3765.1  426.52
  3823.8     425  4042.6  411.82  4394.4  399.77  4421.6  397.25    4453  398.49
  4652.6  392.05  4713.8   387.2  4738.5  388.21  4917.4  381.01  4967.3  376.89
  4989.1  370.09  5011.5  377.14  5311.6   377.1  6089.4   379.7  6117.1  379.45
  6133.6  374.71  6146.9  375.14  6155.8  378.97  6327.1  379.38  6620.3  388.38
  6763.9  387.61    6963  395.06  7259.7   398.7  7379.7  402.44  7646.5   416.3
#Mann= 5 ,-1 , 0
  3520.3     .16       0  4713.8     .12       0  4967.3     .07       0
  5011.5     .12       0  5311.6     .16       0
Bank Sta=4967.3,5011.5
XS Rating Curve= 0 ,0
Exp/Cntr=0.3,0.1

Type RM Length L Ch R = 1 ,9220    ,1669,1669,1669
BEGIN DESCRIPTION:
DAVIS CREEK 15.0
END DESCRIPTION:
XS GIS Cut Line= 3
      3499492.12     10474741.66      3498742.11     10473941.64
       3497592.1     10472491.63
#Sta/Elev= 30
  3882.2  403.98  4002.6  399.09  4408.2  375.64  4957.6  376.28  4975.4  371.46
  4985.8  370.27  5000.5  371.36  5014.9  376.28  5093.4  375.54  5114.2  373.12
  5128.6  374.08    5135  375.75  5263.2  376.26  5285.1  374.74  5312.9  375.95
  5412.8  375.79  5498.8  379.84  5754.7  378.31  5868.9  376.26  5961.6  377.63
  5974.6  376.69  5982.7  374.47  6017.9   377.7  6253.5  374.55  6288.7  376.57
  6416.9  388.14  6487.4  396.97  6708.5  407.19  6772.6  408.37  6829.5  407.49
#Mann= 5 ,-1 , 0
  3882.2     .16       0  4408.2     .12       0  4957.6     .07       0
  5014.9     .12       0  5754.7     .16       0
Bank Sta=4957.6,5014.9
XS Rating Curve= 0 ,0
Exp/Cntr=0.3,0.1

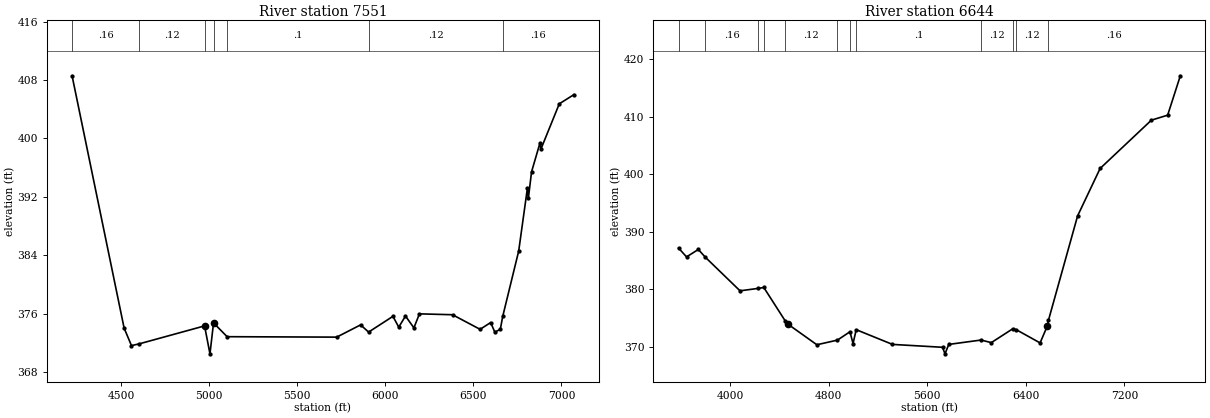
Type RM Length L Ch R = 1 ,7551    ,907,907,907
BEGIN DESCRIPTION:
DAVIS CREEK 12.0
END DESCRIPTION:
XS GIS Cut Line= 3
      3500492.12     10473191.65      3499792.11     10472891.64
      3497792.06     10472291.63
#Sta/Elev= 30
  4220.6  408.59  4516.2  374.01  4557.9  371.61  4600.6  371.84  4973.1  374.31
  5003.7  370.48    5024  374.72  5101.1  372.83  5723.5  372.77  5859.2  374.45
  5904.6  373.46  6042.8  375.62  6075.8  374.14  6114.1  375.66  6161.9  374.04
  6193.3  375.96  6381.2  375.84  6537.8  373.84  6597.8  374.77  6621.3  373.46
  6652.6  373.84  6666.2   375.6    6757  384.57  6806.6   393.2  6811.9  391.81
  6830.1  395.43    6878  399.39  6883.2  398.54  6987.6  404.75  7070.3     406
#Mann= 7 ,-1 , 0
  4220.6     .16       0  4600.6     .12       0  4973.1     .07       0
    5024     .12       0  5101.1      .1       0  5904.6     .12       0
  6666.2     .16       0
Bank Sta=4973.1,5024
XS Rating Curve= 0 ,0
Exp/Cntr=0.3,0.1

Type RM Length L Ch R = 1 ,6644    ,1809,1809,1809
BEGIN DESCRIPTION:
DAVIS CREEK 10.0
END DESCRIPTION:
XS GIS Cut Line= 3
      3501078.75     10471597.23      3500688.11     10472196.21
      3497380.78     10471623.29
#Sta/Elev= 30
  3582.7  387.18  3647.7  385.64  3743.2  386.93  3801.2  385.56  4081.7  379.74
  4231.4  380.17  4274.6  380.32  4449.2  374.48  4471.2  373.93  4705.1  370.36
  4872.2  371.17  4973.7  372.62  4998.7  370.57  5024.5  372.98  5318.8  370.42
  5724.8  369.92  5744.8  368.78  5775.5  370.42  6037.3  371.18  6120.6  370.73
  6292.7  373.11  6322.3  372.99  6516.4  370.68  6576.2  373.67  6584.2   374.6
  6820.8  392.77  7003.5  401.02  7419.6  409.42  7551.6  410.29  7654.4  417.14
#Mann= 12 ,-1 , 0
  3582.7     .12       0  3801.2     .16       0  4231.4     .12       0
  4274.6     .16       0  4449.2     .12       0  4872.2      .1       0
  4973.7     .07       0  5024.5      .1       0  6037.3     .12       0
  6292.7     .05       0  6322.3     .12       0  6584.2     .16       0
Bank Sta=4471.2,6576.2
XS Rating Curve= 0 ,0
Exp/Cntr=0.3,0.1