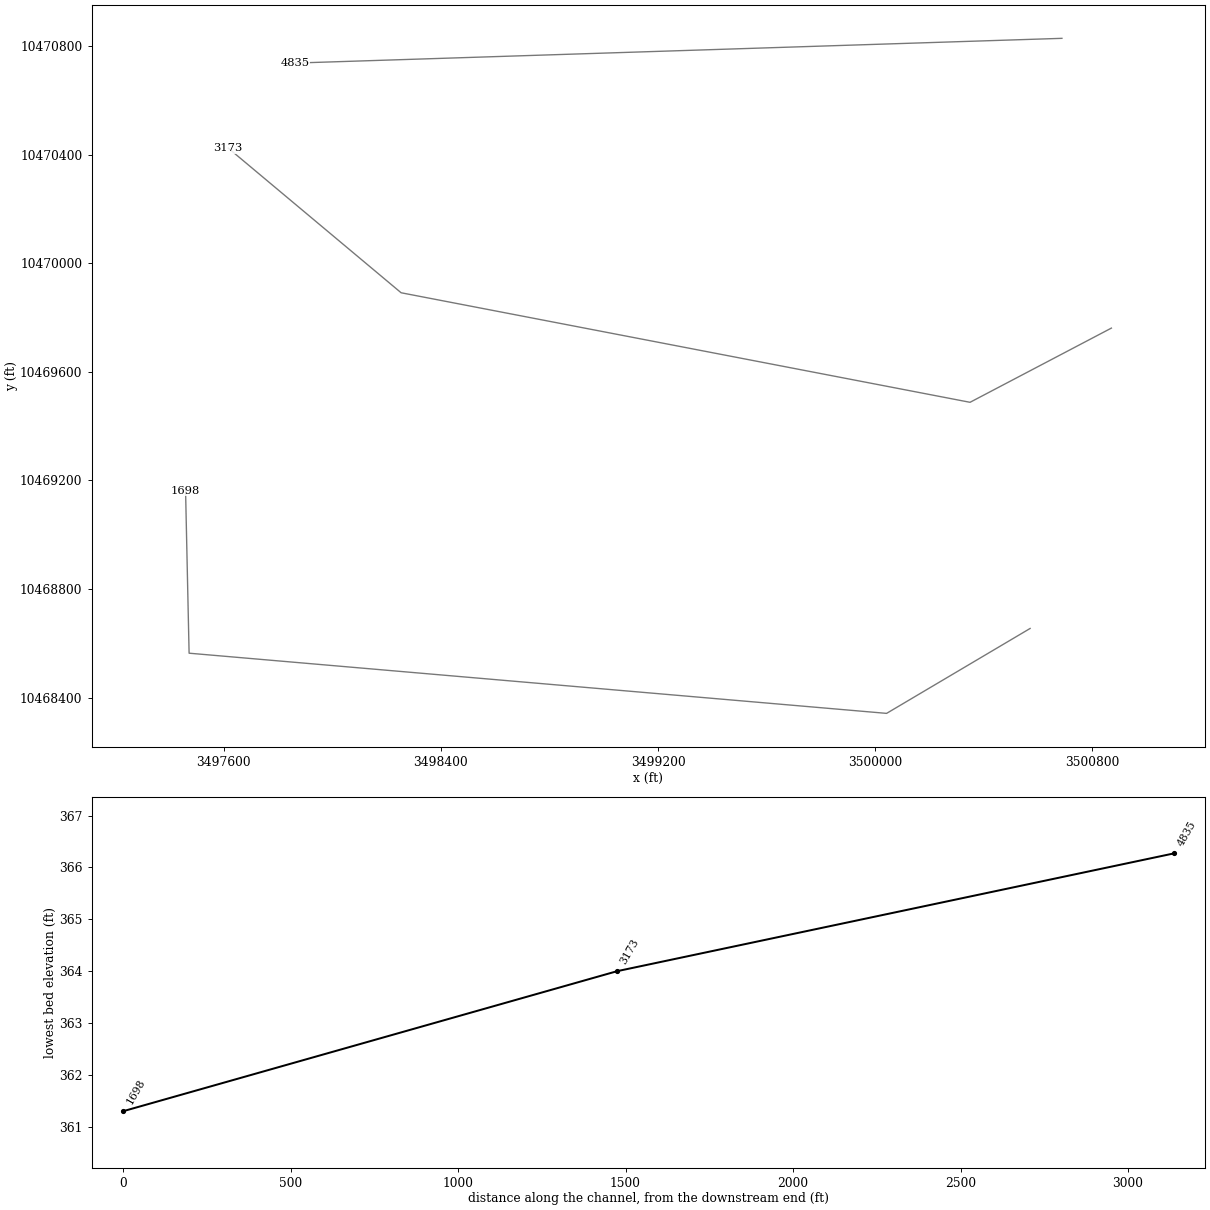
HEC-RAS study DAVIS CREEK.prj: DAVIS CREEK Base Level Engineering

--- DAVIS CREEK.g01 (geometry) --- (continued)

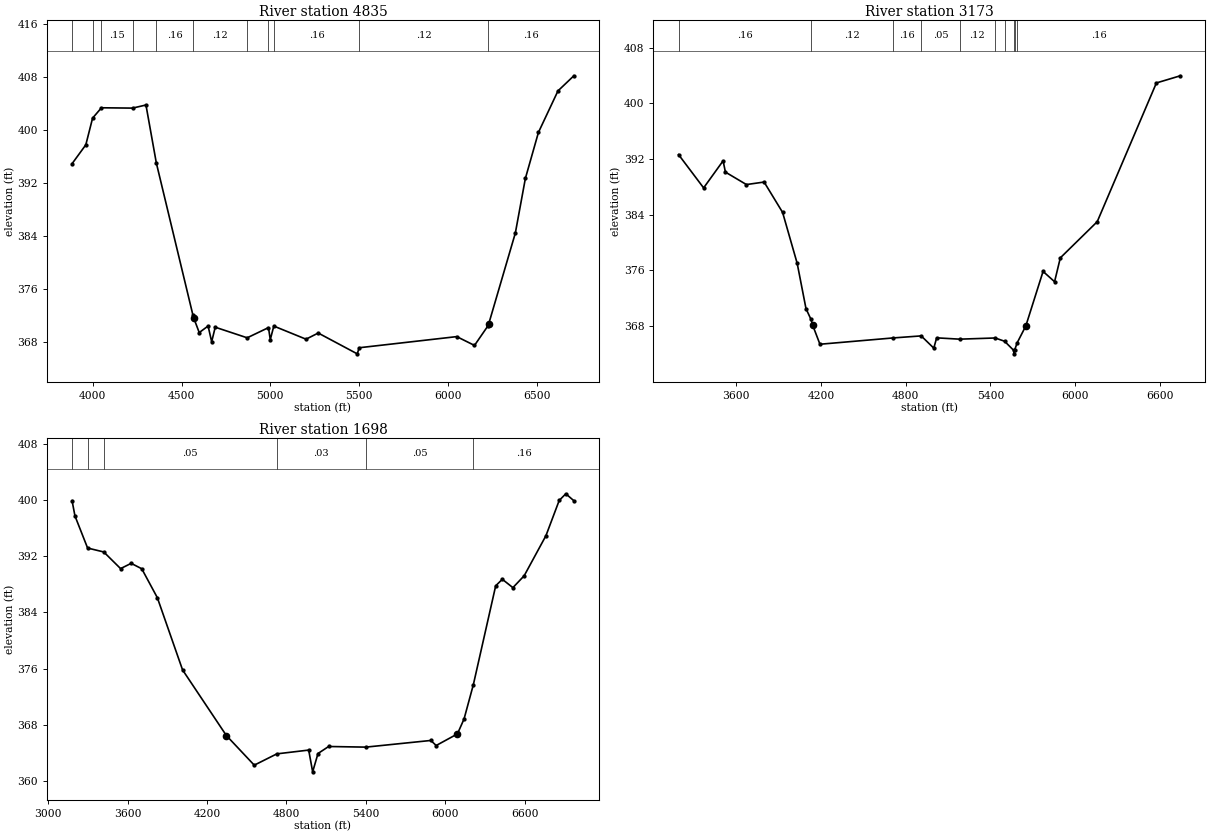
Type RM Length L Ch R = 1 ,4835    ,1662,1662,1662
BEGIN DESCRIPTION:
DAVIS CREEK 7.0
END DESCRIPTION:
XS GIS Cut Line= 2
      3500688.15     10470829.03      3497862.62     10470737.88
#Sta/Elev= 30
  3883.1  394.97  3960.6  397.82  3998.7  401.85  4048.7  403.41  4223.9  403.36
  4299.4  403.83  4357.9  395.07  4564.1   372.1  4569.5  371.61  4599.5  369.48
  4649.5  370.47  4669.6  368.09  4689.6  370.29  4869.7  368.69  4989.7  370.23
  4999.7  368.41  5019.7  370.46  5201.2  368.48  5269.9  369.41  5489.7  366.27
  5500.8  367.19  6050.3  368.87  6150.3  367.54  6225.3  370.46  6230.4  370.79
  6380.4   384.5  6436.9  392.74  6510.5  399.69  6620.6  405.96  6710.1  408.24
#Mann= 11 ,-1 , 0
  3883.1     .16       0  3998.7      .1       0  4048.7     .15       0
  4223.9      .1       0  4357.9     .16       0  4564.1     .12       0
  4869.7     .16       0  4989.7     .07       0  5019.7     .16       0
  5500.8     .12       0  6225.3     .16       0
Bank Sta=4569.5,6230.4
XS Rating Curve= 0 ,0
Exp/Cntr=0.3,0.1

Type RM Length L Ch R = 1 ,3173    ,1475,1475,1475
BEGIN DESCRIPTION:
DAVIS CREEK 4.0
END DESCRIPTION:
XS GIS Cut Line= 4
      3500870.43     10469761.33      3500349.57     10469487.88
      3498253.22     10469891.52      3497616.15     10470424.58
#Sta/Elev= 30
  3191.8  392.65  3369.5  387.86  3507.4  391.75  3523.8  390.13  3672.5  388.34
  3797.9   388.7  3928.7  384.34  4032.1  377.01  4094.6  370.49    4130  368.95
  4141.4  368.14  4193.3  365.38  4707.5  366.28  4910.3  366.58  4999.5  364.82
  5019.9   366.3  5182.5  366.11  5434.2  366.28  5500.9  365.81  5565.3   364.5
    5568     364  5571.3   364.5  5590.4   365.6  5651.3  368.01  5773.5  375.85
    5855  374.37  5895.7   377.8  6157.1     383  6576.1  402.95  6745.6  403.98
#Mann= 10 ,-1 , 0
  3191.8     .16       0    4130     .12       0  4707.5     .16       0
  4910.3     .05       0  5182.5     .12       0  5434.2     .05       0
  5500.9     .12       0  5565.3     .03       0  5571.3     .12       0
  5590.4     .16       0
Bank Sta=4141.4,5651.3
XS Rating Curve= 0 ,0
Exp/Cntr=0.3,0.1

Type RM Length L Ch R = 1 ,1698    ,0,0,0
BEGIN DESCRIPTION:
DAVIS CREEK 1.0
END DESCRIPTION:
XS GIS Cut Line= 4
      3500570.94     10468654.55      3500042.11     10468341.64
      3497471.97      10468563.4      3497458.95      10469162.4
#Sta/Elev= 30
  3179.3  399.92  3201.2  397.75  3296.7  393.18  3418.9  392.62  3546.1  390.25
  3626.1     391    3706  390.23  3823.9  386.11  4014.6  375.82  4345.8  366.47
  4556.6  362.25  4727.2  363.86  4968.1   364.4    4998   361.3  5038.4  363.91
  5118.7  364.91  5399.7  364.82  5891.5  365.77  5931.7  365.05  6092.3   366.7
  6142.5  368.83  6212.7  373.71  6381.7   387.8  6431.7  388.73  6511.7  387.54
    6597  389.23  6761.8  394.95  6861.8  399.96  6911.8  400.91  6972.6  399.92
#Mann= 6 ,-1 , 0
  3179.3     .05       0  3296.7     .16       0  3418.9     .05       0
  4727.2     .03       0  5399.7     .05       0  6212.7     .16       0
Bank Sta=4345.8,6092.3
XS Rating Curve= 0 ,0
Exp/Cntr=0.3,0.1

Chan Stop Cuts=-1
Use User Specified Reach Order=0
Composite Channel Slope=5