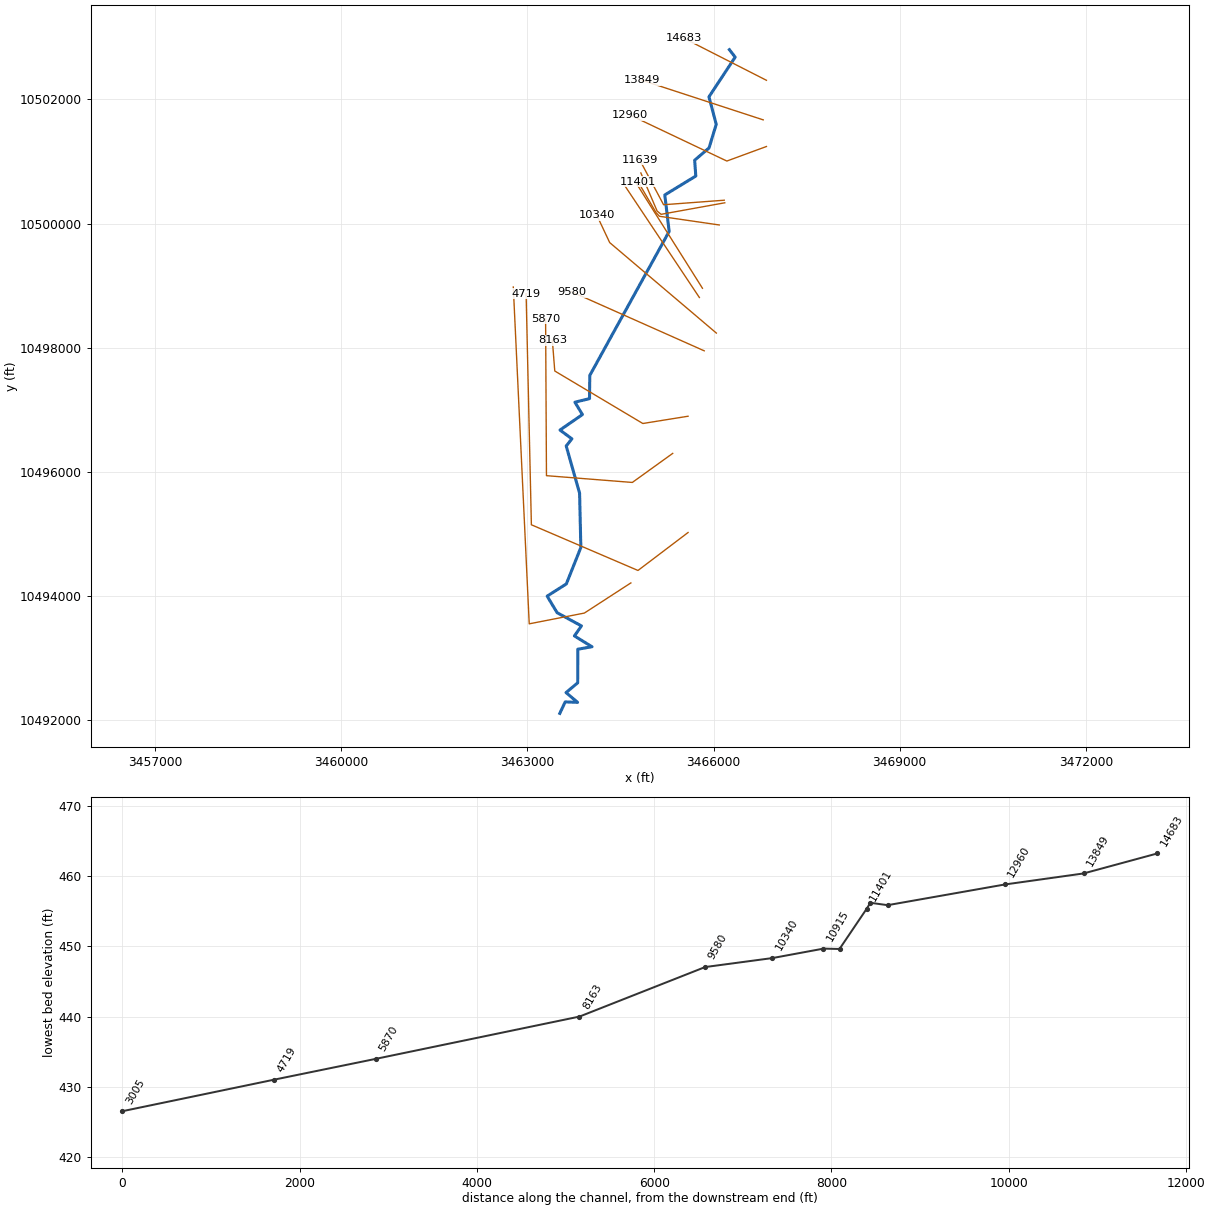
--- EATON BRANCH.prj (project) ---

Proj Title=EATON BRANCH Base Level Engineering
Current Plan=p01
Default Exp/Contr=0.3,0.1
English Units
Geom File=g01
Flow File=f01
Plan File=p01
BEGIN DESCRIPTION:
EATON BRANCH
END DESCRIPTION:

--- EATON BRANCH.p01 (plan) ---

Plan Title=Multiple Run
Short Identifier=Multiple
Geom File=g01
Flow File=f01
Subcritical Flow
K Sum by GR= 0
Std Step Tol= 0.01
Critical Tol= 0.01
Num of Std Step Trials= 20
Max Error Tol= 0.3
Flow Tol Ratio= 0.001
Split Flow NTrial= 30
Split Flow Tol= 0.02
Split Flow Ratio= 0.02
Log Output Level= 0
Friction Slope Method= 1
Unsteady Friction Slope Method= 2
Unsteady Bridges Friction Slope Method= 1
Parabolic Critical Depth
Global Vel Dist=  1 , 1 , 1
Global Log Level= 0
CheckData=True
Encroach Param= -1, 0, 0, 0
BEGIN DESCRIPTION:
Multiple Run
END DESCRIPTION:

--- EATON BRANCH.f01 (steady flow) ---

Flow Title=Multiple
Number of Profiles=7
Profile Names=10-year,25-year,50-year,1pct_min,100-year,1pct_plu,500-year
River Rch & RM= EATON BRANCH,Reach-1,14683
     887    1208    1471    1307    1767    2390    2544
River Rch & RM= EATON BRANCH,Reach-1,12960
    1333    1854    2287    2055    2779    3759    4096
River Rch & RM= EATON BRANCH,Reach-1,8163
    1547    2164    2679    2414    3265    4416    4841
Boundary for River Rch & Prof#=EATON BRANCH,Reach-1,1
Up Type=0
Dn Type=3
Dn Slope=0.005
Boundary for River Rch & Prof#=EATON BRANCH,Reach-1,2
Up Type=0
Dn Type=3
Dn Slope=0.005
Boundary for River Rch & Prof#=EATON BRANCH,Reach-1,3
Up Type=0
Dn Type=3
Dn Slope=0.005
Boundary for River Rch & Prof#=EATON BRANCH,Reach-1,4
Up Type=0
Dn Type=3
Dn Slope=0.005
Boundary for River Rch & Prof#=EATON BRANCH,Reach-1,5
Up Type=0
Dn Type=3
Dn Slope=0.005
Boundary for River Rch & Prof#=EATON BRANCH,Reach-1,6
Up Type=0
Dn Type=3
Dn Slope=0.005
Boundary for River Rch & Prof#=EATON BRANCH,Reach-1,7
Up Type=0
Dn Type=3
Dn Slope=0.005

--- EATON BRANCH.g01 (geometry) ---

Geom Title=Existing Conditions

River Reach=EATON BRANCH,Reach-1
Reach XY= 30
      3466256.02     10502803.06      3466349.03     10502683.19
      3465926.56     10502042.60      3466043.74     10501599.89
      3465927.85     10501218.70      3465695.53     10501020.12
      3465714.66     10500765.53      3465214.83     10500460.82
      3465285.03     10499872.99      3464005.41     10497550.27
      3464001.54     10497176.50      3463765.80     10497119.11
      3463887.10     10496919.62      3463525.49     10496670.05
      3463716.57     10496528.44      3463625.69     10496412.64
      3463841.30     10495651.19      3463861.53     10494776.94
      3463627.48     10494188.58      3463318.17     10493991.91
      3463478.91     10493725.00      3463871.33     10493511.58
      3463757.86     10493350.27      3464041.30     10493175.90
      3463812.46     10493136.46      3463810.81     10492593.83
      3463622.92     10492436.90      3463809.13     10492279.09
      3463609.42     10492286.42      3463522.11     10492101.64

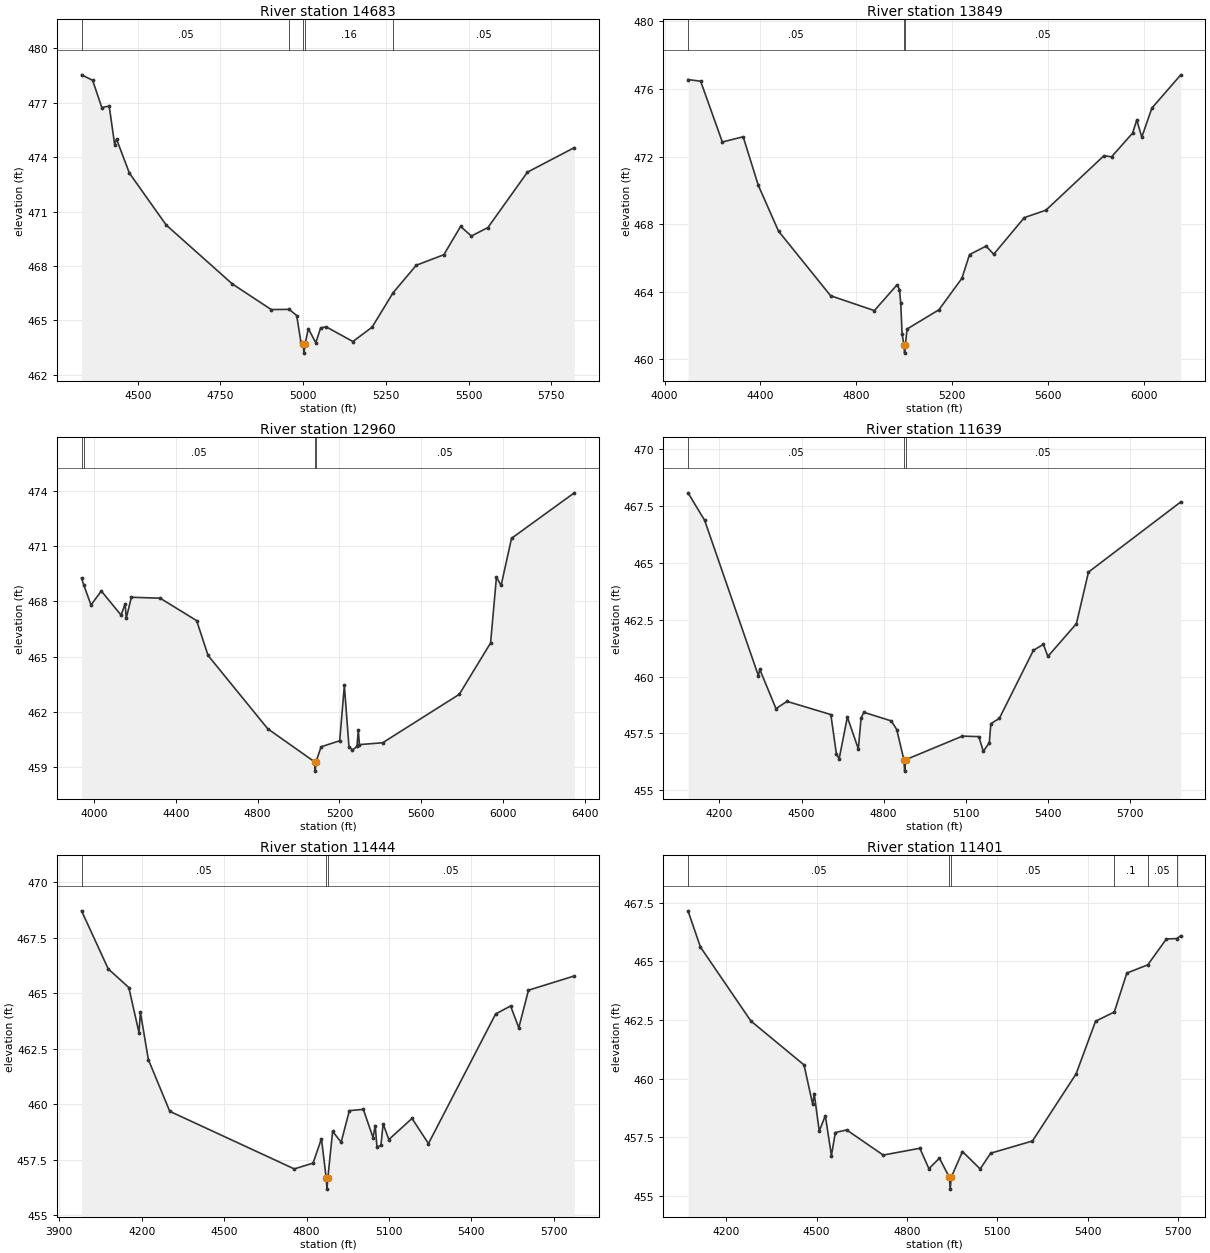
Type RM Length L Ch R = 1,14683,834,834,834
BEGIN DESCRIPTION:
EATON BRANCH 22.0
END DESCRIPTION:
XS GIS Cut Line= 2
      3466852.84     10502309.44      3465525.92     10502985.91
#Sta/Elev= 30
  4330.1  478.53  4363.5  478.23  4391.3  476.73  4413.6  476.81  4430.2  474.69
  4435.8  474.99  4474.6  473.12  4585.8  470.26  4785.9  467.01  4903.4  465.60
  4957.8  465.61  4980.4  465.27  4993.2  463.81  4999.6  463.70  5002.4  463.20
  5005.6  463.70  5015.6  464.55  5038.1  463.77  5052.7  464.59  5069.3  464.65
  5150.3  463.84  5208.3  464.63  5271.5  466.52  5341.7  468.04  5425.1  468.62
  5475.8  470.18  5508.4  469.65  5558.5  470.12  5677.9  473.17  5819.5  474.52
#Mann=5,-1,0
  4330.1    0.05       0  4957.8    0.16       0  4999.6    0.07       0
  5005.6    0.16       0  5271.5    0.05       0
Bank Sta=4999.6,5005.6
Exp/Cntr=0.3,0.1

Type RM Length L Ch R = 1,13849,889,889,889
BEGIN DESCRIPTION:
EATON BRANCH 20.0
END DESCRIPTION:
XS GIS Cut Line= 2
      3466800.72     10501671.43      3464847.59     10502309.45
#Sta/Elev= 30
  4098.0  476.56  4150.7  476.46  4241.1  472.86  4328.0  473.17  4391.1  470.29
  4475.3  467.58  4692.7  463.75  4875.0  462.87  4969.7  464.40  4979.6  464.12
  4984.9  463.34  4990.7  461.48  4998.3  460.85  5001.0  460.35  5004.3  460.85
  5011.5  461.78  5144.3  462.92  5239.9  464.78  5271.8  466.19  5340.9  466.69
  5372.7  466.21  5500.3  468.38  5590.4  468.82  5832.4  472.05  5863.9  471.98
  5951.9  473.39  5969.1  474.16  5990.2  473.15  6032.2  474.87  6152.7  476.84
#Mann=3,-1,0
  4098.0    0.05       0  4998.3    0.03       0  5004.3    0.05       0
Bank Sta=4998.3,5004.3
Exp/Cntr=0.3,0.1

Type RM Length L Ch R = 1,12960,1321,1321,1321
BEGIN DESCRIPTION:
EATON BRANCH 18.0
END DESCRIPTION:
XS GIS Cut Line= 3
      3466852.81     10501241.74      3466214.79     10501007.37
      3464652.31     10501749.55
#Sta/Elev= 30
  3938.8  469.26  3950.2  468.87  3985.0  467.80  4035.4  468.56  4132.1  467.25
  4151.9  467.87  4157.3  467.08  4182.4  468.22  4323.1  468.17  4501.7  466.95
  4557.4  465.06  4849.2  461.08  5078.9  459.28  5081.7  458.78  5084.9  459.28
  5110.2  460.10  5201.1  460.43  5223.8  463.43  5246.5  460.10  5263.6  459.93
  5285.7  460.12  5292.0  461.01  5297.5  460.22  5411.2  460.32  5785.8  462.95
  5938.9  465.74  5967.6  469.32  5990.3  468.86  6041.3  471.42  6348.3  473.89
#Mann=4,-1,0
  3938.8    0.08       0  3950.2    0.05       0  5078.9    0.03       0
  5084.9    0.05       0
Bank Sta=5078.9,5084.9
Exp/Cntr=0.3,0.1

Type RM Length L Ch R = 1,11639,195,195,195
BEGIN DESCRIPTION:
EATON BRANCH 17.0
END DESCRIPTION:
XS GIS Cut Line= 3
      3466172.63     10500375.83      3465195.20     10500302.91
      3464809.83     10501026.78
#Sta/Elev= 30
  4085.3  468.09  4146.0  466.88  4342.4  460.04  4347.4  460.32  4406.7  458.59
  4446.8  458.91  4607.1  458.33  4627.3  456.60  4637.4  456.38  4667.4  458.22
  4707.5  456.82  4717.6  458.18  4727.6  458.43  4827.9  458.05  4847.9  457.67
  4873.9  456.34  4876.7  455.84  4879.9  456.34  5087.5  457.38  5147.7  457.36
  5164.0  456.71  5186.0  457.09  5191.7  457.93  5222.6  458.16  5347.2  461.16
  5383.7  461.42  5400.0  460.89  5504.2  462.33  5548.2  464.60  5885.5  467.69
#Mann=3,-1,0
  4085.3    0.05       0  4873.9   0.035       0  4879.9    0.05       0
Bank Sta=4873.9,4879.9
Exp/Cntr=0.3,0.1

Type RM Length L Ch R = 1,11444,43,43,43
BEGIN DESCRIPTION:
Mapping XS 6e0c59b4
END DESCRIPTION:
XS GIS Cut Line= 4
      3466181.32     10500334.16      3465155.27     10500148.40
      3465091.03     10500200.48      3464828.87     10500815.08
#Sta/Elev= 30
  3980.9  468.70  4077.9  466.09  4152.9  465.25  4190.0  463.22  4195.1  464.14
  4224.0  462.01  4302.0  459.68  4755.2  457.09  4823.6  457.35  4854.1  458.45
  4871.4  456.68  4874.2  456.18  4877.4  456.68  4894.7  458.78  4925.8  458.29
  4955.7  459.71  5006.5  459.77  5041.9  458.50  5049.8  459.04  5056.2  458.07
  5070.6  458.15  5078.6  459.12  5099.4  458.41  5183.7  459.36  5243.6  458.23
  5488.1  464.06  5542.5  464.42  5572.4  463.44  5607.7  465.13  5774.5  465.77
#Mann=3,-1,0
  3980.9    0.05       0  4871.4   0.035       0  4877.4    0.05       0
Bank Sta=4871.4,4877.4
Exp/Cntr=0.3,0.1

Type RM Length L Ch R = 1,11401,305,305,305
BEGIN DESCRIPTION:
Mapping XS c8f49bea
END DESCRIPTION:
XS GIS Cut Line= 4
      3466092.77     10499976.52      3465127.49     10500117.15
      3465073.67     10500176.18      3464782.00     10500676.17
#Sta/Elev= 30
  4073.9  467.15  4115.0  465.61  4282.3  462.46  4458.6  460.59  4487.4  458.91
  4492.4  459.37  4509.1  457.77  4529.3  458.43  4549.5  456.73  4562.5  457.71
  4600.1  457.82  4721.3  456.75  4842.7  457.04  4872.9  456.17  4907.7  456.62
  4940.7  455.80  4943.4  455.30  4946.7  455.80  4984.1  456.90  5042.8  456.16
  5077.7  456.83  5216.2  457.35  5361.0  460.21  5425.5  462.45  5487.6  462.84
  5529.2  464.50  5598.6  464.85  5660.3  465.95  5694.7  465.97  5708.1  466.09
#Mann=6,-1,0
  4073.9    0.05       0  4940.7   0.035       0  4946.7    0.05       0
  5487.6     0.1       0  5598.6    0.05       0  5694.7     0.1       0
Bank Sta=4940.7,4946.7
Exp/Cntr=0.3,0.1

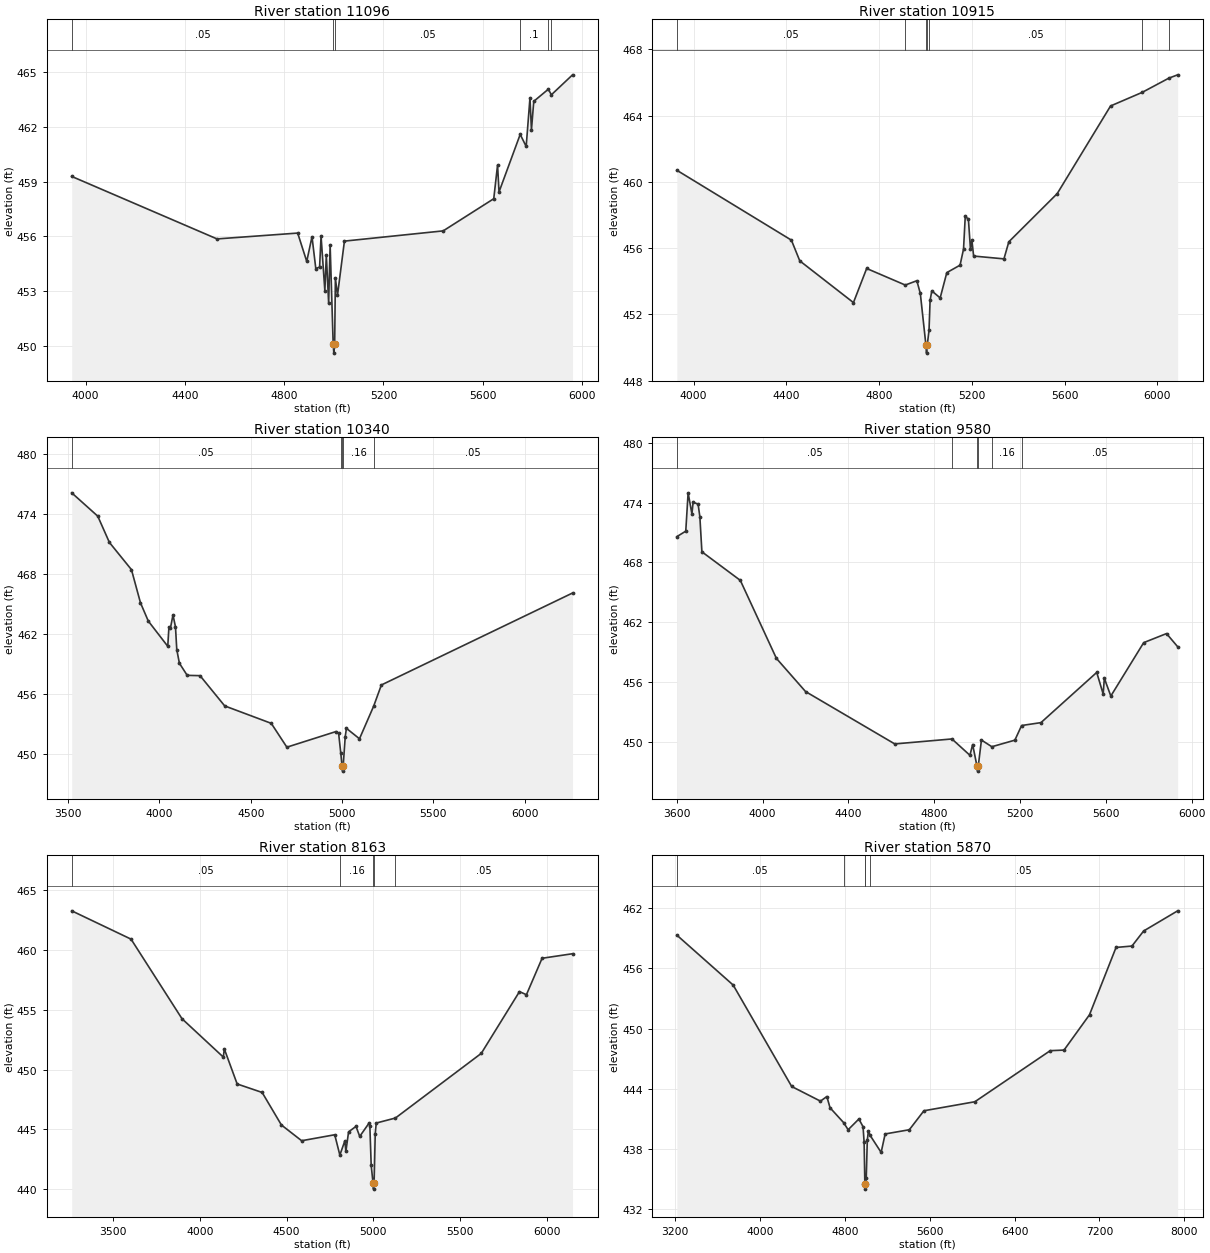
Type RM Length L Ch R = 1,11096,181,181,181
BEGIN DESCRIPTION:
EATON BRANCH 15.0
END DESCRIPTION:
XS GIS Cut Line= 2
      3465821.91     10498955.73      3464746.35     10500662.74
#Sta/Elev= 30
  3944.4  459.28  4529.8  455.86  4854.7  456.18  4891.2  454.63  4912.4  455.98
  4927.7  454.24  4943.0  454.32  4948.9  456.01  4964.2  453.02  4970.1  454.98
  4979.5  452.34  4985.4  455.54  4997.7  450.11  5000.4  449.61  5003.7  450.11
  5006.6  453.71  5015.1  452.78  5043.0  455.74  5440.9  456.30  5644.6  458.06
  5659.9  459.90  5665.8  458.43  5751.1  461.58  5775.2  460.92  5790.5  463.58
  5796.4  461.83  5805.8  463.39  5864.2  464.05  5876.9  463.75  5962.0  464.84
#Mann=6,-1,0
  3944.4    0.05       0  4997.7    0.04       0  5003.7    0.05       0
  5751.1     0.1       0  5864.2    0.05       0  5876.9     0.1       0
Bank Sta=4997.7,5003.7
Exp/Cntr=0.3,0.1

Type RM Length L Ch R = 1,10915,575,575,575
BEGIN DESCRIPTION:
EATON BRANCH 14.0
END DESCRIPTION:
XS GIS Cut Line= 2
      3465772.10     10498806.82      3464574.17     10500603.72
#Sta/Elev= 30
  3927.8  460.70  4421.9  456.48  4458.0  455.23  4689.4  452.71  4746.4  454.77
  4912.9  453.77  4962.8  454.03  4977.8  453.26  5001.8  450.16  5004.6  449.66
  5007.8  450.16  5015.3  451.04  5019.9  452.84  5027.3  453.42  5063.3  452.99
  5092.0  454.52  5149.1  454.97  5164.1  455.94  5171.5  457.91  5185.1  457.75
  5194.1  455.92  5200.1  456.48  5207.6  455.52  5338.4  455.35  5359.4  456.38
  5568.1  459.29  5798.1  464.58  5934.3  465.40  6049.5  466.26  6087.4  466.46
#Mann=7,-1,0
  3927.8    0.05       0  4912.9    0.16       0  5001.8    0.07       0
  5007.8    0.16       0  5015.3    0.05       0  5934.3     0.1       0
  6049.5    0.05       0
Bank Sta=5001.8,5007.8
Exp/Cntr=0.3,0.1

Type RM Length L Ch R = 1,10340,760,760,760
BEGIN DESCRIPTION:
EATON BRANCH 13.0
END DESCRIPTION:
XS GIS Cut Line= 3
      3466045.50     10498233.95      3464326.77     10499692.26
      3464118.45     10500134.95
#Sta/Elev= 30
  3519.4  476.10  3662.1  473.77  3725.8  471.15  3846.7  468.43  3896.1  465.12
  3938.9  463.30  4045.5  460.78  4052.0  462.72  4059.8  462.57  4074.1  463.90
  4087.8  462.73  4094.9  460.45  4109.2  459.09  4152.0  457.88  4222.3  457.85
  4357.4  454.83  4612.4  453.09  4697.9  450.71  4967.0  452.27  4981.3  452.11
  4993.1  450.14  5000.3  448.82  5003.1  448.32  5006.3  448.82  5017.6  451.77
  5024.2  452.59  5095.6  451.55  5173.2  454.80  5215.6  456.92  6262.7  466.10
#Mann=5,-1,0
  3519.4    0.05       0  4993.1    0.16       0  5000.3    0.07       0
  5006.3    0.16       0  5173.2    0.05       0
Bank Sta=5000.3,5006.3
Exp/Cntr=0.3,0.1

Type RM Length L Ch R = 1,9580,1417,1417,1417
BEGIN DESCRIPTION:
EATON BRANCH 10.0
END DESCRIPTION:
XS GIS Cut Line= 2
      3465850.25     10497947.45      3463717.49     10498896.79
#Sta/Elev= 30
  3600.4  470.58  3642.1  471.13  3653.1  474.98  3670.8  472.86  3676.3  474.03
  3699.6  473.85  3707.8  472.58  3717.3  469.06  3896.4  466.19  4064.6  458.36
  4200.4  455.03  4616.3  449.77  4882.8  450.27  4966.6  448.63  4979.3  449.71
  4999.5  447.54  5002.3  447.04  5005.5  447.54  5020.3  450.16  5068.8  449.49
  5176.1  450.15  5207.6  451.62  5297.8  451.91  5557.7  456.95  5587.7  454.78
  5593.1  456.36  5623.4  454.58  5776.6  459.94  5883.0  460.85  5934.9  459.53
#Mann=6,-1,0
  3600.4    0.05       0  4882.8    0.12       0  4999.5    0.07       0
  5005.5    0.12       0  5068.8    0.16       0  5207.6    0.05       0
Bank Sta=4999.5,5005.5
Exp/Cntr=0.3,0.1

Type RM Length L Ch R = 1,8163,2293,2293,2293
BEGIN DESCRIPTION:
EATON BRANCH 7.0
END DESCRIPTION:
XS GIS Cut Line= 4
      3465589.83     10496892.79      3464860.63     10496775.60
      3463441.35     10497621.95      3463402.30     10498116.69
#Sta/Elev= 30
  3260.7  463.29  3602.8  460.92  3896.5  454.26  4134.7  451.05  4140.5  451.73
  4214.5  448.80  4358.5  448.09  4469.5  445.37  4586.3  444.05  4777.0  444.55
  4806.5  442.85  4835.4  444.04  4841.3  443.16  4856.8  444.79  4899.6  445.25
  4921.1  444.41  4973.6  445.50  4979.4  445.32  4987.2  441.99  4997.9  440.50
  5000.6  440.00  5003.9  440.50  5010.5  444.65  5016.4  445.53  5126.9  445.95
  5621.8  451.36  5842.0  456.53  5882.1  456.27  5972.4  459.32  6148.0  459.70
#Mann=5,-1,0
  3260.7    0.05       0  4806.5    0.16       0  4997.9    0.07       0
  5003.9    0.16       0  5126.9    0.05       0
Bank Sta=4997.9,5003.9
Exp/Cntr=0.3,0.1

Type RM Length L Ch R = 1,5870,1151,1151,1151
BEGIN DESCRIPTION:
EATON BRANCH 5.0
END DESCRIPTION:
XS GIS Cut Line= 4
      3465342.38     10496293.81      3464691.35     10495825.08
      3463307.37     10495934.36      3463293.48     10498462.12
#Sta/Elev= 30
  3218.2  459.32  3749.2  454.34  4300.5  444.23  4571.4  442.77  4631.6  443.23
  4661.7  442.11  4788.7  440.64  4832.2  439.92  4933.5  440.99  4972.6  440.22
  4982.7  438.68  4989.7  434.50  4992.4  434.00  4995.7  434.50  5002.7  435.08
  5012.7  438.87  5022.8  439.79  5039.7  439.35  5143.1  437.66  5180.9  439.50
  5408.7  439.92  5546.0  441.81  6026.0  442.71  6736.0  447.80  6866.0  447.86
  7106.0  451.38  7356.0  458.09  7506.0  458.23  7616.0  459.73  7936.5  461.74
#Mann=5,-1,0
  3218.2    0.05       0  4788.7    0.16       0  4989.7    0.07       0
  4995.7    0.16       0  5039.7    0.05       0
Bank Sta=4989.7,4995.7
Exp/Cntr=0.3,0.1

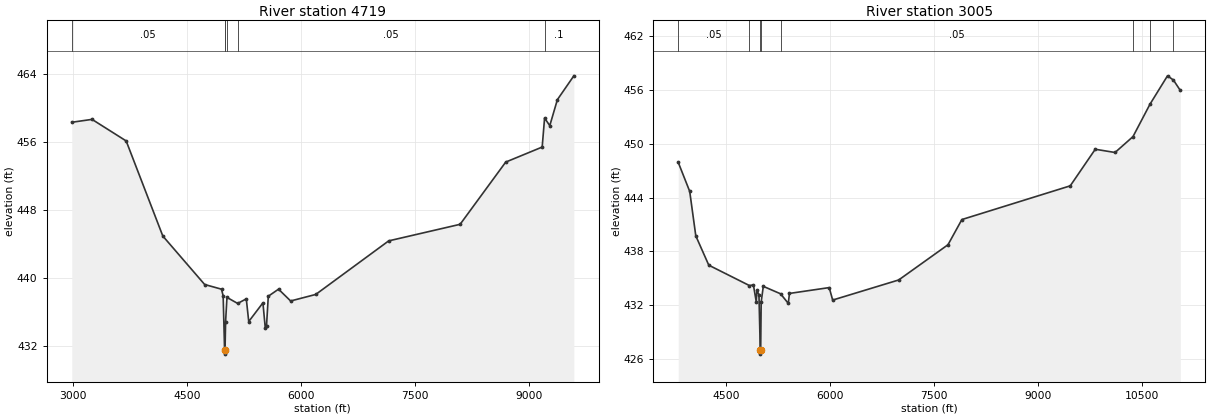
Type RM Length L Ch R = 1,4719,1714,1714,1714
BEGIN DESCRIPTION:
EATON BRANCH 1.0
END DESCRIPTION:
XS GIS Cut Line= 4
      3465589.80     10495017.79      3464782.50     10494405.80
      3463064.32     10495142.69      3462979.29     10498868.34
#Sta/Elev= 30
  2985.7  458.34  3252.5  458.68  3701.9  456.14  4184.2  444.94  4735.1  439.23
  4956.7  438.68  4978.5  437.89  4997.2  431.53  5000.0  431.03  5003.2  431.53
  5010.7  434.87  5028.6  437.71  5169.6  437.00  5283.1  437.54  5315.2  434.87
  5502.0  437.07  5533.4  434.07  5549.1  434.33  5572.7  437.85  5707.5  438.68
  5866.8  437.29  6197.3  438.06  7157.6  444.37  8097.8  446.32  8698.0  453.65
  9178.1  455.42  9209.7  458.84  9278.1  457.94  9378.1  461.00  9594.9  463.81
#Mann=6,-1,0
  2985.7    0.05       0  4997.2   0.035       0  5003.2    0.05       0
  5028.6     0.1       0  5169.6    0.05       0  9209.7     0.1       0
Bank Sta=4997.2,5003.2
Exp/Cntr=0.3,0.1

Type RM Length L Ch R = 1,3005,0,0,0
BEGIN DESCRIPTION:
Mapping XS 780794de
END DESCRIPTION:
XS GIS Cut Line= 4
      3464667.96     10494205.31      3463918.48     10493719.08
      3463029.60     10493545.47      3462772.65     10498976.03
#Sta/Elev= 30
  3814.4  447.93  3979.8  444.69  4067.5  439.73  4254.7  436.46  4839.8  434.19
  4897.7  434.26  4938.4  432.40  4948.6  433.64  4977.7  433.17  4996.6  427.04
  4999.3  426.54  5002.6  427.04  5009.8  432.35  5040.3  434.10  5288.8  433.27
  5400.4  432.20  5417.3  433.31  5990.1  433.96  6040.1  432.57  6991.2  434.81
  7702.0  438.74  7902.2  441.55  9463.9  445.31  9824.3  449.39 10109.6  449.03
 10368.1  450.80 10613.4  454.42 10865.5  457.58 10950.7  457.11 11050.1  455.95
#Mann=8,-1,0
  3814.4    0.05       0  4839.8    0.16       0  4996.6    0.07       0
  5002.6    0.16       0  5288.8    0.05       0 10368.1     0.1       0
 10613.4    0.16       0 10950.7     0.1       0
Bank Sta=4996.6,5002.6
Exp/Cntr=0.3,0.1

Chan Stop Cuts=-1