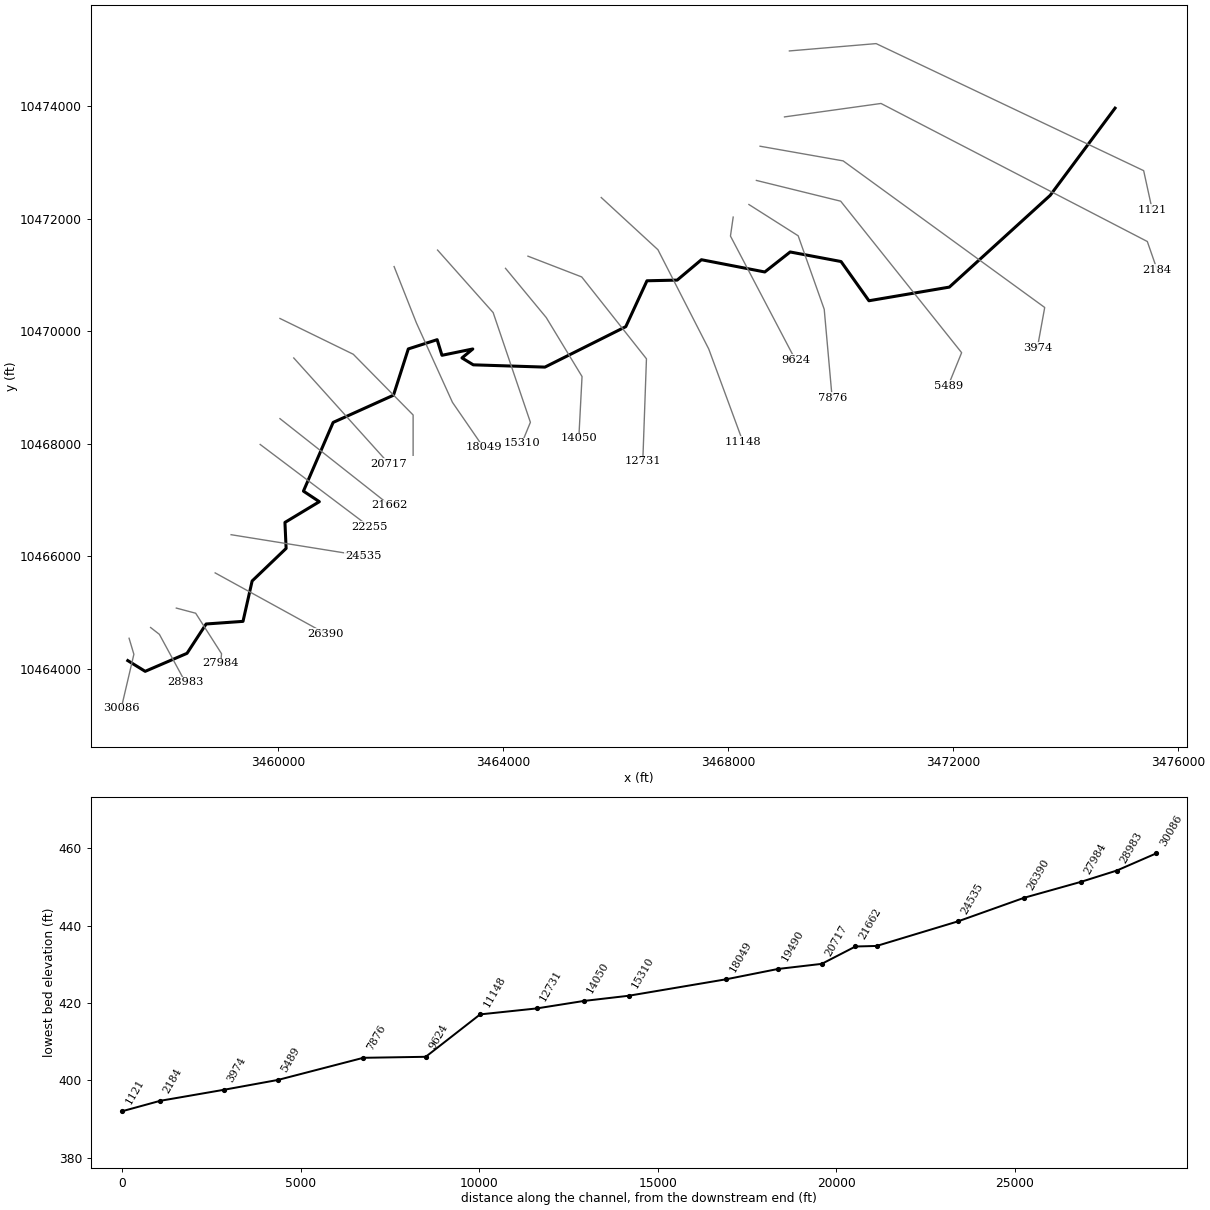
--- GENTRY CREEK.prj (project) ---

Proj Title=GENTRY CREEK Base Level Engineering
Current Plan=p01
Default Exp/Contr=0.3,0.1
English Units
Geom File=g01
Flow File=f01
Plan File=p01
Y Axis Title=Elevation
X Axis Title(PF)=Main Channel Distance
X Axis Title(XS)=Station
BEGIN DESCRIPTION:
GENTRY CREEK
END DESCRIPTION:
DSS Export Rating Curves= 0
DSS Export Rating Curve Sorted= 0
DSS Export Volume Flow Curves= 0
DXF OffsetX= 0
DXF OffsetY= 0
DXF ScaleX= 1
DXF ScaleY= 10

--- GENTRY CREEK.p01 (plan) ---

Plan Title=Multiple Run
Short Identifier=Multiple
Geom File=g01
Flow File=f01
Subcritical Flow
K Sum by GR= 0
Std Step Tol= 0.01
Critical Tol= 0.01
Num of Std Step Trials= 20
Max Error Tol= 0.3
Flow Tol Ratio= 0.001
Split Flow NTrial= 30
Split Flow Tol= 0.02
Split Flow Ratio= 0.02
Log Output Level= 0
Friction Slope Method= 1
Unsteady Friction Slope Method= 2
Unsteady Bridges Friction Slope Method= 1
Parabolic Critical Depth
Global Vel Dist=  1 , 1 , 1
Global Log Level= 0
CheckData=True
Encroach Param= -1, 0, 0, 0
BEGIN DESCRIPTION:
Multiple Run
END DESCRIPTION:

--- GENTRY CREEK.f01 (steady flow) ---

Flow Title=Multiple
Program Version=4.10
Number of Profiles= 7
Profile Names=10-year,25-year,50-year,1pct_min,100-year,1pct_plu,500-year
River Rch & RM=GENTRY CREEK,Reach-1         ,30086
     917    1258    1537    1370    1853    2506    2687
River Rch & RM=GENTRY CREEK,Reach-1         ,26390
    1655    2342    2923    2657    3593    4859    5420
River Rch & RM=GENTRY CREEK,Reach-1         ,22255
    2702    3895    4921    4518    6111    8264    9411
River Rch & RM=GENTRY CREEK,Reach-1         ,15310
    2800    4028    5081    4656    6297    8516    9659
River Rch & RM=GENTRY CREEK,Reach-1         ,14050
    3139    4538    5744    5280    7141    9657   11024
River Rch & RM=GENTRY CREEK,Reach-1         ,11148
    3378    4902    6220    5731    7751   10482   12021
River Rch & RM=GENTRY CREEK,Reach-1         ,9624
    3575    5187    6582    6062    8199   11088   12706
River Rch & RM=GENTRY CREEK,Reach-1         ,5489
    3631    5262    6671    6138    8302   11227   12840
River Rch & RM=GENTRY CREEK,Reach-1         ,2184
    4872    7132    9104    8427   11397   15413   17841
River Rch & RM=GENTRY CREEK,Reach-1         ,1121
    4872    7132    9104    8427   11397   15413   17841
Boundary for River Rch & Prof#=GENTRY CREEK,Reach-1         , 1
Up Type= 0
Dn Type= 3
Dn Slope=0.002
Boundary for River Rch & Prof#=GENTRY CREEK,Reach-1         , 2
Up Type= 0
Dn Type= 3
Dn Slope=0.002
Boundary for River Rch & Prof#=GENTRY CREEK,Reach-1         , 3
Up Type= 0
Dn Type= 3
Dn Slope=0.002
Boundary for River Rch & Prof#=GENTRY CREEK,Reach-1         , 4
Up Type= 0
Dn Type= 3
Dn Slope=0.002
Boundary for River Rch & Prof#=GENTRY CREEK,Reach-1         , 5
Up Type= 0
Dn Type= 3
Dn Slope=0.002
Boundary for River Rch & Prof#=GENTRY CREEK,Reach-1         , 6
Up Type= 0
Dn Type= 3
Dn Slope=0.002
Boundary for River Rch & Prof#=GENTRY CREEK,Reach-1         , 7
Up Type= 0
Dn Type= 3
Dn Slope=0.002
DSS Import GetInterval= 0
DSS Import GetPeak= 0
DSS Import FillOption= 0

--- GENTRY CREEK.g01 (geometry) ---

Geom Title=Existing Conditions
Program Version=4.10

River Reach=GENTRY CREEK    ,Reach-1
Reach XY= 30
      3457336.29     10464149.95      3457645.25     10463959.24
      3458388.41     10464279.28      3458728.02     10464800.46
      3459382.88     10464846.99       3459545.1     10465564.39
      3460148.72     10466142.86      3460128.04      10466604.5
      3460738.98     10466973.05      3460456.44     10467160.29
      3460984.23     10468381.08      3462055.91     10468864.44
      3462319.57     10469686.71      3462831.51     10469850.84
      3462917.36      10469573.4      3463465.18     10469685.78
      3463272.63     10469526.55      3463473.65      10469404.1
      3464746.37     10469363.68      3466182.57     10470082.25
      3466559.14     10470897.28      3467095.48     10470909.17
      3467526.36     10471271.26      3468652.02     10471053.76
      3469103.04      10471408.9      3470006.45     10471239.12
      3470502.21     10470542.33      3471930.77     10470784.86
      3473721.96      10472414.7       3474874.2     10473963.74

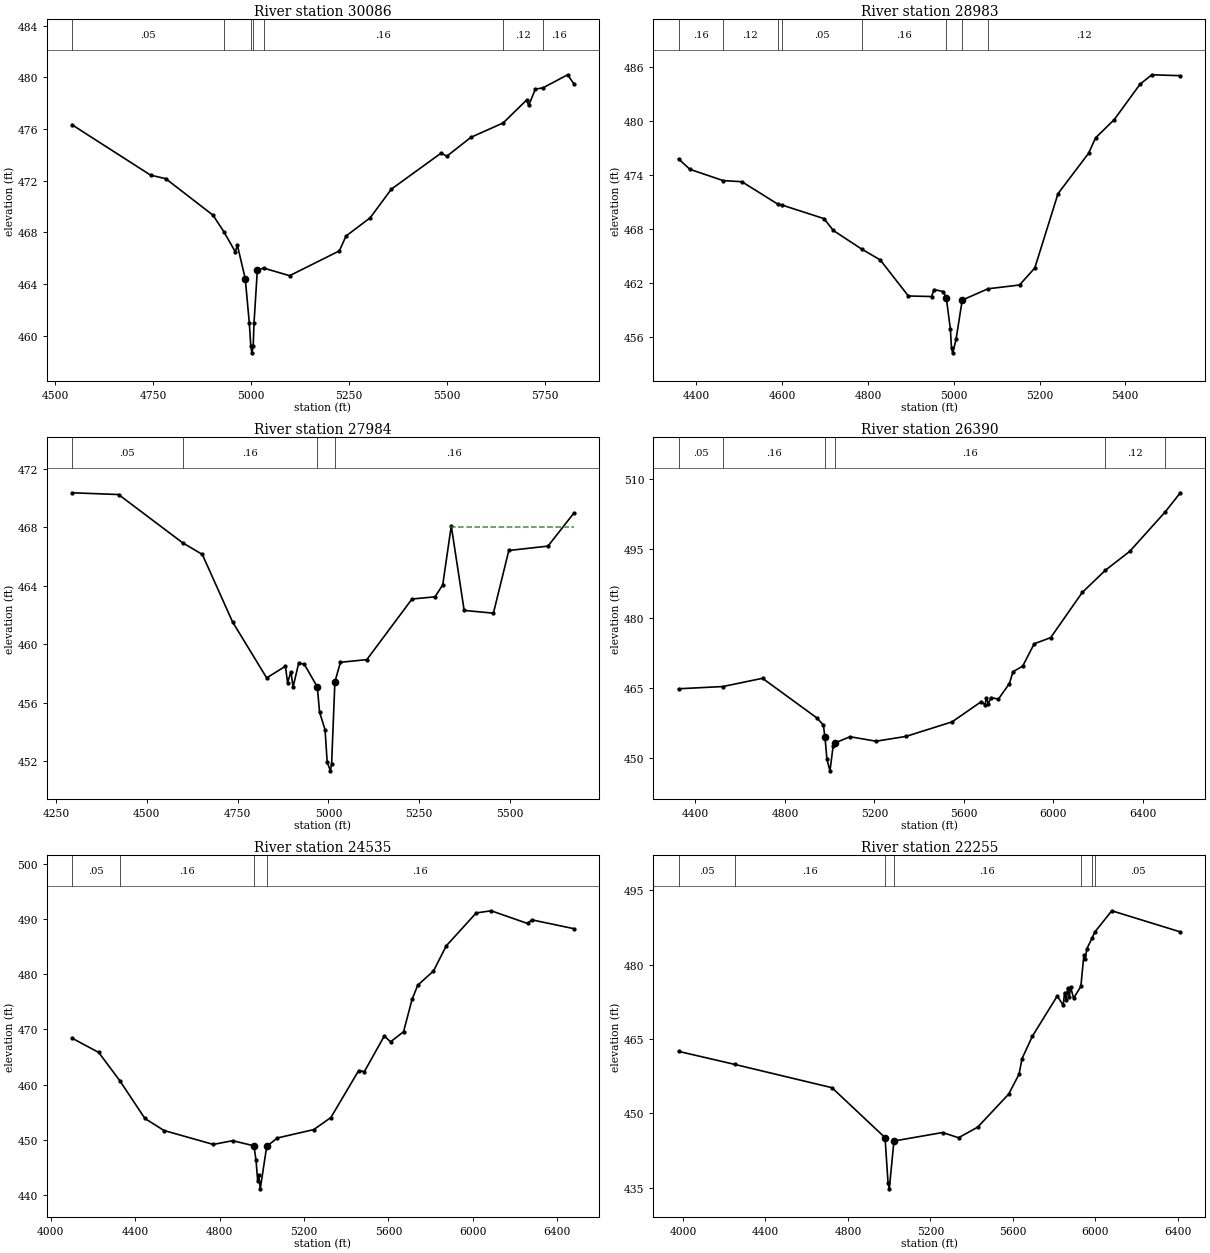
Type RM Length L Ch R = 1 ,30086   ,1103,1103,1103
BEGIN DESCRIPTION:
GENTRY CREEK 48.0
END DESCRIPTION:
XS GIS Cut Line= 3
      3457359.25     10464546.92      3457444.32     10464262.19
      3457220.48     10463306.11
#Sta/Elev= 30
  4543.8  476.32  4744.1  472.42  4782.5  472.15  4903.2  469.32  4930.4  468.06
    4960  466.48  4965.1  467.01  4985.3   464.4  4995.6  460.97  4999.5  459.17
  5002.2  458.67  5005.5  459.17  5007.6  460.99  5016.1  465.08  5032.1  465.23
  5098.3  464.64  5225.1  466.56  5242.1  467.71  5303.7  469.12  5357.7  471.34
  5485.1  474.14  5498.8  473.88  5560.5  475.35  5642.6  476.46  5702.6  478.24
  5707.7  477.82  5724.8  479.08  5744.3  479.18  5806.9  480.19  5822.9  479.49
#Mann= 7 ,-1 , 0
  4543.8     .05       0  4930.4     .12       0  4999.5     .07       0
  5005.5     .12       0  5032.1     .16       0  5642.6     .12       0
  5744.3     .16       0
Bank Sta=4985.3,5016.1
XS Rating Curve= 0 ,0
Exp/Cntr=0.3,0.1

Type RM Length L Ch R = 1 ,28983   ,999,999,999
BEGIN DESCRIPTION:
GENTRY CREEK 46.0
END DESCRIPTION:
XS GIS Cut Line= 3
       3457741.2     10464737.88      3457897.45     10464616.35
        3458361.     10463762.17
#Sta/Elev= 30
  4358.5   475.8    4385  474.64  4462.3  473.39  4506.2  473.26  4589.6  470.78
  4600.3  470.66  4697.6  469.16  4719.4  467.84  4785.3  465.78  4828.7  464.57
  4894.3  460.56  4948.5   460.5  4954.2  461.28  4976.1  461.04  4982.8  460.29
  4992.2  456.91  4994.9  454.74  4997.7  454.24  5005.5  455.74  5019.8   460.1
  5079.8  461.36  5153.4  461.78    5189  463.67  5243.2  471.94  5314.5  476.43
  5330.6  478.13  5374.3  480.17  5434.2  484.09  5461.8  485.15  5528.3  485.05
#Mann= 8 ,-1 , 0
  4358.5     .16       0  4462.3     .12       0  4589.6     .16       0
  4600.3     .05       0  4785.3     .16       0  4982.8     .07       0
  5019.8     .16       0  5079.8     .12       0
Bank Sta=4982.8,5019.8
XS Rating Curve= 0 ,0
Exp/Cntr=0.3,0.1

Type RM Length L Ch R = 1 ,27984   ,1594,1594,1594
BEGIN DESCRIPTION:
GENTRY CREEK 44.0
END DESCRIPTION:
XS GIS Cut Line= 4
       3458198.4     10465082.88      3458542.11     10464991.64
      3459001.61      10464272.6      3458985.99     10464100.75
#Sta/Elev= 30
  4294.2  470.36  4422.2  470.24  4598.4  466.94  4652.8  466.14  4736.1  461.52
    4830  457.69  4881.6  458.49  4887.5  457.37  4896.8   458.1  4902.7  457.07
    4918  458.69  4933.2  458.64  4969.5  457.07  4975.5  455.35  4990.7  454.15
  4996.6  451.91  5005.6  451.33  5008.8  451.83  5017.8  457.42    5033  458.76
  5105.7  458.94  5230.1  463.09  5293.5  463.24  5314.7  464.06 5338.18  468.09
  5373.7  462.31  5454.2  462.12  5496.6  466.41  5604.5  466.71  5675.7  468.97
#Mann= 4 ,-1 , 0
  4294.2     .05       0  4598.4     .16       0  4969.5     .07       0
  5017.8     .16       0
#XS Ineff= 2 , 0
                         5337.27          468.05
Permanent Ineff=
       F       F
Bank Sta=4969.5,5017.8
XS Rating Curve= 0 ,0
Exp/Cntr=0.3,0.1

Type RM Length L Ch R = 1 ,26390   ,1855,1855,1855
BEGIN DESCRIPTION:
GENTRY CREEK 42.0
END DESCRIPTION:
XS GIS Cut Line= 2
      3458888.49     10465707.87      3460854.64     10464627.14
#Sta/Elev= 30
  4324.2  464.85  4522.3  465.33  4699.8   467.1  4944.2  458.53  4971.7  457.05
  4978.8  454.51  4987.8  449.68  5001.3  447.21  5015.3   452.5  5024.4  453.22
    5091  454.54    5207  453.58  5341.1  454.61  5547.6  457.74  5678.3   462.1
  5694.4  461.38  5700.1  462.83  5709.1  461.68  5721.9  462.97  5754.1  462.62
  5803.4  465.96  5819.5   468.5  5863.1  469.73  5914.5  474.53  5988.1  475.84
  6129.2  485.55  6232.5  490.32  6341.4  494.38  6498.9  502.79  6567.8  506.98
#Mann= 6 ,-1 , 0
  4324.2     .05       0  4522.3     .16       0  4978.8     .12       0
  5024.4     .16       0  6232.5     .12       0  6498.9     .16       0
Bank Sta=4978.8,5024.4
XS Rating Curve= 0 ,0
Exp/Cntr=0.3,0.1

Type RM Length L Ch R = 1 ,24535   ,2280,2280,2280
BEGIN DESCRIPTION:
GENTRY CREEK 39.0
END DESCRIPTION:
XS GIS Cut Line= 2
      3459171.42     10466386.46      3461518.87     10466009.67
#Sta/Elev= 30
  4101.2  468.39  4227.4  465.81    4327  460.71  4446.2  453.85    4537  451.67
  4770.3  449.15  4861.9  449.83  4962.8   448.9  4972.9  446.28  4980.7  442.51
  4985.8  443.61  4992.9  441.11  5023.5  448.81  5074.2  450.32  5246.4  451.84
  5327.4  454.02    5459  462.52  5486.3  462.35  5580.6  468.79  5610.2  467.73
  5671.7  469.56  5712.2  475.42  5739.1  477.99  5813.5  480.55  5874.3  485.12
  6016.1  491.07    6087  491.46  6259.2  489.16  6279.4  489.82  6478.7  488.22
#Mann= 4 ,-1 , 0
  4101.2     .05       0    4327     .16       0  4962.8     .12       0
  5023.5     .16       0
Bank Sta=4962.8,5023.5
XS Rating Curve= 0 ,0
Exp/Cntr=0.3,0.1

Type RM Length L Ch R = 1 ,22255   ,593,593,593
BEGIN DESCRIPTION:
Mapping XS 8ff48e1a
END DESCRIPTION:
XS GIS Cut Line= 2
      3459687.99     10467989.58       3461630.9     10466525.46
#Sta/Elev= 30
  3978.6  462.48  4251.1  459.85  4722.5  455.15  4979.8  445.08  4994.4  435.94
  5000.4  434.75    5023   444.4  5258.8  446.11  5336.1  445.06  5429.5  447.21
  5579.4  453.87  5629.4  457.87    5644  461.02  5693.9  465.52  5814.7  473.65
  5843.8  471.76  5850.1  474.35  5858.4  472.76  5864.7   475.2    5873  473.48
  5879.2  475.49  5893.8  473.21  5929.2  475.58  5943.8  481.92    5950  481.02
  5958.3  483.19  5984.1  485.37    5996  486.51  6079.1  490.84  6411.4  486.58
#Mann= 7 ,-1 , 0
  3978.6     .05       0  4251.1     .16       0  4979.8     .12       0
    5023     .16       0  5929.2     .12       0  5984.1     .16       0
    5996     .05       0
Bank Sta=4979.8,5023
XS Rating Curve= 0 ,0
Exp/Cntr=0.3,0.1

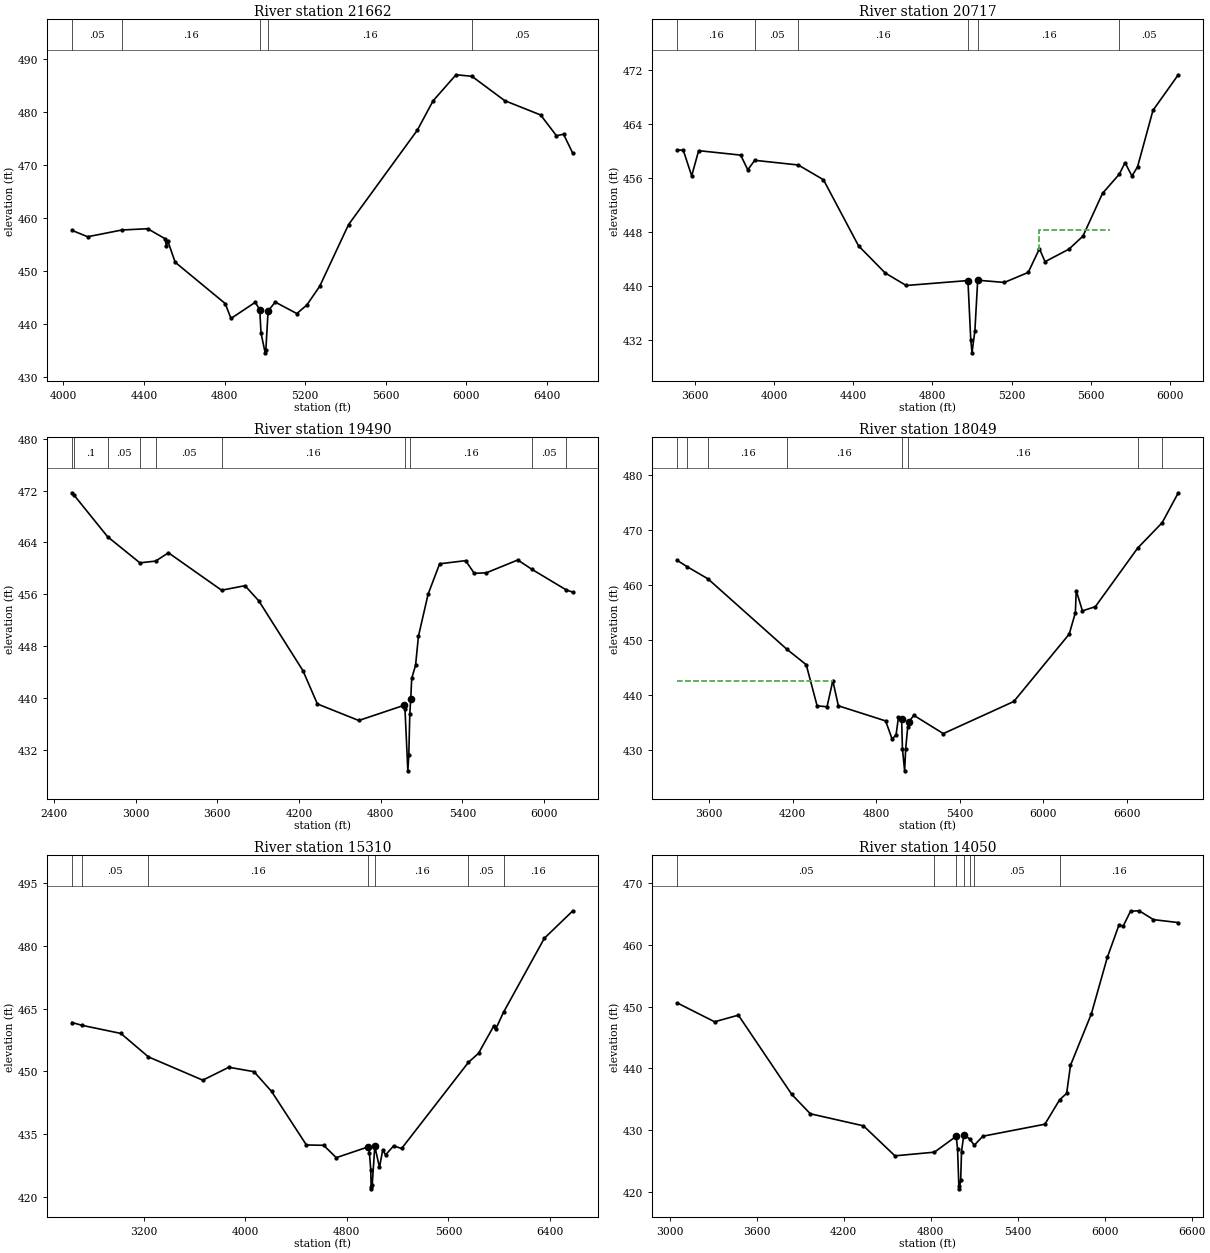
Type RM Length L Ch R = 1 ,21662   ,945,945,945
BEGIN DESCRIPTION:
GENTRY CREEK 34.0
END DESCRIPTION:
XS GIS Cut Line= 2
      3460039.46     10468448.09      3461992.57      10466907.3
#Sta/Elev= 30
  4042.2  457.69  4120.4  456.48  4290.3  457.75  4418.6  457.99  4504.1  456.12
  4511.6  454.79    4518  455.72  4554.9  451.68  4803.4   443.9  4832.3  441.08
  4952.5  444.13    4975  442.76  4981.4  438.31  5001.9  434.61  5005.2  435.11
  5016.6  442.51  5051.9  444.17  5159.3  442.01    5209  443.62  5273.2  447.18
  5415.9  458.76  5757.3  476.54  5835.9  482.09  5949.7  486.99  6028.3  486.71
  6191.8  482.11  6369.8  479.42  6448.4  475.51  6483.6  475.79  6529.9  472.18
#Mann= 5 ,-1 , 0
  4042.2     .05       0  4290.3     .16       0    4975     .12       0
  5016.6     .16       0  6028.3     .05       0
Bank Sta=4975,5016.6
XS Rating Curve= 0 ,0
Exp/Cntr=0.3,0.1

Type RM Length L Ch R = 1 ,20717   ,1227,1227,1227
BEGIN DESCRIPTION:
Mapping XS 36bd9fa1
END DESCRIPTION:
XS GIS Cut Line= 2
      3460284.62     10469526.09      3461976.86     10467646.41
#Sta/Elev= 30
  3511.8  460.13  3541.7  460.09  3584.3  456.29  3619.4  460.02  3831.7  459.36
  3867.6  457.19  3902.5  458.59  4122.4   457.9  4249.5  455.72  4426.6  445.95
  4561.2  441.93  4667.3  440.08    4979  440.81  4993.2  432.09  4999.6  430.12
  5014.1  433.38  5028.3  440.86  5162.8  440.53  5283.2  442.01    5340  445.51
  5368.4   443.6  5488.7  445.45  5559.7  447.38  5658.4   453.7  5743.6  456.55
    5772  458.24  5807.1  456.27  5835.5  457.64  5913.2  465.98    6041  471.24
#Mann= 6 ,-1 , 0
  3511.8     .16       0  3902.5     .05       0  4122.4     .16       0
    4979     .12       0  5028.3     .16       0  5743.6     .05       0
#XS Ineff= 1 ,-1
  5337.5 5693.75  448.34
Permanent Ineff=
       T
Bank Sta=4979,5028.3
XS Rating Curve= 0 ,0
Exp/Cntr=0.3,0.1

Type RM Length L Ch R = 1 ,19490   ,1441,1441,1441
BEGIN DESCRIPTION:
GENTRY CREEK 30.0
END DESCRIPTION:
XS GIS Cut Line= 4
      3460039.41     10470227.63      3461342.11     10469591.64
       3462404.9      10468513.2       3462404.9     10467797.07
#Sta/Elev= 30
  2531.4  471.66  2544.8  471.36  2793.4  464.89  3030.9  460.86  3146.3  461.13
  3240.6  462.41    3631  456.64    3803  457.34    3905  454.98  4228.6  444.24
  4334.6  439.11  4638.7  436.56    4971   438.9    4978  438.36  4999.1   428.8
  5006.3  431.31  5013.5   437.6  5020.5  439.95  5027.6  443.05  5055.9  445.07
    5077  449.55  5147.8  456.02  5232.6  460.71  5423.6   461.2  5487.2  459.24
  5576.7  459.33  5806.7   461.3  5911.2  459.85    6164  456.67  6211.3  456.34
#Mann= 10 ,-1 , 0
  2531.4     .05       0  2544.8      .1       0  2793.4     .05       0
  3030.9      .1       0  3146.3     .05       0    3631     .16       0
    4978     .12       0  5013.5     .16       0  5911.2     .05       0
    6164     .16       0
Bank Sta=4971,5020.5
XS Rating Curve= 0 ,0
Exp/Cntr=0.3,0.1

Type RM Length L Ch R = 1 ,18049   ,2739,2739,2739
BEGIN DESCRIPTION:
Mapping XS b8f6880f
END DESCRIPTION:
XS GIS Cut Line= 4
      3462067.03     10471149.41      3462462.86     10470149.42
      3463103.48     10468737.97      3463655.32     10467936.24
#Sta/Elev= 30
  3371.3  464.46  3442.3  463.31  3591.3  461.11  4159.4  448.26  4297.2  445.48
  4375.6  437.98  4446.8  437.82  4488.3  442.55  4528.2  437.99  4867.8  435.24
  4913.9  431.95  4942.5  432.66  4960.1  435.93  4982.4   435.6  4988.6  430.14
  5004.2  426.15  5011.7  430.15  5026.4  434.13  5034.8  435.08  5070.3  436.26
  5282.1  432.93  5788.7  438.78  6186.6  451.05  6230.8  454.95  6236.8  458.98
  6281.5  455.28  6374.2  456.04  6678.6  466.72  6854.2  471.33  6970.1  476.78
#Mann= 8 ,-1 , 0
  3371.3     .16       0  3442.3     .05       0  3591.3     .16       0
  4159.4     .16       0  4982.4     .12       0  5026.4     .16       0
  6678.6     .05       0  6854.2     .16       0
#XS Ineff= 2 , 0
         4488.51  442.56
Permanent Ineff=
       F       F
Bank Sta=4982.4,5034.8
XS Rating Curve= 0 ,0
Exp/Cntr=0.3,0.1

Type RM Length L Ch R = 1 ,15310   ,1260,1260,1260
BEGIN DESCRIPTION:
GENTRY CREEK 23.0
END DESCRIPTION:
XS GIS Cut Line= 4
      3462838.93     10471442.89       3463826.6     10470332.12
      3464488.23     10468382.99      3464336.33     10468014.08
#Sta/Elev= 30
    2636  461.69  2717.8     461  3021.8  459.07  3237.8  453.47  3666.5  447.89
  3871.4  450.98  4069.6  449.92  4207.4  445.21  4481.9  432.38  4617.8   432.3
  4717.3  429.34 4968.84  431.93  4978.3  430.41  4988.8  426.39  4991.6  422.38
  4994.3  421.88  4999.9  422.71  5020.5  432.04  5057.4  427.02  5083.5  431.27
    5105  429.99  5168.4  432.15  5231.7  431.54  5757.7  452.16    5837  454.32
  5957.3  460.87    5971  460.03  6033.7  464.13  6355.2  481.85  6579.7  488.43
#Mann= 7 ,-1 , 0
    2636     .16       0  2717.8     .05       0  3237.8     .16       0
 4968.84     .12       0  5020.5     .16       0  5757.7     .05       0
  6033.7     .16       0
Bank Sta=4968.84,5020.5
XS Rating Curve= 0 ,0
Exp/Cntr=0.3,0.1

Type RM Length L Ch R = 1 ,14050   ,1319,1319,1319
BEGIN DESCRIPTION:
Mapping XS 55a9f5b2
END DESCRIPTION:
XS GIS Cut Line= 4
       3464046.2     10471118.16      3464770.15     10470243.17
      3465405.57      10469196.3      3465348.28     10468102.57
#Sta/Elev= 30
  3052.4  450.59  3309.4  447.55  3473.5  448.62  3842.1  435.79  3969.8  432.67
  4336.2  430.72  4553.3  425.87  4825.8  426.46  4975.9  429.03  4985.3     427
  4994.2  421.03    4997  420.53  5006.9  421.89  5012.7  426.54  5028.2  429.22
    5068  428.64  5100.4  427.58    5160  429.04  5587.6  430.98  5689.4  434.93
  5737.8  435.97  5764.2   440.5    5908  448.81  6018.2  457.95  6098.3  463.17
  6128.3  463.04  6178.4  465.43  6238.5   465.5  6336.3  464.07  6507.9  463.59
#Mann= 7 ,-1 , 0
  3052.4     .05       0  4825.8     .16       0  4975.9     .07       0
  5028.2     .16       0    5068     .12       0  5100.4     .05       0
  5689.4     .16       0
Bank Sta=4975.9,5028.2
XS Rating Curve= 0 ,0
Exp/Cntr=0.3,0.1

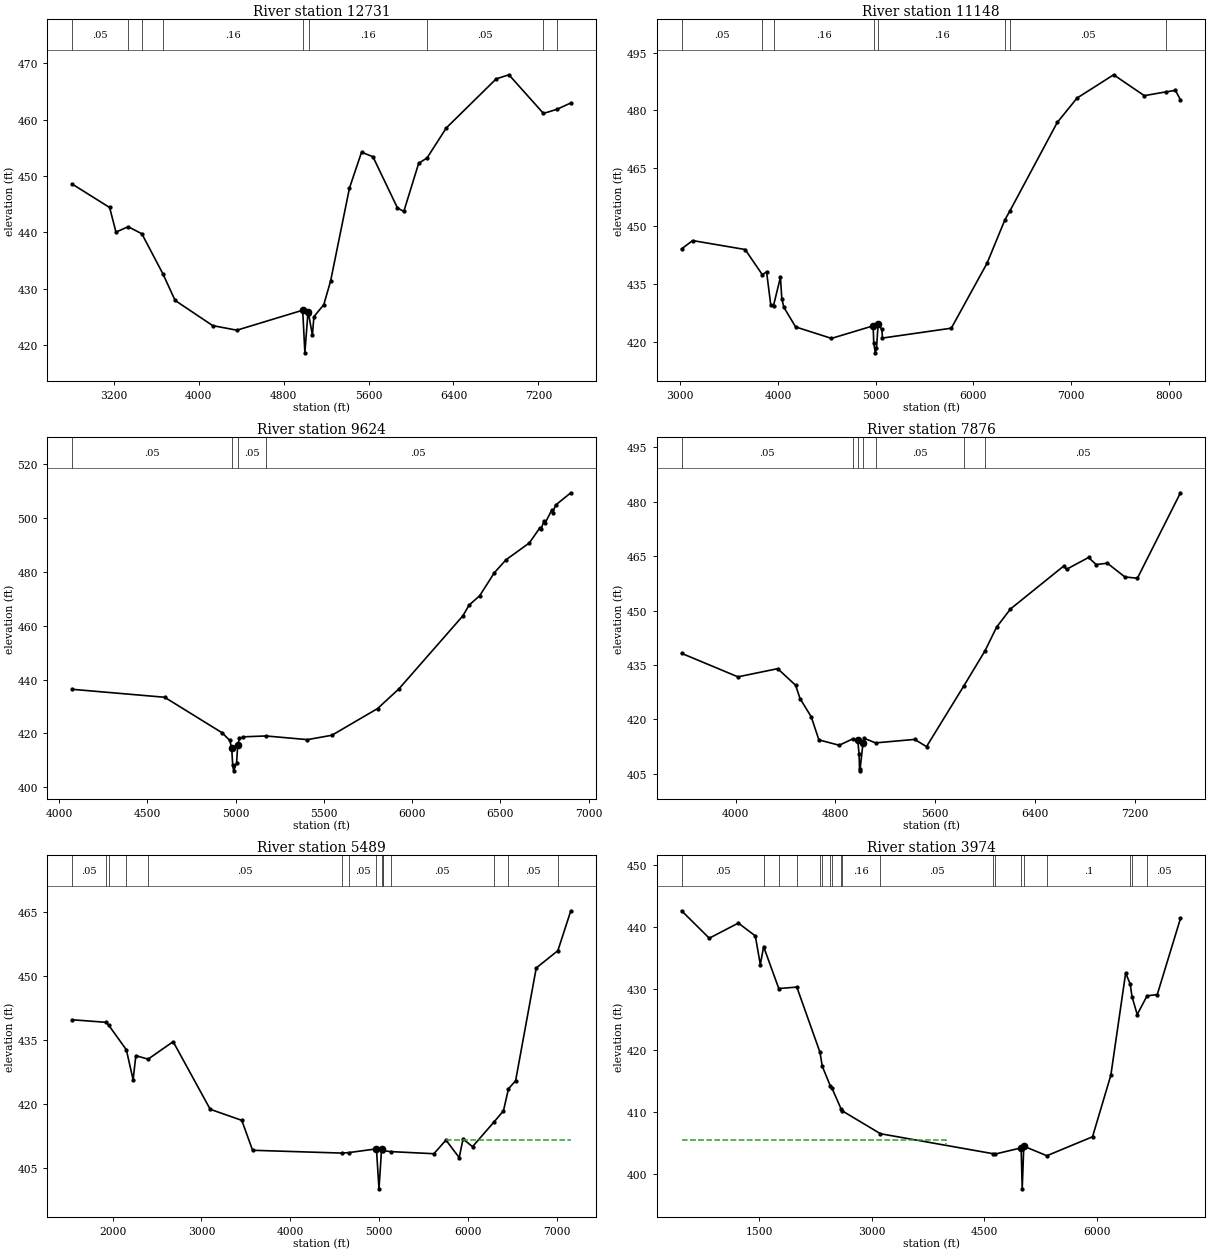
Type RM Length L Ch R = 1 ,12731   ,1583,1583,1583
BEGIN DESCRIPTION:
GENTRY CREEK 22.0
END DESCRIPTION:
XS GIS Cut Line= 4
      3464444.85     10471334.37      3465399.69     10470965.46
      3466549.86     10469511.46      3466484.76     10467688.57
#Sta/Elev= 30
  2804.4  448.59  3159.7   444.4  3219.6  440.03  3334.1  440.99  3463.2  439.74
  3661.4  432.64    3777   427.9  4131.3  423.43  4358.9  422.62  4979.2  426.17
  4999.8   418.6  5028.9   425.8  5035.3  425.45  5070.5  421.77    5085  425.02
  5177.9  427.15  5242.1  431.34    5420  447.85  5533.8  454.22  5641.2  453.41
  5871.9  444.34  5931.9  443.69    6072  452.23  6152.1  453.22  6332.2  458.52
  6802.5  467.23  6922.6  467.96  7248.2   461.1  7373.9  461.82    7506  462.96
#Mann= 9 ,-1 , 0
  2804.4     .05       0  3334.1      .1       0  3463.2     .05       0
  3661.4     .16       0  4979.2     .12       0  5035.3     .16       0
  6152.1     .05       0  7248.2     .16       0  7373.9     .05       0
Bank Sta=4979.2,5028.9
XS Rating Curve= 0 ,0
Exp/Cntr=0.3,0.1

Type RM Length L Ch R = 1 ,11148   ,1524,1524,1524
BEGIN DESCRIPTION:
GENTRY CREEK 18.0
END DESCRIPTION:
XS GIS Cut Line= 4
      3465746.93     10472376.04      3466753.78     10471448.88
      3467656.64     10469685.07      3468264.12     10468036.19
#Sta/Elev= 30
  3013.9  444.05    3127  446.21  3664.6  443.89  3840.8  437.34  3884.1  438.12
  3926.6  429.54    3955  429.32  4025.9  436.68    4040  431.16    4061  428.89
  4181.2  423.79  4548.6  420.81  4974.9  424.07  4981.5  419.61  4997.1  417.06
  5009.3  418.26  5025.9  424.44  5064.7  423.14  5070.3   420.9  5775.3  423.46
  6141.6  440.35  6324.9  451.66  6372.2  453.77  6860.2  476.89  7062.7  483.22
  7437.2  489.26  7750.9  483.84  7972.4  484.82  8069.8  485.21  8121.3  482.75
#Mann= 8 ,-1 , 0
  3013.9     .05       0  3840.8      .1       0    3955     .16       0
  4981.5     .12       0  5025.9     .16       0  6324.9      .1       0
  6372.2     .05       0  7972.4      .1       0
Bank Sta=4974.9,5025.9
XS Rating Curve= 0 ,0
Exp/Cntr=0.3,0.1

Type RM Length L Ch R = 1 ,9624    ,1748,1748,1748
BEGIN DESCRIPTION:
GENTRY CREEK 15.0
END DESCRIPTION:
XS GIS Cut Line= 3
      3468090.67     10472028.87      3468042.11     10471691.64
      3469197.26      10469490.1
#Sta/Elev= 30
  4072.9  436.38  4598.2  433.42  4923.4  420.25  4967.5  417.38  4978.3  414.51
  4983.9  408.21  4989.3   406.1    5006  408.98  5012.1  415.63  5022.4  418.12
  5044.4  418.73  5172.1  419.05  5407.4  417.69    5546  419.31    5805  429.23
  5926.1  436.56  6288.2  463.65  6323.1  467.61  6383.6  471.13  6466.1  479.62
  6532.3  484.45  6664.6   490.7  6725.2  496.39  6730.8   495.8  6747.2  498.75
  6752.9  497.97  6791.3  502.84    6797  501.99  6813.4  504.76  6899.8  509.34
#Mann= 4 ,-1 , 0
  4072.9     .05       0  4978.3     .07       0  5012.1     .05       0
  5172.1     .05       0
Bank Sta=4978.3,5012.1
XS Rating Curve= 0 ,0
Exp/Cntr=0.3,0.1

Type RM Length L Ch R = 1 ,7876    ,2387,2387,2387
BEGIN DESCRIPTION:
Mapping XS b0cc1dd0
END DESCRIPTION:
XS GIS Cut Line= 4
      3468369.97     10472251.86      3469244.98      10471696.3
      3469707.78     10470390.57      3469848.41     10468817.64
#Sta/Elev= 30
  3565.9  438.21    4018  431.73  4336.5  433.99  4480.5  429.41  4516.1  425.73
  4605.6  420.74  4667.1  414.37  4830.1  412.89  4936.7  414.61  4978.7  414.25
  4989.3  410.55  4993.2  406.34    4996  405.84  5021.1  413.53  5032.4  414.77
  5121.4  413.54  5434.9   414.5  5530.3  412.51  5830.3  429.28  5999.3   438.9
  6092.2  445.43  6203.6  450.43  6629.2  462.22  6654.1  461.38    6830  464.62
  6890.2  462.67  6980.6  463.04  7121.1  459.25  7221.5   458.9  7566.9  482.44
#Mann= 7 ,-1 , 0
  3565.9     .05       0  4936.7     .16       0  4978.7     .07       0
  5021.1     .16       0  5121.4     .05       0  5830.3      .1       0
  5999.3     .05       0
Bank Sta=4978.7,5021.1
XS Rating Curve= 0 ,0
Exp/Cntr=0.3,0.1

Type RM Length L Ch R = 1 ,5489    ,1515,1515,1515
BEGIN DESCRIPTION:
GENTRY CREEK 10.0
END DESCRIPTION:
XS GIS Cut Line= 4
      3468502.95     10472679.88      3470000.39     10472310.94
      3472148.82     10469619.97      3471910.65     10469035.35
#Sta/Elev= 30
    1542  439.81  1925.5  439.21  1953.9   438.6  2154.7  432.76  2231.2  425.72
  2261.5  431.39  2399.4  430.56  2681.7  434.67  3098.7   418.8  3454.4   416.2
  3575.9  409.18  4580.1  408.52    4658  408.63  4970.5  409.51  4999.1  400.13
  5028.1  409.38  5040.6   409.1  5128.8  408.87  5617.3  408.37  5753.4  411.57
  5902.3  407.45  5945.6  411.85    6052  410.02  6296.1  415.87  6400.3  418.43
    6457  423.61  6537.1  425.47  6769.7  451.96    7013  456.02  7158.9  465.38
#Mann= 15 ,-1 , 0
    1542     .05       0  1925.5     .16       0  1953.9     .05       0
  2154.7      .1       0  2399.4     .05       0  4580.1     .16       0
    4658     .05       0  4970.5     .03       0  5028.1     .05       0
  5040.6      .1       0  5040.6     .16       0  5128.8     .05       0
  6296.1      .1       0    6457     .05       0    7013      .1       0
#XS Ineff= 2 , 0
                         5753.73          411.59
Permanent Ineff=
       F       F
Bank Sta=4970.5,5028.1
XS Rating Curve= 0 ,0
Exp/Cntr=0.3,0.1

Type RM Length L Ch R = 1 ,3974    ,1790,1790,1790
BEGIN DESCRIPTION:
GENTRY CREEK 7.0
END DESCRIPTION:
XS GIS Cut Line= 4
      3468568.11      10473287.5      3470043.79     10473027.09
      3473624.52     10470422.92      3473494.31     10469706.81
#Sta/Elev= 30
     464  442.59   833.6  438.15  1220.8   440.6  1447.6  438.52    1514  433.88
  1558.4  436.78  1760.5     430  2001.1  430.24  2310.3  419.67  2340.5  417.42
  2449.6  414.19  2466.4  413.98  2592.2  410.49  2602.7  410.23  3116.7   406.5
    4617  403.27  4649.1  403.22  4992.8  404.21  5007.2  397.58  5028.3  404.48
    5336  402.94  5944.9  406.01  6189.2  415.97  6386.9  432.53  6447.4  430.72
  6471.7  428.68    6541   425.8  6672.8  428.83  6808.1  429.02  7117.9  441.35
#Mann= 19 ,-1 , 0
     464     .05       0  1558.4      .1       0  1760.5     .05       0
  2001.1      .1       0  2310.3     .05       0  2340.5     .16       0
  2449.6     .05       0  2466.4     .16       0  2592.2     .05       0
  2602.7     .16       0  3116.7     .05       0    4617     .16       0
  4649.1     .05       0  4992.8    .035       0  5028.3     .05       0
    5336      .1       0  6447.4     .05       0  6471.7      .1       0
  6672.8     .05       0
#XS Ineff= 2 , 0
         3989.67  405.55
Permanent Ineff=
       F       F
Bank Sta=4992.8,5028.3
XS Rating Curve= 0 ,0
Exp/Cntr=0.3,0.1

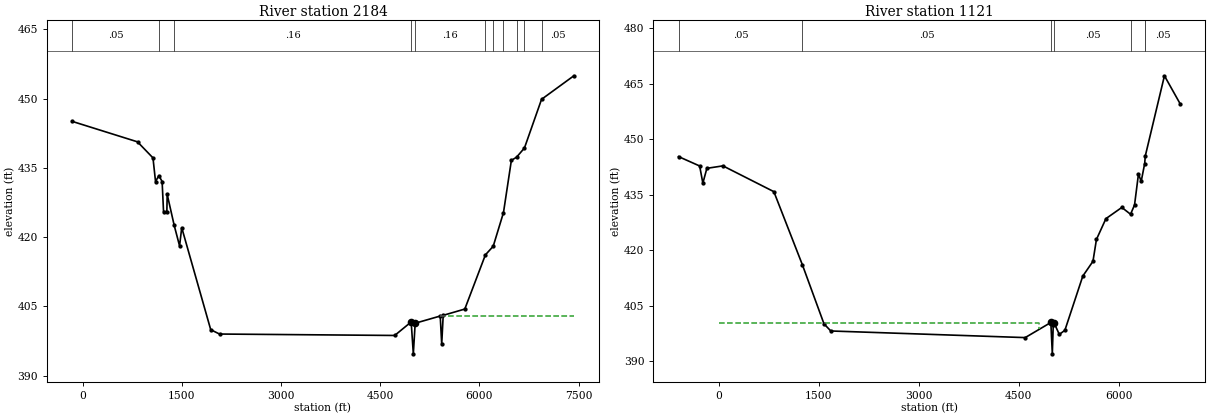
Type RM Length L Ch R = 1 ,2184    ,1063,1063,1063
BEGIN DESCRIPTION:
GENTRY CREEK 3.0
END DESCRIPTION:
XS GIS Cut Line= 4
      3469002.12     10473808.34      3470716.53     10474047.05
      3475447.43      10471594.8      3475620.88     10471096.15
#Sta/Elev= 30
  -158.5  445.08   830.9  440.64    1065  437.16  1103.5  432.04  1154.1  433.32
  1203.2  432.05  1224.7   425.5  1274.8  425.54  1279.8  429.26  1386.2  422.52
    1467   418.1  1499.7  422.05  1938.1  399.95  2070.9  399.01  4719.9   398.7
  4969.1  401.63  5001.7  394.72  5029.7  401.35  5408.4  402.91  5430.9  396.83
  5453.4  403.06    5780  404.42  6091.5  416.16  6209.7  418.02  6364.9  425.32
  6484.1  436.62    6563  437.32    6682  439.31  6940.6  449.85  7429.1  454.95
#Mann= 11 ,-1 , 0
  -158.5     .05       0  1154.1     .16       0  1386.2     .16       0
  4969.1     .12       0  5029.7     .16       0  6091.5     .12       0
  6209.7      .1       0  6364.9      .1       0    6563     .05       0
    6682      .1       0  6940.6     .05       0
#XS Ineff= 2 , 0
       0  4946.3  401.19 5408.59       0  402.92
Permanent Ineff=
       T       T
Bank Sta=4969.1,5029.7
XS Rating Curve= 0 ,0
Exp/Cntr=0.3,0.1

Type RM Length L Ch R = 1 ,1121    ,0,0,0
BEGIN DESCRIPTION:
GENTRY CREEK 1.0
END DESCRIPTION:
XS GIS Cut Line= 4
      3469088.96     10474980.22      3470629.73     10475110.42
      3475382.33     10472853.48      3475534.24     10472159.03
#Sta/Elev= 30
  -599.2  445.36  -282.7  442.82  -234.8  438.18  -174.5  442.19    66.1  442.85
     829  435.88  1256.5   416.1  1580.2  400.14  1682.2  398.21  4594.9  396.42
  4979.3  400.51  5001.2  392.03    5015  399.77  5023.6  400.41  5032.2  400.21
    5106  397.28  5189.6   398.4  5457.9  413.05  5610.3  417.05  5662.4  422.96
  5804.3  428.58  6042.7  431.61  6173.5  429.77  6233.2  432.29  6292.1  440.66
    6333  438.67    6385  443.46  6394.2  445.52  6681.1  467.21  6919.2  459.55
#Mann= 7 ,-1 , 0
  -599.2     .05       0  1256.5     .05       0  4979.3     .03       0
  5032.2     .05       0  6173.5     .05       0    6385      .1       0
  6394.2     .05       0
#XS Ineff= 2 , 0
       0 4803.37  400.49               0
Permanent Ineff=
       T       F
Bank Sta=4979.3,5023.6
XS Rating Curve= 0 ,0
Exp/Cntr=0.3,0.1

Chan Stop Cuts=-1
Use User Specified Reach Order=0
Composite Channel Slope=5