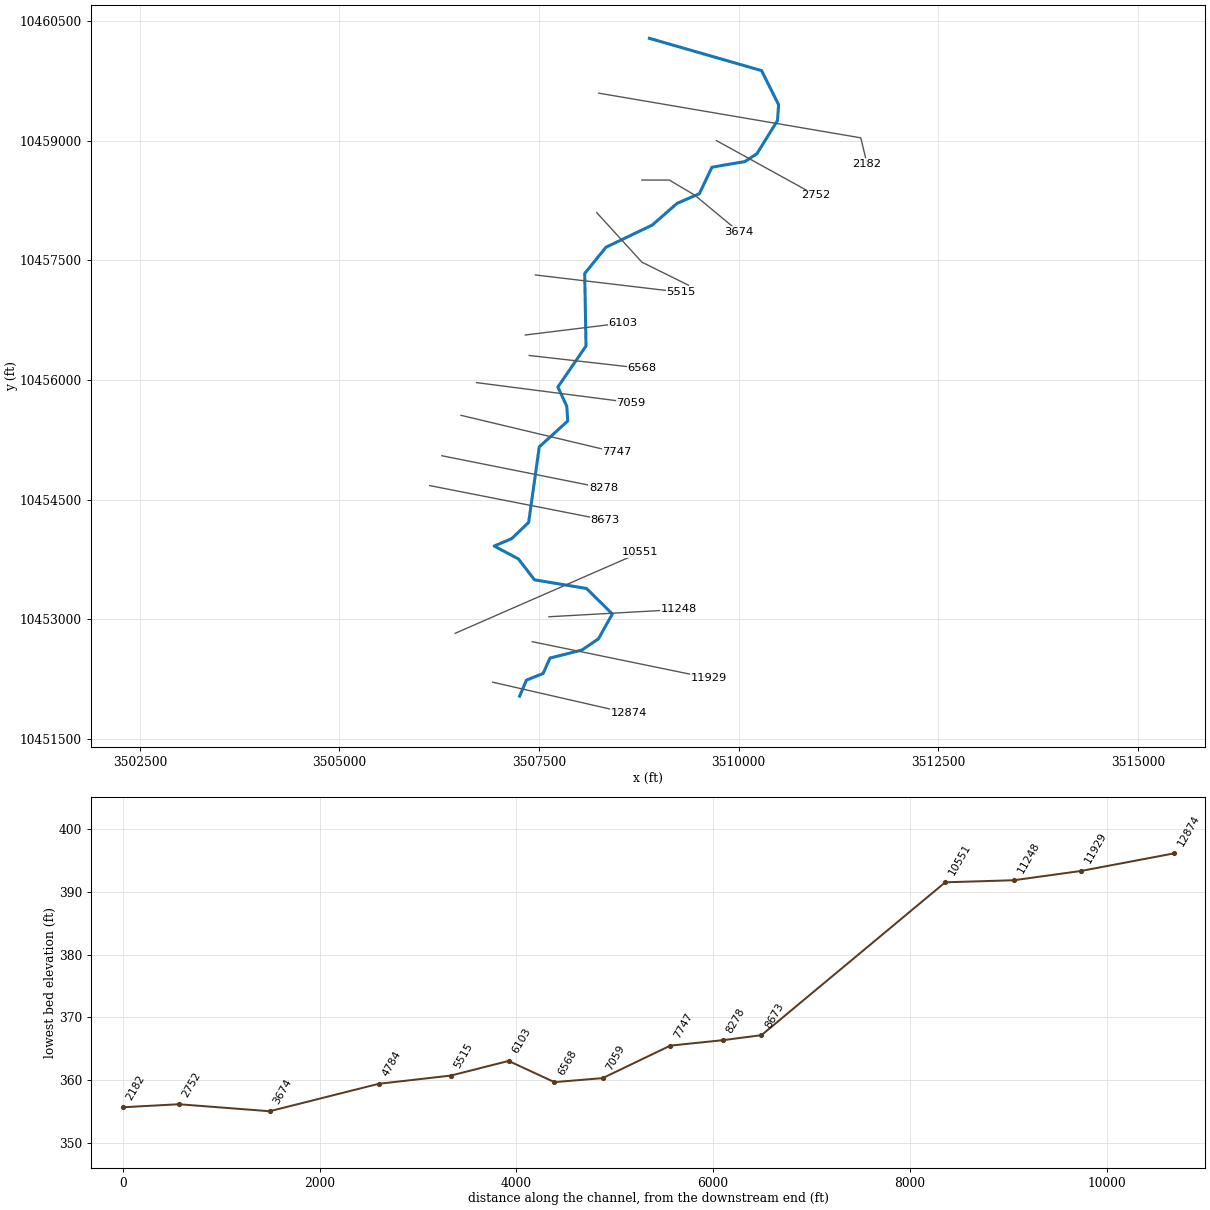
--- HEADS CREEK TRIB 2.prj (project) ---

Proj Title=HEADS CREEK TRIB 2 Base Level Engineering
Current Plan=p01
Default Exp/Contr=0.3,0.1
English Units
Geom File=g01
Flow File=f01
Plan File=p01
Y Axis Title=Elevation
X Axis Title(PF)=Main Channel Distance
X Axis Title(XS)=Station
BEGIN DESCRIPTION:
HEADS CREEK TRIB 2
END DESCRIPTION:
DSS Export Rating Curves= 0
DSS Export Rating Curve Sorted= 0
DSS Export Volume Flow Curves= 0
DXF OffsetX= 0
DXF OffsetY= 0
DXF ScaleX= 1
DXF ScaleY= 10

--- HEADS CREEK TRIB 2.p01 (plan) ---

Plan Title=Multiple Run
Short Identifier=Multiple
Geom File=g01
Flow File=f01
Subcritical Flow
K Sum by GR= 0
Std Step Tol= 0.01
Critical Tol= 0.01
Num of Std Step Trials= 20
Max Error Tol= 0.3
Flow Tol Ratio= 0.001
Split Flow NTrial= 30
Split Flow Tol= 0.02
Split Flow Ratio= 0.02
Log Output Level= 0
Friction Slope Method= 1
Unsteady Friction Slope Method= 2
Unsteady Bridges Friction Slope Method= 1
Parabolic Critical Depth
Global Vel Dist=  1 , 1 , 1
Global Log Level= 0
CheckData=True
Encroach Param= -1, 0, 0, 0
BEGIN DESCRIPTION:
Multiple Run
END DESCRIPTION:

--- HEADS CREEK TRIB 2.f01 (steady flow) ---

Flow Title=Multiple
Program Version=4.10
Number of Profiles= 7
Profile Names=10-year,25-year,50-year,1pct_min,100-year,1pct_plu,500-year
River Rch & RM=HEADS CREEK TRIB,Reach-1         ,12874
     544     728     877     773    1045    1413    1478
River Rch & RM=HEADS CREEK TRIB,Reach-1         ,8673
    1729    2464    3090    2823    3817    5163    5817
River Rch & RM=HEADS CREEK TRIB,Reach-1         ,5515
    1912    2736    3441    3152    4263    5765    6529
River Rch & RM=HEADS CREEK TRIB,Reach-1         ,2182
    2012    2876    3614    3305    4470    6045    6827
Boundary for River Rch & Prof#=HEADS CREEK TRIB,Reach-1         , 1
Up Type= 0
Dn Type= 3
Dn Slope=0.005
Boundary for River Rch & Prof#=HEADS CREEK TRIB,Reach-1         , 2
Up Type= 0
Dn Type= 3
Dn Slope=0.005
Boundary for River Rch & Prof#=HEADS CREEK TRIB,Reach-1         , 3
Up Type= 0
Dn Type= 3
Dn Slope=0.005
Boundary for River Rch & Prof#=HEADS CREEK TRIB,Reach-1         , 4
Up Type= 0
Dn Type= 3
Dn Slope=0.005
Boundary for River Rch & Prof#=HEADS CREEK TRIB,Reach-1         , 5
Up Type= 0
Dn Type= 3
Dn Slope=0.005
Boundary for River Rch & Prof#=HEADS CREEK TRIB,Reach-1         , 6
Up Type= 0
Dn Type= 3
Dn Slope=0.005
Boundary for River Rch & Prof#=HEADS CREEK TRIB,Reach-1         , 7
Up Type= 0
Dn Type= 3
Dn Slope=0.005
DSS Import GetInterval= 0
DSS Import GetPeak= 0
DSS Import FillOption= 0

--- HEADS CREEK TRIB 2.g01 (geometry) ---

Geom Title=Existing Conditions
Program Version=4.10

River Reach=HEADS CREEK TRIB,Reach-1
Reach XY= 30
      3507256.33     10452035.99      3507341.74     10452238.08
       3507550.6     10452320.37      3507636.29     10452514.18
      3508037.36     10452615.07      3508243.52     10452755.05
       3508417.3      10453066.5      3508094.66     10453386.06
      3507442.53     10453494.93      3507239.92     10453757.43
      3506937.92     10453918.41      3507157.43     10454011.48
      3507369.48     10454214.47      3507502.46     10455161.43
      3507858.67     10455484.91      3507847.39     10455668.94
      3507735.41     10455911.12      3508087.84     10456425.88
      3508071.34     10457334.08      3508338.27     10457663.51
      3508916.66     10457940.62      3509228.47     10458213.08
      3509507.59     10458334.29      3509664.92     10458666.32
      3510077.46     10458736.98      3510228.16     10458834.89
      3510485.94      10459251.5      3510500.16     10459447.95
      3510287.21      10459876.8       3508882.2     10460281.55

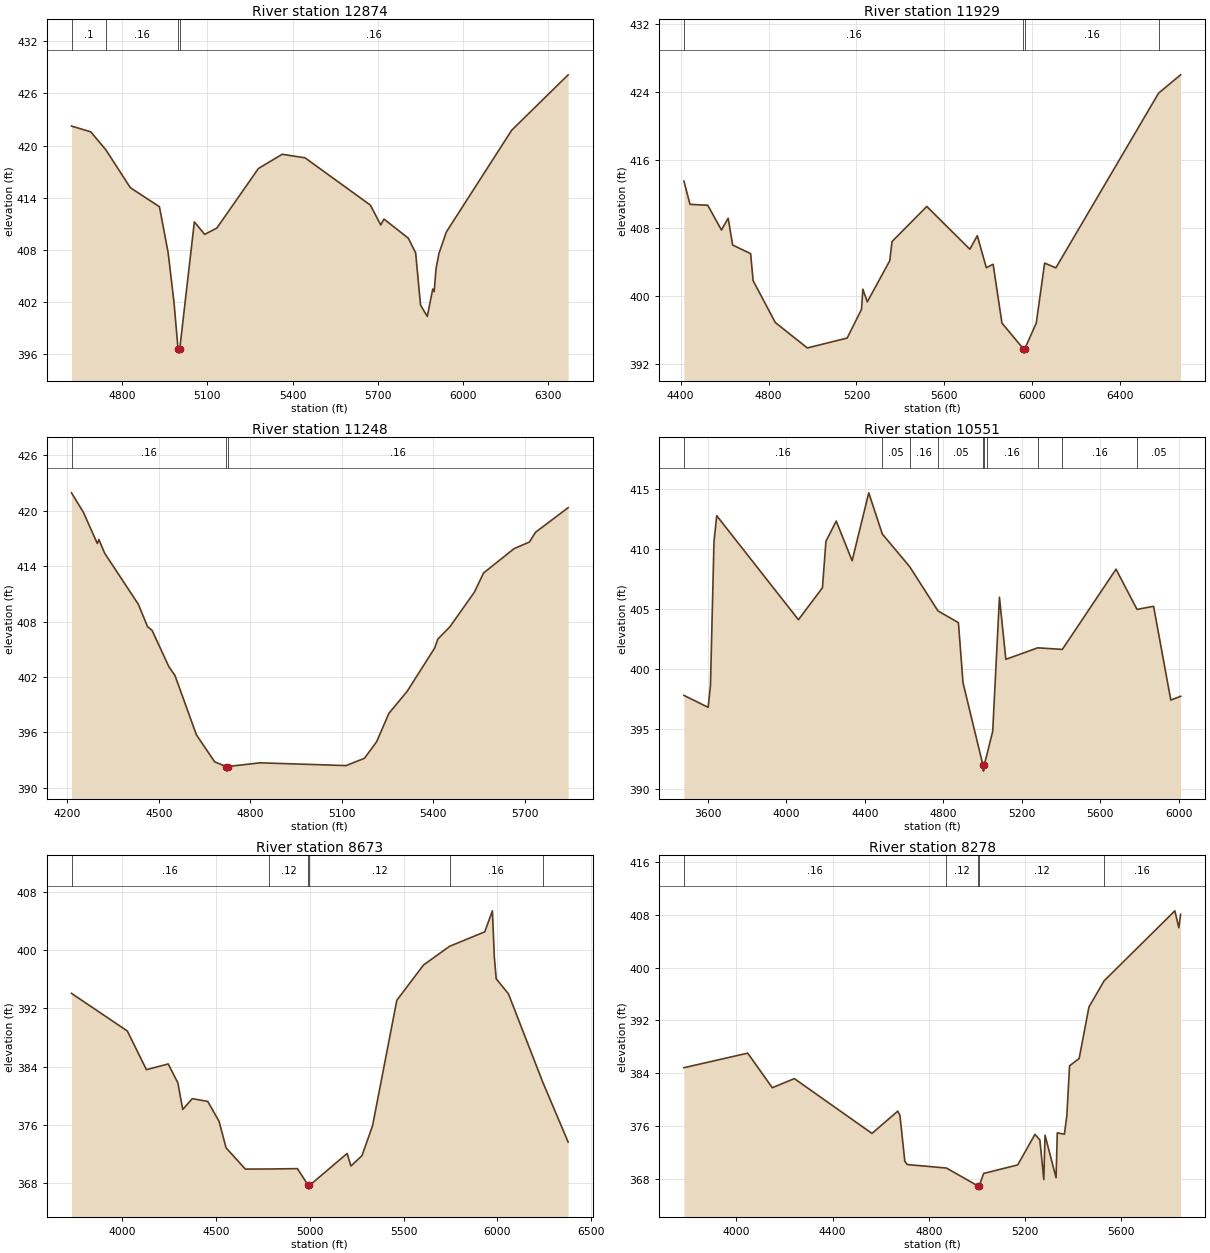
Type RM Length L Ch R = 1 ,12874   ,945,945,945
BEGIN DESCRIPTION:
HEADS CREEK TRIB 2 26.0
END DESCRIPTION:
XS GIS Cut Line= 2
      3506920.11     10452211.55      3508625.86     10451820.93
#Sta/Elev= 30
  4621.1  422.24  4688.9  421.58  4742.5  419.49  4828.3  415.14  4930.9  412.94
  4961.7  407.62  4982.2  401.93  4996.5  396.56  4999.3  396.06  5002.5  396.56
    5054  411.19  5090.5  409.75  5133.4  410.49  5279.7  417.35  5363.4  418.99
  5443.9  418.58  5674.1  413.13  5710.6  410.84  5722.1  411.52  5807.9  409.31
  5833.7  407.61  5850.9   401.6  5874.7  400.29  5893.8  403.45  5898.9  403.14
  5905.5  405.81  5915.8  407.55  5941.8  410.03  6172.2  421.77    6371  428.15
#Mann= 4 ,-1 , 0
  4621.1      .1       0  4742.5     .16       0  4996.5     .07       0
  5002.5     .16       0
Bank Sta=4996.5,5002.5
XS Rating Curve= 0 ,0
Exp/Cntr=0.3,0.1

Type RM Length L Ch R = 1 ,11929   ,681,681,681
BEGIN DESCRIPTION:
HEADS CREEK TRIB 2 23.0
END DESCRIPTION:
XS GIS Cut Line= 2
      3507414.91     10452719.37      3509627.79     10452263.77
#Sta/Elev= 30
  4415.2   413.5    4443  410.77  4523.7  410.66  4585.9  407.75  4616.5  409.14
    4637  405.98  4718.6  404.97  4730.1  401.78  4830.9  396.87  4976.6  393.88
  5157.7  395.04  5223.1  398.42  5229.1  400.79  5249.5   399.3  5351.6  404.14
  5361.8  406.39  5519.9  410.52  5716.1  405.49  5749.8  407.08  5790.7  403.32
  5821.8  403.72  5861.9  396.81  5959.6  393.77  5962.3  393.27  5965.6  393.77
    6018   396.8  6056.1  403.86  6107.2   403.3  6574.6  423.85  6674.5     426
#Mann= 4 ,-1 , 0
  4415.2     .16       0  5959.6     .07       0  5965.6     .16       0
  6574.6     .05       0
Bank Sta=5959.6,5965.6
XS Rating Curve= 0 ,0
Exp/Cntr=0.3,0.1

Type RM Length L Ch R = 1 ,11248   ,698,698,698
BEGIN DESCRIPTION:
HEADS CREEK TRIB 2 22.0
END DESCRIPTION:
XS GIS Cut Line= 2
      3507623.21     10453031.87      3509248.96     10453122.91
#Sta/Elev= 30
    4214  421.94    4253  419.83  4298.7  416.45  4303.7  416.89  4323.1  415.38
  4433.2  409.87  4463.3  407.45  4478.3  407.04  4533.4   403.1  4553.4  402.15
  4623.5  395.73  4683.6   392.8  4720.7   392.3  4723.4   391.8  4726.7   392.3
  4832.4   392.7  5114.3   392.4  5174.4  393.19  5214.5  394.99  5254.5  398.05
  5314.6  400.45  5404.8  405.14  5414.8  406.09  5454.8  407.44    5535  411.19
    5565  413.26  5665.2   415.9  5715.2  416.61  5735.3  417.67  5842.3  420.33
#Mann= 3 ,-1 , 0
    4214     .16       0  4720.7     .07       0  4726.7     .16       0
Bank Sta=4720.7,4726.7
XS Rating Curve= 0 ,0
Exp/Cntr=0.3,0.1

Type RM Length L Ch R = 1 ,10551   ,1868,1868,1868
BEGIN DESCRIPTION:
HEADS CREEK TRIB 2 20.0
END DESCRIPTION:
XS GIS Cut Line= 2
      3506448.96     10452824.29      3508768.09     10453838.74
#Sta/Elev= 30
  3477.3   397.8  3600.8   396.8  3612.6  398.63  3630.5  410.61  3644.5  412.81
  4060.9  404.12  4183.3  406.79  4201.1  410.67  4253.5  412.36  4334.6  409.05
  4419.4  414.72  4488.4  411.28    4628  408.55    4772  404.86  4876.4  403.87
  4899.7  398.86  5001.3  391.97  5004.1  391.47  5007.3  391.97  5021.1  392.82
  5051.1   394.8  5085.4     406    5118  400.81  5280.3  401.77    5406  401.64
  5679.5  408.34  5786.6  404.98  5871.1  405.24  5958.7  397.41  6008.6  397.72
#Mann= 10 ,-1 , 0
  3477.3     .16       0  4488.4     .05       0    4628     .16       0
    4772     .05       0  5001.3     .03       0  5007.3     .05       0
  5021.1     .16       0  5280.3     .12       0    5406     .16       0
  5786.6     .05       0
Bank Sta=5001.3,5007.3
XS Rating Curve= 0 ,0
Exp/Cntr=0.3,0.1

Type RM Length L Ch R = 1 ,8673    ,395,395,395
BEGIN DESCRIPTION:
HEADS CREEK TRIB 2 19.0
END DESCRIPTION:
XS GIS Cut Line= 2
      3506130.01     10454675.93     3508325.657    10454244.189
#Sta/Elev= 30
  3729.1  394.04  4026.8  388.88  4128.7  383.57  4244.8  384.36  4296.2  381.77
  4322.3  378.12  4373.3   379.6  4455.5  379.22    4516  376.49  4553.2  372.86
    4656  369.94  4781.6  369.95  4933.8     370    4992  367.69  4994.7  367.19
    4998  367.69  5198.8  372.08  5219.2  370.36  5277.8  371.78  5334.3  375.87
  5463.8  393.09  5606.5  397.94  5744.9  400.49  5932.6  402.48  5973.4  405.36
  5983.6  399.08  5993.7  396.04  6058.9  393.98    6241  381.93  6377.4  373.64
#Mann= 6 ,-1 , 0
  3729.1     .16       0  4781.6     .12       0    4992     .07       0
    4998     .12       0  5744.9     .16       0    6241      .1       0
Bank Sta=4992,4998
XS Rating Curve= 0 ,0
Exp/Cntr=0.3,0.1

Type RM Length L Ch R = 1 ,8278    ,531,531,531
BEGIN DESCRIPTION:
HEADS CREEK TRIB 2 17.0
END DESCRIPTION:
XS GIS Cut Line= 2
      3506282.11     10455050.09      3508305.44     10454645.43
#Sta/Elev= 30
  3782.7  384.83  4047.8  387.04  4149.8  381.79  4241.6  383.17    4564  374.85
  4671.1  378.23  4680.1  377.61  4700.5  370.61  4710.7  370.12  4873.4  369.59
  5003.5  366.89  5006.2  366.39  5009.5  366.89    5028  368.77  5169.6  370.07
    5241   374.7  5261.4  373.86  5277.9  367.84    5283  374.58  5328.8  368.12
  5333.9  374.94  5363.4  374.73  5373.6  377.56  5384.9  385.12  5424.6  386.21
  5465.4  394.04  5528.4  398.02  5822.3  408.65  5838.8  406.08  5846.1  408.12
#Mann= 5 ,-1 , 0
  3782.7     .16       0  4873.4     .12       0  5003.5     .07       0
  5009.5     .12       0  5528.4     .16       0
Bank Sta=5003.5,5009.5
XS Rating Curve= 0 ,0
Exp/Cntr=0.3,0.1

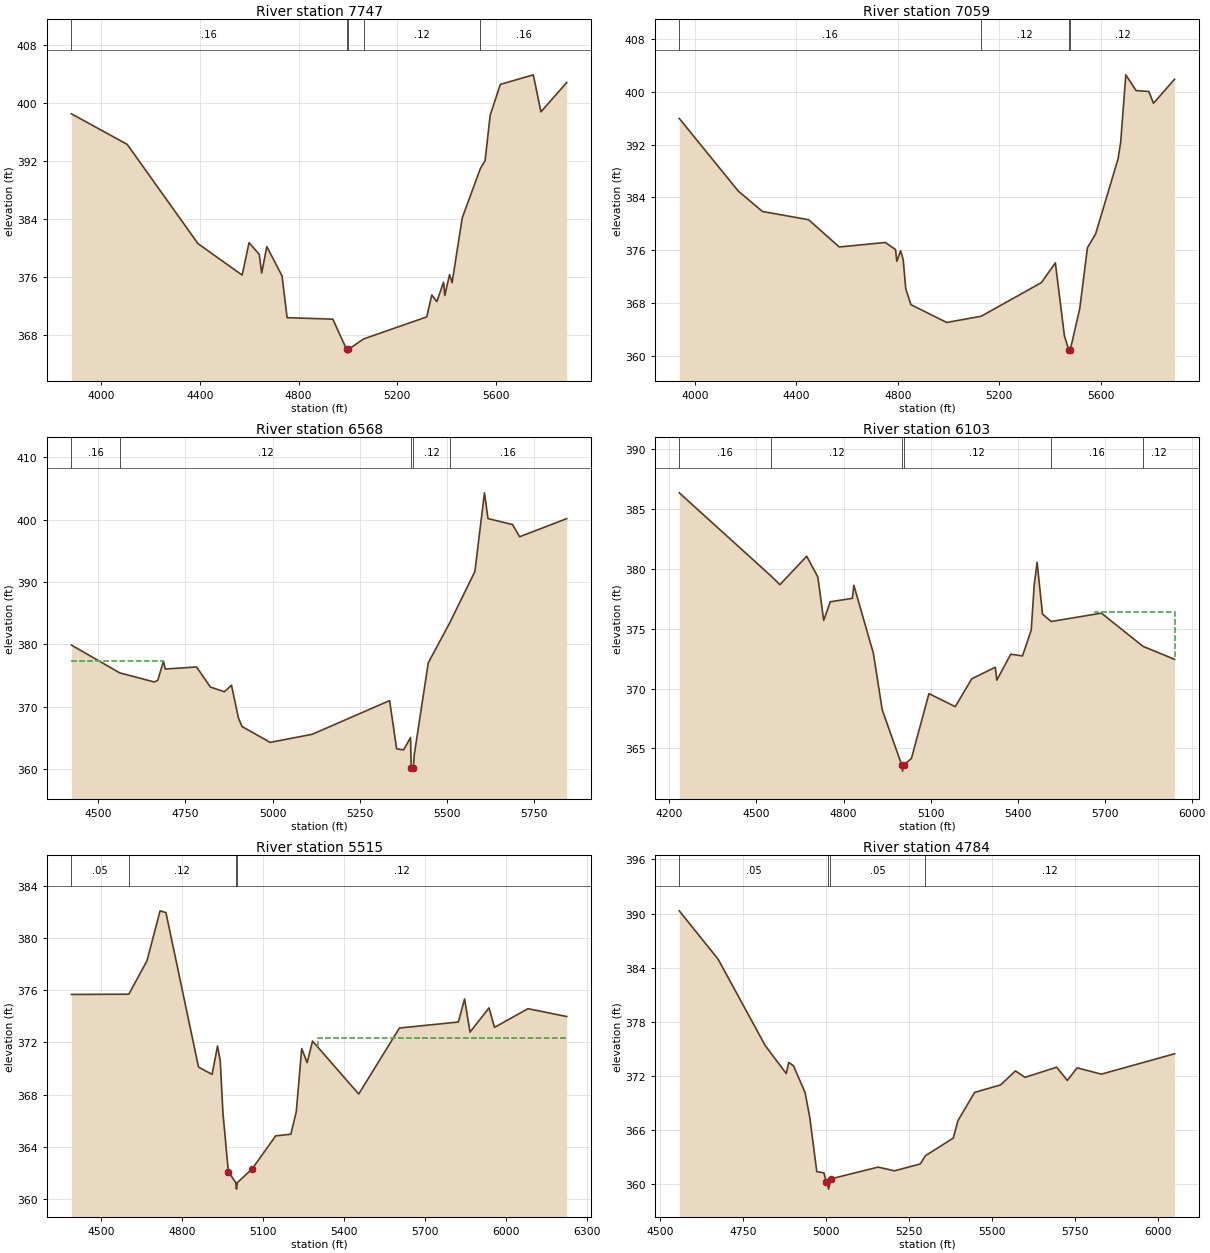
Type RM Length L Ch R = 1 ,7747    ,688,688,688
BEGIN DESCRIPTION:
HEADS CREEK TRIB 2 16.0
END DESCRIPTION:
XS GIS Cut Line= 2
       3506522.3      10455556.5       3508473.7     10455091.22
#Sta/Elev= 30
    3880  398.49    4106  394.28  4392.7  380.61  4571.5  376.28  4599.4  380.74
  4640.5  379.15  4650.6  376.56  4671.4   380.2  4733.1  376.16  4753.6  370.41
  4938.7  370.21  4994.8  366.03  4997.6  365.53  5000.8  366.03    5064  367.49
    5319  370.52  5339.6  373.54  5360.2  372.62  5387.2   375.3  5392.3  373.47
  5411.6  376.35  5421.8  375.22    5463  384.17  5536.1  390.93  5555.5  392.03
  5576.1   398.3  5617.2  402.54  5750.8  403.86  5781.7  398.76  5886.1   402.8
#Mann= 5 ,-1 , 0
    3880     .16       0  4994.8     .07       0  5000.8     .16       0
    5064     .12       0  5536.1     .16       0
Bank Sta=4994.8,5000.8
XS Rating Curve= 0 ,0
Exp/Cntr=0.3,0.1

Type RM Length L Ch R = 1 ,7059    ,491,491,491
BEGIN DESCRIPTION:
HEADS CREEK TRIB 2 12.0
END DESCRIPTION:
XS GIS Cut Line= 2
      3506716.84     10455966.48      3508652.66     10455716.42
#Sta/Elev= 30
  3939.2  395.98  4171.8  384.96  4267.2  381.86  4448.7  380.62  4569.7  376.48
  4751.2  377.16  4791.5  376.09  4796.6   374.3  4811.7  375.91  4821.7  374.55
  4831.8  370.13    4852  367.73  4993.1  365.02  5129.2  365.97  5366.2  371.07
  5421.4  374.06    5457  363.01  5474.1  360.87  5476.9  360.37  5480.1  360.87
  5517.5  367.13  5547.7  376.35  5580.1  378.47  5668.7  389.88  5678.8  392.39
    5699   402.6  5739.3  400.21  5789.7  400.07  5808.1  398.28  5891.1  401.93
#Mann= 4 ,-1 , 0
  3939.2     .16       0  5129.2     .12       0  5474.1     .07       0
  5480.1     .12       0
Bank Sta=5474.1,5480.1
XS Rating Curve= 0 ,0
Exp/Cntr=0.3,0.1

Type RM Length L Ch R = 1 ,6568    ,465,465,465
BEGIN DESCRIPTION:
Mapping XS 8dde4c10
END DESCRIPTION:
XS GIS Cut Line= 2
       3507376.5     10456306.49      3508786.18     10456146.77
#Sta/Elev= 30
  4423.9   379.9  4562.5  375.45    4661     374  4671.1  374.25  4687.6  377.33
  4692.6  376.07  4782.3   376.4    4822  373.18    4862  372.44  4882.4  373.47
  4902.5  368.19  4912.6  366.87  4993.1  364.33  5113.9  365.63  5335.3  371.02
  5355.4  363.29  5375.6  363.14  5395.2   365.1  5397.2  360.23  5399.9  359.73
  5403.2  360.23  5405.7  362.27    5446  377.06  5507.7  383.48  5579.6  391.68
    5607  404.27  5617.1  400.15  5687.5  399.19  5707.7  397.24  5842.6  400.14
#Mann= 5 ,-1 , 0
  4423.9     .16       0  4562.5     .12       0  5397.2     .07       0
  5403.2     .12       0  5507.7     .16       0
#XS Ineff= 2 , 0
         4687.27  377.33
Permanent Ineff=
       F       F
Bank Sta=5397.2,5403.2
XS Rating Curve= 0 ,0
Exp/Cntr=0.3,0.1

Type RM Length L Ch R = 1 ,6103    ,588,588,588
BEGIN DESCRIPTION:
Mapping XS e91b4908
END DESCRIPTION:
XS GIS Cut Line= 2
      3507327.93     10456563.44     3508550.914    10456713.808
#Sta/Elev= 30
  4233.9  386.37  4551.4  379.39  4580.7  378.69  4673.1  381.07  4711.6  379.33
  4731.8   375.7  4754.4  377.26  4830.6  377.55  4835.7  378.64  4903.1  372.94
  4933.3  368.24  5000.8   363.6  5003.6   363.1  5006.8   363.6  5034.1  364.16
  5094.5  369.58  5185.2  368.49    5242  370.82  5323.3  371.79  5328.4  370.71
  5376.6  372.88  5416.9  372.73  5447.1  374.89  5457.2  378.63  5467.3  380.56
  5485.9  376.23  5515.7  375.61    5689  376.31  5832.7  373.53  5941.1  372.45
#Mann= 6 ,-1 , 0
  4233.9     .16       0  4551.4     .12       0  5000.8     .07       0
  5006.8     .12       0  5515.7     .16       0  5832.7     .12       0
#XS Ineff= 2 , 0
                         5667.61          376.41
Permanent Ineff=
       F       F
Bank Sta=5000.8,5006.8
XS Rating Curve= 0 ,0
Exp/Cntr=0.3,0.1

Type RM Length L Ch R = 1 ,5515    ,731,731,731
BEGIN DESCRIPTION:
HEADS CREEK TRIB 2 9.0
END DESCRIPTION:
XS GIS Cut Line= 2
      3507453.99     10457315.72      3509278.23     10457099.59
#Sta/Elev= 30
  4389.4  375.67  4602.4  375.69  4669.5  378.24  4718.2  382.07    4740  381.93
  4860.8  370.11  4911.1  369.55  4931.3  371.72  4941.4  370.58  4951.4  366.59
  4971.5   362.1  4998.8  361.27  5001.5  360.77  5004.8  361.27  5059.3  362.31
  5147.1  364.85  5203.2  364.97  5223.3  366.69  5243.5  371.53  5263.6  370.45
  5283.7   372.1  5454.9  368.05    5606   373.1  5824.5  373.56  5847.6  375.33
  5867.8  372.79  5938.3  374.64  5958.4  373.15  6082.9  374.58  6226.4  373.98
#Mann= 4 ,-1 , 0
  4389.4     .05       0  4602.4     .12       0  4998.8     .07       0
  5004.8     .12       0
#XS Ineff= 2 , 0
                         5303.98           372.3
Permanent Ineff=
       F       F
Bank Sta=4971.5,5059.3
XS Rating Curve= 0 ,0
Exp/Cntr=0.3,0.1

Type RM Length L Ch R = 1 ,4784    ,1110,1110,1110
BEGIN DESCRIPTION:
HEADS CREEK TRIB 2 7.0
END DESCRIPTION:
XS GIS Cut Line= 3
      3508222.16       10458097.      3508788.52     10457475.84
      3509371.32     10457187.12
#Sta/Elev= 30
  4557.9  390.31  4674.7  384.96  4816.5  375.39    4880  372.28  4887.5  373.51
  4901.7  373.14  4936.8  370.16    4951  367.36  4971.9  361.41  4993.5  361.27
  5000.3  360.28  5004.7  359.97  5007.5  359.47  5010.7  359.97  5014.5  360.61
  5156.4  361.91  5205.7   361.5  5283.4  362.26  5298.8  363.17  5382.7  365.12
  5396.9  367.07  5447.2  370.19  5525.3  371.02  5569.9  372.57  5598.6  371.86
  5693.9  372.98  5726.1  371.51  5755.6  372.91  5828.4  372.21  6048.9  374.47
#Mann= 4 ,-1 , 0
  4557.9     .05       0  5004.7     .03       0  5010.7     .05       0
  5298.8     .12       0
Bank Sta=5000.3,5014.5
XS Rating Curve= 0 ,0
Exp/Cntr=0.3,0.1

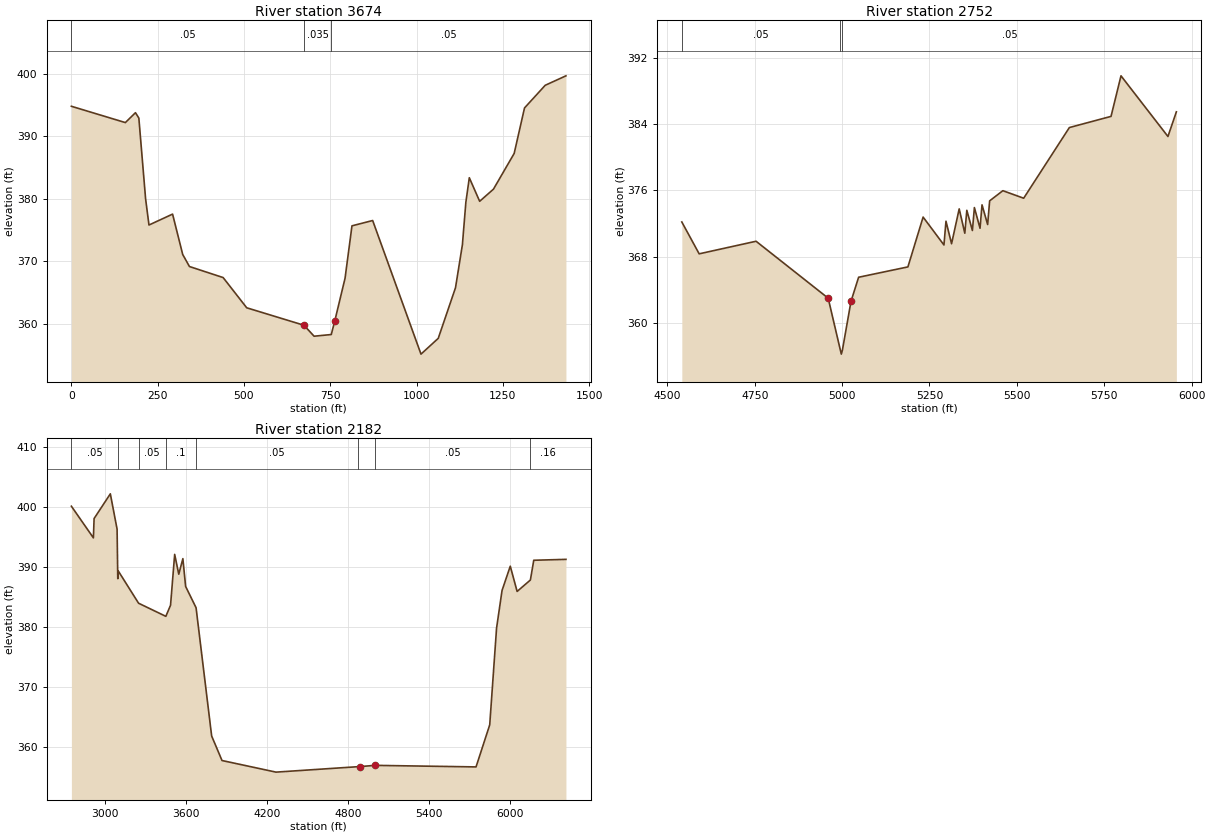
Type RM Length L Ch R = 1 ,3674    ,922,922,922
XS GIS Cut Line= 4
      3508787.33    10458505.478      3509131.08    10458505.478
     3509448.788    10458316.676      3510006.08    10457854.437
#Sta/Elev= 30
       0394.7586156.3492392.1499185.6647393.7332195.4365392.8691214.9802379.9536
 224.752375.7618293.1548377.5066322.4702371.0552342.0139369.1228439.6051367.3571
 507.919362.5218673.8241359.7268703.1014 357.974752.8536358.2445762.8519360.3686
792.8466367.2521812.8431375.6314872.8326376.48311012.808 355.1091062.799357.6321
1112.791365.72661132.787372.60841142.785379.38961152.784383.32681182.778379.5565
1222.771381.49971282.761387.21291312.756394.49381372.745398.11751432.735399.6298
#Mann= 3 ,-1 , 0
       0     .05       0673.8241    .035       0752.8536     .05       0
#XS Ineff= 2 , 0
                          871.82          376.41
Permanent Ineff=
       F       F
Bank Sta=673.8241,762.8519
XS Rating Curve= 0 ,0
Exp/Cntr=0.3,0.1

Type RM Length L Ch R = 1 ,2752    ,570,570,570
BEGIN DESCRIPTION:
HEADS CREEK TRIB 2 4.0
END DESCRIPTION:
XS GIS Cut Line= 2
      3509721.95     10458999.66      3510960.84     10458316.42
#Sta/Elev= 30
  4541.5  372.19  4591.1  368.34  4753.9  369.86  4960.2  362.98    4995  356.72
  4997.8  356.22    5001  356.72  5025.5   362.6  5047.3  365.51  5188.3  366.76
  5231.8  372.78  5291.4  369.41  5297.2  372.28  5313.2  369.56    5335  373.77
  5351.1  370.83  5356.8   373.6  5372.8  371.16  5378.5  373.93  5394.6  371.43
  5400.3  374.26  5416.4  371.88  5422.1  374.74  5459.9  375.97  5519.5  375.06
  5650.2   383.6  5769.4  384.95  5797.9  389.85  5932.2  382.52  5956.3   385.5
#Mann= 3 ,-1 , 0
  4541.5     .05       0    4995     .03       0    5001     .05       0
Bank Sta=4960.2,5025.5
XS Rating Curve= 0 ,0
Exp/Cntr=0.3,0.1

Type RM Length L Ch R = 1 ,2182    ,0,0,0
BEGIN DESCRIPTION:
HEADS CREEK TRIB 2 1.0
END DESCRIPTION:
XS GIS Cut Line= 3
      3508248.24     10459594.37      3511529.48     10459034.47
      3511607.36     10458709.95
#Sta/Elev= 30
  2750.5  400.17  2913.5  394.88  2918.6  398.11  3038.9  402.24  3088.9  396.34
    3094  388.06  3098.5  389.32  3248.1  383.96    3450  381.77  3484.8  383.63
  3515.3  392.12  3545.7  388.81  3576.1  391.41  3596.4  386.77  3673.8  383.21
  3789.2  361.78  3865.9  357.68  4265.7  355.74  4873.4  356.65  4884.8  356.66
  4998.8  356.87  5747.1  356.61  5848.5  363.64  5899.2  379.81  5939.8   386.1
  6000.7  390.15  6051.4  385.93  6149.6  387.84  6174.6  391.14  6412.9  391.29
#Mann= 8 ,-1 , 0
  2750.5     .05       0  3098.5     .16       0  3248.1     .05       0
    3450      .1       0  3673.8     .05       0  4873.4    .035       0
  4998.8     .05       0  6149.6     .16       0
Bank Sta=4884.8,4998.8
XS Rating Curve= 0 ,0
Exp/Cntr=0.3,0.1
Stream Node=HEADS CREEK TRIB,Reach-1         , 0 , 0 ,Upstream end
Stream Node=HEADS CREEK TRIB,Reach-1         , 0 , 1 ,Downstream end

Chan Stop Cuts=-1
Use User Specified Reach Order=0
Composite Channel Slope=5