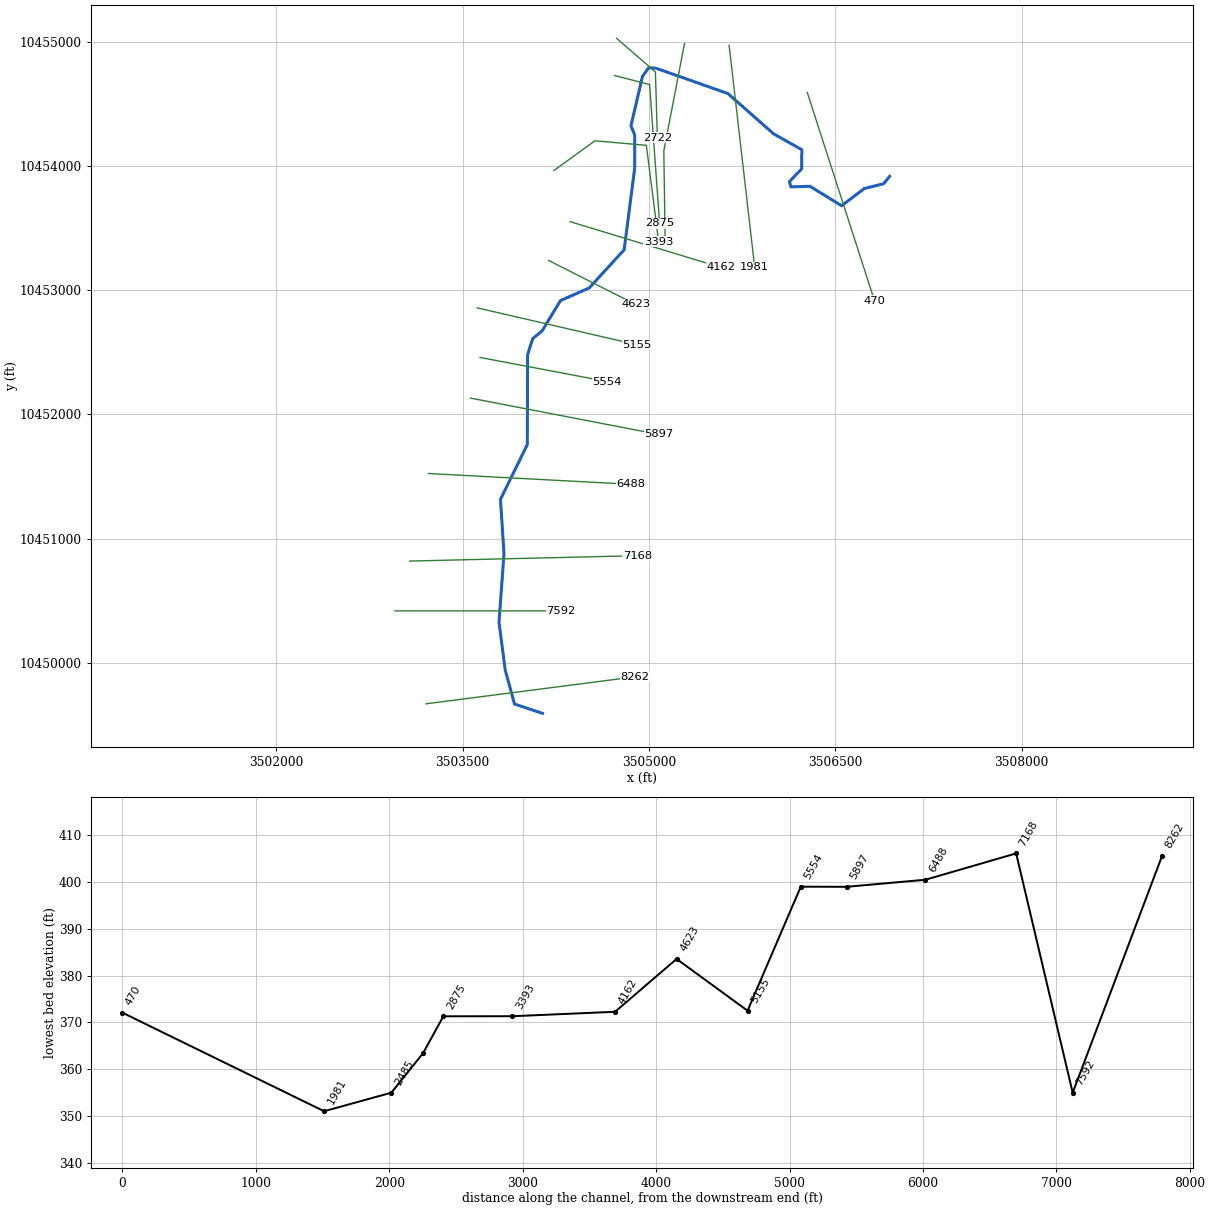
--- HEADS CREEK TRIB 3.prj (project) ---

Proj Title=HEADS CREEK TRIB 3 Base Level Engineering
Current Plan=p01
Default Exp/Contr=0.3,0.1
English Units
Geom File=g01
Flow File=f01
Plan File=p01
Y Axis Title=Elevation
X Axis Title(PF)=Main Channel Distance
X Axis Title(XS)=Station
BEGIN DESCRIPTION:
HEADS CREEK TRIB 3
END DESCRIPTION:
DSS Export Rating Curves= 0
DSS Export Rating Curve Sorted= 0
DSS Export Volume Flow Curves= 0
DXF OffsetX= 0
DXF OffsetY= 0
DXF ScaleX= 1
DXF ScaleY= 10

--- HEADS CREEK TRIB 3.p01 (plan) ---

Plan Title=Multiple Run
Short Identifier=Multiple
Geom File=g01
Flow File=f01
Subcritical Flow
K Sum by GR= 0
Std Step Tol= 0.01
Critical Tol= 0.01
Num of Std Step Trials= 20
Max Error Tol= 0.3
Flow Tol Ratio= 0.001
Split Flow NTrial= 30
Split Flow Tol= 0.02
Split Flow Ratio= 0.02
Log Output Level= 0
Friction Slope Method= 1
Unsteady Friction Slope Method= 2
Unsteady Bridges Friction Slope Method= 1
Parabolic Critical Depth
Global Vel Dist=  1 , 1 , 1
Global Log Level= 0
CheckData=True
Encroach Param= -1, 0, 0, 0
BEGIN DESCRIPTION:
Multiple Run
END DESCRIPTION:

--- HEADS CREEK TRIB 3.f01 (steady flow) ---

Flow Title=Multiple
Number of Profiles=7
Profile Names=10-year,25-year,50-year,1pct_min,100-year,1pct_plu,500-year
River Rch & RM= HEADS CREEK TRIB,Reach-1,8262
     937    1287    1574    1405    1900    2569    2761
Boundary for River Rch & Prof#=HEADS CREEK TRIB,Reach-1,1
Up Type=0
Dn Type=3
Dn Slope=0.005
Boundary for River Rch & Prof#=HEADS CREEK TRIB,Reach-1,2
Up Type=0
Dn Type=3
Dn Slope=0.005
Boundary for River Rch & Prof#=HEADS CREEK TRIB,Reach-1,3
Up Type=0
Dn Type=3
Dn Slope=0.005
Boundary for River Rch & Prof#=HEADS CREEK TRIB,Reach-1,4
Up Type=0
Dn Type=3
Dn Slope=0.005
Boundary for River Rch & Prof#=HEADS CREEK TRIB,Reach-1,5
Up Type=0
Dn Type=3
Dn Slope=0.005
Boundary for River Rch & Prof#=HEADS CREEK TRIB,Reach-1,6
Up Type=0
Dn Type=3
Dn Slope=0.005
Boundary for River Rch & Prof#=HEADS CREEK TRIB,Reach-1,7
Up Type=0
Dn Type=3
Dn Slope=0.005

--- HEADS CREEK TRIB 3.g01 (geometry) ---

Geom Title=Existing Conditions
Program Version=4.10

River Reach=HEADS CREEK TRIB,Reach-1
Reach XY= 30
      3504142.11     10449591.64       3503916.8     10449666.95
      3503842.11     10449941.64      3503792.11     10450325.87
      3503832.42     10450879.97      3503803.82     10451315.86
      3504020.25     10451757.37       3504022.3     10452481.48
      3504063.66     10452611.19      3504139.27     10452673.31
      3504287.14     10452917.27      3504518.67     10453019.33
      3504800.05     10453326.78      3504884.96     10453985.37
      3504884.96     10454252.04      3504854.69     10454325.51
      3504947.93     10454724.14      3504996.11     10454792.37
      3505053.86      10454790.5      3505635.17      10454585.6
      3506003.66     10454260.86      3506231.23     10454132.69
      3506229.41     10453978.53      3506130.97     10453875.66
      3506142.69     10453833.48      3506296.45     10453838.16
      3506550.96     10453681.46      3506734.12     10453820.35
      3506889.07     10453858.98      3506937.92     10453918.41

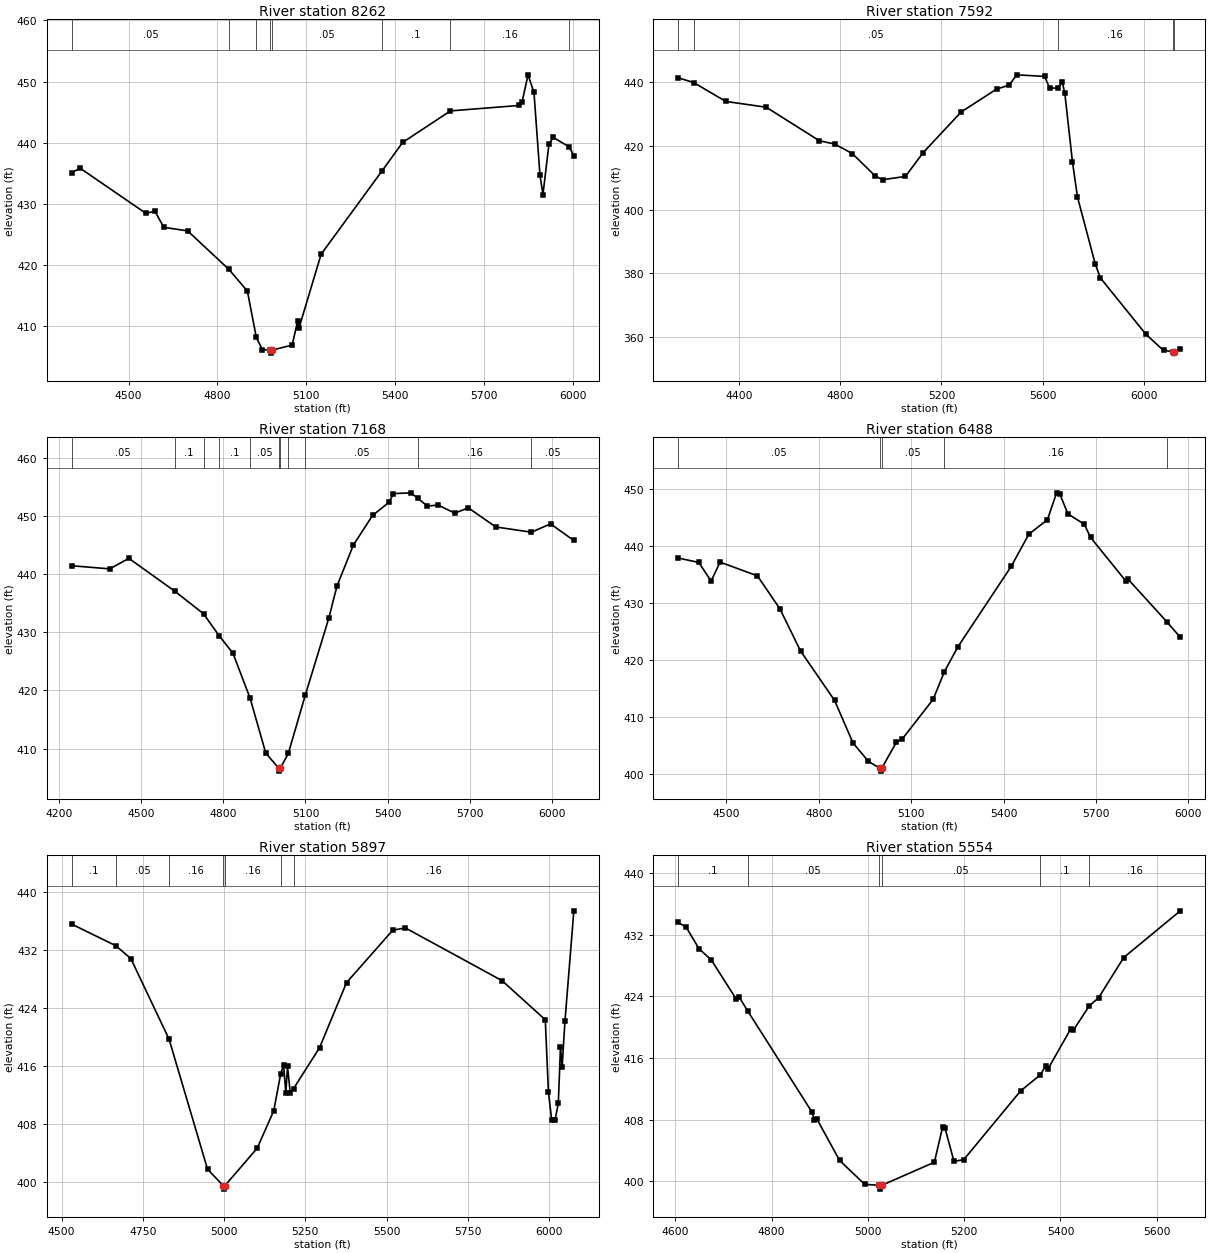
Type RM Length L Ch R = 1 ,8262    ,670,670,670
BEGIN DESCRIPTION:
HEADS CREEK TRIB 3 18.0
END DESCRIPTION:
XS GIS Cut Line= 2
       3503203.8     10449668.62      3504885.66     10449885.64
#Sta/Elev= 30
  4308.3  435.11  4336.8  435.83  4558.7  428.45  4588.9  428.81  4619.2  426.17
  4699.8  425.58  4839.4  419.27  4901.5  415.73  4931.5  408.18  4951.9  406.16
  4979.1  406.09  4981.9  405.59  4985.1  406.09  5052.7   406.9  5071.1  410.81
  5076.1  409.75  5150.5  421.77  5355.3  435.33  5425.8  440.05  5587.3  445.21
    5819   446.1  5829.1  446.62  5849.3  451.11  5869.4  448.24  5889.6  434.76
  5899.7  431.53  5919.9  439.72  5934.4  440.87    5989  439.31  6004.1  437.87
#Mann= 8 ,-1 , 0
  4308.3     .05       0  4839.4      .1       0  4931.5     .05       0
  4979.1     .03       0  4985.1     .05       0  5355.3      .1       0
  5587.3     .16       0    5989      .1       0
Bank Sta=4979.1,4985.1
XS Rating Curve= 0 ,0
Exp/Cntr=0.3,0.1

Type RM Length L Ch R = 1 ,7592    ,424,424,424
BEGIN DESCRIPTION:
HEADS CREEK TRIB 3 16.0
END DESCRIPTION:
XS GIS Cut Line= 2
      3502954.21     10450417.32     3504292.042    10450417.321
#Sta/Elev= 30
  4159.8  441.42  4220.7  439.93  4347.7     434  4507.7  432.17  4717.7  421.64
  4777.7  420.62  4847.7  417.63  4937.7  410.62  4967.7  409.41  5057.7  410.44
  5127.7  417.91  5277.7  430.66  5417.7  437.86  5467.7  439.11  5497.7  442.35
  5607.7  441.85  5627.7  438.23  5659.7  438.15  5677.7  440.06  5687.7   436.5
  5717.7  415.12  5737.7  403.95  5807.7  383.02  5827.7  378.62  6007.7  360.91
  6077.7   355.8  6114.7  355.45  6117.4  354.95  6120.7  355.45  6144.1  356.35
#Mann= 5 ,-1 , 0
  4159.8      .1       0  4220.7     .05       0  5659.7     .16       0
  6114.7    .035       0  6120.7     .16       0
Bank Sta=6114.7,6120.7
XS Rating Curve= 0 ,0
Exp/Cntr=0.3,0.1

Type RM Length L Ch R = 1 ,7168    ,680,680,680
BEGIN DESCRIPTION:
HEADS CREEK TRIB 3 15.0
END DESCRIPTION:
XS GIS Cut Line= 2
      3503073.58      10450818.8      3504907.27      10450862.2
#Sta/Elev= 30
  4246.3  441.49  4384.9  440.95  4454.9  442.76  4622.2  437.12  4727.6  433.22
  4784.1  429.46    4835  426.44  4897.8  418.67    4955  409.22  5002.3  406.61
    5005  406.11  5008.3  406.61  5037.4  409.15  5099.3  419.18  5185.1  432.43
  5215.1  437.98  5275.1  445.06  5345.1  450.15  5405.1  452.42  5421.6  453.91
  5485.2  454.05  5511.2  453.08  5545.2  451.77  5585.2  451.94  5645.2  450.55
  5695.2  451.46  5795.3  448.17  5925.4  447.27  5995.3   448.7  6080.5  445.84
#Mann= 11 ,-1 , 0
  4246.3     .05       0  4622.2      .1       0  4727.6     .05       0
  4784.1      .1       0  4897.8     .05       0  5002.3     .03       0
  5008.3     .05       0  5037.4      .1       0  5099.3     .05       0
  5511.2     .16       0  5925.4     .05       0
Bank Sta=5002.3,5008.3
XS Rating Curve= 0 ,0
Exp/Cntr=0.3,0.1

Type RM Length L Ch R = 1 ,6488    ,591,591,591
BEGIN DESCRIPTION:
HEADS CREEK TRIB 3 13.0
END DESCRIPTION:
XS GIS Cut Line= 2
      3503225.54     10451524.09      3504853.13     10451437.29
#Sta/Elev= 30
  4343.8  437.91  4410.5  437.13  4450.5  433.86  4479.6  437.19  4600.7  434.78
  4673.6  429.01  4740.9  421.58  4851.1  412.92  4911.2  405.42  4961.2   402.2
  4998.3  400.98    5001  400.48  5004.3  400.98  5051.7  405.52  5071.4  406.15
  5171.5   413.1  5207.6  417.92  5251.7  422.32  5424.7  436.43    5482   442.1
  5542.1  444.62  5572.1  449.36  5582.1  449.22  5608.7  445.67  5662.2  443.82
  5682.3  441.53  5797.7  433.81  5802.7  434.27  5929.4  426.74  5973.7  423.99
#Mann= 5 ,-1 , 0
  4343.8     .05       0  4998.3     .03       0  5004.3     .05       0
  5207.6     .16       0  5929.4      .1       0
Bank Sta=4998.3,5004.3
XS Rating Curve= 0 ,0
Exp/Cntr=0.3,0.1

Type RM Length L Ch R = 1 ,5897    ,343,343,343
BEGIN DESCRIPTION:
HEADS CREEK TRIB 3 12.0
END DESCRIPTION:
XS GIS Cut Line= 2
      3503561.87     10452131.73      3505079.02     10451839.14
#Sta/Elev= 30
  4531.3  435.55    4667  432.57  4713.2  430.79  4830.8  419.66  4949.1  401.72
    4997  399.47  4999.8  398.97    5003  399.47  5101.9  404.62  5152.8  409.78
  5174.3   414.9  5183.3  416.09  5190.1  412.23  5195.2   415.9  5203.7  412.27
  5213.7  412.84  5293.9   418.5  5376.8  427.48  5519.4  434.73  5558.3  435.02
  5855.5  427.75  5988.5  422.35  5998.1  412.44  6008.3  408.45  6018.4  408.46
  6028.6  410.83  6035.3  418.63  6040.3  415.79    6049  422.13  6076.4  437.39
#Mann= 7 ,-1 , 0
  4531.3      .1       0    4667     .05       0  4830.8     .16       0
    4997     .07       0    5003     .16       0  5174.3     .05       0
  5213.7     .16       0
Bank Sta=4997,5003
XS Rating Curve= 0 ,0
Exp/Cntr=0.3,0.1

Type RM Length L Ch R = 1 ,5554    ,399,399,399
BEGIN DESCRIPTION:
Mapping XS d785b2fc
END DESCRIPTION:
XS GIS Cut Line= 2
      3503639.55     10452459.41      3504663.86     10452264.96
#Sta/Elev= 30
  4606.3   433.6  4622.7  432.99  4649.6  430.18  4674.9  428.74  4727.2  423.61
  4732.3  423.98  4750.3  422.14  4883.7  409.03    4889  407.98  4894.1  408.11
  4941.3  402.73  4993.5  399.62  5023.2   399.5    5026     399  5029.2   399.5
  5138.2  402.49  5155.4   407.1  5160.5  406.87  5178.9   402.6  5199.3  402.83
  5317.2  411.74  5358.5  413.84  5369.5  415.01  5374.6  414.64  5421.8  419.84
  5426.9  419.63  5459.9  422.78  5479.1  423.82  5531.4  429.05  5648.9  435.11
#Mann= 6 ,-1 , 0
  4606.3      .1       0  4750.3     .05       0  5023.2    .035       0
  5029.2     .05       0  5358.5      .1       0  5459.9     .16       0
Bank Sta=5023.2,5029.2
XS Rating Curve= 0 ,0
Exp/Cntr=0.3,0.1

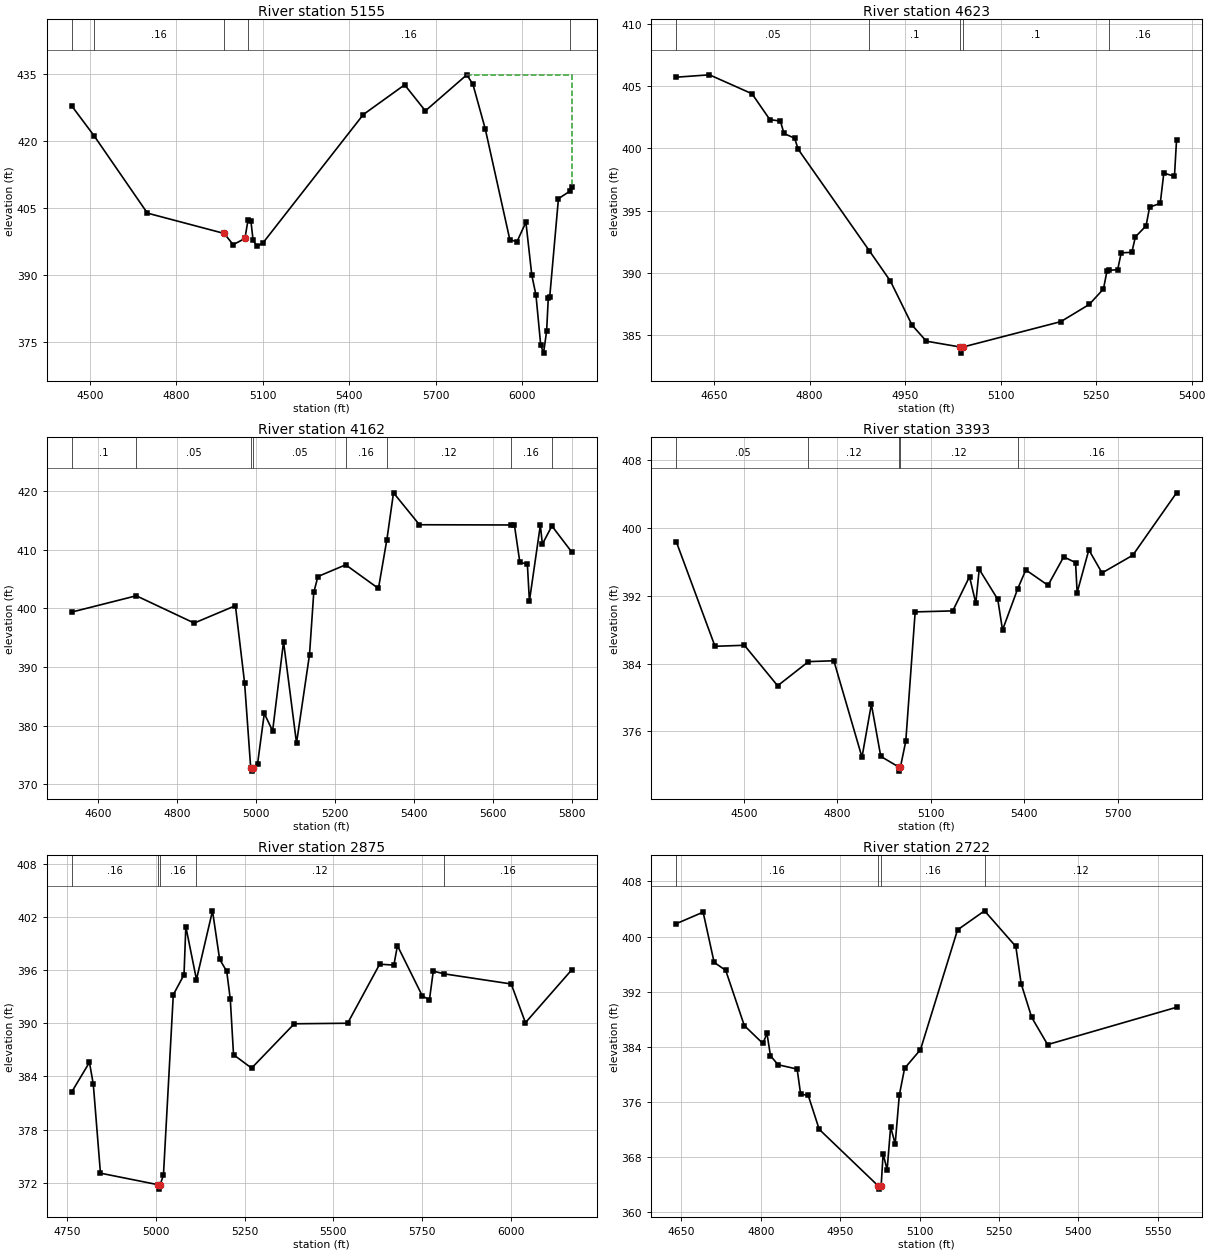
Type RM Length L Ch R = 1 ,5155    ,532,532,532
BEGIN DESCRIPTION:
HEADS CREEK TRIB 3 10.0
END DESCRIPTION:
XS GIS Cut Line= 2
      3503616.16     10452858.72     3504904.701    10452561.367
#Sta/Elev= 30
  4437.2  427.92  4515.1  421.19  4699.9  403.87  4966.7  399.31  4997.5  396.79
  5038.5   398.2  5048.8  402.22  5059.1  402.13  5066.6  397.89  5079.6  396.46
  5100.1  397.12  5449.1  425.96  5592.7  432.63  5664.6  426.79  5808.3  434.87
  5829.5  432.78  5872.3  422.78  5957.8  397.89  5982.7  397.49  6013.5  401.84
    6034  389.94  6048.4  385.51  6064.8  374.36  6074.8  372.49  6085.4  377.44
  6091.2  384.88  6096.3  385.18  6126.4  407.12  6167.5  408.84  6173.5  409.62
#Mann= 5 ,-1 , 0
  4437.2     .05       0  4515.1     .16       0  4966.7     .07       0
  5048.8     .16       0  6167.5     .05       0
#XS Ineff= 2 , 0
       0                 5806.25       0  434.83
Permanent Ineff=
       F       T
Bank Sta=4966.7,5038.5
XS Rating Curve= 0 ,0
Exp/Cntr=0.3,0.1

Type RM Length L Ch R = 1 ,4623    ,461,461,461
BEGIN DESCRIPTION:
Mapping XS c21eb920
END DESCRIPTION:
XS GIS Cut Line= 2
      3504191.58     10453240.68      3504892.85     10452886.57
#Sta/Elev= 30
  4590.7  405.71  4642.9   405.9  4709.7  404.38  4737.6  402.31  4754.3  402.18
  4759.9  401.19  4776.6  400.81  4782.2  399.92  4893.8  391.78  4927.1  389.33
    4961   385.8  4983.4  384.51  5035.6  384.05  5038.3  383.55  5041.6  384.05
  5194.6  386.08  5239.2  387.46  5261.5   388.7  5267.1  390.15  5270.3   390.2
  5283.8  390.25  5289.4   391.6  5306.1  391.65  5311.7  392.89  5328.4  393.77
    5334  395.27  5350.7  395.58  5356.3  398.01    5373  397.75  5376.3  400.68
#Mann= 5 ,-1 , 0
  4590.7     .05       0  4893.8      .1       0  5035.6     .07       0
  5041.6      .1       0  5270.3     .16       0
Bank Sta=5035.6,5041.6
XS Rating Curve= 0 ,0
Exp/Cntr=0.3,0.1

Type RM Length L Ch R = 1 ,4162    ,769,769,769
BEGIN DESCRIPTION:
HEADS CREEK TRIB 3 8.0
END DESCRIPTION:
XS GIS Cut Line= 2
      3504364.87     10453553.16      3505578.58     10453184.72
#Sta/Elev= 30
  4532.4  399.37  4696.2  402.15    4843   397.5  4947.5  400.46  4970.8  387.27
  4986.3  372.76  4989.1  372.26  4992.3  372.76  5003.7  373.53  5020.7  382.09
  5041.8  379.11  5069.5   394.3  5102.4  377.05  5135.3  392.11  5146.1  402.71
  5156.6  405.43    5227  407.43  5310.1   403.4  5331.5  411.74  5348.3   419.7
    5414  414.26  5645.2  414.22  5654.7  414.25  5668.6  407.83  5687.6  407.57
  5692.8  401.24  5720.5  414.18  5725.7  410.96  5749.8  414.05  5800.8  409.55
#Mann= 8 ,-1 , 0
  4532.4      .1       0  4696.2     .05       0  4986.3     .03       0
  4992.3     .05       0    5227     .16       0  5331.5     .12       0
  5645.2     .16       0  5749.8     .05       0
Bank Sta=4986.3,4992.3
XS Rating Curve= 0 ,0
Exp/Cntr=0.3,0.1

Type RM Length L Ch R = 1 ,3393    ,518,518,518
BEGIN DESCRIPTION:
Mapping XS a4aa226a
END DESCRIPTION:
XS GIS Cut Line= 4
      3504234.06     10453965.19      3504564.76     10454204.75
      3504978.82     10454168.29      3505077.77      10453392.3
#Sta/Elev= 30
  4283.1  398.42  4407.6  386.05    4502  386.17  4608.7  381.39  4707.7  384.24
  4789.2  384.34  4879.5  372.95  4909.6  379.21  4939.8  373.05    4997  371.81
  4999.7  371.31    5003  371.81  5020.1  374.84  5050.2  390.11  5170.9  390.23
  5224.7  394.27  5244.9  391.14  5255.8  395.14  5315.4  391.59  5330.7  387.97
  5379.4  392.84  5405.5  395.07  5476.7  393.25  5527.1  396.61  5565.2  395.93
  5570.2  392.38  5607.8  397.44  5650.1  394.71  5748.9   396.8  5889.4  404.17
#Mann= 5 ,-1 , 0
  4283.1     .05       0  4707.7     .12       0    4997     .07       0
    5003     .12       0  5379.4     .16       0
Bank Sta=4997,5003
XS Rating Curve= 0 ,0
Exp/Cntr=0.3,0.1

Type RM Length L Ch R = 1 ,2875    ,153,153,153
BEGIN DESCRIPTION:
Mapping XS 17ab67ab
END DESCRIPTION:
XS GIS Cut Line= 3
      3504723.64     10454730.79      3505004.86     10454657.88
      3505085.59     10453540.71
#Sta/Elev= 30
  4762.7  382.24  4812.8  385.59  4823.7   383.1  4843.8  373.09    5006  371.79
  5008.8  371.29    5012  371.79  5021.4  372.86  5049.2  393.22  5079.4  395.47
  5084.5   400.9  5114.5  394.93  5159.7  402.68  5179.8  397.22  5199.8  395.86
  5209.9   392.7    5219  386.45    5270  384.94  5390.3  389.94  5540.7     390
    5631  396.66  5671.1  396.56  5681.1  398.75  5751.3  393.08  5771.3  392.64
  5782.2  395.88    5813  395.57  6001.9  394.43    6042  390.06  6173.3  396.06
#Mann= 5 ,-1 , 0
  4762.7     .16       0    5006     .07       0    5012     .16       0
  5114.5     .12       0    5813     .16       0
Bank Sta=5006,5012
XS Rating Curve= 0 ,0
Exp/Cntr=0.3,0.1

Type RM Length L Ch R = 1 ,2722    ,237,237,237
BEGIN DESCRIPTION:
Mapping XS d68559f0
END DESCRIPTION:
XS GIS Cut Line= 3
       3504739.2      10455030.3      3505051.74     10454759.44
      3505067.36     10454228.14
#Sta/Elev= 30
  4640.4  401.86  4691.2  403.54    4712  396.26  4733.9  395.09    4769  387.09
  4804.2  384.49  4811.8  385.96  4818.4  382.72  4832.7  381.41  4868.8  380.78
  4875.4  377.14  4889.7  376.97  4910.5  372.04  5021.5  363.87  5024.3  363.37
  5027.5  363.87  5031.2   368.5  5038.8  366.15  5045.4  372.39    5054  369.92
  5061.8     377  5071.8  380.89  5101.8   383.6  5171.8  400.97  5222.8  403.73
  5281.9  398.56  5291.9  393.18  5311.9  388.27  5341.9  384.33  5585.5  389.74
#Mann= 4 ,-1 , 0
  4640.4     .16       0  5021.5     .07       0  5027.5     .16       0
  5222.8     .12       0
Bank Sta=5021.5,5027.5
XS Rating Curve= 0 ,0
Exp/Cntr=0.3,0.1

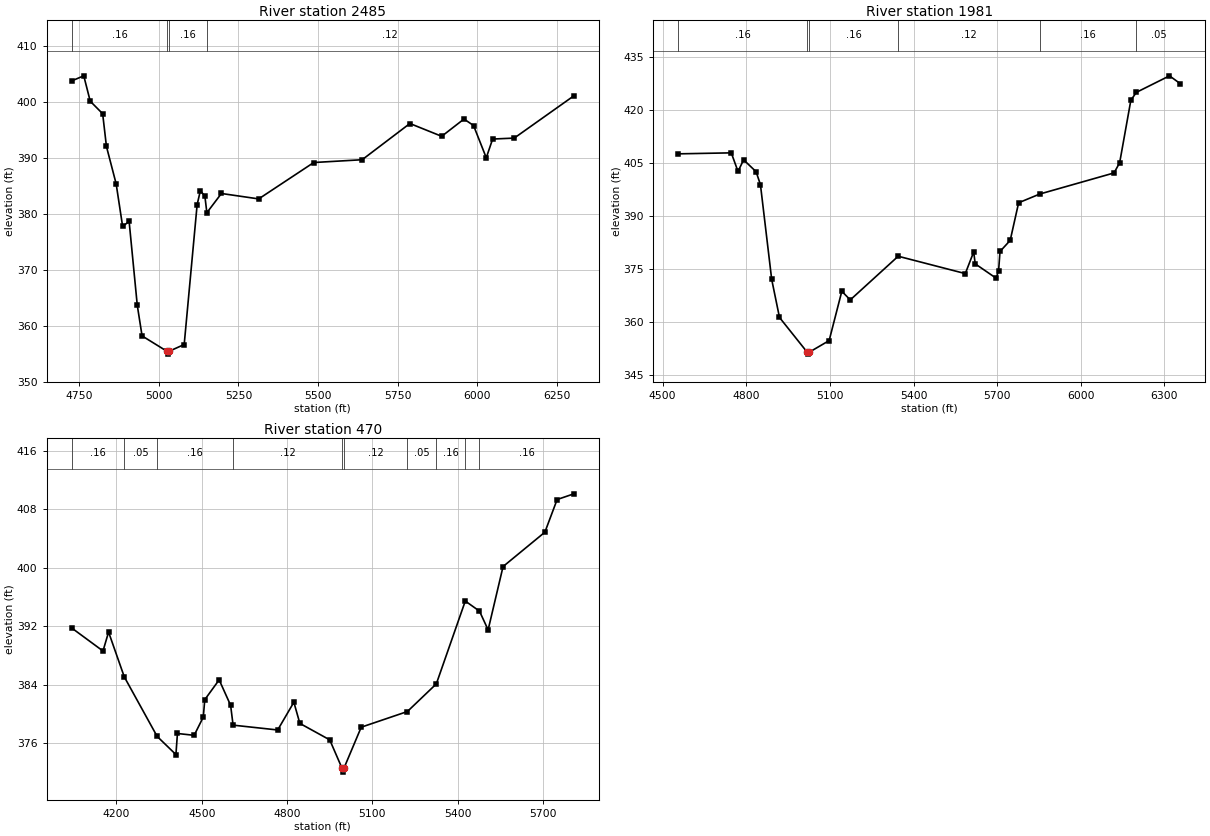
Type RM Length L Ch R = 1 ,2485    ,504,504,504
BEGIN DESCRIPTION:
HEADS CREEK TRIB 3 5.0
END DESCRIPTION:
XS GIS Cut Line= 3
      3505286.12     10454988.64      3505119.44     10454124.02
      3505129.86     10453426.33
#Sta/Elev= 30
    4726  403.85  4763.7  404.75    4784  400.21  4823.1  397.97    4835  392.11
  4865.5  385.43  4885.9   377.8  4906.3  378.71  4931.9   363.7    4947  358.22
  5025.5  355.46  5028.2  354.96  5031.5  355.46  5079.4  356.68  5120.1  381.71
  5130.3  384.22  5144.5  383.19  5150.7  380.26  5196.4   383.7  5313.6  382.73
  5486.7  389.24  5638.9  389.74  5788.9  396.22  5888.9  393.93    5959  397.02
    5989  395.86    6029  390.09    6049  393.44  6116.9  393.61  6304.3  401.17
#Mann= 4 ,-1 , 0
    4726     .16       0  5025.5     .07       0  5031.5     .16       0
  5150.7     .12       0
Bank Sta=5025.5,5031.5
XS Rating Curve= 0 ,0
Exp/Cntr=0.3,0.1

Type RM Length L Ch R = 1 ,1981    ,1511,1511,1511
BEGIN DESCRIPTION:
HEADS CREEK TRIB 3 3.0
END DESCRIPTION:
XS GIS Cut Line= 2
      3505645.22      10454974.6      3505851.25     10453185.43
#Sta/Elev= 30
    4556  407.53  4746.3  407.81  4770.4  402.56  4790.5  405.84  4835.3  402.49
  4850.9  398.82  4891.2  372.11  4919.2  361.35    5019   351.5  5021.8     351
    5025   351.5  5097.3  354.82  5142.8  368.75    5173   366.3    5345  378.63
  5585.7  373.73  5615.9  379.87  5621.2  376.49  5696.4  372.43  5705.2  374.57
  5710.2  379.97  5746.8  383.11    5777  393.72  5852.9  396.19  6119.2  402.14
  6139.4  405.01  6179.6  422.67  6199.5  424.89  6318.2  429.55    6357  427.33
#Mann= 6 ,-1 , 0
    4556     .16       0    5019     .07       0    5025     .16       0
    5345     .12       0  5852.9     .16       0  6199.5     .05       0
Bank Sta=5019,5025
XS Rating Curve= 0 ,0
Exp/Cntr=0.3,0.1

Type RM Length L Ch R = 1 ,470     ,0,0,0
BEGIN DESCRIPTION:
HEADS CREEK TRIB 3 1.0
END DESCRIPTION:
XS GIS Cut Line= 2
      3506274.56     10454594.84      3506816.51     10452914.78
#Sta/Elev= 30
  4043.1  391.75  4152.9  388.61  4172.5   391.2  4227.7  385.08  4343.3  376.94
  4409.3  374.46  4414.6  377.34  4473.4  377.09  4505.5  379.58  4510.7  381.96
  4561.3  384.67  4601.6  381.19  4610.3  378.48  4767.1  377.82    4824  381.61
    4845  378.72  4950.1  376.47  4993.7  372.56  4996.4  372.06  4999.7  372.56
  5060.8   378.2  5223.1  380.34  5324.9  384.12  5426.7  395.44  5476.6  394.06
    5507   391.5  5559.5  400.15  5706.6  404.85  5749.6  409.31  5808.4  410.09
#Mann= 10 ,-1 , 0
  4043.1     .16       0  4227.7     .05       0  4343.3     .16       0
  4610.3     .12       0  4993.7     .07       0  4999.7     .12       0
  5223.1     .05       0  5324.9     .16       0  5426.7     .05       0
  5476.6     .16       0
Bank Sta=4993.7,4999.7
XS Rating Curve= 0 ,0
Exp/Cntr=0.3,0.1

Chan Stop Cuts=-1
Use User Specified Reach Order=0
Composite Channel Slope=5