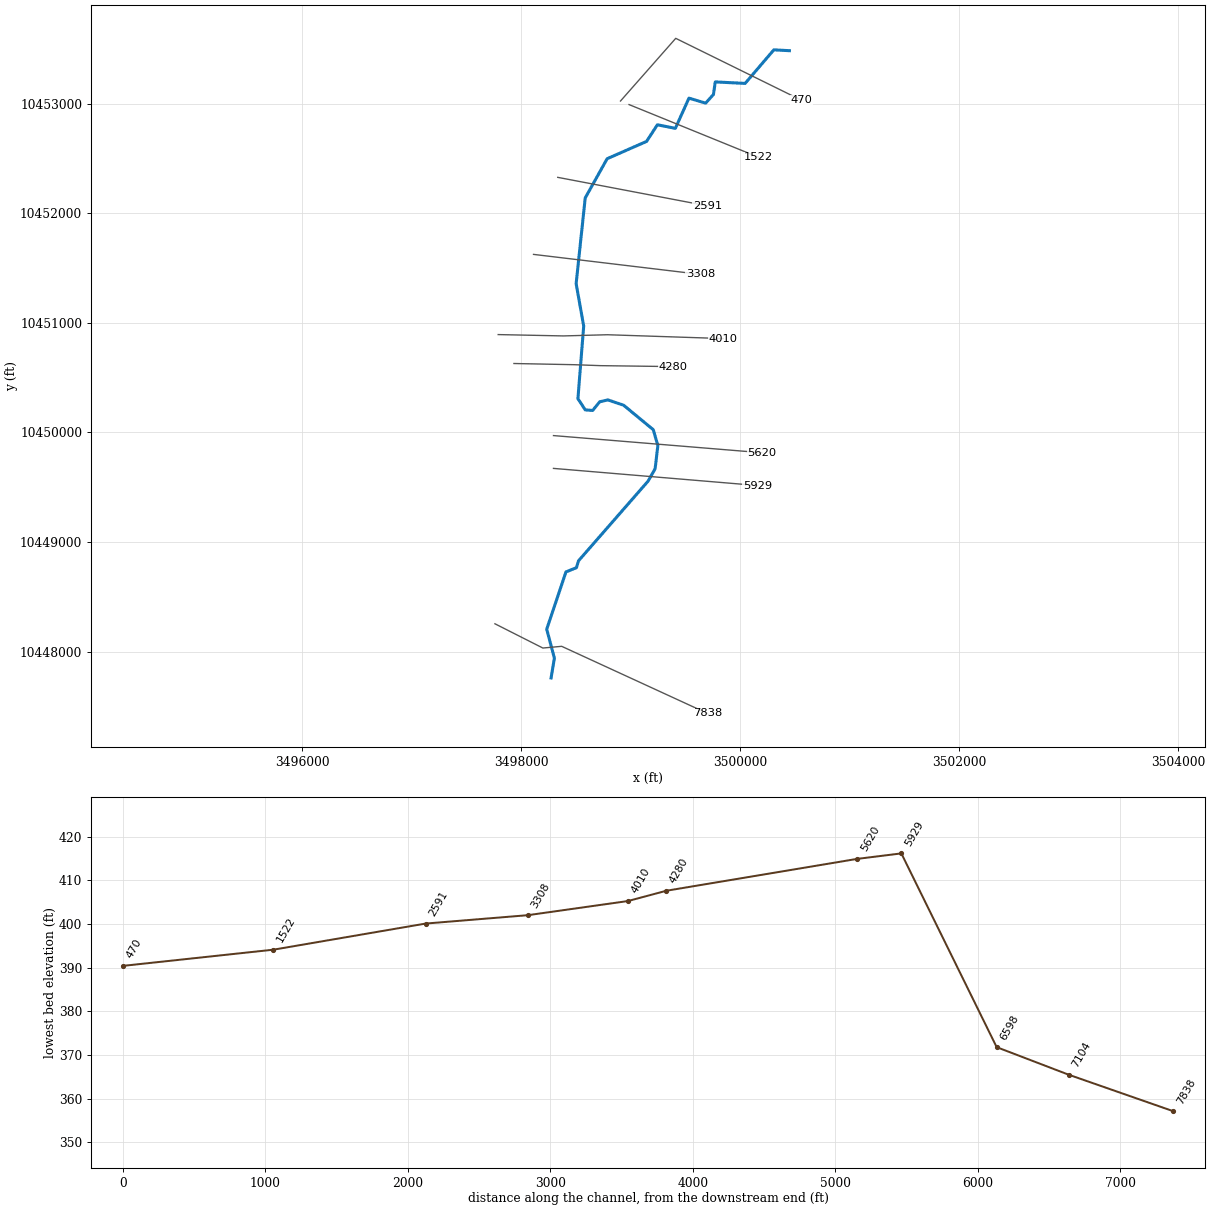
--- HEADS CREEK TRIB 4.prj (project) ---

Proj Title=HEADS CREEK TRIB 4 Base Level Engineering
Current Plan=p01
Default Exp/Contr=0.3,0.1
English Units
Geom File=g01
Flow File=f01
Plan File=p01
Y Axis Title=Elevation
X Axis Title(PF)=Main Channel Distance
X Axis Title(XS)=Station
BEGIN DESCRIPTION:
HEADS CREEK TRIB 4
END DESCRIPTION:
DSS Export Rating Curves= 0
DSS Export Rating Curve Sorted= 0
DSS Export Volume Flow Curves= 0
DXF OffsetX= 0
DXF OffsetY= 0
DXF ScaleX= 1
DXF ScaleY= 10

--- HEADS CREEK TRIB 4.p01 (plan) ---

Plan Title=Multiple Run
Short Identifier=Multiple
Geom File=g01
Flow File=f01
Subcritical Flow
K Sum by GR= 0
Std Step Tol= 0.01
Critical Tol= 0.01
Num of Std Step Trials= 20
Max Error Tol= 0.3
Flow Tol Ratio= 0.001
Split Flow NTrial= 30
Split Flow Tol= 0.02
Split Flow Ratio= 0.02
Log Output Level= 0
Friction Slope Method= 1
Unsteady Friction Slope Method= 2
Unsteady Bridges Friction Slope Method= 1
Parabolic Critical Depth
Global Vel Dist=  1 , 1 , 1
Global Log Level= 0
CheckData=True
Encroach Param= -1, 0, 0, 0
BEGIN DESCRIPTION:
Multiple Run
END DESCRIPTION:

--- HEADS CREEK TRIB 4.f01 (steady flow) ---

Flow Title=Multiple
Program Version=4.10
Number of Profiles= 7
Profile Names=10-year,25-year,50-year,1pct_min,100-year,1pct_plu,500-year
River Rch & RM=HEADS CREEK TRIB,Reach-1         ,7838
     764    1033    1250    1105    1494    2020    2127
Boundary for River Rch & Prof#=HEADS CREEK TRIB,Reach-1         , 1
Up Type= 0
Dn Type= 3
Dn Slope=0.005
Boundary for River Rch & Prof#=HEADS CREEK TRIB,Reach-1         , 2
Up Type= 0
Dn Type= 3
Dn Slope=0.005
Boundary for River Rch & Prof#=HEADS CREEK TRIB,Reach-1         , 3
Up Type= 0
Dn Type= 3
Dn Slope=0.005
Boundary for River Rch & Prof#=HEADS CREEK TRIB,Reach-1         , 4
Up Type= 0
Dn Type= 3
Dn Slope=0.005
Boundary for River Rch & Prof#=HEADS CREEK TRIB,Reach-1         , 5
Up Type= 0
Dn Type= 3
Dn Slope=0.005
Boundary for River Rch & Prof#=HEADS CREEK TRIB,Reach-1         , 6
Up Type= 0
Dn Type= 3
Dn Slope=0.005
Boundary for River Rch & Prof#=HEADS CREEK TRIB,Reach-1         , 7
Up Type= 0
Dn Type= 3
Dn Slope=0.005
DSS Import GetInterval= 0
DSS Import GetPeak= 0
DSS Import FillOption= 0

--- HEADS CREEK TRIB 4.g01 (geometry) ---

Geom Title=Existing Conditions
Program Version=4.10

River Reach=HEADS CREEK TRIB,Reach-1
Reach XY= 30
      3498273.28      10447759.5      3498303.62     10447940.55
      3498233.48     10448204.44      3498409.18     10448727.35
      3498505.01     10448766.24      3498523.76     10448828.74
      3499158.49     10449555.35      3499223.29     10449668.95
      3499248.29     10449880.07      3499206.62      10450025.2
      3498935.79     10450248.82      3498792.04     10450297.43
      3498717.04     10450280.07      3498653.15      10450200.9
      3498585.09     10450206.45      3498518.43     10450308.54
      3498571.16      10450971.6      3498502.15     10451358.13
      3498585.04     10452140.43      3498785.34      10452498.5
      3499144.95     10452656.44      3499244.18     10452808.21
      3499408.41     10452775.82      3499532.24     10453051.58
      3499684.53     10453005.78      3499756.01     10453084.77
      3499772.58     10453199.55      3500045.04     10453185.87
      3500307.49      10453492.2      3500449.81     10453484.69

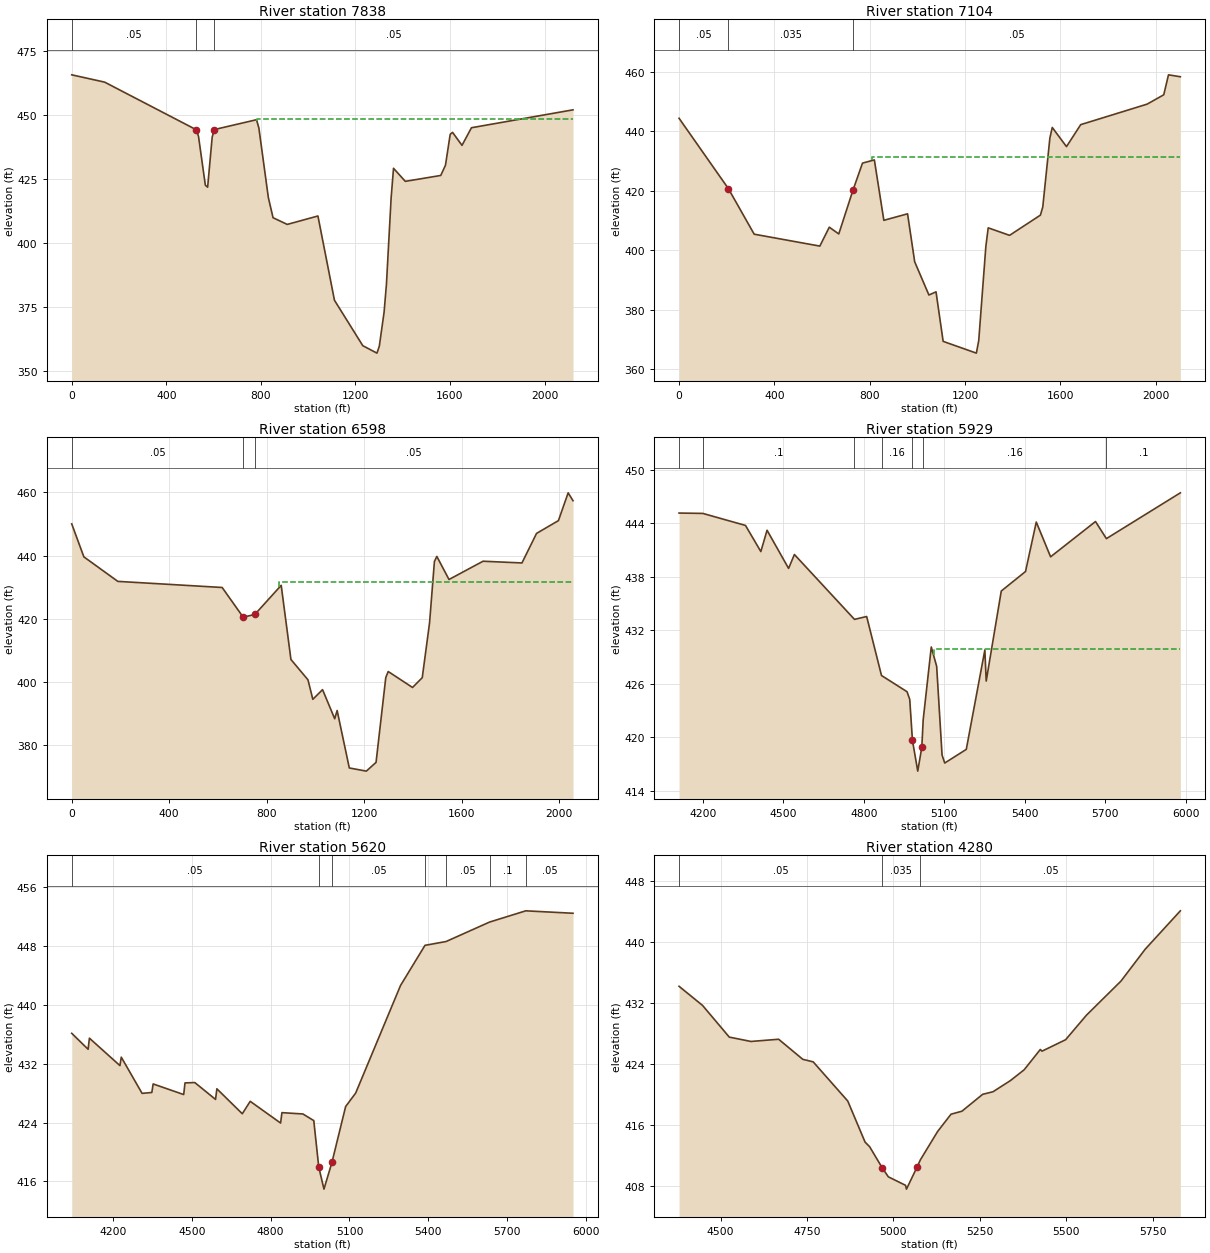
Type RM Length L Ch R = 1 ,7838    ,734,734,734
XS GIS Cut Line= 4
     3497760.749    10448254.189     3498198.249    10448032.835
     3498370.124     10448048.46     3499700.853     10447436.48
#Sta/Elev= 30
       0465.7449139.3512462.8899526.6443444.3209536.2982441.7457565.2597422.6667
574.9136421.8953594.2213 441.477603.8751444.3962781.7013448.2193791.6932444.9908
 831.661417.8846851.6448409.9727911.5964407.34891041.492410.64151111.435377.7497
1231.338360.0098 1291.29357.10941301.282359.87521321.266373.01181331.258 383.894
1351.241417.79541361.233429.26441411.193424.16221561.072426.46481581.056430.4642
 1601.04 442.5221611.032443.27931650.999438.21441690.967 445.089 2120.62452.0809
#Mann= 3 ,-1 , 0
       0     .05       0526.6443    .035       0603.8751     .05       0
#XS Ineff= 2 , 0
                          782.67          448.46
Permanent Ineff=
       F       F
Bank Sta=526.6443,603.8751
XS Rating Curve= 0 ,0
Exp/Cntr=0.3,0.1

Type RM Length L Ch R = 1 ,7104    ,506,506,506
#Sta/Elev= 30
       0444.3046206.8374 420.702315.1807405.3954590.5681 401.402630.2305407.7482
670.0338405.4775729.7389420.2124769.5422429.2501819.2964430.3237859.0999410.0505
958.6083412.2347988.4608396.14491048.166384.98271078.018386.04751107.871369.4255
1247.183365.47541257.134369.66191286.986401.24421296.937407.52441386.494405.0083
1515.855411.79021525.806414.53661555.659437.6753 1565.61 441.2171625.315434.7861
 1685.02442.16581963.643449.04712033.299452.18762053.201458.88482102.955458.2388
#Mann= 3 , 0 , 0
       0     .05       0206.8374    .035       0729.7389     .05       0
#XS Ineff= 2 , 0
                          811.08          431.21
Permanent Ineff=
       F       F
Bank Sta=206.8374,729.7389
XS Rating Curve= 0 ,0
Exp/Cntr=0.3,0.1

Type RM Length L Ch R = 1 ,6598    ,669,669,669
#Sta/Elev= 30
       0450.032949.77363439.6033189.1398431.8405 617.193429.9095703.3989420.5088
 751.291421.3801  859.38  430.59899.3456407.1254969.1807400.6949989.1336394.5248
1029.039397.58061078.922388.37581088.898390.9766 1138.78372.80241208.615371.7987
1248.521374.57041288.427401.41031298.403403.31731398.168398.27021438.073 401.369
1468.003418.68691487.956438.14361497.932439.73711547.814432.43481687.484438.2181
1847.108437.67261906.966447.02091996.754451.0701 2036.66459.86222056.613457.3728
#Mann= 3 , 0 , 0
       0     .05       0703.3989    .035       0 751.291     .05       0
#XS Ineff= 2 , 0
                          852.27          431.71
Permanent Ineff=
       F       F
Bank Sta=703.3989,751.291
XS Rating Curve= 0 ,0
Exp/Cntr=0.3,0.1

Type RM Length L Ch R = 1 ,5929    ,309,309,309
BEGIN DESCRIPTION:
Mapping XS 8e9ed186
END DESCRIPTION:
XS GIS Cut Line= 2
      3498295.27     10449672.29      3500157.22     10449516.05
#Sta/Elev= 30
  4111.6  445.17  4200.1  445.13  4359.3  443.78  4416.4  440.85  4439.6  443.24
  4519.9  438.96  4541.5  440.52  4765.5  433.24  4810.9  433.56  4866.2  426.94
  4961.4  425.12  4971.4  424.27  4981.5  419.67  5001.3  416.21  5016.4  418.88
  5021.6  421.98  5051.7  430.14  5071.8  427.97  5091.9  418.02  5101.9  417.12
  5182.2  418.65  5251.4   429.8  5256.5  426.32  5312.6  436.42    5403  438.61
  5443.1  444.16  5496.5  440.26  5663.9  444.22  5704.4   442.3  5980.1  447.44
#Mann= 7 ,-1 , 0
  4111.6     .05       0  4200.1      .1       0  4765.5     .05       0
  4866.2     .16       0  4981.5     .07       0  5021.6     .16       0
  5704.4      .1       0
#XS Ineff= 2 , 0
                         5060.23          429.89
Permanent Ineff=
       F       F
Bank Sta=4981.5,5016.4
XS Rating Curve= 0 ,0
Exp/Cntr=0.3,0.1

Type RM Length L Ch R = 1 ,5620    ,1340,1340,1340
BEGIN DESCRIPTION:
HEADS CREEK TRIB 4 11.0
END DESCRIPTION:
XS GIS Cut Line= 2
      3498295.34     10449971.77      3500196.33     10449815.52
#Sta/Elev= 30
  4043.1  436.13  4105.4  433.96  4110.4  435.47  4226.6  431.74  4231.6  432.89
  4310.8  427.97  4347.9  428.09  4352.9  429.25  4469.1  427.81  4474.1  429.39
  4511.4  429.44  4590.3  427.15  4595.4  428.59  4692.1   425.2  4722.2  426.89
  4837.8  423.94  4842.9  425.35  4922.8  425.17  4964.1  424.27    4983  417.97
  5002.8  414.96  5033.2  418.59  5085.3  426.18  5123.5  428.01  5294.1  442.62
  5387.2  448.08  5467.5   448.6  5632.8  451.24  5770.7  452.77  5950.5  452.44
#Mann= 7 ,-1 , 0
  4043.1     .05       0    4983    .035       0  5033.2     .05       0
  5387.2      .1       0  5467.5     .05       0  5632.8      .1       0
  5770.7     .05       0
Bank Sta=4983,5033.2
XS Rating Curve= 0 ,0
Exp/Cntr=0.3,0.1

Type RM Length L Ch R = 1 ,4280    ,270,270,270
BEGIN DESCRIPTION:
HEADS CREEK TRIB 4 9.0
END DESCRIPTION:
XS GIS Cut Line= 4
      3497934.21     10450629.55      3498485.42      10450618.7
      3498724.13     10450610.02      3499383.89     10450601.34
#Sta/Elev= 30
  4380.1   434.2    4448   431.7  4525.4  427.55    4588  426.98  4668.1  427.27
  4738.1  424.64  4768.1  424.31  4868.1  419.18  4918.1  413.81  4931.4   413.2
  4968.1  410.41  4985.5  409.26  5035.2  408.15  5037.9  407.65  5068.2  410.51
  5078.2  411.49  5128.2  415.21  5166.8  417.46  5198.3  417.85  5258.3  420.06
  5288.3   420.4  5338.3  421.85  5378.3  423.27    5425  425.93    5430  425.71
  5498.3  427.21  5558.3  430.41  5658.3  434.88  5728.3  439.05  5830.1  444.08
#Mann= 3 ,-1 , 0
  4380.1     .05       0  4968.1    .035       0  5078.2     .05       0
Bank Sta=4968.1,5068.2
XS Rating Curve= 0 ,0
Exp/Cntr=0.3,0.1

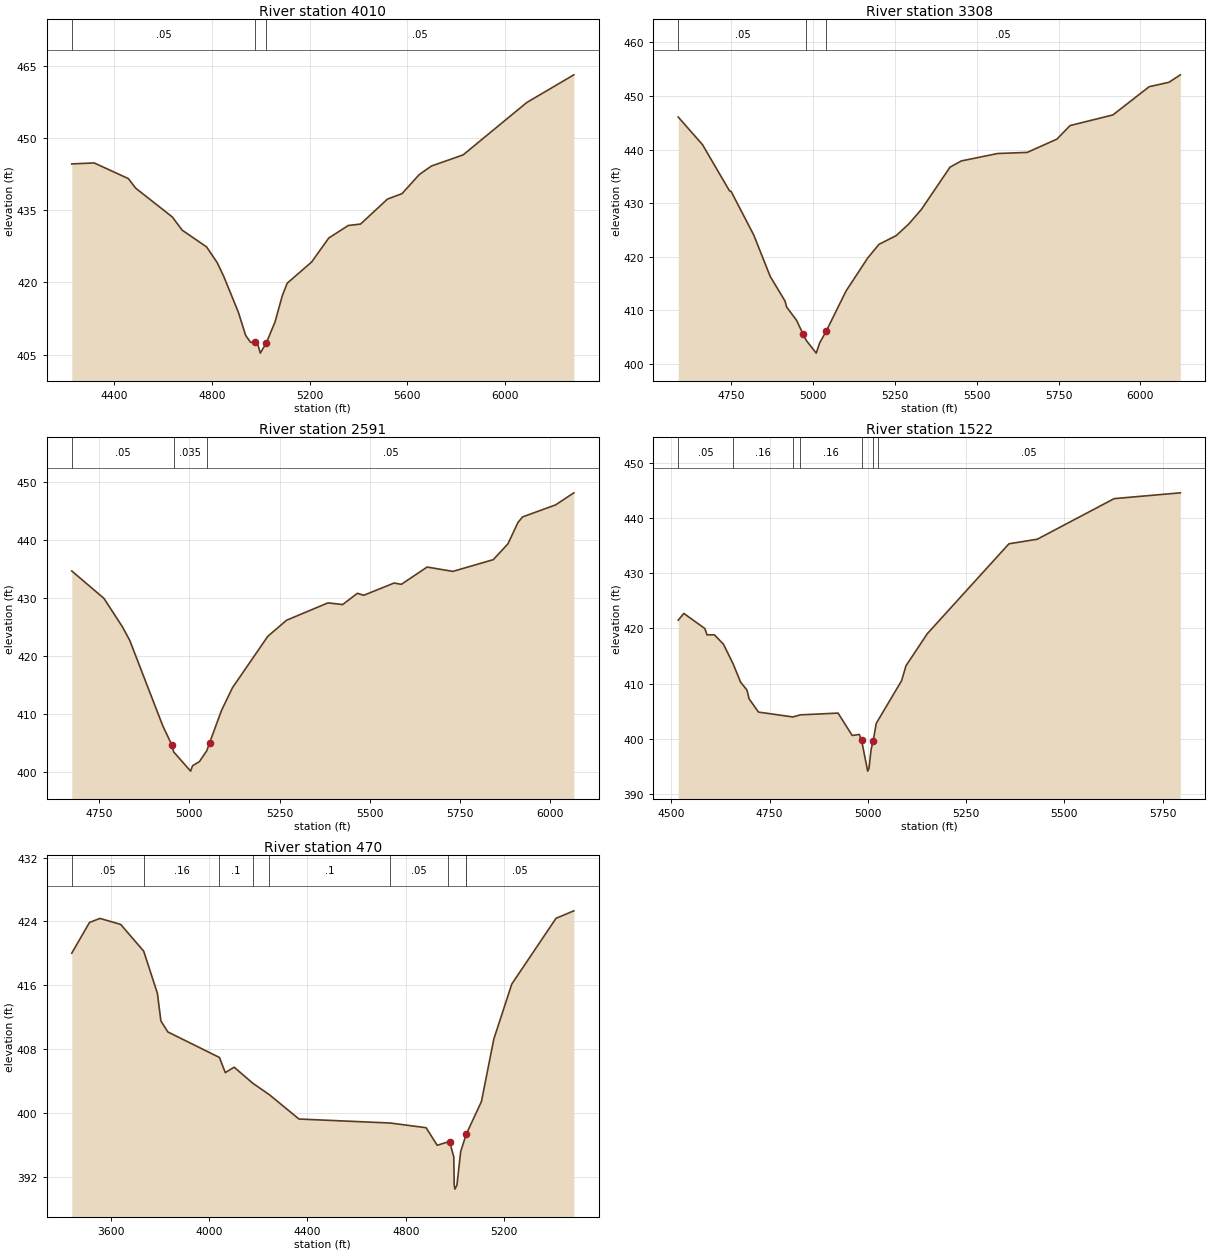
Type RM Length L Ch R = 1 ,4010    ,702,702,702
BEGIN DESCRIPTION:
HEADS CREEK TRIB 4 8.0
END DESCRIPTION:
XS GIS Cut Line= 4
      3497790.37     10450893.55      3498385.59     10450881.28
      3498789.24     10450892.13      3499844.82     10450857.19
#Sta/Elev= 30
    4226  444.63  4317.8  444.83  4457.8  441.57  4487.8  439.58  4637.8  433.59
  4677.8  430.86  4777.8  427.38  4821.3  424.11  4847.9  421.27  4907.9  413.81
  4937.9  408.97  4957.9  407.54  4977.9  407.51  4987.9  407.05  4997.7  405.29
  5021.9  407.35  5057.9  411.75    5088  417.26    5108  419.83    5208  424.24
    5278  429.22  5358.1  431.83  5408.1  432.12  5518.2  437.31  5578.2  438.46
  5648.2   442.4  5698.3  444.19  5828.3  446.51  6088.5  457.39  6281.3  463.15
#Mann= 3 ,-1 , 0
    4226     .05       0  4977.9    .035       0  5021.9     .05       0
Bank Sta=4977.9,5021.9
XS Rating Curve= 0 ,0
Exp/Cntr=0.3,0.1

Type RM Length L Ch R = 1 ,3308    ,717,717,717
BEGIN DESCRIPTION:
HEADS CREEK TRIB 4 7.0
END DESCRIPTION:
XS GIS Cut Line= 2
      3498113.05     10451625.41      3499636.48     10451443.12
#Sta/Elev= 30
  4587.9  446.06  4662.1  440.91  4744.5  432.31  4749.5  432.19  4818.6  424.08
  4868.9  416.36  4914.2  411.76  4919.3  410.63  4949.5  408.17  4969.7  405.56
  4979.7  404.37  5009.7  402.05    5020  403.95  5040.2  406.15  5100.6  413.62
  5166.4  419.74  5201.3  422.33  5253.8  423.95  5291.9  426.09  5331.1  428.85
  5418.5  436.72  5453.1  437.88  5563.9  439.26  5654.5  439.47  5745.2  441.95
  5785.4  444.47  5916.4  446.46  6027.1  451.72  6087.6  452.54  6122.2  453.93
#Mann= 3 ,-1 , 0
  4587.9     .05       0  4979.7    .035       0  5040.2     .05       0
Bank Sta=4969.7,5040.2
XS Rating Curve= 0 ,0
Exp/Cntr=0.3,0.1

Type RM Length L Ch R = 1 ,2591    ,1069,1069,1069
BEGIN DESCRIPTION:
HEADS CREEK TRIB 4 5.0
END DESCRIPTION:
XS GIS Cut Line= 2
      3498334.36     10452328.54      3499701.58     10452068.12
#Sta/Elev= 30
  4673.9  434.65  4763.2  429.92  4814.1  425.04  4834.5   422.7  4926.1  407.96
  4951.4  404.63  4956.6  403.43  5003.3  400.13  5008.7  401.05  5027.9  401.78
  5048.3  403.67  5055.7  404.97    5089   410.6  5119.5  414.53  5217.4  423.39
  5269.5  426.16  5384.2  429.15  5424.9  428.86  5465.6   430.8  5483.3  430.46
  5567.4  432.57  5587.6  432.35    5659  435.33  5730.3  434.58  5842.3   436.6
    5883  439.33  5910.9  443.03  5923.7  443.98  6015.2  446.05  6065.7  448.13
#Mann= 3 ,-1 , 0
  4673.9     .05       0  4956.6    .035       0  5048.3     .05       0
Bank Sta=4951.4,5055.7
XS Rating Curve= 0 ,0
Exp/Cntr=0.3,0.1

Type RM Length L Ch R = 1 ,1522    ,1056,1056,1056
BEGIN DESCRIPTION:
HEADS CREEK TRIB 4 2.0
END DESCRIPTION:
XS GIS Cut Line= 2
      3498985.37     10452992.62      3500168.69     10452511.49
#Sta/Elev= 30
  4517.5  421.48  4531.8   422.7  4585.3  419.96  4590.7  418.82  4609.4  418.83
  4632.7  417.11  4657.6   413.5  4675.9  410.29  4692.4  408.82  4697.8  407.23
  4721.8  404.83  4809.3  403.95    4828  404.33  4924.2  404.65  4960.1   400.6
  4978.2  400.78  4984.1  399.69  4999.5  394.14  5002.8  394.64  5008.2  398.07
  5013.6  399.63  5021.3  402.79  5025.7  403.32  5085.8  410.52  5096.9  413.21
  5150.9  419.01  5358.9  435.31  5431.1  436.14  5626.6  443.49  5794.9  444.54
#Mann= 7 ,-1 , 0
  4517.5     .05       0  4657.6     .16       0  4809.3     .05       0
    4828     .16       0  4984.1     .07       0  5013.6     .16       0
  5025.7     .05       0
Bank Sta=4984.1,5013.6
XS Rating Curve= 0 ,0
Exp/Cntr=0.3,0.1

Type RM Length L Ch R = 1 ,470     ,0,0,0
BEGIN DESCRIPTION:
HEADS CREEK TRIB 4 2.0
END DESCRIPTION:
XS GIS Cut Line= 3
      3498907.26      10453025.2       3499411.6     10453597.26
      3500558.53     10453032.89
#Sta/Elev= 30
  3442.4  420.02  3514.4  423.87  3557.1  424.38  3641.5  423.62  3734.8  420.27
  3790.5  414.99  3804.7  411.52  3833.1  410.14  4042.7  406.94  4066.5  405.04
  4102.5  405.72  4178.2  403.71  4245.7  402.27  4366.1  399.22  4737.3  398.72
  4882.9  398.13  4927.8  395.93  4972.8  396.36  4978.3  396.36  4995.2   394.5
    4997  390.93  4999.8  390.43    5008  390.93  5023.3  395.14  5045.8  397.31
  5107.6  401.41  5158.1  409.26  5231.1  416.15  5410.8  424.39  5483.3  425.33
#Mann= 9 ,-1 , 0
  3442.4     .05       0  3734.8     .16       0  4042.7      .1       0
  4178.2     .16       0  4245.7      .1       0  4737.3     .05       0
  4972.8     .03       0  5045.8     .16       0  5045.8     .05       0
Bank Sta=4978.3,5045.8
XS Rating Curve= 0 ,0
Exp/Cntr=0.3,0.1

Chan Stop Cuts=-1
Use User Specified Reach Order=0
Composite Channel Slope=5