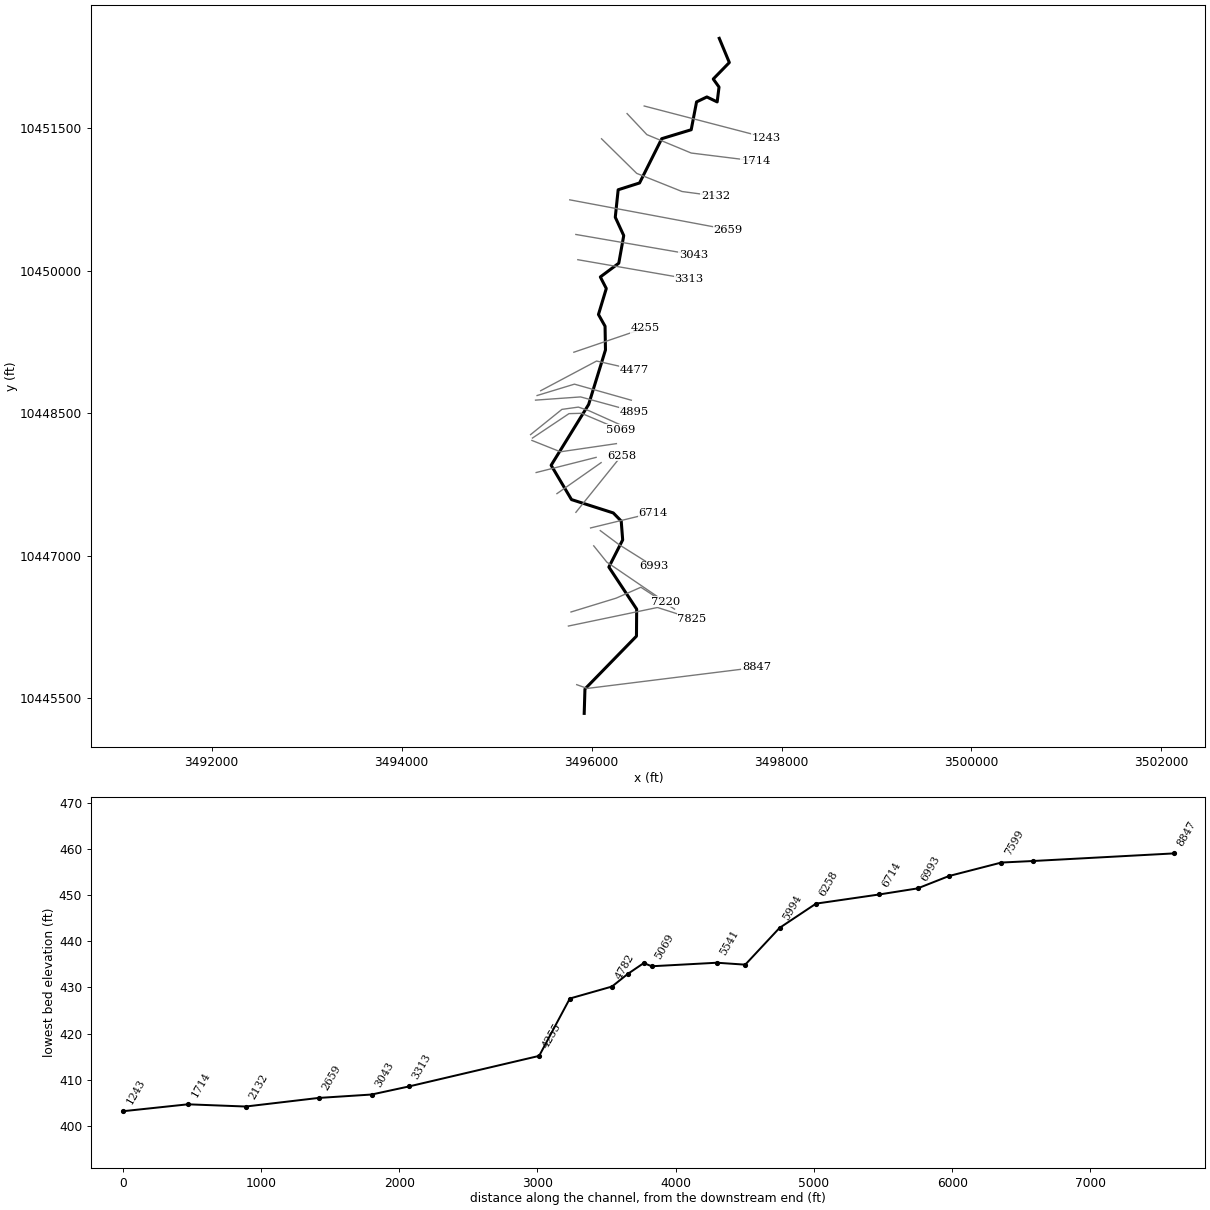
--- HEADS CREEK TRIB 5.prj (project) ---

Proj Title=HEADS CREEK TRIB 5 Base Level Engineering
Current Plan=p01
Default Exp/Contr=0.3,0.1
English Units
Geom File=g01
Flow File=f01
Plan File=p01
Y Axis Title=Elevation
X Axis Title(PF)=Main Channel Distance
X Axis Title(XS)=Station
BEGIN DESCRIPTION:
HEADS CREEK TRIB 5
END DESCRIPTION:
DSS Export Rating Curves= 0
DSS Export Rating Curve Sorted= 0
DSS Export Volume Flow Curves= 0
DXF OffsetX= 0
DXF OffsetY= 0
DXF ScaleX= 1
DXF ScaleY= 10

--- HEADS CREEK TRIB 5.p01 (plan) ---

Plan Title=Multiple Run
Short Identifier=Multiple
Geom File=g01
Flow File=f01
Subcritical Flow
K Sum by GR= 0
Std Step Tol= 0.01
Critical Tol= 0.01
Num of Std Step Trials= 20
Max Error Tol= 0.3
Flow Tol Ratio= 0.001
Split Flow NTrial= 30
Split Flow Tol= 0.02
Split Flow Ratio= 0.02
Log Output Level= 0
Friction Slope Method= 1
Unsteady Friction Slope Method= 2
Unsteady Bridges Friction Slope Method= 1
Parabolic Critical Depth
Global Vel Dist=  1 , 1 , 1
Global Log Level= 0
CheckData=True
Encroach Param= -1, 0, 0, 0
BEGIN DESCRIPTION:
Multiple Run
END DESCRIPTION:

--- HEADS CREEK TRIB 5.f01 (steady flow) ---

Flow Title=Multiple
Program Version=4.10
Number of Profiles= 7
Profile Names=10-year,25-year,50-year,1pct_min,100-year,1pct_plu,500-year
River Rch & RM=HEADS CREEK TRIB,Reach-1         ,8847
     452     594     705     613     828    1120    1139
River Rch & RM=HEADS CREEK TRIB,Reach-1         ,3313
    1099    1521    1871    1678    2269    3068    3330
Boundary for River Rch & Prof#=HEADS CREEK TRIB,Reach-1         , 1
Up Type= 0
Dn Type= 3
Dn Slope=0.005
Boundary for River Rch & Prof#=HEADS CREEK TRIB,Reach-1         , 2
Up Type= 0
Dn Type= 3
Dn Slope=0.005
Boundary for River Rch & Prof#=HEADS CREEK TRIB,Reach-1         , 3
Up Type= 0
Dn Type= 3
Dn Slope=0.005
Boundary for River Rch & Prof#=HEADS CREEK TRIB,Reach-1         , 4
Up Type= 0
Dn Type= 3
Dn Slope=0.005
Boundary for River Rch & Prof#=HEADS CREEK TRIB,Reach-1         , 5
Up Type= 0
Dn Type= 3
Dn Slope=0.005
Boundary for River Rch & Prof#=HEADS CREEK TRIB,Reach-1         , 6
Up Type= 0
Dn Type= 3
Dn Slope=0.005
Boundary for River Rch & Prof#=HEADS CREEK TRIB,Reach-1         , 7
Up Type= 0
Dn Type= 3
Dn Slope=0.005
DSS Import GetInterval= 0
DSS Import GetPeak= 0
DSS Import FillOption= 0

--- HEADS CREEK TRIB 5.g01 (geometry) ---

Geom Title=Existing Conditions
Program Version=4.10

River Reach=HEADS CREEK TRIB,Reach-1
Reach XY= 30
      3495922.36     10445341.57      3495930.22     10445598.27
      3496472.63     10446154.59       3496474.8     10446438.88
        3496182.     10446881.76      3496327.48      10447167.6
      3496312.03     10447365.86      3496228.52     10447451.46
      3495788.42     10447592.08      3495574.19      10447953.2
      3495968.89     10448592.97      3496146.24     10449167.18
       3496141.9     10449416.74      3496072.46     10449540.44
      3496154.92     10449813.88      3496092.11     10449935.62
      3496286.43     10450080.37      3496338.51     10450371.17
      3496249.54     10450564.31      3496279.92     10450853.37
      3496505.18     10450924.99      3496738.91     10451391.12
      3497049.02     10451485.32      3497105.44     10451778.29
      3497213.95     10451830.37      3497322.46     10451778.29
      3497341.99     10451934.54      3497281.22     10452019.17
      3497450.49     10452192.78      3497344.43     10452447.45

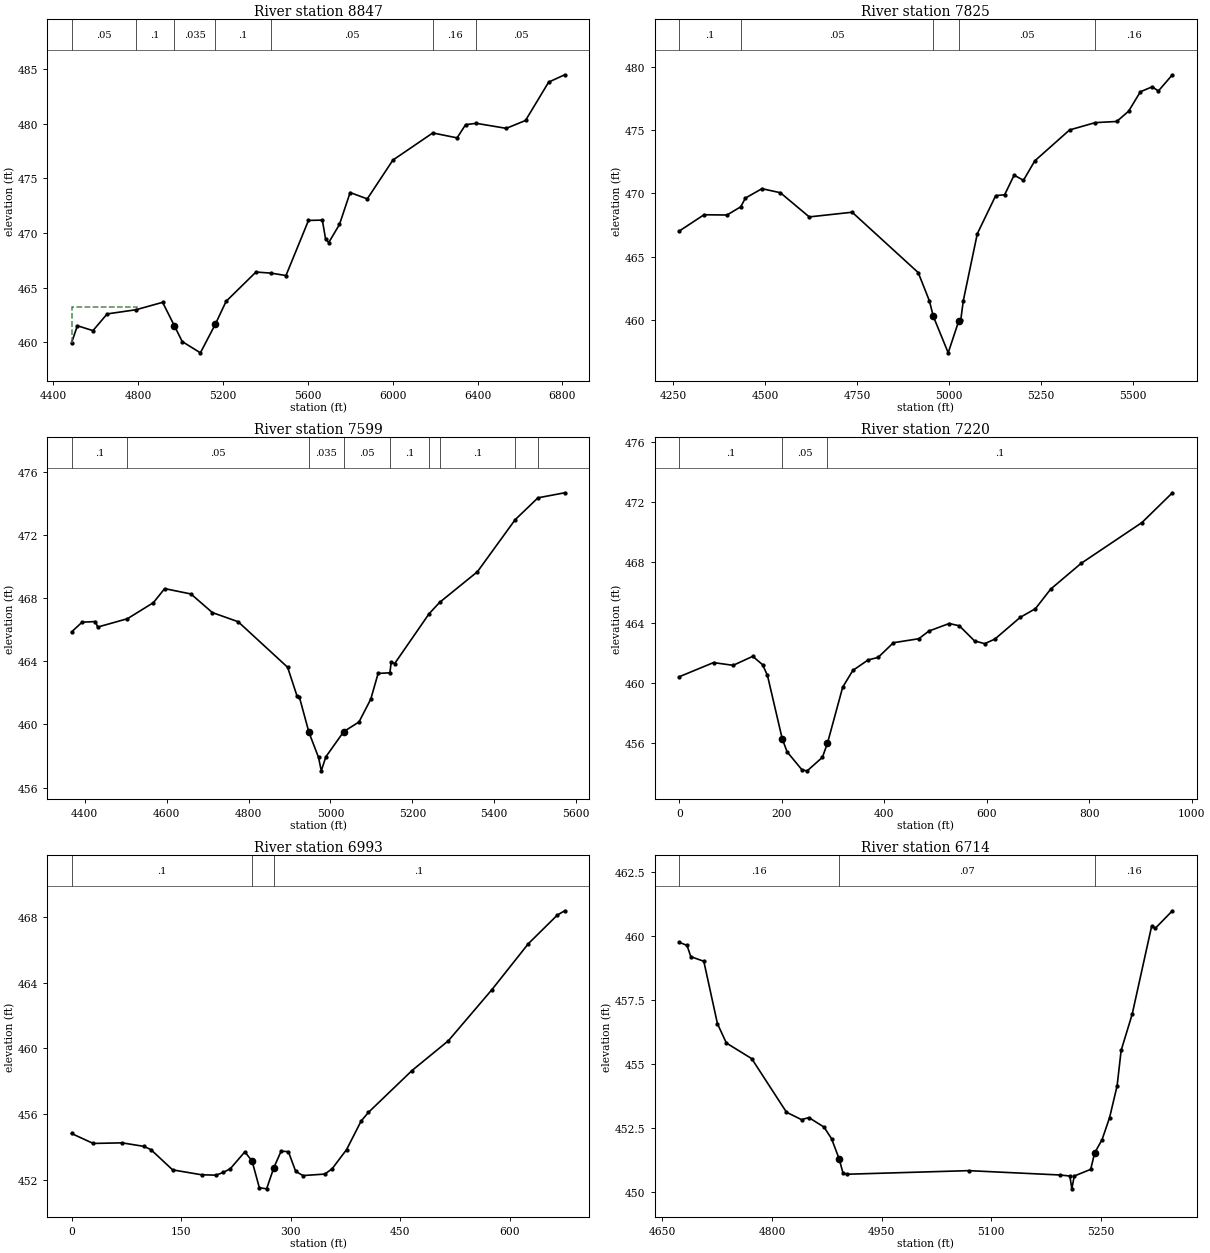
Type RM Length L Ch R = 1 ,8847    ,1022,1022,1022
BEGIN DESCRIPTION:
HEADS CREEK TRIB 5 11.0
END DESCRIPTION:
XS GIS Cut Line= 3
     3495843.457    10445643.812      3495954.64     10445604.16
      3497735.33     10445825.57
#Sta/Elev= 30
  4486.6  459.95  4514.3  461.52  4587.6  461.07  4654.5   462.6  4790.3  462.98
  4915.9  463.66  4970.8  461.53  5008.3  460.07  5093.8  459.04  5164.6  461.67
    5215  463.75  5355.7  466.43  5426.6  466.33  5497.1  466.11  5603.2  471.15
  5668.4  471.18    5684  469.42  5698.7  469.13  5749.1  470.78  5799.4   473.7
  5880.1  473.12    6001  476.67  6188.8  479.15  6303.3   478.7  6343.6  479.91
  6393.7  480.03  6535.1  479.57  6625.8  480.29  6734.8   483.8  6810.4  484.47
#Mann= 7 ,-1 , 0
  4486.6     .05       0  4790.3      .1       0  4970.8    .035       0
  5164.6      .1       0  5426.6     .05       0  6188.8     .16       0
  6393.7     .05       0
#XS Ineff= 2 , 0
         4796.02  463.19
Permanent Ineff=
       F       F
Bank Sta=4970.8,5164.6
XS Rating Curve= 0 ,0
Exp/Cntr=0.3,0.1

Type RM Length L Ch R = 1 ,7825    ,226,226,226
BEGIN DESCRIPTION:
Mapping XS aa00ea05
END DESCRIPTION:
XS GIS Cut Line= 3
      3495756.07     10446260.92      3496693.57     10446456.23
      3497058.38      10446339.7
#Sta/Elev= 30
  4266.5  467.01    4334   468.3  4396.5  468.28  4433.8  468.93  4446.5  469.62
  4491.5  470.36  4541.5  470.04    4620  468.13  4736.6   468.5  4916.2  463.73
  4946.8  461.48    4957  460.29  4997.7  457.39  5026.7  459.94  5031.8  459.98
  5038.8  461.52  5076.8   466.8  5126.8  469.81  5151.1  469.88  5176.9  471.43
  5202.2  471.02  5233.1  472.56  5327.6     475  5397.4  475.58  5455.8  475.67
    5488  476.48  5520.2  478.02  5552.3  478.41    5569  478.08  5607.1  479.36
#Mann= 5 ,-1 , 0
  4266.5      .1       0  4433.8     .05       0    4957    .035       0
  5026.7     .05       0  5397.4     .16       0
Bank Sta=4957,5026.7
XS Rating Curve= 0 ,0
Exp/Cntr=0.3,0.1

Type RM Length L Ch R = 1 ,7599    ,379,379,379
BEGIN DESCRIPTION:
Mapping XS b35650cb
END DESCRIPTION:
XS GIS Cut Line= 4
      3495783.26     10446408.83      3496258.97     10446554.67
      3496519.38     10446669.25      3496873.51     10446438.95
#Sta/Elev= 30
  4367.6  465.87  4393.4  466.49  4426.1  466.53  4431.4  466.18  4504.1  466.71
  4567.6  467.73  4595.1  468.62  4659.3  468.28  4711.6   467.1  4774.5  466.52
  4895.4  463.63  4918.7  461.78  4924.2  461.73  4947.5   459.5  4970.9  457.91
  4977.6  457.06  4988.8  457.95  5032.5  459.55  5069.7  460.16  5098.5  461.61
  5116.4  463.24  5145.2  463.28  5148.4  463.97  5156.7  463.86    5241  467.03
  5266.8  467.75  5358.9  469.69    5451  472.99  5506.8  474.38  5572.1   474.7
#Mann= 9 ,-1 , 0
  4367.6      .1       0  4504.1     .05       0  4947.5    .035       0
  5032.5     .05       0  5145.2      .1       0    5241     .16       0
  5266.8      .1       0    5451     .05       0  5506.8     .16       0
Bank Sta=4947.5,5032.5
XS Rating Curve= 0 ,0
Exp/Cntr=0.3,0.1

Type RM Length L Ch R = 1 ,7220    ,227,227,227
XS GIS Cut Line= 3
     3496022.681    10447105.164     3496160.354    10446933.998
      3496774.59    10446515.638
#Sta/Elev= 30
       0460.395366.97692461.3373105.2495461.1554 143.522461.7527162.6582461.1991
172.2264460.4843200.9308456.2882210.4989455.4085239.8633454.1978249.7614454.1423
279.4559455.0401 289.354 455.985319.0484459.7056338.8447460.8162368.5391461.5106
388.3354461.6848418.0298462.6583467.5205462.9236487.3168463.4343526.9093463.9356
546.7056463.7821   576.4462.7771596.1963462.5963615.9926 462.899665.4833464.3451
695.1777464.9212724.8721466.2213784.2609467.9322903.0386470.6466962.4274472.6252
#Mann= 3 , 0 , 0
       0      .1       0200.9308     .05       0 289.354      .1       0
Bank Sta=200.9308,289.354
XS Rating Curve= 0 ,0
Exp/Cntr=0.3,0.1

Type RM Length L Ch R = 1 ,6993    ,279,279,279
XS GIS Cut Line= 3
     3496091.836     10447265.32     3496289.695    10447117.461
     3496654.538    10446888.468
#Sta/Elev= 30
       0454.825229.67097454.220469.23228454.255998.90325454.0441108.7936453.8426
138.4646 452.613178.0258452.3167197.8065452.2922207.6968452.4545217.5871452.6895
237.3678453.7091247.2581453.1498257.2149451.5296267.1716 451.461277.1284452.7518
287.0851453.7541297.0418453.7186306.9986452.5233316.9553452.2671346.8256452.3577
356.7823452.6746376.6958453.8468396.6093455.5811 406.566456.1046466.3065458.6513
516.0902460.4613575.8307463.5725625.6144466.3604665.4413468.1042675.3981  468.36
#Mann= 3 , 0 , 0
       0      .1       0247.2581     .05       0277.1284      .1       0
Bank Sta=247.2581,277.1284
XS Rating Curve= 0 ,0
Exp/Cntr=0.3,0.1

Type RM Length L Ch R = 1 ,6714    ,456,456,456
BEGIN DESCRIPTION:
Mapping XS 65143c8b
END DESCRIPTION:
XS GIS Cut Line= 2
      3495989.38     10447293.45      3496645.63     10447453.17
#Sta/Elev= 30
  4672.9  459.76  4683.6  459.64  4688.8   459.2  4706.6  459.02  4725.3  456.58
  4737.5  455.83  4772.2  455.22  4819.8  453.13  4840.4  452.84  4850.5  452.92
  4871.2  452.55  4881.5   452.1  4891.8  451.32  4897.4  450.74  4902.5  450.71
  5069.5  450.85  5194.6  450.68  5207.9  450.64  5210.6  450.14  5213.9  450.64
  5236.4   450.9  5241.8  451.54    5252  452.06  5262.3  452.92  5272.6  454.16
  5278.1  455.54  5293.2  456.95  5319.8  460.38    5325  460.31  5348.3  460.99
#Mann= 3 ,-1 , 0
  4672.9     .16       0  4891.8     .07       0  5241.8     .16       0
Bank Sta=4891.8,5241.8
XS Rating Curve= 0 ,0
Exp/Cntr=0.3,0.1

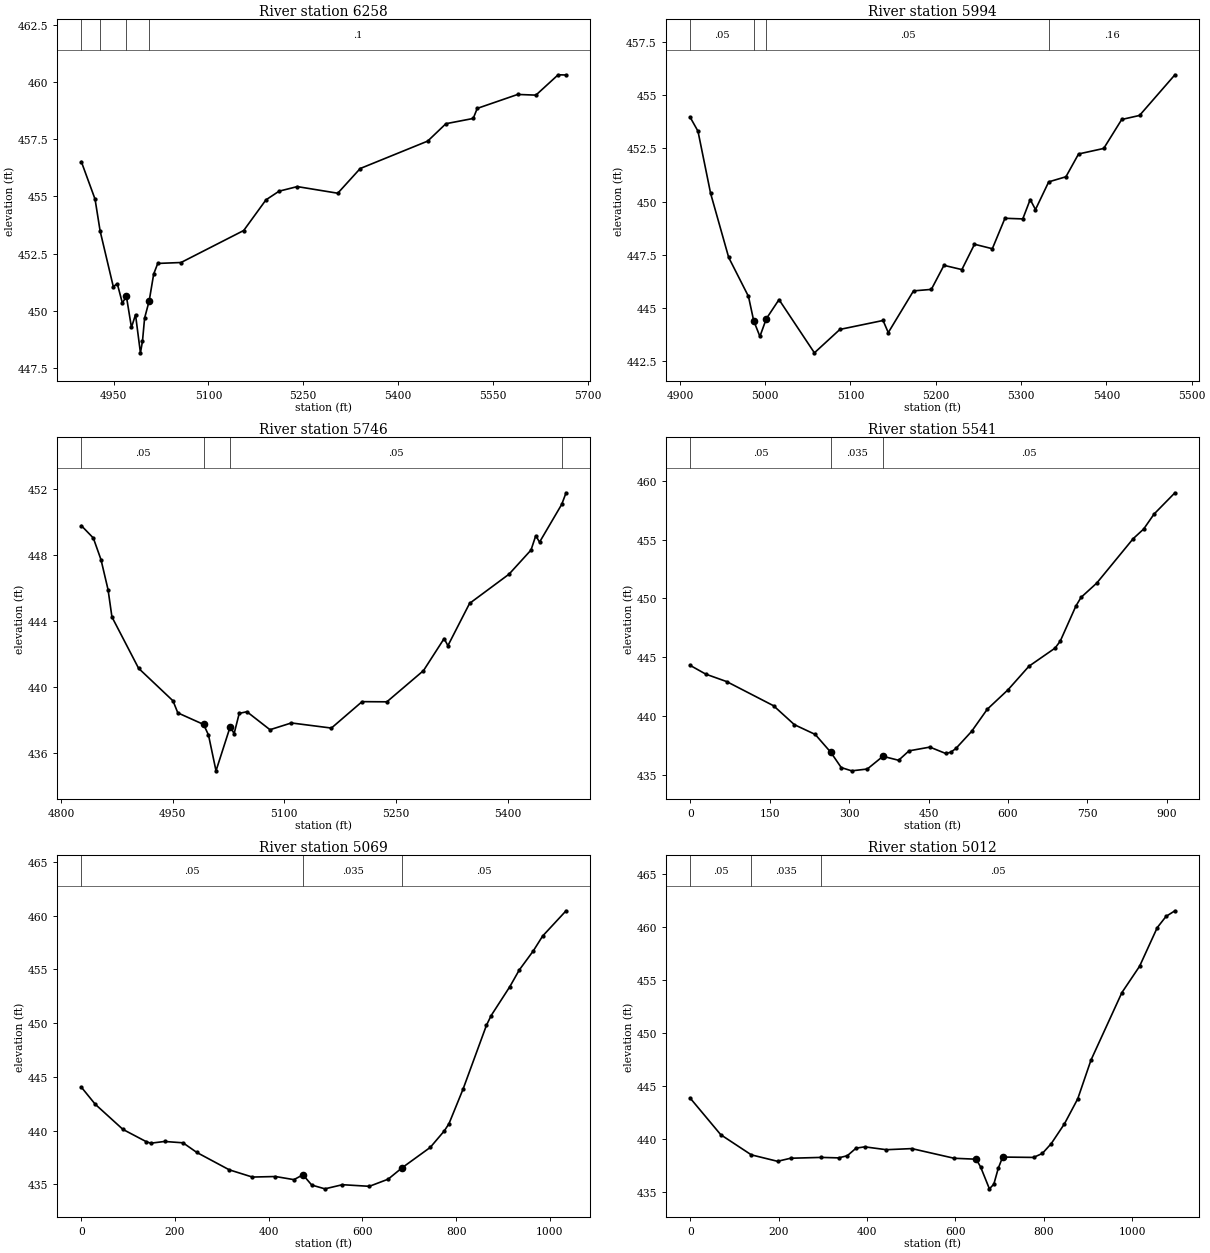
Type RM Length L Ch R = 1 ,6258    ,264,264,264
BEGIN DESCRIPTION:
HEADS CREEK TRIB 5 10.0
END DESCRIPTION:
XS GIS Cut Line= 2
      3495834.86     10447457.97      3496315.76     10448055.36
#Sta/Elev= 30
    4899  456.52  4920.7  454.88  4928.7  453.49  4949.5  451.06  4955.9  451.18
  4963.9  450.34  4970.3  450.63  4978.3  449.27  4984.7  449.83  4992.5  448.16
  4995.7  448.66  4999.1  449.68  5006.4  450.44  5013.5  451.61  5019.9  452.07
  5056.7  452.11  5155.9  453.51  5191.1  454.85  5211.9  455.23  5240.7  455.43
  5304.7  455.14  5340.2  456.22    5447  457.42  5475.8  458.18    5519  458.41
  5525.4  458.85  5589.4  459.46  5618.2  459.43  5653.4  460.32  5665.9  460.31
#Mann= 4 ,-1 , 0
    4899     .05       0  4928.7      .1       0  4970.3     .05       0
  5006.4      .1       0
Bank Sta=4970.3,5006.4
XS Rating Curve= 0 ,0
Exp/Cntr=0.3,0.1

Type RM Length L Ch R = 1 ,5994    ,248,248,248
BEGIN DESCRIPTION:
Mapping XS 5fa4759e
END DESCRIPTION:
XS GIS Cut Line= 2
      3495635.22     10447654.58      3496100.46     10447980.94
#Sta/Elev= 30
  4912.1  453.96  4921.2  453.31    4936  450.39  4957.2  447.38  4980.4  445.55
  4986.5  444.41  4993.8  443.67  5001.3   444.5  5016.2   445.4  5057.7   442.9
  5087.6     444  5138.2  444.42  5144.3  443.85  5173.9  445.81  5194.8  445.88
  5209.6  447.01  5230.6  446.81  5245.4     448  5266.3  447.79  5281.1  449.22
    5302  449.19  5310.7   450.1  5316.9  449.63  5332.4  450.93  5352.6  451.17
  5367.4  452.24  5396.9   452.5    5418  453.86  5438.9  454.05  5480.4  455.96
#Mann= 4 ,-1 , 0
  4912.1     .05       0  4986.5    .035       0  5001.3     .05       0
  5332.4     .16       0
Bank Sta=4986.5,5001.3
XS Rating Curve= 0 ,0
Exp/Cntr=0.3,0.1

Type RM Length L Ch R = 1 ,5746    ,205,205,205
BEGIN DESCRIPTION:
Mapping XS dcd6e6c0
END DESCRIPTION:
XS GIS Cut Line= 2
      3495416.48     10447876.79      3496047.73     10448036.33
#Sta/Elev= 30
  4827.3  449.79  4843.4  449.04  4853.7  447.73  4863.2  445.91  4868.4  444.26
  4904.2  441.15  4950.4  439.18  4956.9  438.45  4991.5  437.75  4998.1  437.11
  5008.2  434.94  5027.3  437.62  5032.5  437.19  5039.4  438.42  5049.7  438.52
  5080.7  437.43  5109.4  437.84  5163.2  437.53  5204.4  439.13  5237.7  439.12
  5286.9  441.01  5314.6  442.95  5319.7  442.52  5348.8  445.08  5401.8  446.85
  5431.3  448.31  5437.7  449.18  5442.8  448.79  5472.6  451.08  5478.4  451.78
#Mann= 4 ,-1 , 0
  4827.3     .05       0  4991.5    .035       0  5027.3     .05       0
  5472.6     .16       0
Bank Sta=4991.5,5027.3
XS Rating Curve= 0 ,0
Exp/Cntr=0.3,0.1

Type RM Length L Ch R = 1 ,5541    ,472,472,472
XS GIS Cut Line= 3
     3495371.732    10448214.832     3495671.521    10448095.148
     3496261.365    10448181.086
#Sta/Elev= 30
       0444.309529.49848443.567968.82979442.9377157.3252440.8863196.6565439.2788
235.9879438.4497265.4863436.9265 285.152435.6352304.8177435.3592334.3269435.5136
363.8577436.5945393.3884436.2557413.0756 437.056  452.45 437.375481.9807 436.839
491.8243436.9345501.6679437.2616531.1987438.7068560.7294440.5855600.1038442.2473
639.4781444.2409688.6961445.7763698.5397446.3688728.0704449.3478 737.914450.0887
767.4448 451.299836.3499455.0759856.0371455.8886875.7243457.1632915.0986458.9684
#Mann= 3 , 0 , 0
       0     .05       0265.4863    .035       0363.8577     .05       0
Bank Sta=265.4863,363.8577
XS Rating Curve= 0 ,0
Exp/Cntr=0.3,0.1

Type RM Length L Ch R = 1 ,5069    ,57,57,57
XS GIS Cut Line= 4
     3495377.251    10448239.679     3495762.233    10448496.895
     3495893.744    10448500.367     3496304.117    10448326.268
#Sta/Elev= 30
       0444.051129.59757442.464988.79271440.1223 138.122438.9917147.9879438.8383
177.5854     439217.0488438.8752246.6464437.9754315.7074 436.364365.0367435.6904
 414.366435.7398453.8294435.4499 473.063435.9016491.7985434.9467519.9016434.5944
557.3726434.9788614.8369434.8295654.8236435.4906684.8137436.5567744.7938438.4479
774.7838439.9828784.7805 440.654814.7706443.8609 864.754 449.804874.7507450.7067
914.7374453.4029934.7308454.9438964.7208456.7222984.7142458.10651034.698460.4561
#Mann= 3 ,-1 , 0
       0     .05       0 473.063    .035       0684.8137     .05       0
Bank Sta=473.063,684.8137
XS Rating Curve= 0 ,0
Exp/Cntr=0.3,0.1

Type RM Length L Ch R = 1 ,5012    ,117,117,117
XS GIS Cut Line= 5
     3495357.676    10448275.921      3495687.58      10448541.6
     3495860.649    10448565.699     3495971.285    10448528.162
     3496321.261    10448371.027
#Sta/Elev= 30
       0443.846869.14301440.3964 138.286438.4974197.5514437.8888227.1842438.1778
296.3271438.2562335.8375438.2122355.5926438.4158375.3477439.1311395.1029439.2524
 443.914438.9827501.4492439.0875597.3412438.1744647.2098438.0873657.1835437.3556
 677.131435.2904687.1047435.7268697.0784437.2192707.0522438.2892777.0208438.2545
 797.019438.6335817.0173439.5545847.0148441.4303877.0122443.7836907.0096447.4405
977.0036453.8109    1017456.29381056.997459.94151076.995461.00171096.993461.5278
#Mann= 3 ,-1 , 0
       0     .05       0 138.286    .035       0296.3271     .05       0
#XS Ineff= 2 , 0
          377.05  439.13
Permanent Ineff=
       F       F
Bank Sta=647.2098,707.0522
XS Rating Curve= 0 ,0
Exp/Cntr=0.3,0.1

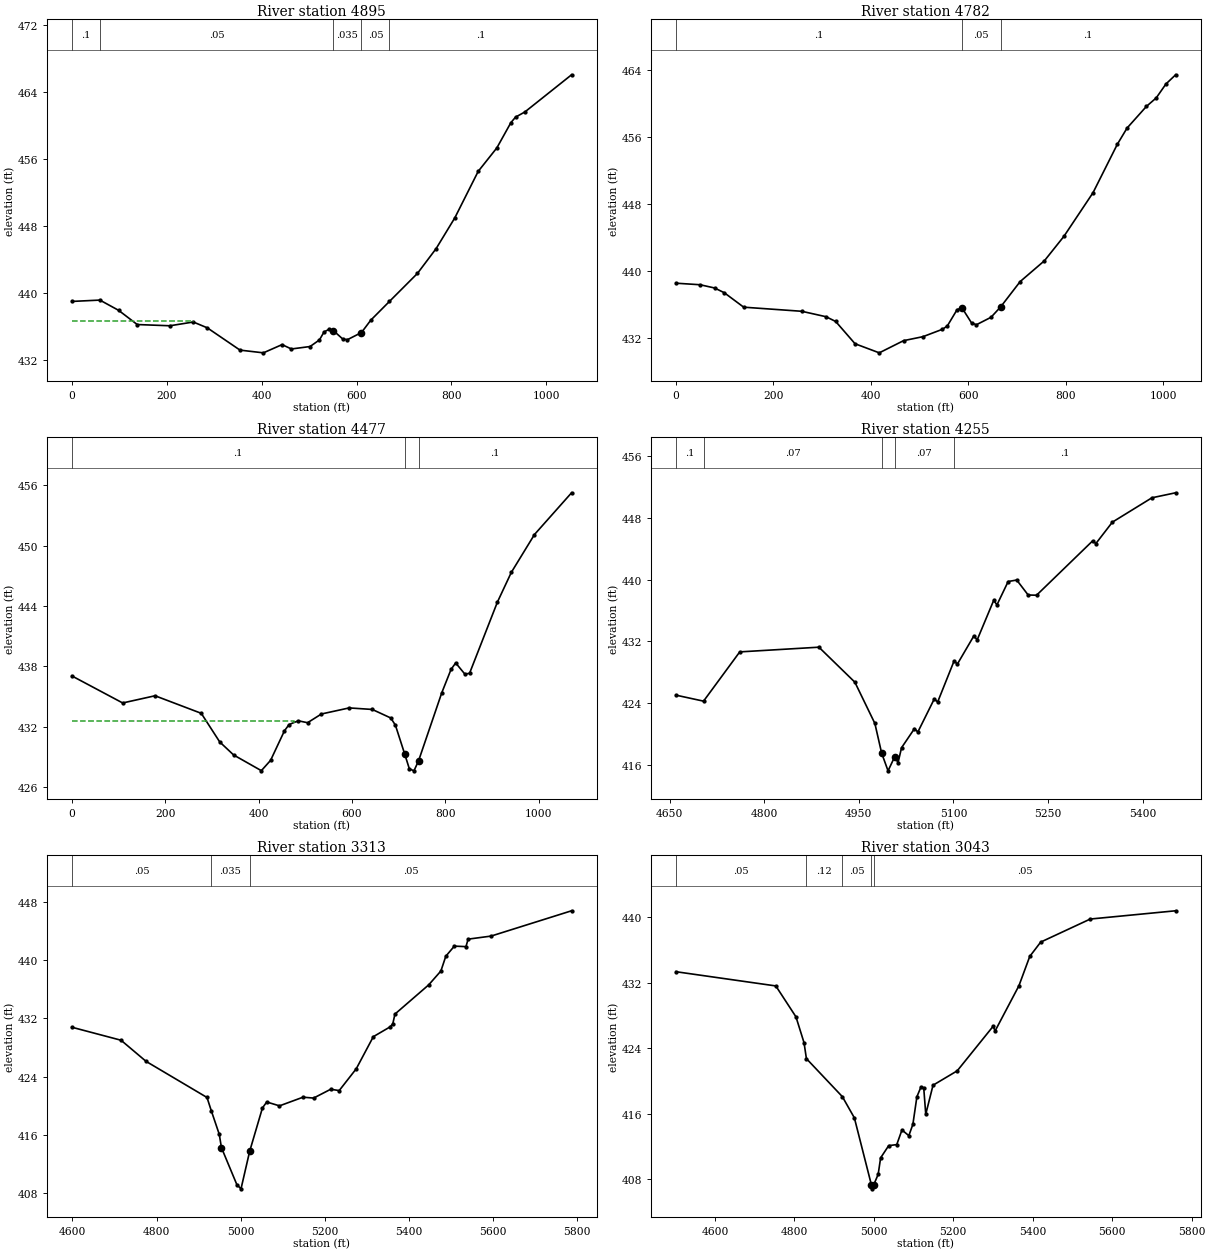
Type RM Length L Ch R = 1 ,4895    ,113,113,113
XS GIS Cut Line= 3
     3495409.803    10448638.985     3495884.629    10448672.839
3496445.3927645410448519.1930645
#Sta/Elev= 30
       0439.041459.07104439.201498.45174437.9843137.8324 436.285206.7487436.1389
255.9745 436.588  285.51435.8909354.4263433.2346403.6521432.9101443.0328433.8915
462.7232433.3704502.0901433.6637521.7713434.4493531.6119435.4087541.4525435.6976
551.2931435.5567570.9742434.5576580.8149434.4806610.3366435.3275630.0178436.8061
669.3802 439.044728.4237442.3884767.7861445.3486807.1484449.0123856.3514454.5522
895.7137457.3544925.2355460.3611935.0761461.0226954.7573461.64011053.163 466.074
#Mann= 5 ,-1 , 0
       0      .1       059.07104     .05       0551.2931    .035       0
610.3366     .05       0669.3802      .1       0
#XS Ineff= 2 , 0
          256.36  436.66
Permanent Ineff=
       F       F
#Block Obstruct= 2 , 0
          543.45  434.48
Bank Sta=551.2931,610.3366
XS Rating Curve= 0 ,0
Exp/Cntr=0.3,0.1

Type RM Length L Ch R = 1 ,4782    ,305,305,305
XS GIS Cut Line= 3
     3495426.218    10448687.464     3495819.447    10448807.256
     3496418.405    10448637.985
#Sta/Elev= 30
       0438.527849.67509438.342479.48014437.953899.35017437.3839139.0902435.6597
258.3105435.1693307.9855434.5203327.8556433.9524367.5956 431.288417.3055 430.202
467.1544431.6585507.0335432.1361546.9126433.0182556.8824433.4118 576.822435.3477
586.7917435.6015606.7313 433.771 616.701433.5616646.6104434.4516666.5499435.7084
706.4291438.7218 756.278441.2143 796.157444.1249855.9757449.3499905.8246455.1357
925.7642 457.072965.6433 459.669985.5829460.67361005.522462.33951025.462463.4426
#Mann= 3 , 0 , 0
       0      .1       0586.7917     .05       0666.5499      .1       0
#Block Obstruct= 2 , 0
          582.95  433.46
Bank Sta=586.7917,666.5499
XS Rating Curve= 0 ,0
Exp/Cntr=0.3,0.1

Type RM Length L Ch R = 1 ,4477    ,222,222,222
XS GIS Cut Line= 3
      3495464.05    10448738.066     3496052.592    10449050.566
3496450.16188096 10448960.289027
#Sta/Elev= 30
       0437.0439108.9248434.3532178.2405435.0695 277.263433.3242 316.872430.4773
346.5787429.1853405.9922427.6239425.7968428.6484455.5035431.5869465.4058 432.208
485.2102432.5808505.0147432.3909534.7215433.2577 594.135433.8614643.6462433.7096
683.3127432.8598693.2438 432.142713.1058429.2804723.0368427.8131732.9678427.6067
742.8988428.6134792.5538 435.367812.4158437.6902822.3469438.3321842.2089437.2131
852.1399437.3093911.7259444.3796941.5189447.3322 991.174451.09891070.622455.2469
#Mann= 3 , 0 , 0
       0      .1       0713.1058     .05       0742.8988      .1       0
#XS Ineff= 2 , 0
          475.91  432.58
Permanent Ineff=
       F       F
Bank Sta=713.1058,742.8988
XS Rating Curve= 0 ,0
Exp/Cntr=0.3,0.1

Type RM Length L Ch R = 1 ,4255    ,942,942,942
BEGIN DESCRIPTION:
HEADS CREEK TRIB 5 8.0
END DESCRIPTION:
XS GIS Cut Line= 2
       3495813.5     10449143.29      3496563.47     10449398.48
#Sta/Elev= 30
    4660     425  4703.8  424.22  4761.2  430.61  4886.7  431.22  4943.7  426.68
  4975.4  421.33  4986.1  417.49  4996.3  415.18  5006.9  417.02  5012.1  416.23
  5017.7  418.18  5038.2  420.66  5043.5  420.21  5069.6  424.51  5074.9   424.1
    5101  429.44  5106.2  429.03  5132.3  432.68  5137.6  432.17  5163.7  437.28
    5169  436.72  5186.7  439.74  5200.3  439.93  5218.4  437.99  5231.7  437.96
  5320.5     445  5325.8  444.67  5351.9  447.44  5414.6   450.6  5452.2  451.25
#Mann= 5 ,-1 , 0
    4660      .1       0  4703.8     .07       0  4986.1     .05       0
  5006.9     .07       0    5101      .1       0
Bank Sta=4986.1,5006.9
XS Rating Curve= 0 ,0
Exp/Cntr=0.3,0.1

Type RM Length L Ch R = 1 ,3313    ,270,270,270
BEGIN DESCRIPTION:
HEADS CREEK TRIB 5 7.0
END DESCRIPTION:
XS GIS Cut Line= 2
      3495855.17     10450117.24        3497027.     10449914.13
#Sta/Elev= 30
  4598.5  430.78  4715.6  428.99  4775.3  426.08  4920.2  421.12  4930.3  419.31
  4949.4  416.05  4954.5  414.23  4991.2  409.14  5001.1  408.56  5021.7  413.72
  5052.1  419.68  5062.3   420.5  5092.7  419.97  5148.7  421.16  5173.9  421.04
  5214.5  422.25  5234.8  422.07  5275.4  425.07    5316  429.48  5356.6  430.85
  5362.4  431.27  5367.5  432.59  5447.9  436.61  5476.8  438.51  5488.5  440.54
  5508.8  441.93  5536.5  441.86  5541.6  442.89  5596.2  443.31  5787.8  446.79
#Mann= 3 ,-1 , 0
  4598.5     .05       0  4930.3    .035       0  5021.7     .05       0
Bank Sta=4954.5,5021.7
XS Rating Curve= 0 ,0
Exp/Cntr=0.3,0.1

Type RM Length L Ch R = 1 ,3043    ,384,384,384
BEGIN DESCRIPTION:
HEADS CREEK TRIB 5 6.0
END DESCRIPTION:
XS GIS Cut Line= 2
       3495834.3     10450382.87      3497073.94     10450169.32
#Sta/Elev= 30
  4501.8  433.36  4753.3  431.62    4804  427.84  4824.3  424.68  4830.3  422.73
  4920.8  418.08    4951  415.49  4993.8  407.31  4996.5  406.81  4999.8  407.31
  5010.9  408.58  5017.1   410.6  5037.4  412.09  5057.7  412.22  5070.8  414.01
  5088.1  413.31  5098.3   414.7  5108.4  418.07  5118.6  419.26  5125.6  419.16
  5130.7  415.93    5149  419.48  5209.9  421.24  5300.2  426.68  5305.3  426.12
  5365.2  431.64  5392.5  435.23    5420  436.98  5544.8   439.8  5759.7  440.81
#Mann= 5 ,-1 , 0
  4501.8     .05       0  4830.3     .12       0  4920.8     .05       0
  4993.8     .04       0  4999.8     .05       0
Bank Sta=4993.8,4999.8
XS Rating Curve= 0 ,0
Exp/Cntr=0.3,0.1

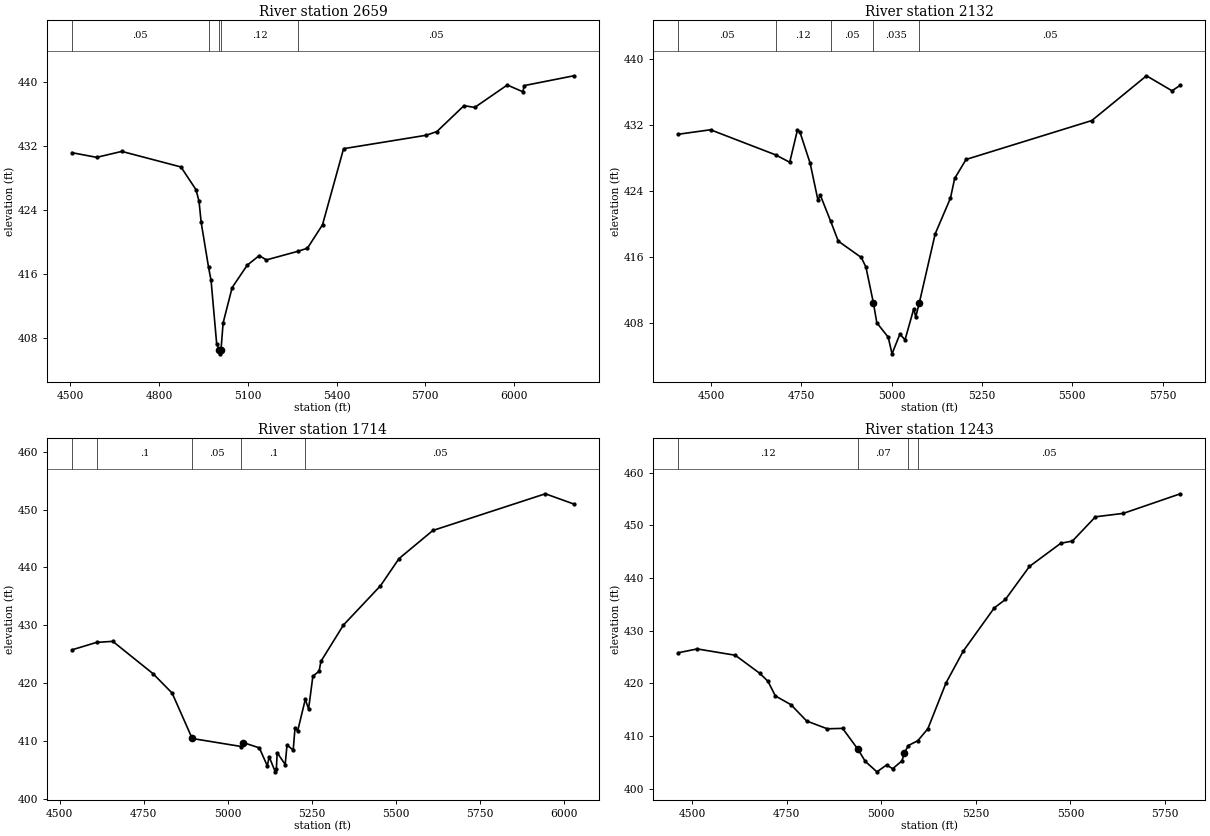
Type RM Length L Ch R = 1 ,2659    ,527,527,527
BEGIN DESCRIPTION:
HEADS CREEK TRIB 5 5.0
END DESCRIPTION:
XS GIS Cut Line= 2
      3495770.11     10450747.45      3497436.76     10450434.95
#Sta/Elev= 30
  4506.2  431.15  4589.6  430.57  4674.7  431.31  4874.5  429.37  4925.4  426.53
  4935.6  425.08  4942.7  422.48  4967.8  416.84  4976.2  415.23  4995.2   407.3
  5003.8  406.57  5006.5  406.07  5009.8  406.57  5016.9  409.92  5047.5  414.34
  5098.3  417.12    5139  418.32  5163.1  417.78    5270  418.86  5301.8  419.24
  5352.7  422.16  5423.9  431.65    5704  433.33  5739.3  433.79  5830.9  437.02
  5866.8  436.79    5977  439.59  6029.3  438.75  6034.7  439.52  6201.9  440.74
#Mann= 5 ,-1 , 0
  4506.2     .05       0  4967.8     .12       0  5003.8     .07       0
  5009.8     .12       0    5270     .05       0
Bank Sta=5003.8,5009.8
XS Rating Curve= 0 ,0
Exp/Cntr=0.3,0.1

Type RM Length L Ch R = 1 ,2132    ,418,418,418
BEGIN DESCRIPTION:
Mapping XS 968ee9c5
END DESCRIPTION:
XS GIS Cut Line= 4
      3496104.91     10451390.04      3496475.19     10451025.92
      3496952.62     10450834.95      3497304.88     10450787.97
#Sta/Elev= 30
    4410  430.85  4498.8  431.39  4678.8  428.35    4718  427.45  4739.3  431.35
  4746.3  431.11  4774.6  427.32  4795.8  422.92  4802.9  423.43  4831.1  420.32
  4852.4  417.88    4916   415.9  4928.8  414.75  4949.5  410.41    4959  407.98
  4990.6  406.23  5001.1  404.21  5022.9   406.6  5037.1  405.91  5061.3  409.68
  5066.7  408.67  5076.8  410.43  5120.6  418.77  5162.9  423.11  5174.4  425.48
    5206  427.79    5554  432.51  5705.3  437.94  5775.9  436.12  5798.9  436.79
#Mann= 5 ,-1 , 0
    4410     .05       0  4678.8     .12       0  4831.1     .05       0
  4949.5    .035       0  5076.8     .05       0
Bank Sta=4949.5,5076.8
XS Rating Curve= 0 ,0
Exp/Cntr=0.3,0.1

Type RM Length L Ch R = 1 ,1714    ,471,471,471
BEGIN DESCRIPTION:
HEADS CREEK TRIB 5 1.0
END DESCRIPTION:
XS GIS Cut Line= 4
      3496373.87     10451655.15      3496582.21      10451433.8
      3497048.74     10451240.14      3497728.73     10451155.88
#Sta/Elev= 30
  4536.5  425.76  4609.9  427.05    4658  427.23  4778.2  421.63  4834.8  418.29
  4894.5  410.45  5041.2  409.06  5046.6  409.74  5094.4  408.83  5118.2  405.71
  5123.6   407.3  5141.8  404.69  5145.1  405.19  5147.5     408  5171.4  405.95
  5176.8  409.34  5195.2  408.44  5200.7  412.33  5208.5  411.75  5231.3  417.23
    5241  415.53  5253.8  421.21  5272.3  422.07  5277.7  423.77  5344.7  430.04
  5455.1  436.83  5510.2  441.52    5611  446.38  5945.9  452.72  6030.8  450.95
#Mann= 5 ,-1 , 0
  4536.5     .16       0  4609.9      .1       0  4894.5     .05       0
  5041.2      .1       0  5231.3     .05       0
Bank Sta=4894.5,5046.6
XS Rating Curve= 0 ,0
Exp/Cntr=0.3,0.1

Type RM Length L Ch R = 1 ,1243    ,0,0,0
BEGIN DESCRIPTION:
HEADS CREEK TRIB 5 1.1
END DESCRIPTION:
XS GIS Cut Line= 2
      3496554.07     10451735.12      3497837.94     10451401.14
#Sta/Elev= 30
    4464   425.8  4513.6  426.52  4614.3  425.32    4679  421.89  4700.5  420.39
  4720.3   417.6  4761.6  415.93  4802.9  412.84  4857.5  411.36    4898  411.44
  4938.5  407.47  4957.9  405.17  4988.7  403.19  5014.4   404.5  5030.3  403.78
  5054.9  405.28  5061.3  406.78  5071.6  408.18  5096.8   409.1  5123.3  411.37
  5171.3  420.07    5217  426.12  5298.9  434.31  5328.3  435.91  5391.9  442.18
  5474.6  446.57  5505.6  447.01  5566.3   451.6  5639.9  452.25  5790.6  455.97
#Mann= 4 ,-1 , 0
    4464     .12       0  4938.5     .07       0  5071.6     .12       0
  5096.8     .05       0
Bank Sta=4938.5,5061.3
XS Rating Curve= 0 ,0
Exp/Cntr=0.3,0.1
Stream Node=HEADS CREEK TRIB,Reach-1         , 0 , 0 ,Upstream end
Stream Node=HEADS CREEK TRIB,Reach-1         , 0 , 1 ,Downstream end

Chan Stop Cuts=-1
Use User Specified Reach Order=0
Composite Channel Slope=5