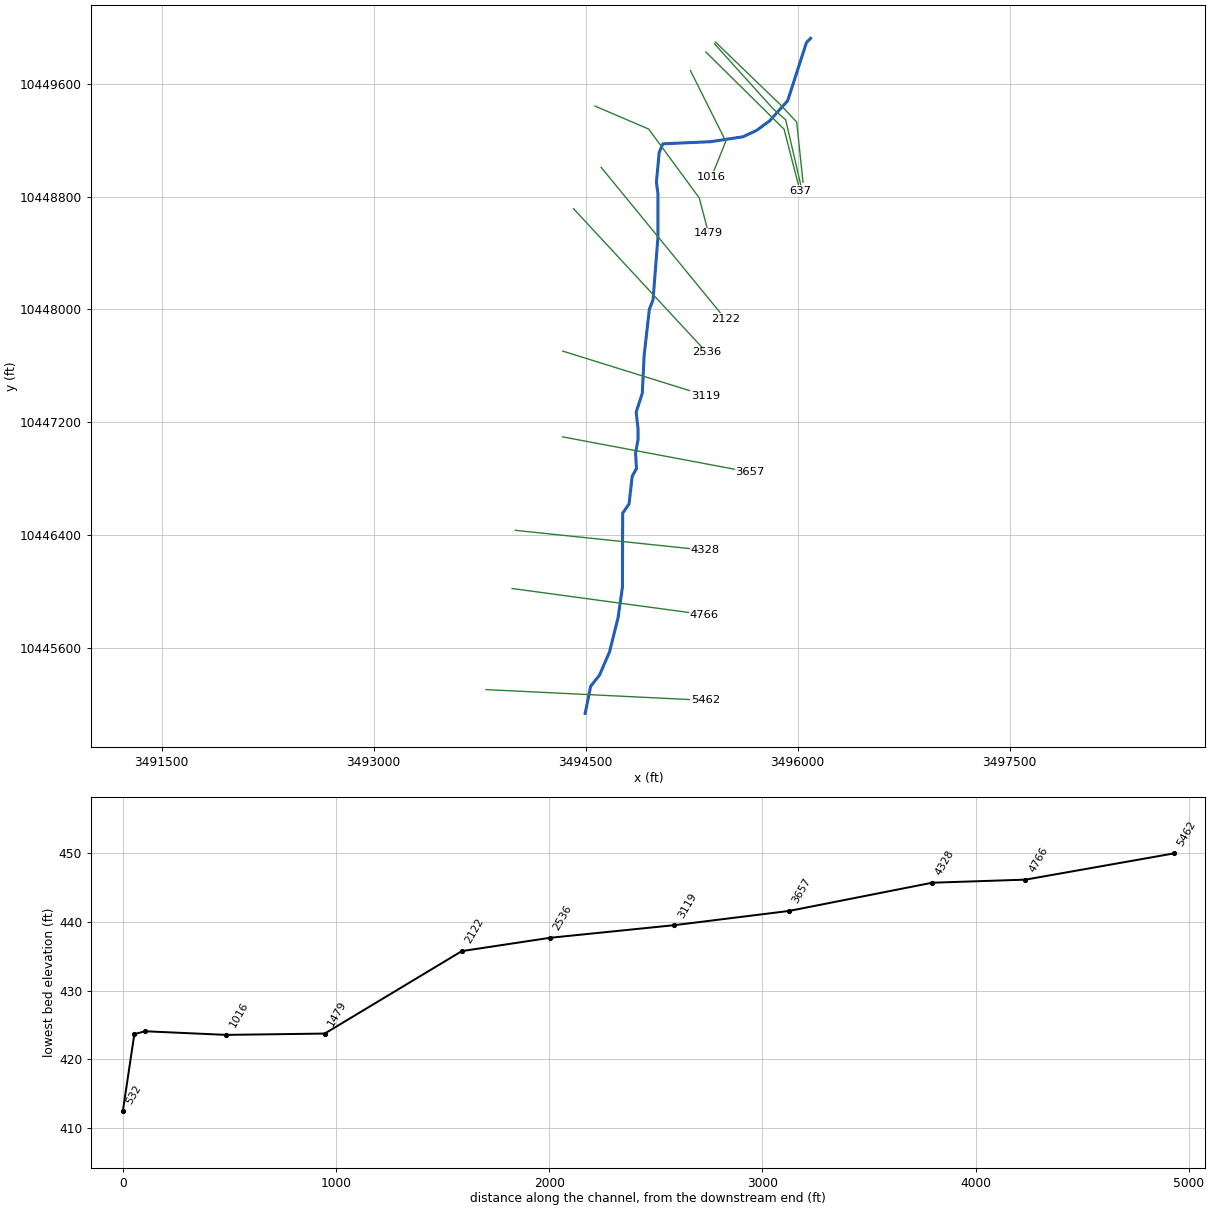
--- HEADS CREEK TRIB 7.prj (project) ---

Proj Title=HEADS CREEK TRIB 7 Base Level Engineering
Current Plan=p01
Default Exp/Contr=0.3,0.1
English Units
Geom File=g01
Flow File=f01
Plan File=p01
Y Axis Title=Elevation
X Axis Title(PF)=Main Channel Distance
X Axis Title(XS)=Station
BEGIN DESCRIPTION:
HEADS CREEK TRIB 7
END DESCRIPTION:
DSS Export Rating Curves= 0
DSS Export Rating Curve Sorted= 0
DSS Export Volume Flow Curves= 0
DXF OffsetX= 0
DXF OffsetY= 0
DXF ScaleX= 1
DXF ScaleY= 10

--- HEADS CREEK TRIB 7.p01 (plan) ---

Plan Title=Multiple Run
Short Identifier=Multiple
Geom File=g01
Flow File=f01
Subcritical Flow
K Sum by GR= 0
Std Step Tol= 0.01
Critical Tol= 0.01
Num of Std Step Trials= 20
Max Error Tol= 0.3
Flow Tol Ratio= 0.001
Split Flow NTrial= 30
Split Flow Tol= 0.02
Split Flow Ratio= 0.02
Log Output Level= 0
Friction Slope Method= 1
Unsteady Friction Slope Method= 2
Unsteady Bridges Friction Slope Method= 1
Parabolic Critical Depth
Global Vel Dist=  1 , 1 , 1
Global Log Level= 0
CheckData=True
Encroach Param= -1, 0, 0, 0
BEGIN DESCRIPTION:
Multiple Run
END DESCRIPTION:

--- HEADS CREEK TRIB 7.f01 (steady flow) ---

Flow Title=Multiple
Program Version=4.10
Number of Profiles= 7
Profile Names=10-year,25-year,50-year,1pct_min,100-year,1pct_plu,500-year
River Rch & RM=HEADS CREEK TRIB,Reach-1         ,5462
     750    1016    1233    1092    1477    1997    2114
Boundary for River Rch & Prof#=HEADS CREEK TRIB,Reach-1         , 1
Up Type= 0
Dn Type= 3
Dn Slope=0.005
Boundary for River Rch & Prof#=HEADS CREEK TRIB,Reach-1         , 2
Up Type= 0
Dn Type= 3
Dn Slope=0.005
Boundary for River Rch & Prof#=HEADS CREEK TRIB,Reach-1         , 3
Up Type= 0
Dn Type= 3
Dn Slope=0.005
Boundary for River Rch & Prof#=HEADS CREEK TRIB,Reach-1         , 4
Up Type= 0
Dn Type= 3
Dn Slope=0.005
Boundary for River Rch & Prof#=HEADS CREEK TRIB,Reach-1         , 5
Up Type= 0
Dn Type= 3
Dn Slope=0.005
Boundary for River Rch & Prof#=HEADS CREEK TRIB,Reach-1         , 6
Up Type= 0
Dn Type= 3
Dn Slope=0.005
Boundary for River Rch & Prof#=HEADS CREEK TRIB,Reach-1         , 7
Up Type= 0
Dn Type= 3
Dn Slope=0.005
DSS Import GetInterval= 0
DSS Import GetPeak= 0
DSS Import FillOption= 0

--- HEADS CREEK TRIB 7.g01 (geometry) ---

Geom Title=Existing Conditions
Program Version=4.10

River Reach=HEADS CREEK TRIB,Reach-1
Reach XY= 30
      3494497.21     10445138.19      3494535.88     10445330.07
      3494598.27     10445408.52      3494669.22     10445572.84
      3494730.12     10445817.46      3494760.89     10446032.15
      3494762.51     10446556.48      3494807.43     10446621.29
      3494829.83     10446818.65      3494860.22     10446872.91
      3494853.71     10446981.41      3494871.07      10447076.9
      3494871.07     10447155.02      3494858.05     10447272.21
      3494901.45     10447406.76      3494914.47     10447675.86
      3494951.36     10448001.38       3494977.4     10448068.65
        3495012.      10448511.6       3495012.1     10448818.47
      3495001.28     10448901.99      3495020.81     10449112.49
      3495046.85     10449173.25      3495385.39     10449188.44
      3495613.25     10449223.17      3495710.91     10449268.74
      3495802.06     10449336.01      3495930.09     10449479.24
      3496062.74     10449891.31      3496092.11     10449920.65

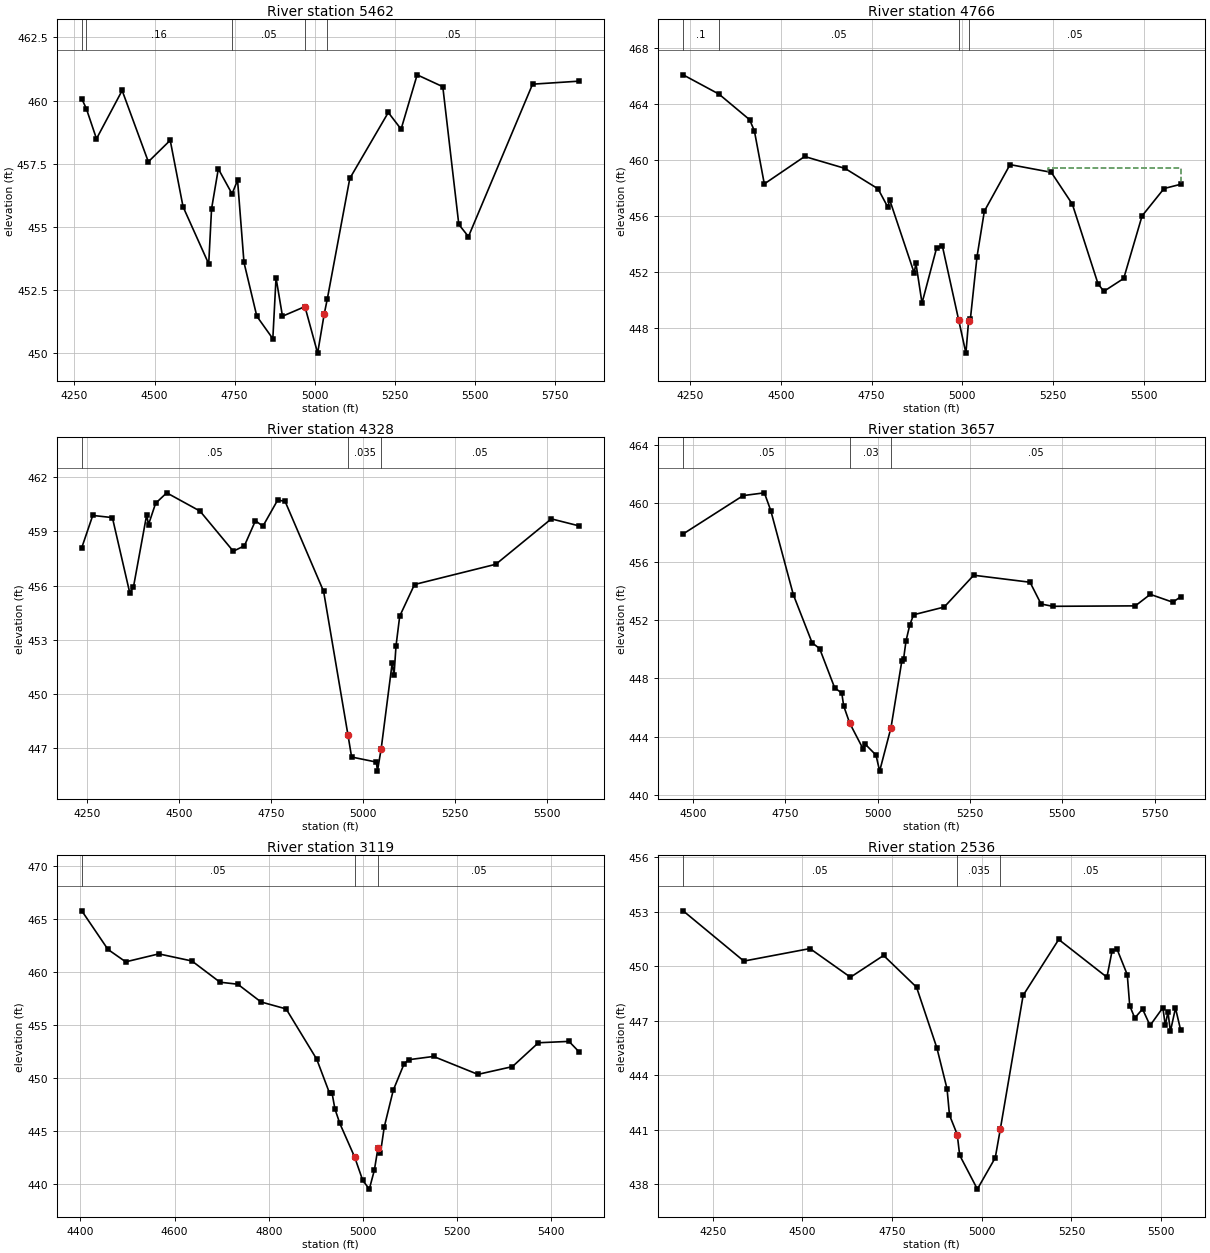
Type RM Length L Ch R = 1 ,5462    ,696,696,696
BEGIN DESCRIPTION:
HEADS CREEK TRIB 7 11.0
END DESCRIPTION:
XS GIS Cut Line= 2
      3493796.29     10445306.64      3495347.53     10445230.71
#Sta/Elev= 30
  4272.8  460.07  4287.1  459.68  4318.7  458.49  4398.8   460.4  4480.6  457.58
  4548.9  458.43    4589   455.8  4669.1  453.54    4678  455.72  4699.1   457.3
    4742  456.31  4759.2  456.85  4779.2   453.6  4819.3  451.47  4869.3  450.58
  4879.3  452.99  4899.4  451.47  4969.5  451.85  5009.2  450.01  5029.5  451.54
  5039.5  452.16  5109.6  456.92  5229.8  459.53  5269.8  458.87  5319.9  461.02
    5400  460.55    5450   455.1  5480.1  454.62  5680.3  460.65  5825.9  460.77
#Mann= 5 ,-1 , 0
  4272.8     .05       0  4287.1     .16       0    4742     .05       0
  4969.5    .035       0  5039.5     .05       0
Bank Sta=4969.5,5029.5
XS Rating Curve= 0 ,0
Exp/Cntr=0.3,0.1

Type RM Length L Ch R = 1 ,4766    ,438,438,438
BEGIN DESCRIPTION:
HEADS CREEK TRIB 7 9.0
END DESCRIPTION:
XS GIS Cut Line= 2
      3493980.74     10446022.79      3495337.05     10445838.33
#Sta/Elev= 30
  4231.5  466.09  4330.2  464.71  4414.5  462.88  4427.6  462.08  4454.9  458.29
  4565.9  460.25  4676.9   459.4  4767.8  457.94  4794.8  456.63  4799.8  457.16
  4867.2  451.93  4872.2   452.6  4888.9  449.77  4929.2  453.73  4944.7  453.87
  4989.8  448.55  5009.7  446.19  5017.1  448.51  5022.1  448.66  5040.2  453.08
  5060.4  456.34  5131.1  459.67  5244.5  459.12  5302.6  456.84  5373.3  451.14
  5389.3  450.61  5443.9  451.53  5494.4     456  5554.9  457.96  5600.3  458.26
#Mann= 4 ,-1 , 0
  4231.5      .1       0  4330.2     .05       0  4989.8    .035       0
  5017.1     .05       0
#XS Ineff= 2 , 0
                         5234.55          459.42
Permanent Ineff=
       F       F
Bank Sta=4989.8,5017.1
XS Rating Curve= 0 ,0
Exp/Cntr=0.3,0.1

Type RM Length L Ch R = 1 ,4328    ,671,671,671
BEGIN DESCRIPTION:
HEADS CREEK TRIB 7 8.0
END DESCRIPTION:
XS GIS Cut Line= 2
      3494002.46     10446435.11      3495347.48      10446294.1
#Sta/Elev= 30
  4236.2   458.1    4266  459.88  4319.4  459.76  4366.6   455.6  4376.6  455.91
  4412.6  459.91  4417.6  459.37  4436.9  460.55  4467.1  461.13  4557.6  460.12
  4648.1   457.9  4678.3   458.2  4708.4  459.59  4728.5  459.28  4768.8  460.73
  4788.9  460.66  4893.7  455.68  4959.8  447.75  4969.8  446.52  5037.2  446.24
    5040  445.74  5050.3  446.99  5080.1  451.72  5085.1  451.04  5090.5  452.66
  5100.6  454.31  5140.8  456.06    5362  457.18  5512.8  459.69  5588.6   459.3
#Mann= 3 ,-1 , 0
  4236.2     .05       0  4959.8    .035       0  5050.3     .05       0
Bank Sta=4959.8,5050.3
XS Rating Curve= 0 ,0
Exp/Cntr=0.3,0.1

Type RM Length L Ch R = 1 ,3657    ,538,538,538
BEGIN DESCRIPTION:
HEADS CREEK TRIB 7 7.0
END DESCRIPTION:
XS GIS Cut Line= 2
      3494338.83       10447097.      3495662.61     10446847.44
#Sta/Elev= 30
  4473.3  457.89  4635.8  460.52  4693.3  460.71  4710.7  459.49  4771.7  453.73
  4822.6  450.43    4843  450.03  4883.7  447.34    4903  446.98  4908.1   446.1
  4924.4  444.92  4960.5  443.16  4965.6   443.5  4995.6  442.73  5005.5  441.63
  5036.3  444.62  5065.4  449.15  5070.5  449.35    5077  450.57  5087.2  451.66
  5097.4  452.35  5180.4  452.88  5260.2  455.06  5412.8  454.58  5442.6  453.09
  5473.9  452.93  5697.8  452.96  5738.5  453.75  5799.5  453.21  5820.4  453.58
#Mann= 3 , 0 , 0
  4473.3     .05       0  4924.4     .03       0  5036.3     .05       0
Bank Sta=4924.4,5036.3
XS Rating Curve= 0 ,0
Exp/Cntr=0.3,0.1

Type RM Length L Ch R = 1 ,3119    ,583,583,583
BEGIN DESCRIPTION:
HEADS CREEK TRIB 7 6.0
END DESCRIPTION:
XS GIS Cut Line= 2
      3494338.76     10447704.66      3495347.55     10447390.09
#Sta/Elev= 30
  4402.8   465.8  4458.4  462.16  4496.1  460.99  4566.4  461.74  4636.8  461.07
  4696.4  459.07  4734.2  458.88  4783.4  457.21  4836.9  456.55  4901.9  451.81
  4929.2   448.6  4934.4  448.63  4940.5  447.13    4951  445.75  4982.4  442.59
  4999.5   440.4  5013.6  439.56  5024.3  441.34    5032  443.43  5037.2  442.94
  5045.3  445.41  5064.5  448.89  5087.2  451.34    5097  451.76    5150  452.07
  5244.3  450.38  5317.6  451.11  5372.8  453.36  5437.8  453.49  5459.5  452.49
#Mann= 3 , 0 , 0
  4402.8     .05       0  4982.4    .035       0    5032     .05       0
Bank Sta=4982.4,5032
XS Rating Curve= 0 ,0
Exp/Cntr=0.3,0.1

Type RM Length L Ch R = 1 ,2536    ,414,414,414
BEGIN DESCRIPTION:
HEADS CREEK TRIB 7 5.0
END DESCRIPTION:
XS GIS Cut Line= 2
      3494414.74     10448713.77      3495356.59     10447696.14
#Sta/Elev= 30
  4167.7  453.06    4337  450.29  4521.3  450.98  4634.1   449.4  4726.5   450.6
  4818.4  448.85  4875.1   445.5  4903.4  443.25  4910.2   441.8  4931.8  440.73
  4938.6  439.59  4987.9  437.72  5037.8  439.45    5052  441.04  5115.5   448.4
  5214.7  451.48  5349.1   449.4  5363.3  450.84  5377.4  450.94  5405.8  449.54
  5412.6  447.83  5426.8  447.15  5448.3  447.65  5469.3  446.74    5505  447.72
  5511.8  446.74  5519.2   447.5    5526  446.41  5540.2   447.7  5554.3  446.51
#Mann= 3 , 0 , 0
  4167.7     .05       0  4931.8    .035       0    5052     .05       0
Bank Sta=4931.8,5052
XS Rating Curve= 0 ,0
Exp/Cntr=0.3,0.1

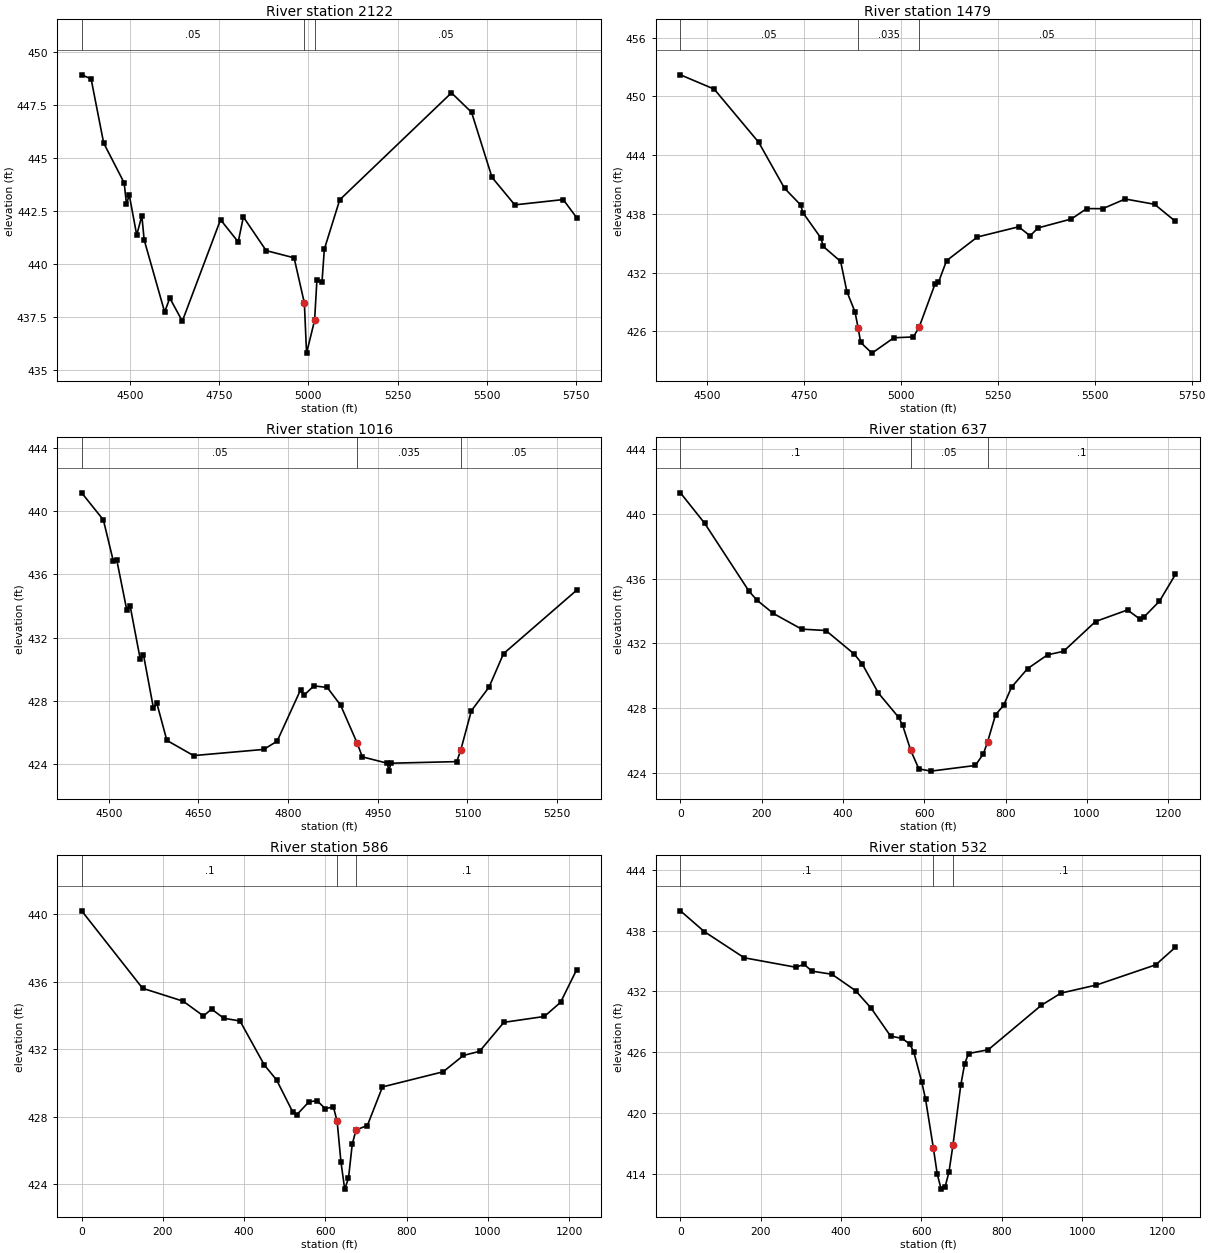
Type RM Length L Ch R = 1 ,2122    ,643,643,643
BEGIN DESCRIPTION:
HEADS CREEK TRIB 7 4.0
END DESCRIPTION:
XS GIS Cut Line= 2
      3494610.09      10449006.7      3495488.01     10447933.68
#Sta/Elev= 30
  4365.3  448.92  4391.7  448.73  4426.9   445.7  4484.3  443.82  4490.8  442.82
  4498.6  443.25  4519.5  441.35  4533.8  442.27  4540.3  441.13  4597.7  437.72
  4612.1  438.38  4647.2  437.29  4754.2  442.08  4803.7  441.03  4818.1  442.21
    4882  440.62  4960.2  440.28  4988.9  438.15  4995.1  435.78  5017.6  437.33
  5024.1  439.23  5038.4  439.16  5044.9  440.69    5088  443.02  5400.9  448.07
  5457.2  447.15  5514.4  444.08  5578.2  442.78  5713.9  443.03  5751.7  442.17
#Mann= 3 , 0 , 0
  4365.3     .05       0  4988.9    .035       0  5017.6     .05       0
#XS Ineff= 2 , 0
         4755.45  442.05
Permanent Ineff=
       F       F
Bank Sta=4988.9,5017.6
XS Rating Curve= 0 ,0
Exp/Cntr=0.3,0.1

Type RM Length L Ch R = 1 ,1479    ,463,463,463
BEGIN DESCRIPTION:
HEADS CREEK TRIB 7 3.0
END DESCRIPTION:
XS GIS Cut Line= 4
      3494566.63     10449440.77      3494946.43       10449278.
      3495304.51     10448789.72       3495369.6     10448540.19
#Sta/Elev= 30
  4431.7  452.19  4518.8  450.73  4633.5   445.3  4700.1  440.61  4741.8   438.9
  4747.3  438.13  4794.4   435.5  4799.9  434.67  4844.9  433.13    4861  430.05
  4881.8  427.99    4890  426.34  4896.5  424.86  4925.6  423.77  4982.2  425.34
  5032.3  425.42    5047  426.39  5088.7  430.88  5097.2  431.01    5118  433.21
  5197.5  435.63    5304  436.67  5333.3  435.75  5354.2  436.56  5439.9  437.47
  5479.4  438.53  5520.8  438.52  5578.6  439.51  5654.4  438.97  5708.3  437.22
#Mann= 3 , 0 , 0
  4431.7     .05       0    4890    .035       0    5047     .05       0
Bank Sta=4890,5047
XS Rating Curve= 0 ,0
Exp/Cntr=0.3,0.1

Type RM Length L Ch R = 1 ,1016    ,379,379,379
BEGIN DESCRIPTION:
HEADS CREEK TRIB 7 2.0
END DESCRIPTION:
XS GIS Cut Line= 3
      3495242.13      10449691.6      3495492.11     10449191.64
      3495392.12     10448941.67
#Sta/Elev= 30
  4454.6  441.14  4490.9  439.43  4507.7  436.81  4513.3   436.9    4530  433.76
  4535.6  434.02  4552.4  430.68    4558  430.92  4574.7  427.55  4580.3  427.87
  4597.1  425.52  4641.8  424.56  4759.2  424.95  4781.6  425.47  4820.7   428.7
  4826.3  428.36  4843.1  428.96  4865.4  428.86  4887.8  427.74  4915.7  425.33
  4924.1  424.48  4965.8  424.08  4968.6  423.58  4971.8  424.08  5082.2  424.18
    5089  424.94  5106.5  427.39  5136.1  428.88  5160.3  430.99  5282.8     435
#Mann= 3 , 0 , 0
  4454.6     .05       0  4915.7    .035       0    5089     .05       0
Bank Sta=4915.7,5089
XS Rating Curve= 0 ,0
Exp/Cntr=0.3,0.1

Type RM Length L Ch R = 1 ,637     ,51,51,51
XS GIS Cut Line= 3
      3495350.85    10449823.903     3495904.236    10449277.028
     3496016.215    10448842.132
#Sta/Elev= 30
       0441.299759.63397 439.418168.9629435.2122188.8409434.6553228.5969433.8467
298.1699432.8791357.8038432.7935427.3768431.3434447.2548430.7247487.0108428.9292
536.7057427.4311546.6448426.9329566.5228425.3895586.4008424.2463616.2177424.1067
725.5467424.4566745.4247425.1891755.3636425.9049775.2416427.5972794.9062428.1663
814.5707429.2977853.8997430.4378 903.061431.2922942.3901 431.5081021.048433.3497
1099.706434.06381129.203433.51861139.035 433.5991178.364434.60531217.693436.2632
#Mann= 3 , 0 , 0
       0      .1       0566.5228     .05       0755.3636      .1       0
Bank Sta=566.5228,755.3636
XS Rating Curve= 0 ,0
Exp/Cntr=0.3,0.1

Type RM Length L Ch R = 1 ,586     ,54,54,54
XS GIS Cut Line= 4
     3495412.482    10449881.455     3495827.013    10449421.038
     3495915.629    10449343.844     3496025.329    10448869.476
#Sta/Elev= 30
       0440.2054149.9046435.6113 249.841434.8445299.8092433.9672319.7964434.3769
349.7774433.8318389.7519433.6704449.7138431.0572479.6947 430.178519.6693428.2683
529.6629428.1107559.6438428.8784 579.631428.9387599.6183428.4676619.6057428.5783
628.9055427.7165638.2053425.3244647.5051423.6946656.8049424.3345666.1047426.3593
675.4045427.2091 703.304427.4674740.5032 429.758889.9462430.6567939.7605431.6249
979.6119431.87111039.389433.58891139.018433.93851178.869434.77621218.721436.7213
#Mann= 3 , 0 , 0
       0      .1       0628.9055     .05       0675.4045      .1       0
Bank Sta=628.9055,675.4045
XS Rating Curve= 0 ,0
Exp/Cntr=0.3,0.1

Type RM Length L Ch R = 1 ,532     ,0,0,0
XS GIS Cut Line= 4
     3495418.159    10449894.996     3495879.791    10449448.932
     3495993.506    10449327.404      3496038.35    10448902.028
#Sta/Elev= 30
       0439.954659.54691437.8985158.7917435.3165  287.81434.3769 307.659434.6726
 327.508433.9979377.1304433.6878436.1751432.0649474.8687430.3352523.2356427.5792
552.2557427.3459571.6025426.7664581.2759425.9766600.6227 423.073610.2961 421.347
629.6428416.5499639.3162413.9656649.0936412.4596658.8708412.6703668.6482414.1624
678.4255416.7867697.9802422.7273707.7574424.8654717.5348425.8573766.4214426.2308
 898.079430.6072947.2636431.82341035.796432.6267 1183.35434.62071232.534436.3641
#Mann= 3 , 0 , 0
       0      .1       0629.6428     .05       0678.4255      .1       0
Bank Sta=629.6428,678.4255
XS Rating Curve= 0 ,0
Exp/Cntr=0.3,0.1
Stream Node=HEADS CREEK TRIB,Reach-1         , 0 , 0 ,Upstream end
Stream Node=HEADS CREEK TRIB,Reach-1         , 0 , 1 ,Downstream end

Chan Stop Cuts=-1
Use User Specified Reach Order=0
Composite Channel Slope=5