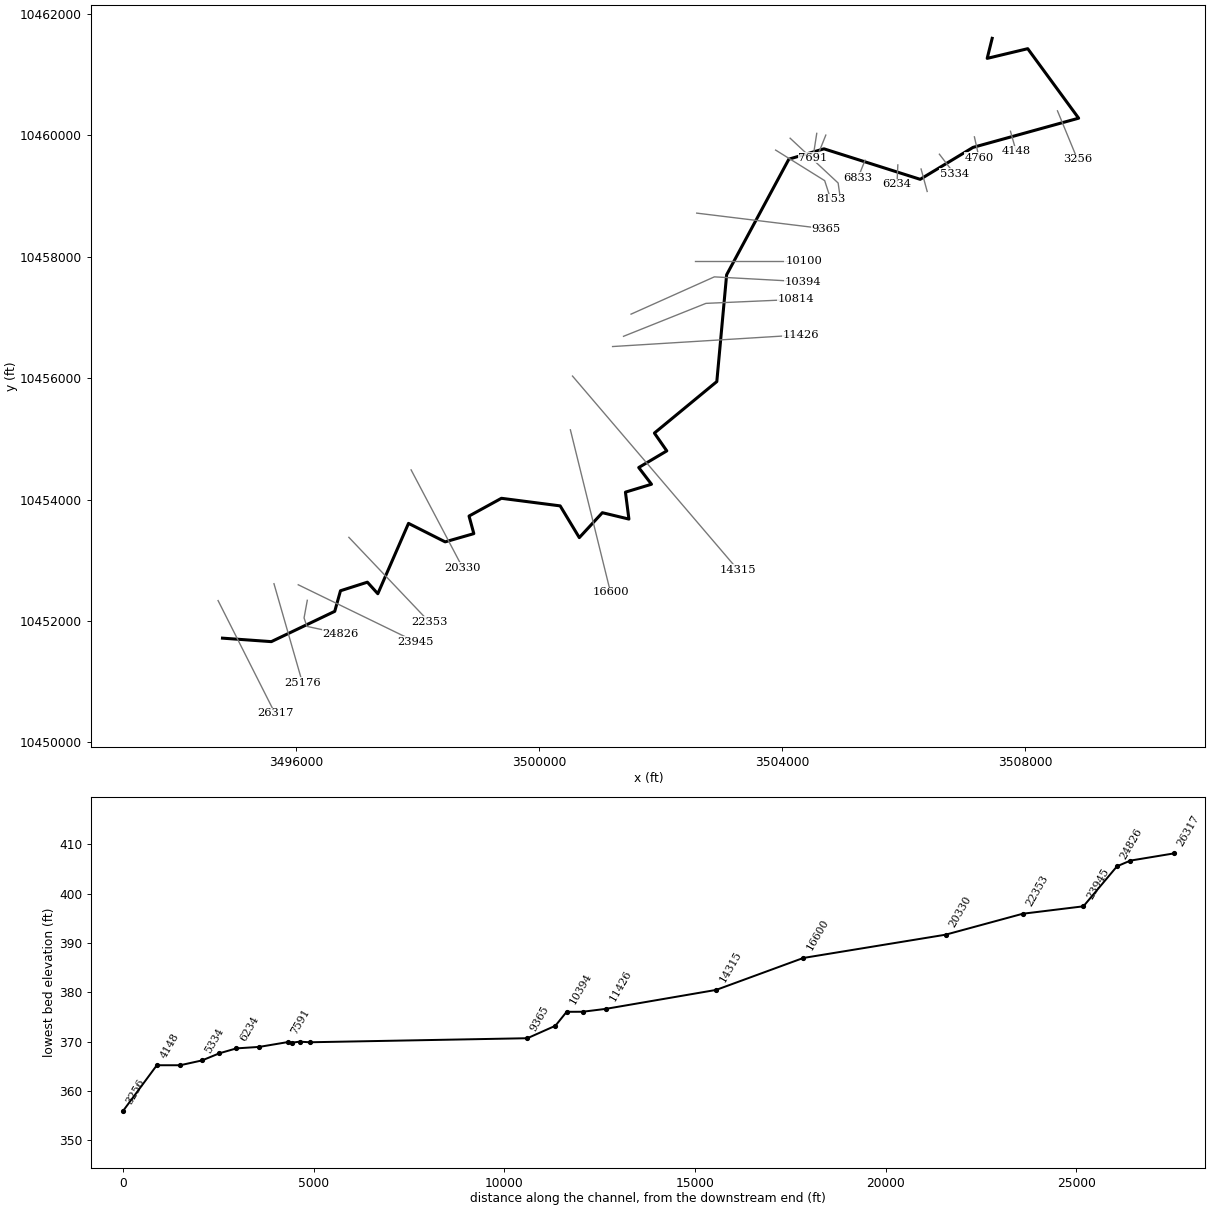
--- HEADS CREEK.prj (project) ---

Proj Title=HEADS CREEK Base Level Engineering
Current Plan=p01
Default Exp/Contr=0.3,0.1
English Units
Geom File=g01
Flow File=f01
Plan File=p01
Y Axis Title=Elevation
X Axis Title(PF)=Main Channel Distance
X Axis Title(XS)=Station
BEGIN DESCRIPTION:
HEADS CREEK
END DESCRIPTION:
DSS Export Rating Curves= 0
DSS Export Rating Curve Sorted= 0
DSS Export Volume Flow Curves= 0
DXF OffsetX= 0
DXF OffsetY= 0
DXF ScaleX= 1
DXF ScaleY= 10

--- HEADS CREEK.p01 (plan) ---

Plan Title=Multiple Run
Short Identifier=Multiple
Geom File=g01
Flow File=f01
Subcritical Flow
K Sum by GR= 0
Std Step Tol= 0.01
Critical Tol= 0.01
Num of Std Step Trials= 20
Max Error Tol= 0.3
Flow Tol Ratio= 0.001
Split Flow NTrial= 30
Split Flow Tol= 0.02
Split Flow Ratio= 0.02
Log Output Level= 0
Friction Slope Method= 1
Unsteady Friction Slope Method= 2
Unsteady Bridges Friction Slope Method= 1
Parabolic Critical Depth
Global Vel Dist=  1 , 1 , 1
Global Log Level= 0
CheckData=True
Encroach Param= -1, 0, 0, 0
BEGIN DESCRIPTION:
Multiple Run
END DESCRIPTION:

--- HEADS CREEK.f01 (steady flow) ---

Flow Title=Multiple
Program Version=4.10
Number of Profiles= 7
Profile Names=10-year,25-year,50-year,1pct_min,100-year,1pct_plu,500-year
River Rch & RM=HEADS CREEK,Reach-1         ,26317
    1134    1577    1946    1751    2368    3203    3500
River Rch & RM=HEADS CREEK,Reach-1         ,23945
    2033    2892    3622    3300    4463    6035    6765
River Rch & RM=HEADS CREEK,Reach-1         ,22353
    2033    2892    3622    3300    4463    6035    6765
River Rch & RM=HEADS CREEK,Reach-1         ,16600
    2643    3790    4770    4362    5900    7978    9013
Boundary for River Rch & Prof#=HEADS CREEK,Reach-1         , 1
Up Type= 0
Dn Type= 3
Dn Slope=0.0013
Boundary for River Rch & Prof#=HEADS CREEK,Reach-1         , 2
Up Type= 0
Dn Type= 3
Dn Slope=0.0013
Boundary for River Rch & Prof#=HEADS CREEK,Reach-1         , 3
Up Type= 0
Dn Type= 3
Dn Slope=0.0013
Boundary for River Rch & Prof#=HEADS CREEK,Reach-1         , 4
Up Type= 0
Dn Type= 3
Dn Slope=0.0013
Boundary for River Rch & Prof#=HEADS CREEK,Reach-1         , 5
Up Type= 0
Dn Type= 3
Dn Slope=0.0013
Boundary for River Rch & Prof#=HEADS CREEK,Reach-1         , 6
Up Type= 0
Dn Type= 3
Dn Slope=0.0013
Boundary for River Rch & Prof#=HEADS CREEK,Reach-1         , 7
Up Type= 0
Dn Type= 3
Dn Slope=0.0013
DSS Import GetInterval= 0
DSS Import GetPeak= 0
DSS Import FillOption= 0

--- HEADS CREEK.g01 (geometry) ---

Geom Title=Existing Conditions
Program Version=4.10

River Reach=HEADS CREEK     ,Reach-1
Reach XY= 30
      3494791.41     10451717.79      3495595.17     10451660.38
      3496638.67     10452159.33      3496733.39     10452498.34
      3497176.03     10452639.61      3497347.77     10452449.43
      3497852.98     10453608.08      3498456.05     10453303.59
      3498928.08     10453439.18      3498849.11     10453728.61
       3499382.1     10454021.14      3500349.11     10453896.14
      3500664.05     10453373.36      3501043.39     10453783.95
      3501480.46     10453678.91      3501423.25     10454122.32
      3501852.07     10454252.53        3501642.      10454527.7
      3502103.81       10454802.      3501899.82     10455095.41
      3502927.16      10455943.5      3503088.62     10457702.18
      3504112.92     10459606.69      3504691.05     10459776.83
      3506274.38     10459274.66      3507143.74     10459800.49
       3508882.2     10460281.55      3508044.48     10461426.15
      3507377.12     10461266.49      3507459.16     10461596.67

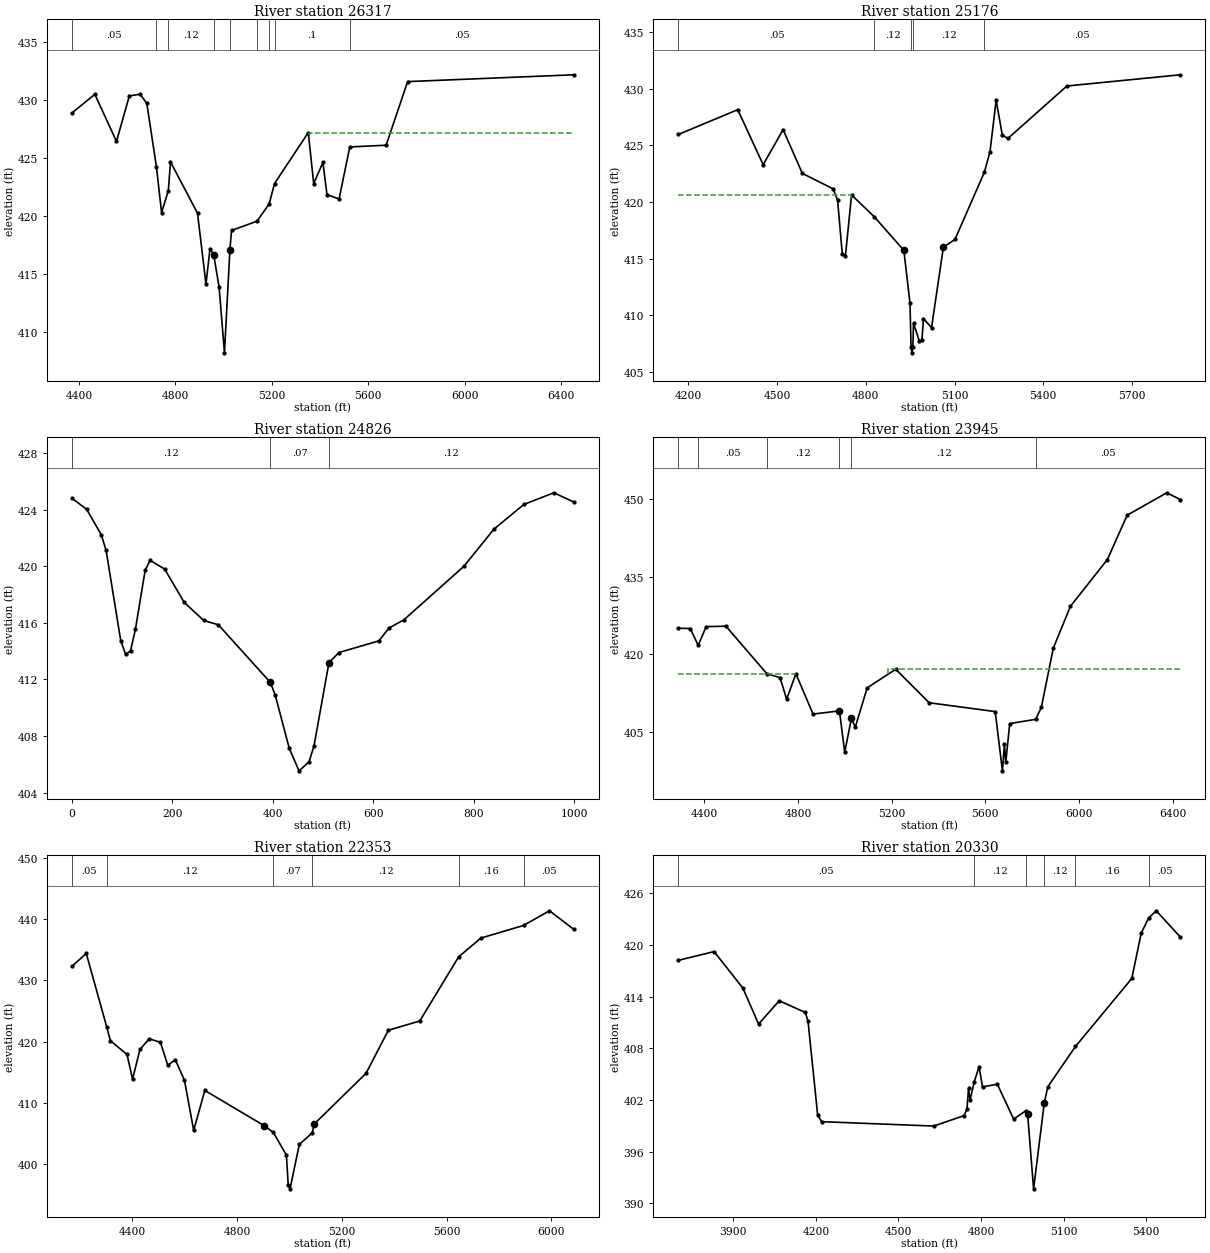
Type RM Length L Ch R = 1 ,26317   ,1141,1141,1141
BEGIN DESCRIPTION:
HEADS CREEK 10.0
END DESCRIPTION:
XS GIS Cut Line= 2
      3494718.58     10452336.43      3495656.08     10450478.79
#Sta/Elev= 30
  4371.1   428.9  4466.1  430.51  4555.7  426.44    4609  430.37  4653.6  430.52
  4681.5  429.73  4721.2  424.27  4742.8  420.29  4770.7  422.17  4779.7  424.67
  4891.7  420.23  4926.8   414.1  4943.5  417.17  4958.9  416.62  4981.3  413.83
  5003.5  408.16  5026.1  417.09  5032.7  418.74  5138.2  419.54  5188.8  421.03
  5211.1   422.8    5351   427.2  5373.4   422.8  5411.8  424.62  5428.5  421.84
  5478.7  421.46  5523.1  425.96  5673.8  426.11    5763  431.61  6451.9   432.2
#Mann= 9 ,-1 , 0
  4371.1     .05       0  4721.2      .1       0  4770.7     .12       0
  4958.9     .07       0  5026.1     .12       0  5138.2     .16       0
  5188.8     .12       0  5211.1      .1       0  5523.1     .05       0
#XS Ineff= 2 , 0
         4779.83  424.64 5352.27          427.19
Permanent Ineff=
       F       F
Bank Sta=4958.9,5026.1
XS Rating Curve= 0 ,0
Exp/Cntr=0.3,0.1

Type RM Length L Ch R = 1 ,25176   ,350,350,350
BEGIN DESCRIPTION:
Mapping XS b3173b34
END DESCRIPTION:
XS GIS Cut Line= 2
       3495638.7     10452614.25      3496107.28     10450982.91
#Sta/Elev= 30
  4166.2  425.97  4366.6  428.15  4452.6   423.3  4520.1  426.39  4585.1  422.53
  4689.1  421.17  4704.3  420.17  4720.3  415.42  4730.8  415.25  4751.6  420.63
  4828.6   418.7  4928.4  415.74  4949.2  411.08  4952.9   407.2  4955.6   406.7
  4958.9   407.2  4961.1  409.32  4980.5  407.76  4989.6  407.83  4994.8  409.72
  5022.1  408.92  5062.2  416.03  5101.2   416.7  5200.9  422.64  5219.8  424.45
  5240.6  428.98  5261.4  425.92  5280.2  425.61  5479.9  430.24  5863.5  431.23
#Mann= 5 ,-1 , 0
  4166.2     .05       0  4828.6     .12       0  4952.9     .07       0
  4958.9     .12       0  5200.9     .05       0
#XS Ineff= 2 , 0
            4750  420.62
Permanent Ineff=
       F       F
Bank Sta=4928.4,5062.2
XS Rating Curve= 0 ,0
Exp/Cntr=0.3,0.1

Type RM Length L Ch R = 1 ,24826   ,881,881,881
XS GIS Cut Line= 4
     3496186.938    10452341.401     3496133.813    10452051.007
     3496180.427    10451911.713     3496735.556    10451791.624
#Sta/Elev= 30
       0424.801129.16318424.024158.32636422.232868.04742421.115297.21059414.7385
106.9317 413.772116.6527414.0168126.3738415.5348145.8159419.7072 155.537420.4169
184.7001419.7982223.5844417.4466262.4686 416.168291.6318415.8639395.2411411.7925
404.6602410.9218432.9173407.1367452.2881405.5473472.1916406.1806482.1433407.3047
511.9986413.1977 531.902413.9046 611.516414.7296631.4195415.6325661.2747416.2155
780.6957419.9938840.4061422.6118900.1166424.3644959.8271425.1886999.6341424.5368
#Mann= 3 , 0 , 0
       0     .12       0395.2411     .07       0511.9986     .12       0
Bank Sta=395.2411,511.9986
XS Rating Curve= 0 ,0
Exp/Cntr=0.3,0.1

Type RM Length L Ch R = 1 ,23945   ,1592,1592,1592
BEGIN DESCRIPTION:
Mapping XS 49d49542
END DESCRIPTION:
XS GIS Cut Line= 2
        3496038.     10452596.87      3497965.06     10451659.38
#Sta/Elev= 30
    4290  425.06  4340.4     425  4374.2  421.74  4408.1  425.37  4492.7  425.45
  4667.4  416.25  4723.8  415.48  4751.9   411.3  4791.4  416.24  4864.6  408.43
  4977.4  409.04  4999.9  401.04  5028.5  407.58    5045  405.88  5095.7   413.5
  5217.6  417.11  5360.7  410.62  5642.5  408.91  5673.3  397.43    5682   402.6
  5687.6  399.09  5704.5  406.59  5815.4  407.41  5839.8  409.77  5890.5  421.19
  5963.7   429.3  6121.6  438.37  6206.2  446.97  6375.2   451.3    6433  449.98
#Mann= 6 ,-1 , 0
    4290      .1       0  4374.2     .05       0  4667.4     .12       0
  4977.4     .07       0  5028.5     .12       0  5815.4     .05       0
#XS Ineff= 2 , 0
         4791.19  416.28 5184.66          417.16
Permanent Ineff=
       F       F
Bank Sta=4977.4,5028.5
XS Rating Curve= 0 ,0
Exp/Cntr=0.3,0.1

Type RM Length L Ch R = 1 ,22353   ,2023,2023,2023
BEGIN DESCRIPTION:
Mapping XS 9a6fec14
END DESCRIPTION:
XS GIS Cut Line= 2
      3496871.32     10453378.15      3498190.82     10451989.19
#Sta/Elev= 30
  4170.1   432.3  4224.7  434.42  4302.7  422.42  4316.9  420.14  4380.4  417.89
  4401.5  413.85  4429.8  418.73  4465.4  420.46  4507.8  419.87  4536.1  416.11
  4564.5  417.05  4599.7  413.66  4634.9  405.47  4677.3  412.01  4903.8  406.25
    4939  405.14  4988.8  401.43  4995.7  396.57  5002.7  395.92  5038.1  403.18
  5087.9  405.09  5094.8  406.51  5292.9  414.82  5377.9  421.85    5498  423.37
  5646.5  433.87  5731.4  436.93    5894  438.99  5993.1  441.39  6085.9  438.35
#Mann= 6 ,-1 , 0
  4170.1     .05       0  4302.7     .12       0    4939     .07       0
  5087.9     .12       0  5646.5     .16       0    5894     .05       0
#XS Ineff= 2 , 0
          4677.6  411.98
Permanent Ineff=
       F       F
Bank Sta=4903.8,5094.8
XS Rating Curve= 0 ,0
Exp/Cntr=0.3,0.1

Type RM Length L Ch R = 1 ,20330   ,3730,3730,3730
BEGIN DESCRIPTION:
Mapping XS 28ed4d63
END DESCRIPTION:
XS GIS Cut Line= 2
      3497895.67      10454489.2      3498745.81     10452875.66
#Sta/Elev= 30
  3700.6  418.21  3830.1  419.22  3934.6  414.98  3991.7  410.81  4066.8  413.51
  4161.3  412.16  4171.3  411.16  4206.5  400.22    4221  399.47  4628.2  398.96
  4738.4  400.17    4749  400.93  4754.8  403.35  4760.4  401.98  4775.5  404.12
  4793.2  405.85  4805.5   403.5  4859.3  403.83  4918.6  399.77  4963.8  400.75
  4969.4  400.35  4991.2  391.67  5029.9  401.63  5042.9  403.53  5143.3   408.2
  5348.1   416.1  5382.3  421.37  5410.1  423.15  5437.1  423.96  5524.4  420.91
#Mann= 6 ,-1 , 0
  3700.6     .05       0  4775.5     .12       0  4963.8     .07       0
  5029.9     .12       0  5143.3     .16       0  5410.1     .05       0
Bank Sta=4969.4,5029.9
XS Rating Curve= 0 ,0
Exp/Cntr=0.3,0.1

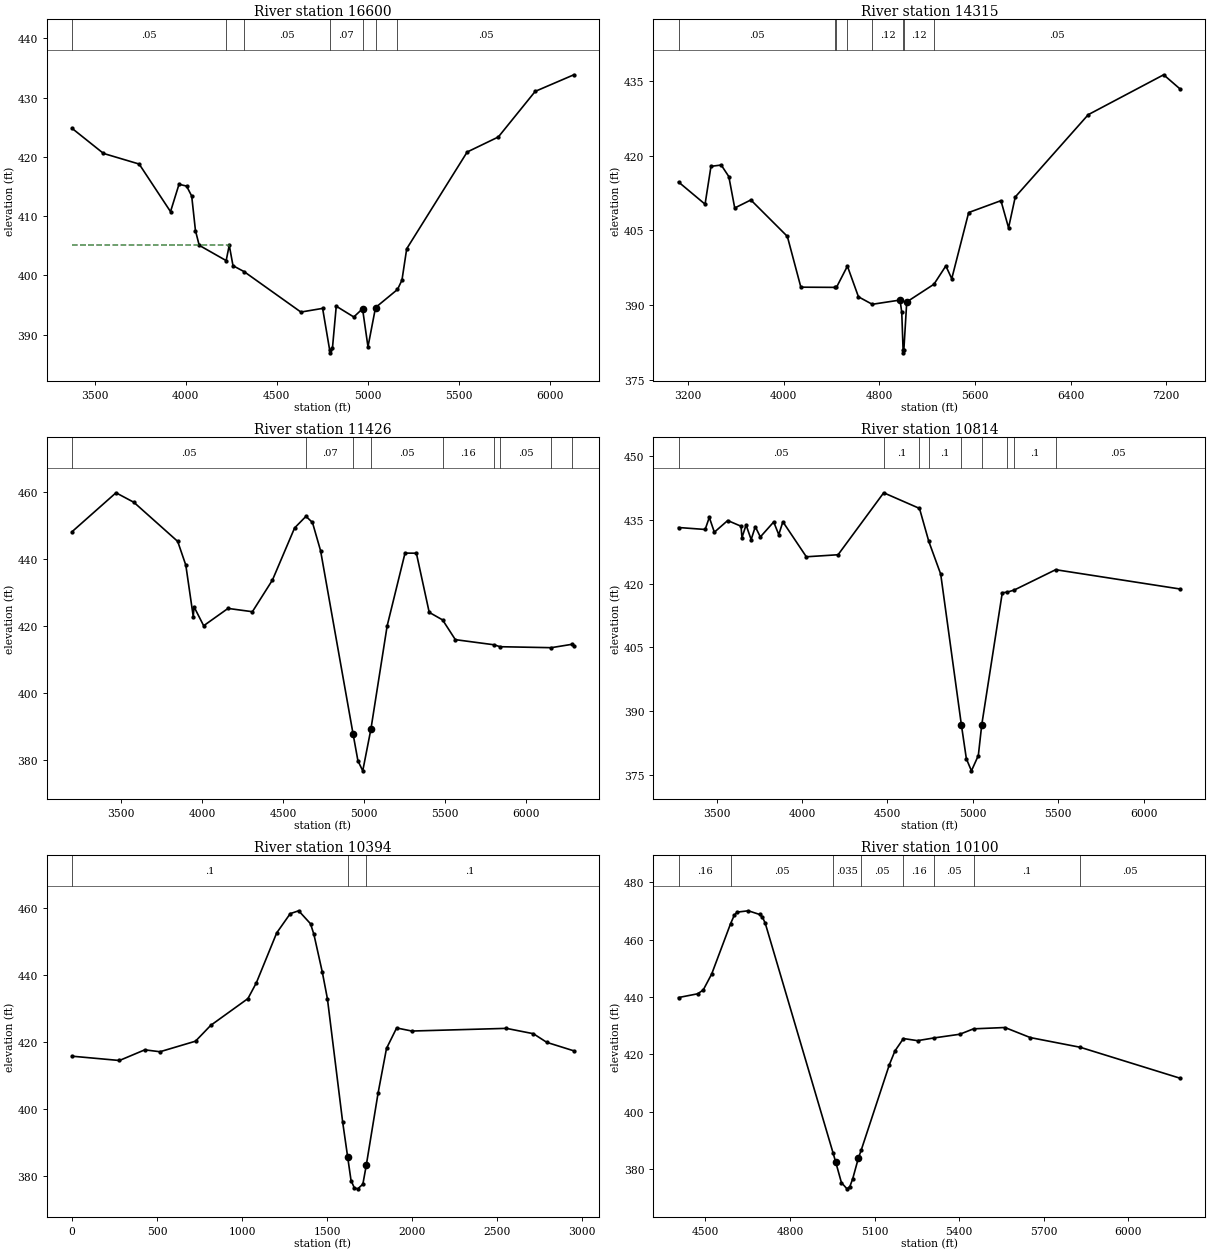
Type RM Length L Ch R = 1 ,16600   ,2285,2285,2285
BEGIN DESCRIPTION:
Mapping XS 834caf31
END DESCRIPTION:
XS GIS Cut Line= 2
      3500517.17     10455148.98      3501176.75     10452475.95
#Sta/Elev= 30
  3376.3  424.82  3548.7  420.59  3744.4   418.8  3916.5  410.77  3963.1  415.39
  4004.6  415.08  4032.7   413.4  4053.3  407.57  4073.9  405.09  4221.8  402.51
  4238.7   405.1  4259.3  401.65  4319.8  400.66  4631.8  393.83    4751  394.45
  4789.5  387.45  4792.3  386.95  4805.2  387.83  4825.8  394.82  4922.1     393
    4970  394.39  4999.9  387.97  5041.3  394.59  5161.8  397.64  5186.3  399.21
  5212.4  404.51  5544.1  420.83  5715.2  423.37  5917.4  431.06  6129.5  433.86
#Mann= 7 ,-1 , 0
  3376.3     .05       0  4221.8      .1       0  4319.8     .05       0
  4789.5     .07       0    4970     .05       0  5041.3     .12       0
  5161.8     .05       0
#XS Ineff= 2 , 0
         4236.93  405.08
Permanent Ineff=
       F       F
Bank Sta=4970,5041.3
XS Rating Curve= 0 ,0
Exp/Cntr=0.3,0.1

Type RM Length L Ch R = 1 ,14315   ,2889,2889,2889
BEGIN DESCRIPTION:
Mapping XS c24e9131
END DESCRIPTION:
XS GIS Cut Line= 2
      3500551.93     10456034.33      3503277.38     10452840.17
#Sta/Elev= 30
  3119.6  414.71  3341.6  410.26  3391.1  417.85  3476.7  418.11  3540.4   415.8
  3589.8   409.5  3724.8  411.11  4030.1  403.81  4143.2  393.63  4432.6  393.59
  4441.1  393.59  4532.7  397.85  4625.1   391.7  4740.6   390.2  4973.2  391.05
  4987.5  388.57  4998.8  380.97  5001.5  380.47  5004.8  380.97  5029.2  390.67
  5256.9  394.22  5356.4  397.89  5405.8  395.33  5547.4  408.59  5817.5  410.97
  5881.2  405.53  5937.2  411.71  6547.7   428.2    7179   436.2  7318.5  433.31
#Mann= 8 ,-1 , 0
  3119.6     .05       0  4432.6     .16       0  4441.1     .05       0
  4532.7     .16       0  4740.6     .12       0  4998.8     .07       0
  5004.8     .12       0  5256.9     .05       0
Bank Sta=4973.2,5029.2
XS Rating Curve= 0 ,0
Exp/Cntr=0.3,0.1

Type RM Length L Ch R = 1 ,11426   ,612,612,612
BEGIN DESCRIPTION:
Mapping XS 03f0f823
END DESCRIPTION:
XS GIS Cut Line= 2
      3501211.62     10456520.48      3504301.93     10456711.45
#Sta/Elev= 30
  3197.7  448.11  3468.7  459.74  3578.9   456.9  3849.4  445.21  3899.5  438.12
  3945.4  422.75  3950.4  425.64  4009.7     420    4160  425.18  4310.3  424.19
  4434.1  433.66  4570.8  449.23  4640.9   452.7    4681  450.86  4731.1  442.42
  4931.5  387.68  4961.5  379.64  4991.3  376.63  5041.7  389.11  5141.9  419.97
  5252.1  441.71  5322.2  441.68  5401.4     424    5484  421.74  5562.6  415.84
    5801  414.31  5838.7  413.73  6154.2  413.44  6279.8  414.43  6293.9  414.08
#Mann= 9 ,-1 , 0
  3197.7     .05       0  4640.9     .07       0  4931.5     .05       0
  5041.7     .05       0    5484     .16       0    5801     .12       0
  5838.7     .05       0  6154.2      .1       0  6279.8     .05       0
Bank Sta=4931.5,5041.7
XS Rating Curve= 0 ,0
Exp/Cntr=0.3,0.1

Type RM Length L Ch R = 1 ,10814   ,420,420,420
BEGIN DESCRIPTION:
Mapping XS 3723f386
END DESCRIPTION:
XS GIS Cut Line= 3
      3501391.74     10456689.02      3502748.08     10457231.56
      3504223.52     10457296.65
#Sta/Elev= 30
  3276.8  433.14  3432.7  432.68  3456.9  435.52  3486.5  432.04  3564.6  434.78
  3642.7  433.44  3648.1  430.76  3672.3  433.74  3701.9   430.3  3726.1  433.33
  3755.8  430.93  3833.9  434.44  3863.5  431.47  3887.7  434.48    4025  426.27
  4210.8  426.75  4477.9  441.29  4687.4  437.62  4742.1  429.86  4811.7  422.19
  4932.4  386.91  4961.9  378.87  4991.6  376.04  5031.9  379.63    5052  386.86
  5172.1  417.82  5202.1  417.98  5242.1  418.47  5484.7  423.24  6214.5   418.7
#Mann= 9 ,-1 , 0
  3276.8     .05       0  4477.9      .1       0  4687.4     .05       0
  4742.1      .1       0  4932.4     .07       0    5052      .1       0
  5202.1     .05       0  5242.1      .1       0  5484.7     .05       0
Bank Sta=4932.4,5052
XS Rating Curve= 0 ,0
Exp/Cntr=0.3,0.1

Type RM Length L Ch R = 1 ,10394   ,294,294,294
XS GIS Cut Line= 3
     3501515.749    10457054.248     3502886.374    10457668.137
     3504346.478    10457588.102
#Sta/Elev= 30
       0415.6868 278.639414.4023  427.91417.5873517.4725417.0199726.4518420.1765
816.0143424.91051034.945432.91641084.702437.66031204.119452.5489 1283.73458.3076
1333.487459.16771403.147455.28651423.049 452.1211472.806440.76551502.661432.8425
1592.054396.10721621.852385.52091641.718378.48881661.583376.26621681.448376.0268
1711.246377.43571731.111383.0265 1800.64404.62291850.303418.00571909.899424.1309
1999.293423.21022555.521424.01022714.443422.41182793.904 419.8172952.826417.2884
#Mann= 3 , 0 , 0
       0      .1       01621.852     .07       01731.111      .1       0
Bank Sta=1621.852,1731.111
XS Rating Curve= 0 ,0
Exp/Cntr=0.3,0.1

Type RM Length L Ch R = 1 ,10100   ,735,735,735
BEGIN DESCRIPTION:
HEADS CREEK 8.0
END DESCRIPTION:
XS GIS Cut Line= 2
      3502574.46     10457936.85      3504353.96     10457936.85
#Sta/Elev= 30
  4404.6  439.83  4472.2  441.13  4492.2  442.46  4522.2  448.04  4588.9  465.49
  4602.2  468.48  4612.2  469.58  4652.2  470.05  4692.2  468.76  4702.2  467.84
  4712.2  465.68  4952.2  385.84  4962.2  382.45  4982.2  375.37    5002   373.2
  5012.2  374.01  5022.2  376.67  5042.2  383.84  5052.2  386.62  5152.2  416.43
  5172.2  421.26  5202.2  425.55  5252.2  424.81  5309.1  425.74  5402.2  427.05
  5450.7  428.93  5562.2  429.39  5652.2  425.88  5829.1  422.51  6184.1   411.7
#Mann= 8 ,-1 , 0
  4404.6     .16       0  4588.9     .05       0  4952.2    .035       0
  5052.2     .05       0  5202.2     .16       0  5309.1     .05       0
  5450.7      .1       0  5829.1     .05       0
Bank Sta=4962.2,5042.2
XS Rating Curve= 0 ,0
Exp/Cntr=0.3,0.1

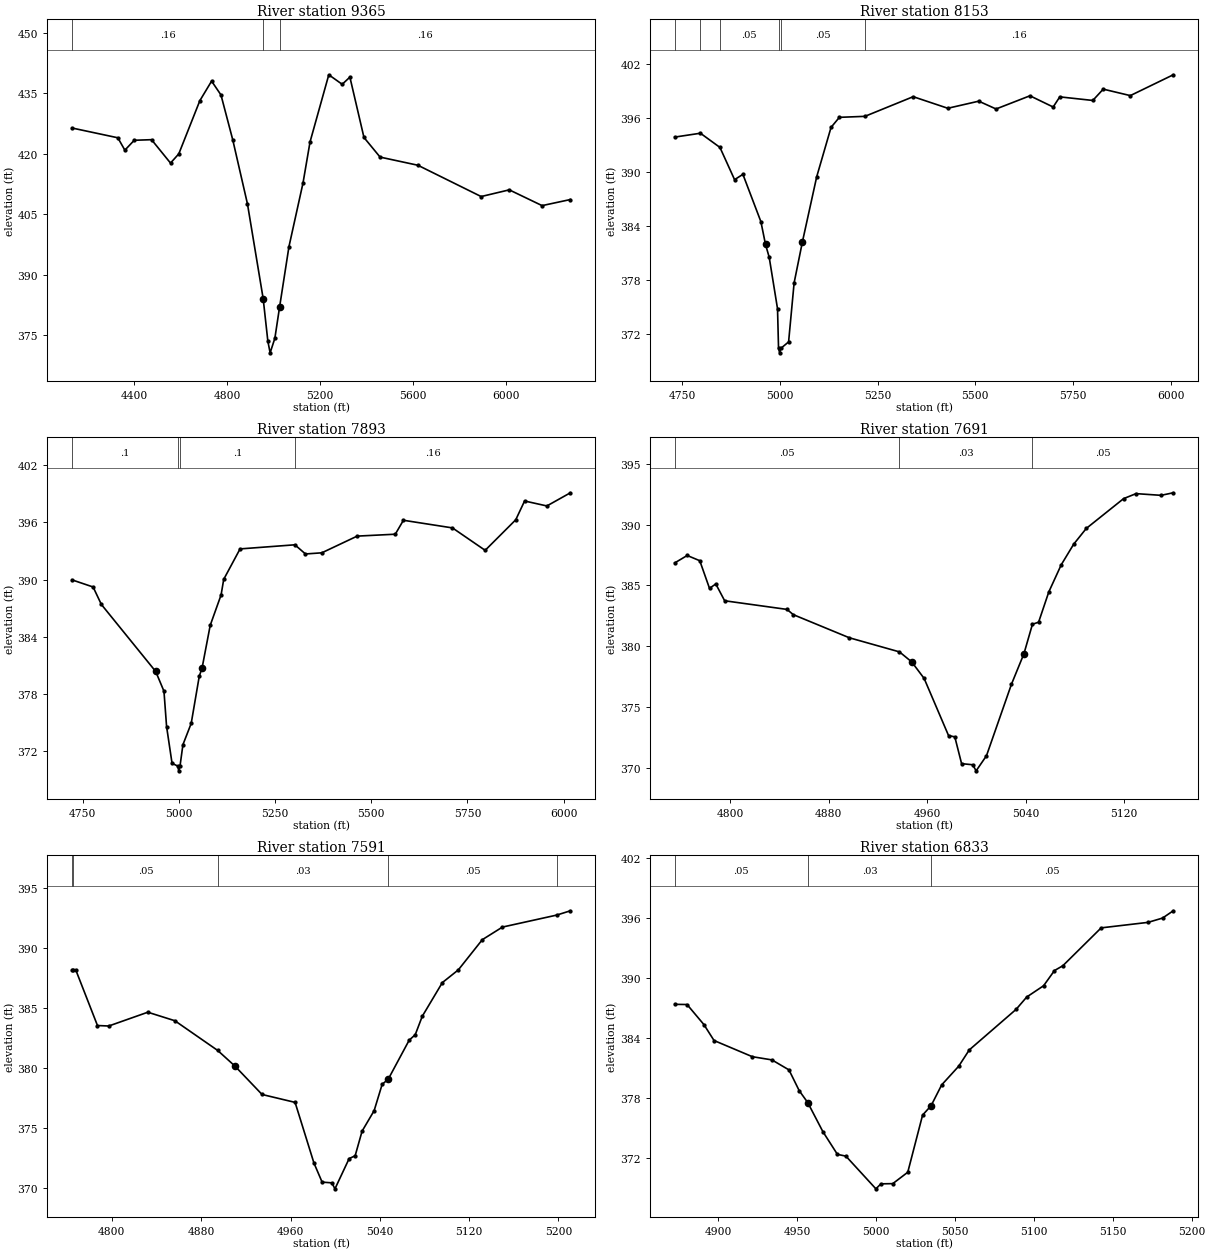
Type RM Length L Ch R = 1 ,9365    ,5711,5711,5711
BEGIN DESCRIPTION:
HEADS CREEK 7.0
END DESCRIPTION:
XS GIS Cut Line= 2
      3502596.15     10458718.11      3504722.86     10458457.69
#Sta/Elev= 30
  4133.2  426.42  4330.6  423.99  4360.8  420.92  4401.1  423.37  4475.5  423.52
    4557  417.72  4592.6     420  4683.2   433.2  4733.6  438.04  4773.9  434.61
  4824.3  423.54  4887.7  407.61  4955.3   384.1  4975.4  373.56  4985.2  370.67
  5005.6   374.3  5025.8  382.02  5066.1     397  5126.5  412.78  5156.7  422.96
  5237.3  439.61  5294.9  437.25    5328  439.03  5388.5  424.06  5457.8   419.2
  5620.2  417.18  5892.2  409.42  6013.1  411.08  6154.1  407.17  6275.8  408.68
#Mann= 3 , 0 , 0
  4133.2     .16       0  4955.3     .07       0  5025.8     .16       0
Bank Sta=4955.3,5025.8
XS Rating Curve= 0 ,0
Exp/Cntr=0.3,0.1

Type RM Length L Ch R = 1 ,8153    ,260,260,260
BEGIN DESCRIPTION:
Mapping XS 0b988b93
END DESCRIPTION:
XS GIS Cut Line= 3
      3503895.21     10459756.26      3504702.54     10459252.76
      3504802.03     10458945.64
#Sta/Elev= 30
  4731.7  393.88  4797.3  394.31  4847.2  392.73  4884.6  389.14  4905.9  389.73
  4951.9  384.46  4963.7  381.92  4973.1   380.5  4994.4  374.76    4997  370.35
  4999.8  369.85    5003  370.35  5022.7  371.07  5036.8  377.64  5058.1  382.23
  5094.6  389.47  5131.2  394.96  5152.5  396.08  5217.8  396.19  5341.2  398.38
  5429.7  397.09  5508.8  397.88    5553  397.01  5639.7  398.48    5699  397.23
  5715.9  398.36  5800.3  397.96    5827  399.22  5896.2   398.5    6006  400.82
#Mann= 6 ,-1 , 0
  4731.7      .1       0  4797.3     .16       0  4847.2     .05       0
    4997     .03       0    5003     .05       0  5217.8     .16       0
Bank Sta=4963.7,5058.1
XS Rating Curve= 0 ,0
Exp/Cntr=0.3,0.1

Type RM Length L Ch R = 1 ,7893    ,202,202,202
BEGIN DESCRIPTION:
Mapping XS bb607c54
END DESCRIPTION:
XS GIS Cut Line= 3
      3504133.94     10459951.57       3504923.9      10459213.7
      3504954.28     10459001.02
#Sta/Elev= 30
    4722  389.98  4777.1  389.23  4798.6   387.4  4939.8  380.38  4961.3  378.31
  4968.1  374.61  4982.3  370.76    4997  370.47  4999.8  369.97    5003  370.47
  5010.6  372.71  5032.1  374.94  5053.1  379.89  5060.4  380.75  5081.5  385.21
  5109.8   388.4  5116.6  390.03  5159.1  393.22  5301.6  393.65  5329.1  392.69
  5371.6  392.81  5463.5  394.56  5562.6  394.76  5583.7  396.22  5711.2  395.42
  5796.2  393.07  5875.7  396.27  5898.7  398.24  5956.6  397.72  6017.8   399.1
#Mann= 4 ,-1 , 0
    4722      .1       0    4997     .07       0    5003      .1       0
  5301.6     .16       0
Bank Sta=4939.8,5060.4
XS Rating Curve= 0 ,0
Exp/Cntr=0.3,0.1

Type RM Length L Ch R = 1 ,7691    ,100,100,100
BEGIN DESCRIPTION:
Mapping XS 3fa0ae80
END DESCRIPTION:
XS GIS Cut Line= 2
3504571.8619677810460031.6690423      3504509.87     10459631.85
#Sta/Elev= 30
  4755.2  386.85  4765.3  387.46  4775.5  387.03  4783.4  384.76  4788.5  385.12
  4795.7  383.74  4846.3  383.03  4851.4   382.6  4896.9   380.7  4937.6  379.54
  4947.5  378.72  4957.6  377.36  4977.4  372.67  4982.5  372.56    4988  370.36
    4997  370.27  4999.8  369.77  5008.2  371.01  5028.5  376.89  5038.6  379.39
  5045.5  381.81  5050.5  381.98  5058.8  384.47  5068.9   386.7    5079  388.39
  5089.2  389.68  5119.5  392.13  5129.6  392.54  5149.9   392.4  5159.8  392.61
#Mann= 3 ,-1 , 0
  4755.2     .05       0  4937.6     .03       0  5045.5     .05       0
Bank Sta=4947.5,5038.6
XS Rating Curve= 0 ,0
Exp/Cntr=0.3,0.1

Type RM Length L Ch R = 1 ,7591    ,758,758,758
BEGIN DESCRIPTION:
Mapping XS 3fa0a
END DESCRIPTION:
XS GIS Cut Line= 2
      3504721.13     10460002.92      3504555.12     10459588.43
#Sta/Elev= 30
  4764.2  388.17  4765.4  388.17  4767.6  388.17  4787.1  383.52  4797.2  383.48
  4832.2  384.63  4856.4  383.92  4894.8  381.44  4910.3  380.13  4934.5  377.77
  4964.1  377.11    4981  372.05  4988.3  370.46    4997   370.4  4999.8   369.9
  5012.5  372.42  5017.9  372.66  5024.1  374.71  5034.9  376.42  5042.1  378.62
  5047.5  379.04  5066.3   382.3  5071.7  382.75    5078  384.29    5096   387.1
  5110.3  388.16  5131.8  390.68  5149.8  391.73  5198.4  392.73  5210.7  393.09
#Mann= 5 ,-1 , 0
  4764.2     .16       0  4765.4     .05       0  4894.8     .03       0
  5047.5     .05       0  5198.4      .1       0
Bank Sta=4910.3,5047.5
XS Rating Curve= 0 ,0
Exp/Cntr=0.3,0.1

Type RM Length L Ch R = 1 ,6833    ,599,599,599
BEGIN DESCRIPTION:
Mapping XS 95af9b8e
END DESCRIPTION:
XS GIS Cut Line= 2
      3505366.72     10459588.86      3505249.76      10459295.3
#Sta/Elev= 30
  4872.3  387.37  4880.1  387.35  4890.8  385.34  4897.2  383.75  4921.5  382.13
  4933.9  381.81  4944.7  380.81  4951.2  378.73  4956.6  377.54  4966.2  374.63
  4975.4  372.36  4980.8  372.18  4999.8  368.91    5003  369.41  5010.5  369.43
    5020  370.57  5029.4  376.29  5034.8  377.23  5041.5  379.31  5052.3  381.18
    5059  382.81  5088.7  386.87  5095.4   388.1  5106.1  389.23    5113  390.75
  5118.3  391.23  5142.6  395.02  5172.3  395.57  5181.5     396  5188.3  396.73
#Mann= 3 , 0 , 0
  4872.3     .05       0  4956.6     .03       0  5034.8     .05       0
Bank Sta=4956.6,5034.8
XS Rating Curve= 0 ,0
Exp/Cntr=0.3,0.1

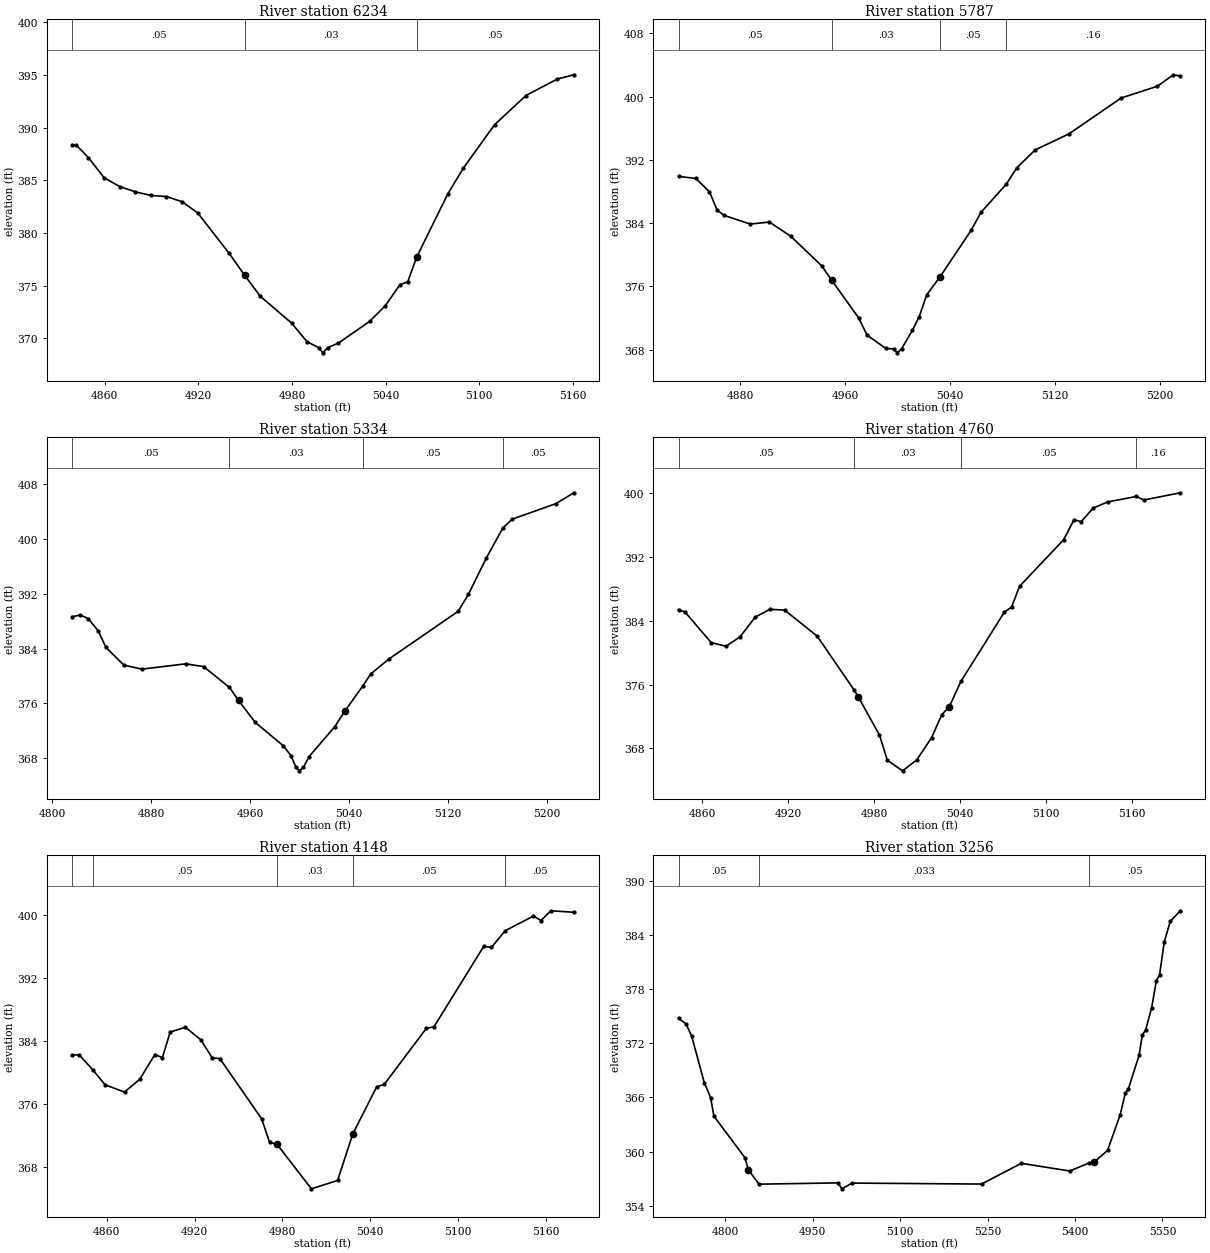
Type RM Length L Ch R = 1 ,6234    ,447,447,447
BEGIN DESCRIPTION:
Mapping XS e7ce486c
END DESCRIPTION:
XS GIS Cut Line= 2
      3505906.38     10459512.13      3505892.49     10459190.93
#Sta/Elev= 30
  4839.1  388.32  4841.9  388.32  4849.6  387.14  4859.6  385.24  4869.6   384.4
  4879.6   383.9  4889.6  383.55  4899.6  383.45  4909.7  382.95  4919.7  381.88
  4939.7  378.06  4949.7  375.97  4959.7  373.98  4979.7  371.44  4989.7  369.66
    4997  369.11  4999.8  368.61    5003  369.11  5009.8  369.54  5029.8   371.6
  5039.8  373.09  5049.2  375.08  5054.2  375.36  5059.8  377.67  5079.8  383.69
  5089.8  386.15  5109.8  390.27  5129.9  393.04  5149.9   394.6  5160.6  395.01
#Mann= 3 , 0 , 0
  4839.1     .05       0  4949.7     .03       0  5059.8     .05       0
Bank Sta=4949.7,5059.8
XS Rating Curve= 0 ,0
Exp/Cntr=0.3,0.1

Type RM Length L Ch R = 1 ,5787    ,453,453,453
BEGIN DESCRIPTION:
Mapping XS d4bff364
END DESCRIPTION:
XS GIS Cut Line= 2
      3506289.18      10459444.4      3506389.37     10459074.74
#Sta/Elev= 30
  4832.8  389.92    4846  389.65  4856.4  387.97  4862.3  385.65  4867.5  384.99
  4887.5  383.89  4902.2  384.14  4918.5  382.34    4942  378.62  4949.6  376.81
  4970.3  372.02  4976.7  369.85  4991.1  368.16    4997  368.11  4999.8  367.61
    5003  368.11  5011.3  370.45  5016.5  372.18  5022.2  374.93  5032.5  377.25
  5056.3  383.14  5063.6  385.36  5082.9  388.92    5091     391    5105  393.26
  5130.8  395.29  5170.6  399.82  5198.3  401.31  5210.5  402.76  5215.8  402.59
#Mann= 4 ,-1 , 0
  4832.8     .05       0  4949.6     .03       0  5032.5     .05       0
  5082.9     .16       0
Bank Sta=4949.6,5032.5
XS Rating Curve= 0 ,0
Exp/Cntr=0.3,0.1

Type RM Length L Ch R = 1 ,5334    ,574,574,574
BEGIN DESCRIPTION:
Mapping XS 704a2a9b
END DESCRIPTION:
XS GIS Cut Line= 2
       3506590.4     10459688.31      3506836.66     10459366.02
#Sta/Elev= 30
    4816  388.64  4822.6  388.88  4828.9  388.38    4837  386.62  4843.4  384.16
  4857.9  381.58  4872.4     381  4907.8  381.77  4922.3  381.37  4943.1  378.35
  4950.6  376.43    4964  373.24  4986.7  369.83    4993  368.37    4997  366.67
  4999.8  366.17    5003  366.67  5007.5  368.23  5028.4  372.62  5036.6  374.91
  5050.9  378.52  5057.4  380.29  5071.9  382.45  5128.1  389.43  5136.4  391.91
  5150.9  397.23  5164.2  401.57  5171.7  402.86    5207  405.12  5221.6  406.71
#Mann= 4 ,-1 , 0
    4816     .05       0  4943.1     .03       0  5050.9     .05       0
  5164.2     .05       0
Bank Sta=4950.6,5036.6
XS Rating Curve= 0 ,0
Exp/Cntr=0.3,0.1

Type RM Length L Ch R = 1 ,4760    ,612,612,612
BEGIN DESCRIPTION:
Mapping XS 378e9d88
END DESCRIPTION:
XS GIS Cut Line= 2
      3507166.79     10459973.91      3507242.74     10459632.15
#Sta/Elev= 30
  4843.5  385.42    4848  385.12  4866.3  381.28  4876.6  380.82  4886.4     382
    4897  384.48  4907.3  385.46  4917.5  385.36  4940.2   382.1  4965.9  375.36
  4968.8   374.5  4983.7  369.67  4989.2  366.52  4999.8  365.19  5009.7  366.56
    5020  369.33  5027.2  372.25  5032.3   373.2  5040.5  376.41  5070.8  385.09
  5075.9  385.75  5081.4  388.34  5112.2  394.19  5119.4  396.69  5124.5  396.46
  5132.7  398.15  5142.9  398.93    5163  399.62  5168.1  399.17  5193.6  400.08
#Mann= 4 ,-1 , 0
  4843.5     .05       0  4965.9     .03       0  5040.5     .05       0
    5163     .16       0
Bank Sta=4968.8,5032.3
XS Rating Curve= 0 ,0
Exp/Cntr=0.3,0.1

Type RM Length L Ch R = 1 ,4148    ,892,892,892
BEGIN DESCRIPTION:
Mapping XS f5f3cc82
END DESCRIPTION:
XS GIS Cut Line= 2
      3507760.32     10460066.13      3507853.58     10459736.47
#Sta/Elev= 30
  4836.4  382.22  4841.3  382.22  4850.4  380.36    4859  378.42  4872.2   377.5
  4882.6  379.12  4892.9  382.27  4898.1  381.89  4903.4  385.14  4913.8  385.74
  4924.2  384.17  4932.1  381.85  4937.3  381.76  4965.8  374.11  4971.2  371.14
  4976.4  370.84  4999.8  365.19  5017.7  366.26  5028.1  372.19  5044.4  378.17
  5049.6  378.49  5078.3  385.61  5083.5   385.8  5117.5  396.05  5122.7  395.89
  5132.1  398.02  5151.4  399.89  5156.6  399.32  5163.2  400.56    5179  400.37
#Mann= 5 ,-1 , 0
  4836.4     .16       0  4850.4     .05       0  4976.4     .03       0
  5028.1     .05       0  5132.1     .05       0
Bank Sta=4976.4,5028.1
XS Rating Curve= 0 ,0
Exp/Cntr=0.3,0.1

Type RM Length L Ch R = 1 ,3256    ,0,0,0
BEGIN DESCRIPTION:
HEADS CREEK 1.0
END DESCRIPTION:
XS GIS Cut Line= 2
      3508533.84     10460402.48      3508861.74     10459606.15
#Sta/Elev= 30
  4719.5  374.79  4732.4  374.16    4742  372.82  4763.7  367.64  4774.5  365.99
  4780.2  363.93  4833.5  359.31  4839.4  357.98  4857.5  356.38  4993.4  356.52
  4999.8  355.86  5017.4   356.5  5239.5  356.39  5307.8  358.69  5390.9  357.84
  5423.4  358.71    5433  358.84  5455.8  360.12  5477.4  364.07  5486.3  366.47
  5491.7  366.98  5509.9  370.68  5515.6  372.97    5521  373.46  5531.5  375.96
  5539.6  378.98    5545  379.58  5553.1  383.25  5563.5  385.56  5580.7  386.72
#Mann= 3 ,-1 , 0
  4719.5     .05       0  4857.5    .033       0  5423.4     .05       0
Bank Sta=4839.4,5433
XS Rating Curve= 0 ,0
Exp/Cntr=0.3,0.1

Chan Stop Cuts=-1
Use User Specified Reach Order=0
Composite Channel Slope=5