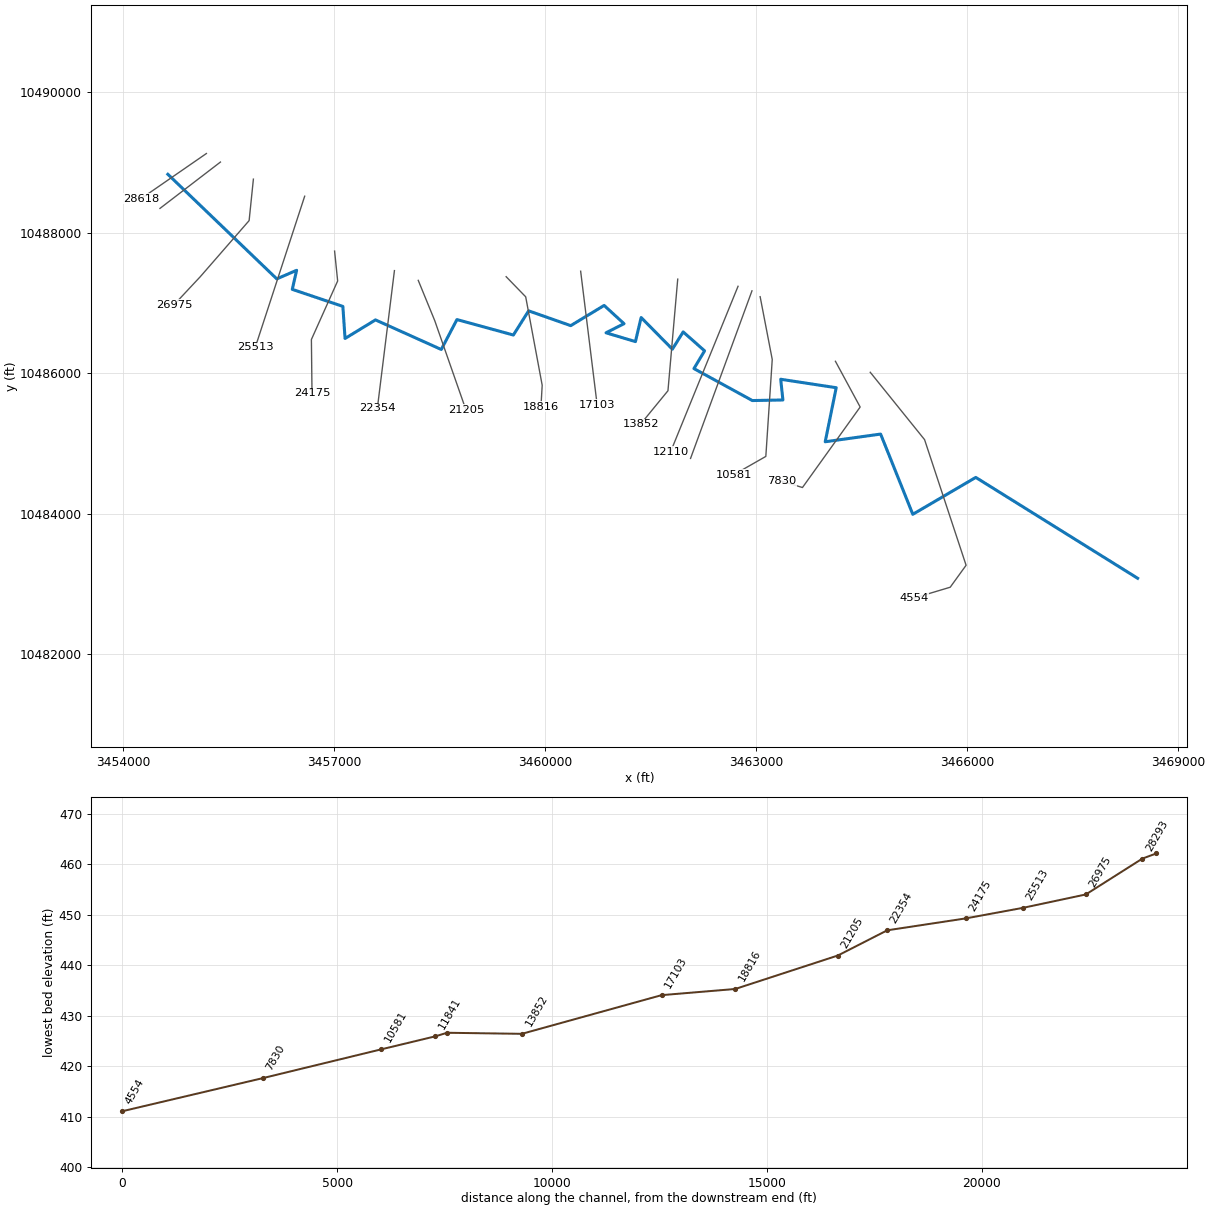
--- MILLS CREEK.prj (project) ---

Proj Title=MILLS CREEK Base Level Engineering
Current Plan=p01
Default Exp/Contr=0.3,0.1
English Units
Geom File=g01
Flow File=f01
Plan File=p01
Y Axis Title=Elevation
X Axis Title(PF)=Main Channel Distance
X Axis Title(XS)=Station
BEGIN DESCRIPTION:
MILLS CREEK
END DESCRIPTION:
DSS Export Rating Curves= 0
DSS Export Rating Curve Sorted= 0
DSS Export Volume Flow Curves= 0
DXF OffsetX= 0
DXF OffsetY= 0
DXF ScaleX= 1
DXF ScaleY= 10

--- MILLS CREEK.p01 (plan) ---

Plan Title=Multiple Run
Short Identifier=Multiple
Geom File=g01
Flow File=f01
Subcritical Flow
K Sum by GR= 0
Std Step Tol= 0.01
Critical Tol= 0.01
Num of Std Step Trials= 20
Max Error Tol= 0.3
Flow Tol Ratio= 0.001
Split Flow NTrial= 30
Split Flow Tol= 0.02
Split Flow Ratio= 0.02
Log Output Level= 0
Friction Slope Method= 1
Unsteady Friction Slope Method= 2
Unsteady Bridges Friction Slope Method= 1
Parabolic Critical Depth
Global Vel Dist=  1 , 1 , 1
Global Log Level= 0
CheckData=True
Encroach Param= -1, 0, 0, 0
BEGIN DESCRIPTION:
Multiple Run
END DESCRIPTION:

--- MILLS CREEK.f01 (steady flow) ---

Flow Title=Multiple
Program Version=4.10
Number of Profiles= 7
Profile Names=10-year,25-year,50-year,1pct_min,100-year,1pct_plu,500-year
River Rch & RM=MILLS CREEK,Reach-1         ,28618
     780    1058    1285    1139    1540    2082    2206
River Rch & RM=MILLS CREEK,Reach-1         ,26975
    1747    2464    3068    2780    3759    5084    5636
River Rch & RM=MILLS CREEK,Reach-1         ,13852
    1732    2433    3021    2729    3690    4990    5498
River Rch & RM=MILLS CREEK,Reach-1         ,11841
    2055    2905    3621    3281    4437    6000    6652
Boundary for River Rch & Prof#=MILLS CREEK,Reach-1         , 1
Up Type= 0
Dn Type= 3
Dn Slope=0.002
Boundary for River Rch & Prof#=MILLS CREEK,Reach-1         , 2
Up Type= 0
Dn Type= 3
Dn Slope=0.002
Boundary for River Rch & Prof#=MILLS CREEK,Reach-1         , 3
Up Type= 0
Dn Type= 3
Dn Slope=0.002
Boundary for River Rch & Prof#=MILLS CREEK,Reach-1         , 4
Up Type= 0
Dn Type= 3
Dn Slope=0.002
Boundary for River Rch & Prof#=MILLS CREEK,Reach-1         , 5
Up Type= 0
Dn Type= 3
Dn Slope=0.002
Boundary for River Rch & Prof#=MILLS CREEK,Reach-1         , 6
Up Type= 0
Dn Type= 3
Dn Slope=0.002
Boundary for River Rch & Prof#=MILLS CREEK,Reach-1         , 7
Up Type= 0
Dn Type= 3
Dn Slope=0.002
DSS Import GetInterval= 0
DSS Import GetPeak= 0
DSS Import FillOption= 0

--- MILLS CREEK.g01 (geometry) ---

Geom Title=Existing Conditions
Program Version=4.10

River Reach=MILLS CREEK     ,Reach-1
Reach XY= 30
      3454633.98     10488832.42      3456182.96     10487343.28
      3456465.11     10487465.69      3456403.08     10487194.22
      3457122.34     10486951.53      3457153.55     10486494.97
      3457586.25     10486759.33      3458521.83     10486338.15
       3458744.4     10486764.22      3459546.37     10486544.21
      3459763.67     10486888.33      3460361.85     10486677.67
      3460837.05     10486965.12      3461119.77     10486705.65
      3460863.96     10486575.73      3461281.93     10486450.37
      3461363.09     10486793.25      3461807.39     10486342.28
      3461960.72      10486588.5        3462265.     10486319.29
      3462113.96     10486066.25      3462944.26     10485611.39
      3463378.68     10485619.59      3463347.47     10485914.34
      3464136.53     10485794.12      3463980.23     10485024.66
      3464767.94     10485134.17      3465225.67     10483992.03
      3466120.98     10484517.33      3468422.11     10483081.64

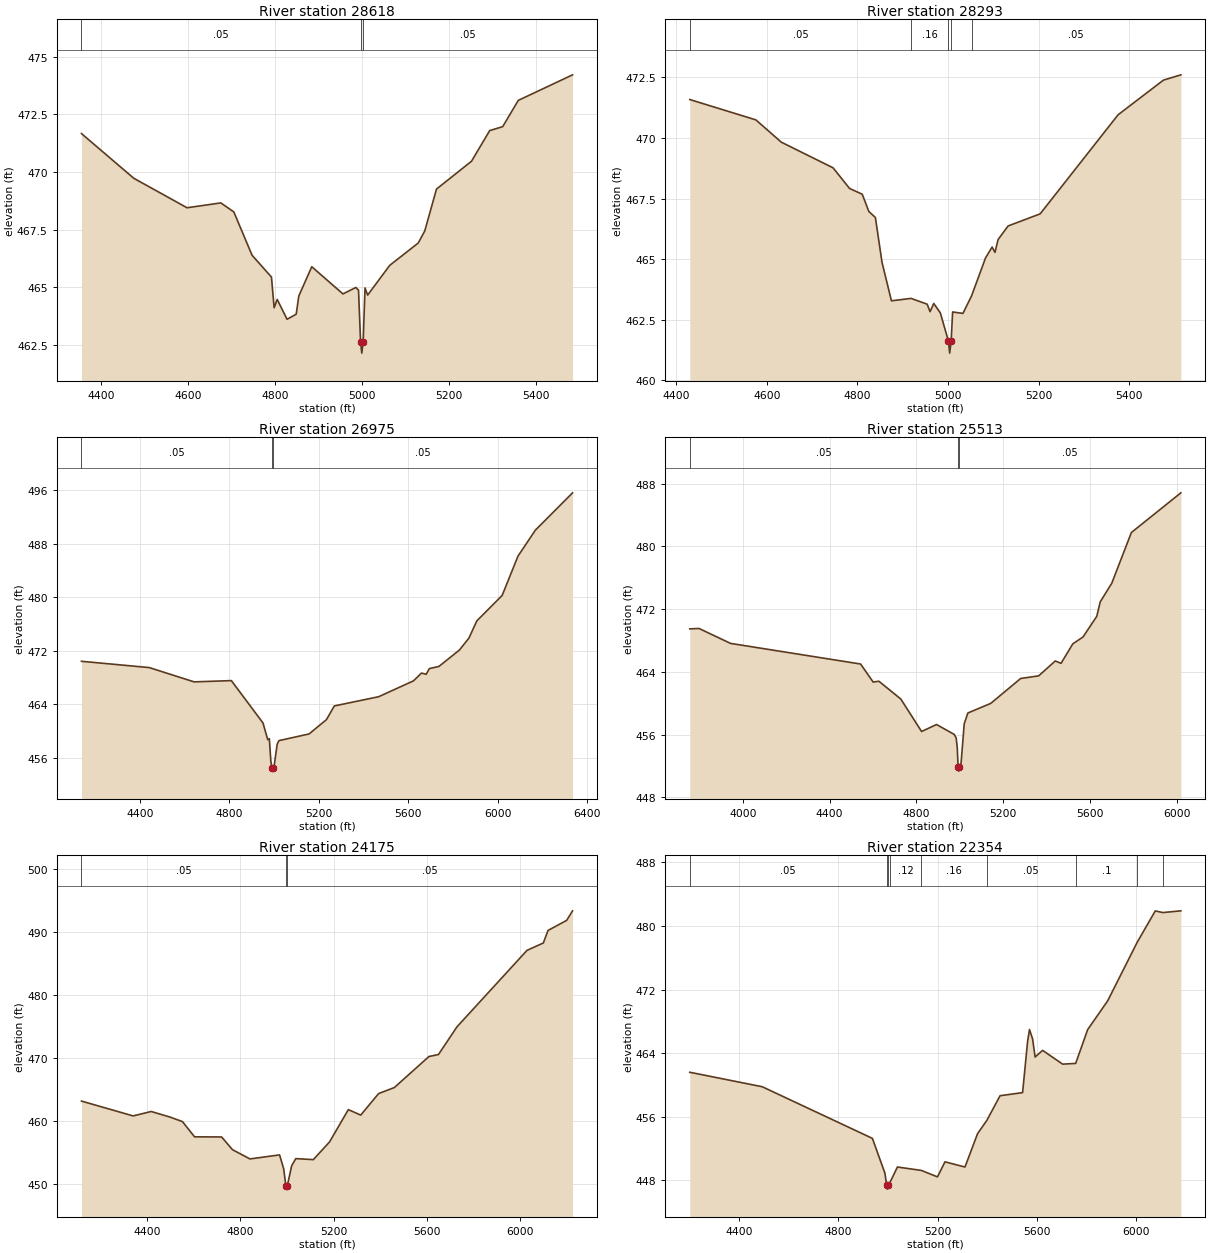
Type RM Length L Ch R = 1 ,28618   ,325,325,325
BEGIN DESCRIPTION:
MILLS CREEK 40.0
END DESCRIPTION:
XS GIS Cut Line= 2
      3455181.94      10489127.8      3454254.03     10488486.07
#Sta/Elev= 30
  4355.6  471.67  4475.8  469.73  4598.1  468.45  4675.8  468.66  4705.6  468.27
  4747.5  466.39  4792.1  465.44  4798.2  464.11  4805.3  464.47  4827.9  463.61
  4848.9  463.83  4854.9  464.62  4884.7  465.89  4956.3  464.71  4986.1  464.99
  4992.1  464.87  4996.8  462.64  4999.6  462.14  5002.8  462.64    5007  464.97
  5013.1  464.66  5063.8  465.95  5129.3  466.92  5144.2  467.44  5171.2  469.26
  5251.7  470.47  5293.5   471.8  5323.3  471.97  5359.1  473.11  5483.8  474.22
#Mann= 3 ,-1 , 0
  4355.6     .05       0  4996.8     .03       0  5002.8     .05       0
Bank Sta=4996.8,5002.8
XS Rating Curve= 0 ,0
Exp/Cntr=0.3,0.1

Type RM Length L Ch R = 1 ,28293   ,1318,1318,1318
BEGIN DESCRIPTION:
MILLS CREEK 39.0
END DESCRIPTION:
XS GIS Cut Line= 2
      3455381.62      10489006.3      3454522.25     10488346.57
#Sta/Elev= 30
  4430.1  471.59  4575.9  470.75    4632  469.83  4746.3  468.77  4782.5  467.92
  4810.6  467.68  4825.1  466.97  4839.6  466.72  4854.2  464.87    4875  463.28
  4918.3  463.38  4953.9  463.14  4960.2  462.83  4968.4  463.17  4982.9  462.78
  5000.7  461.62  5003.5  461.12  5006.7  461.62    5010  462.82  5032.7  462.76
  5051.7  463.48  5082.6  465.05  5097.1   465.5  5103.4  465.28  5110.3  465.81
  5132.4  466.37  5203.1  466.87    5375  470.96    5475  472.39  5513.5  472.61
#Mann= 5 ,-1 , 0
  4430.1     .05       0  4918.3     .16       0  5000.7     .07       0
  5006.7     .16       0  5051.7     .05       0
Bank Sta=5000.7,5006.7
XS Rating Curve= 0 ,0
Exp/Cntr=0.3,0.1

Type RM Length L Ch R = 1 ,26975   ,1462,1462,1462
BEGIN DESCRIPTION:
MILLS CREEK 37.0
END DESCRIPTION:
XS GIS Cut Line= 4
      3455850.35     10488763.19      3455789.59     10488172.95
      3455095.14     10487374.34      3454722.62     10486975.82
#Sta/Elev= 30
  4138.1  470.44  4441.2   469.5  4642.3  467.36  4808.8  467.55  4950.2  461.22
  4971.7   458.7  4978.7  458.87  4985.3  455.53    4990  454.51  4992.7  454.01
    4996  454.51  4999.6  454.66  5013.8  458.04  5021.5  458.57  5156.3  459.57
  5234.2  461.71  5269.3  463.76  5467.7  465.14  5623.4  467.51  5659.5  468.68
  5680.4   468.5  5694.7  469.35  5737.4  469.67  5829.3  472.13  5871.8  473.92
  5906.9  476.48  6020.3  480.29  6091.1  486.17  6168.8  490.05  6335.3  495.64
#Mann= 3 ,-1 , 0
  4138.1     .05       0    4990    .035       0    4996     .05       0
Bank Sta=4990,4996
XS Rating Curve= 0 ,0
Exp/Cntr=0.3,0.1

Type RM Length L Ch R = 1 ,25513   ,1338,1338,1338
BEGIN DESCRIPTION:
MILLS CREEK 34.0
END DESCRIPTION:
XS GIS Cut Line= 2
      3456579.52     10488520.18      3455876.74     10486368.44
#Sta/Elev= 30
  3755.1  469.49    3798  469.54  3942.9  467.64  4542.6  465.01  4600.4  462.71
  4626.7  462.82  4727.9  460.55  4823.6  456.41  4892.6   457.3  4973.9  456.04
    4983   455.6  4988.2   454.3  4991.9  451.86  4994.7  451.36  4997.9  451.86
  5005.4  452.32  5020.1  457.39    5037  458.77  5142.2  459.99  5280.5  463.17
  5363.1   463.5  5439.9   465.4  5466.5   465.1  5520.9  467.59  5567.4  468.45
  5631.2  471.09  5647.1  472.94  5700.2   475.3  5790.6  481.77  6018.7  486.83
#Mann= 3 ,-1 , 0
  3755.1     .05       0  4991.9     .03       0  4997.9     .05       0
Bank Sta=4991.9,4997.9
XS Rating Curve= 0 ,0
Exp/Cntr=0.3,0.1

Type RM Length L Ch R = 1 ,24175   ,1821,1821,1821
BEGIN DESCRIPTION:
MILLS CREEK 33.0
END DESCRIPTION:
XS GIS Cut Line= 4
      3457004.87     10487738.93      3457048.27     10487313.57
      3456675.01     10486480.24      3456683.69     10485716.46
#Sta/Elev= 30
  4119.6   463.2  4340.9  460.85  4418.4  461.55  4498.8  460.67  4552.4  459.95
  4604.2  457.54  4720.2  457.52  4766.6  455.51  4841.6  454.04  4968.5  454.68
  4986.2  452.48  4995.5  449.76  4998.3  449.26  5001.5  449.76  5020.4  452.96
  5038.1  454.09  5113.1  453.93  5182.7  456.73  5263.2  461.85  5316.3  460.98
    5393  464.39  5460.3  465.34  5608.9  470.26  5649.5  470.57  5728.9  474.96
  6028.9  487.06  6098.9  488.23  6118.9  490.21  6198.9  491.81  6224.1  493.32
#Mann= 3 ,-1 , 0
  4119.6     .05       0  4995.5     .03       0  5001.5     .05       0
Bank Sta=4995.5,5001.5
XS Rating Curve= 0 ,0
Exp/Cntr=0.3,0.1

Type RM Length L Ch R = 1 ,22354   ,1149,1149,1149
BEGIN DESCRIPTION:
MILLS CREEK 30.0
END DESCRIPTION:
XS GIS Cut Line= 2
      3457855.57     10487461.18      3457612.51     10485499.38
#Sta/Elev= 30
  4202.2   461.6  4493.9  459.78  4937.3  453.29  4987.7  448.92  4994.8  447.41
  4997.5  446.91  5000.8  447.41    5007  447.68  5038.1  449.69  5134.5  449.26
  5199.3  448.45  5229.5  450.34  5310.1  449.69  5360.5  453.87    5398  455.55
  5451.2  458.65  5541.9  459.04  5562.1  465.48  5569.7  466.97  5582.2  465.79
  5592.3  463.52  5622.5  464.35  5703.1  462.62  5755.6  462.71  5803.9  466.96
  5884.5  470.58  6002.8  477.91    6076  481.88  6106.5  481.67    6179  481.89
#Mann= 9 ,-1 , 0
  4202.2     .05       0  4994.8    .035       0  5000.8     .05       0
    5007     .12       0  5134.5     .16       0    5398     .05       0
  5755.6      .1       0  6002.8     .05       0  6106.5      .1       0
Bank Sta=4994.8,5000.8
XS Rating Curve= 0 ,0
Exp/Cntr=0.3,0.1

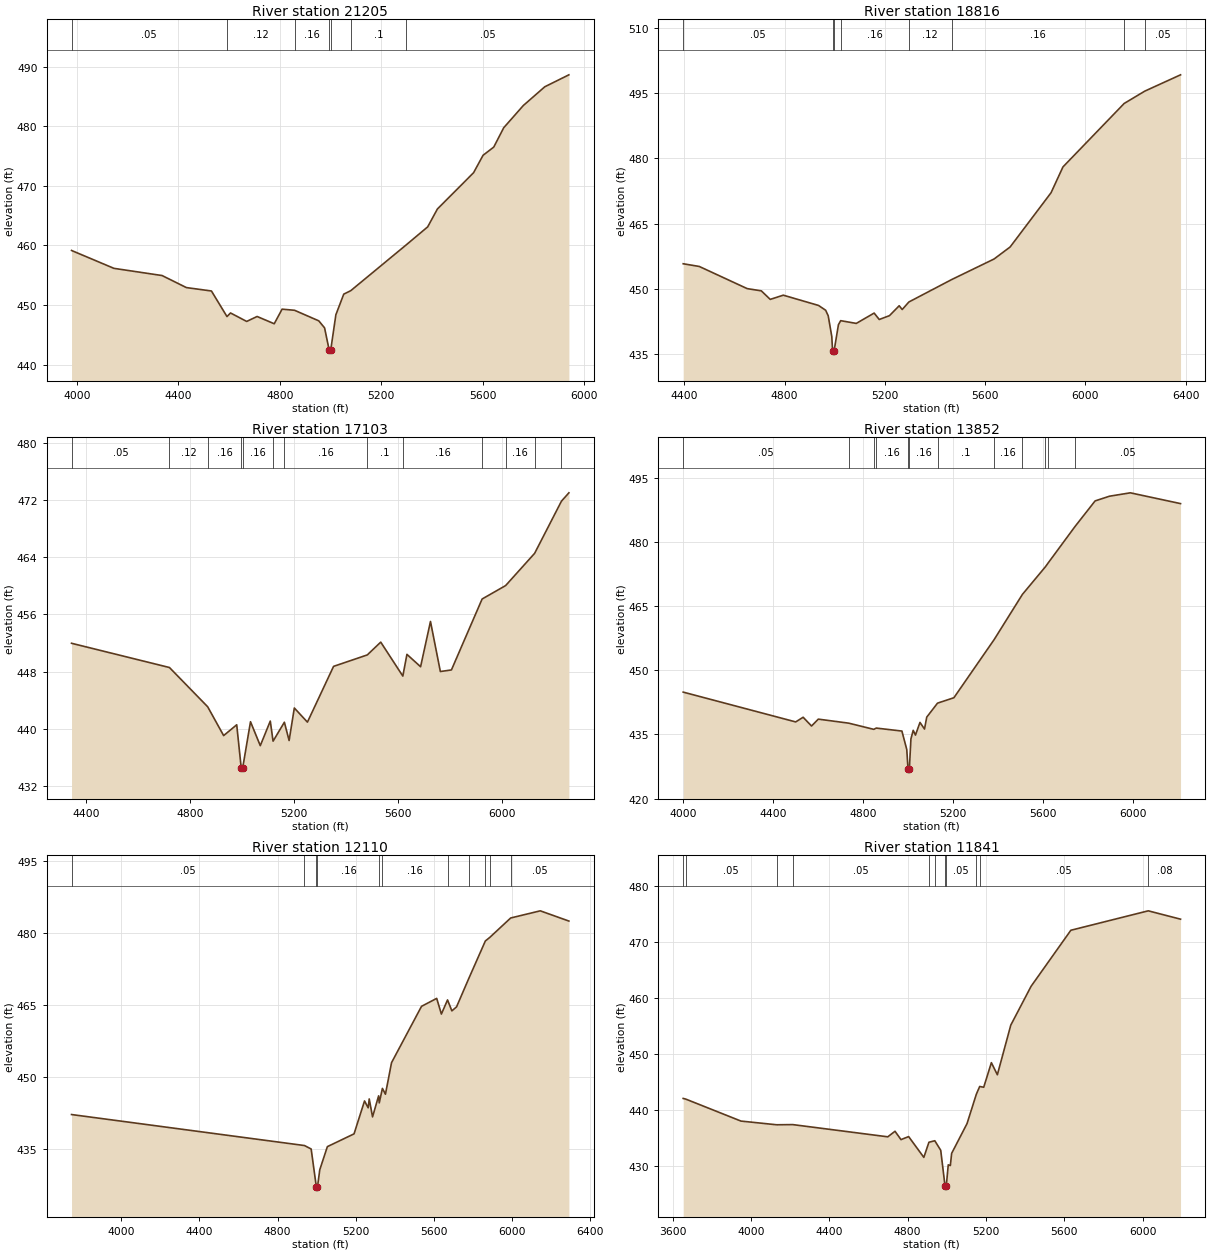
Type RM Length L Ch R = 1 ,21205   ,2389,2389,2389
BEGIN DESCRIPTION:
MILLS CREEK 26.0
END DESCRIPTION:
XS GIS Cut Line= 3
      3458194.11     10487322.23      3458428.48     10486749.34
      3458871.17     10485482.01
#Sta/Elev= 30
  3979.1  459.15  4146.3  456.15  4336.3  454.94  4432.1  452.92  4530.8  452.35
  4592.1  448.06  4606.2  448.66  4669.8  447.24    4711  448.07  4778.4  446.85
  4809.5   449.3  4858.7  449.11  4954.1  447.34    4977  446.16  4995.2  442.42
  4997.9  441.92  5001.2  442.42  5021.5  448.35  5052.6  451.82  5080.2   452.4
  5297.3  460.03  5383.6  463.11  5421.9  466.11  5564.6   472.2  5601.9  475.12
  5644.3  476.51  5683.5  479.75  5760.8  483.48  5845.6  486.63  5940.5  488.63
#Mann= 7 ,-1 , 0
  3979.1     .05       0  4592.1     .12       0  4858.7     .16       0
  4995.2     .07       0  5001.2     .16       0  5080.2      .1       0
  5297.3     .05       0
Bank Sta=4995.2,5001.2
XS Rating Curve= 0 ,0
Exp/Cntr=0.3,0.1

Type RM Length L Ch R = 1 ,18816   ,1713,1713,1713
BEGIN DESCRIPTION:
MILLS CREEK 21.0
END DESCRIPTION:
XS GIS Cut Line= 4
      3459444.07     10487374.37      3459721.88     10487087.88
      3459956.26      10485829.2      3459938.93     10485525.98
#Sta/Elev= 30
  4395.9   455.8  4460.1  455.18  4650.9   450.1  4707.5  449.58    4743  447.62
    4795  448.59  4935.7  446.23  4964.1  445.12  4974.2  443.85  4988.4   439.1
  4991.6  435.79  4994.3  435.29  4997.6  435.79  5014.9  441.81  5023.9  442.74
  5086.1  442.11  5157.3  444.48  5177.7  443.01  5218.4  443.89  5257.2  446.16
  5269.2   445.3  5295.9  447.03  5466.7  452.18  5635.4  456.89  5699.5  459.65
  5862.8  472.11  5910.1  478.02  6154.3  492.59  6236.5  495.42    6379  499.16
#Mann= 8 ,-1 , 0
  4395.9     .05       0  4991.6    .035       0  4997.6     .05       0
  5023.9     .16       0  5295.9     .12       0  5466.7     .16       0
  6154.3      .1       0  6236.5     .05       0
Bank Sta=4991.6,4997.6
XS Rating Curve= 0 ,0
Exp/Cntr=0.3,0.1

Type RM Length L Ch R = 1 ,17103   ,3251,3251,3251
BEGIN DESCRIPTION:
MILLS CREEK 20.0
END DESCRIPTION:
XS GIS Cut Line= 2
      3460503.13      10487452.5       3460737.3     10485553.08
#Sta/Elev= 30
  4344.5  451.95  4721.3  448.56  4868.4  443.07  4929.8  439.04  4980.1  440.55
  4997.3  434.57    5000  434.07  5003.3  434.57  5033.2  440.98  5070.8  437.63
  5109.3  441.07    5120  438.26  5163.5  440.91  5181.7  438.35  5201.8   442.9
  5252.2  440.92  5352.8  448.72  5482.5  450.32  5534.3  452.11  5619.3  447.36
  5635.1   450.4  5687.6  448.67  5725.7     455  5763.7     448  5806.3  448.22
  5924.4  458.14  6014.9  460.02  6126.5  464.53  6229.6  471.82  6258.3  472.99
#Mann= 13 ,-1 , 0
  4344.5     .05       0  4721.3     .12       0  4868.4     .16       0
  4997.3     .07       0  5003.3     .16       0    5120     .12       0
  5163.5     .16       0  5482.5      .1       0  5619.3     .16       0
  5924.4     .12       0  6014.9     .16       0  6126.5     .12       0
  6229.6     .16       0
Bank Sta=4997.3,5003.3
XS Rating Curve= 0 ,0
Exp/Cntr=0.3,0.1

Type RM Length L Ch R = 1 ,13852   ,1742,1742,1742
BEGIN DESCRIPTION:
MILLS CREEK 15.0
END DESCRIPTION:
XS GIS Cut Line= 3
      3461883.34     10487339.64      3461744.45     10485751.07
      3461355.02     10485275.11
#Sta/Elev= 30
  4000.5  444.89  4500.4  437.92  4533.4  439.01  4570.7  436.96  4600.8  438.57
  4735.8  437.63  4847.4  436.18  4858.2  436.48  4972.2  435.78  4993.9  431.45
  4999.3  426.91  5002.1  426.41  5005.3  426.91  5012.3  433.95  5022.4  435.95
  5032.4  434.84  5052.5   437.8  5072.6  436.25  5082.6  439.04  5130.4  442.31
  5203.1  443.57  5381.8  457.16  5507.5  467.74    5610  474.22  5622.6  475.14
  5741.1  483.61  5830.6  489.61  5894.5  490.71  5987.1   491.5  6210.1  488.98
#Mann= 12 ,-1 , 0
  4000.5     .05       0  4735.8     .16       0  4847.4     .12       0
  4858.2     .16       0  4999.3     .07       0  5005.3     .16       0
  5130.4      .1       0  5381.8     .16       0  5507.5     .12       0
    5610     .16       0  5622.6      .1       0  5741.1     .05       0
Bank Sta=4999.3,5005.3
XS Rating Curve= 0 ,0
Exp/Cntr=0.3,0.1

Type RM Length L Ch R = 1 ,12110   ,269,269,269
BEGIN DESCRIPTION:
MILLS CREEK 14.0
END DESCRIPTION:
XS GIS Cut Line= 2
      3462740.87     10487237.82      3461781.79     10484881.31
#Sta/Elev= 30
  3745.9  442.14  4937.4  435.69  4971.7  434.97  4998.1  427.12  5000.9  426.62
  5004.1  427.12  5015.8  430.66  5054.6  435.46  5191.1  438.12  5244.7  444.97
  5263.3  443.54  5268.7  445.39  5285.7  441.65  5316.8  446.03  5320.1  444.56
  5336.1  447.58  5351.7  446.37  5382.8  452.93  5536.3  464.66  5613.9  466.31
  5637.9  463.05  5669.3  465.99  5691.5  463.71  5715.5  464.55  5776.9  470.35
  5862.8  478.26  5884.6  478.97  5992.3  483.04  6143.7  484.53  6290.1   482.4
#Mann= 11 ,-1 , 0
  3745.9     .05       0  4937.4     .16       0  4998.1     .07       0
  5004.1     .16       0  5320.1     .12       0  5336.1     .16       0
  5669.3      .1       0  5776.9     .16       0  5862.8      .1       0
  5884.6     .16       0  5992.3     .05       0
Bank Sta=4998.1,5004.1
XS Rating Curve= 0 ,0
Exp/Cntr=0.3,0.1

Type RM Length L Ch R = 1 ,11841   ,1260,1260,1260
BEGIN DESCRIPTION:
MILLS CREEK 13.0
END DESCRIPTION:
XS GIS Cut Line= 2
      3462938.88     10487173.08      3462065.61     10484787.49
#Sta/Elev= 30
  3653.4  442.11  3666.2     442  3948.6  438.07  4130.7  437.41  4213.2  437.44
  4698.5  435.26  4735.4  436.25  4765.9  434.76    4805   435.3  4882.6  431.59
  4908.6  434.29  4938.6  434.56  4968.9  432.85  4991.1  426.42  4993.8  425.92
  4997.1  426.42  5007.3  430.26    5018  430.13  5024.6   432.3  5103.2  437.62
  5150.7  442.86  5167.9  444.25  5188.4  444.11  5227.6   448.5  5258.1  446.34
  5326.8  455.21  5430.5  462.14  5633.5  472.14  6028.9  475.61  6193.8  474.12
#Mann= 11 ,-1 , 0
  3653.4     .08       0  3666.2     .05       0  4130.7     .08       0
  4213.2     .05       0  4908.6     .08       0  4938.6     .05       0
  4991.1     .04       0  4997.1     .05       0  5150.7     .12       0
  5167.9     .05       0  6028.9     .08       0
Bank Sta=4991.1,4997.1
XS Rating Curve= 0 ,0
Exp/Cntr=0.3,0.1

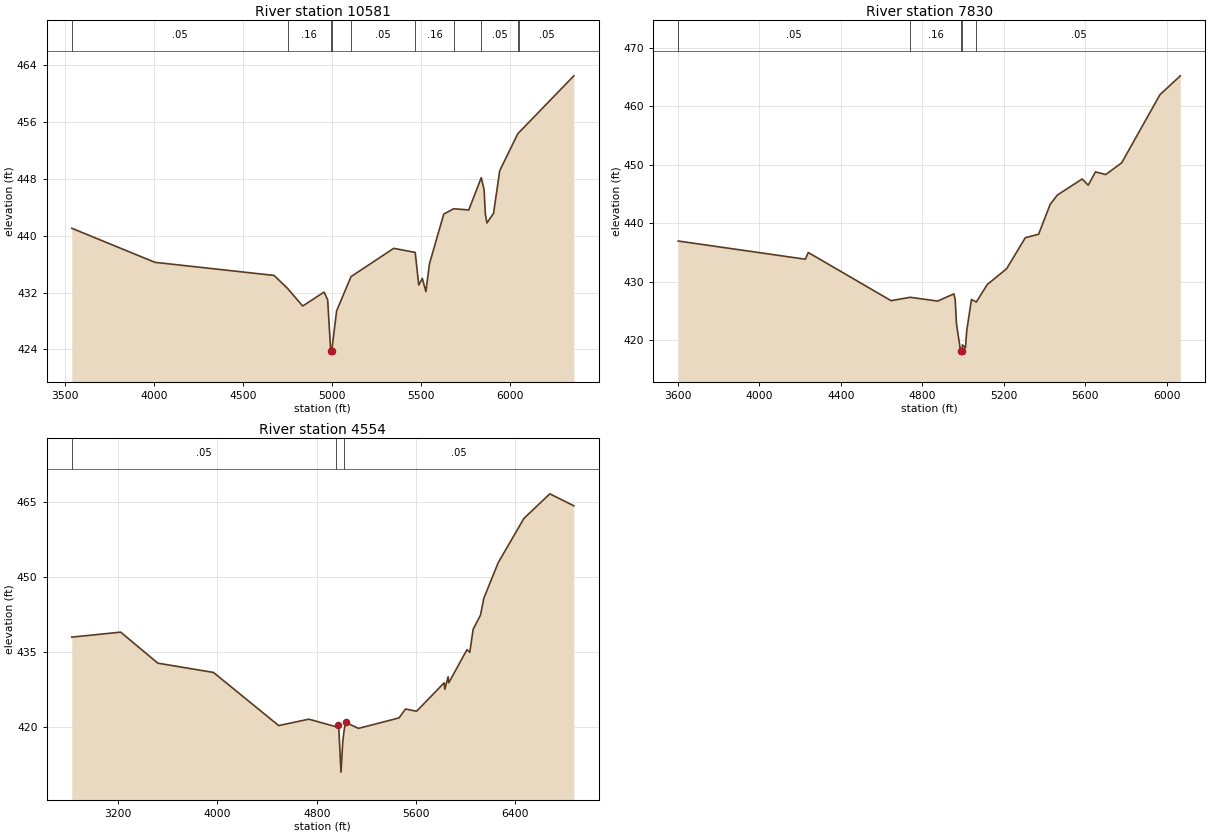
Type RM Length L Ch R = 1 ,10581   ,2751,2751,2751
BEGIN DESCRIPTION:
MILLS CREEK 12.0
END DESCRIPTION:
XS GIS Cut Line= 4
      3463055.04     10487089.95      3463227.09     10486196.39
      3463135.94     10484816.18      3462680.97      10484556.2
#Sta/Elev= 30
  3539.7  441.03  4006.4  436.24  4674.9   434.4  4750.4  432.58  4835.3   430.1
  4955.5  432.06  4975.6  430.98  4992.6  423.84  4995.4  423.34  4998.6  423.84
  5025.7  429.41  5106.6  434.23  5346.4  438.21  5466.8  437.63  5486.7  433.05
  5506.7  433.98  5526.8  432.13  5546.8  436.04    5627  443.02  5682.7  443.77
  5767.3   443.6  5837.4  448.14  5853.3  446.47  5860.3  443.07  5869.2  441.77
  5906.4  443.13    5941  449.12  6042.4  454.31    6050  454.51  6356.9  462.45
#Mann= 10 ,-1 , 0
  3539.7     .05       0  4750.4     .16       0  4992.6     .07       0
  4998.6     .16       0  5106.6     .05       0  5466.8     .16       0
  5682.7      .1       0  5837.4     .05       0  6042.4     .16       0
    6050     .05       0
Bank Sta=4992.6,4998.6
XS Rating Curve= 0 ,0
Exp/Cntr=0.3,0.1

Type RM Length L Ch R = 1 ,7830    ,3276,3276,3276
BEGIN DESCRIPTION:
MILLS CREEK 11.0
END DESCRIPTION:
XS GIS Cut Line= 4
      3464125.51     10486170.37      3464477.09      10485519.3
      3463656.78     10484373.47      3463357.27     10484464.63
#Sta/Elev= 30
  3603.2  436.99  4226.8  433.88  4240.9  435.03  4646.9  426.79  4740.7  427.37
  4875.4  426.72  4955.2  427.96  4961.4  426.97  4967.6  422.87  4987.9  418.15
  4990.7  417.65  4993.9  418.15  4997.1  419.24  5011.8  418.72  5017.9  421.64
  5041.3     427    5065  426.56  5118.7  429.55  5213.3  432.24  5305.4  437.56
  5370.5  438.15    5427  443.25  5462.6  444.86  5584.3   447.6  5613.7  446.54
  5649.4  448.81  5699.7  448.36  5778.1  450.37  5965.2     462  6065.4  465.24
#Mann= 5 ,-1 , 0
  3603.2     .05       0  4740.7     .16       0  4987.9     .07       0
  4993.9     .16       0    5065     .05       0
Bank Sta=4987.9,4993.9
XS Rating Curve= 0 ,0
Exp/Cntr=0.3,0.1

Type RM Length L Ch R = 1 ,4554    ,0,0,0
BEGIN DESCRIPTION:
MILLS CREEK 1.0
END DESCRIPTION:
XS GIS Cut Line= 5
      3464620.33     10486014.08      3465392.89     10485054.89
      3465983.17      10483266.7      3465757.47      10482954.2
       3465236.9     10482798.03
#Sta/Elev= 30
  2826.9  438.03    3221  439.02  3520.1  432.83    3968  430.98  4493.7  420.37
  4735.9  421.65  4957.1  420.13    4969  420.49  4978.1  419.59  4995.3  411.08
  5009.7   417.2  5020.2  419.38  5032.5  421.01  5136.1  419.81  5462.5   421.9
  5515.2  423.68    5604  423.23  5826.2  428.91  5831.5  427.62    5858  430.11
  5863.2  428.91  6009.5  435.51  6032.7     435  6059.8  439.62  6118.6  442.41
  6145.6  445.79  6260.9  452.86  6468.4  461.72  6677.2  466.63  6870.6  464.24
#Mann= 3 ,-1 , 0
  2826.9     .05       0  4957.1     .03       0  5020.2     .05       0
Bank Sta=4969,5032.5
XS Rating Curve= 0 ,0
Exp/Cntr=0.3,0.1

Chan Stop Cuts=-1
Use User Specified Reach Order=0
Composite Channel Slope=5