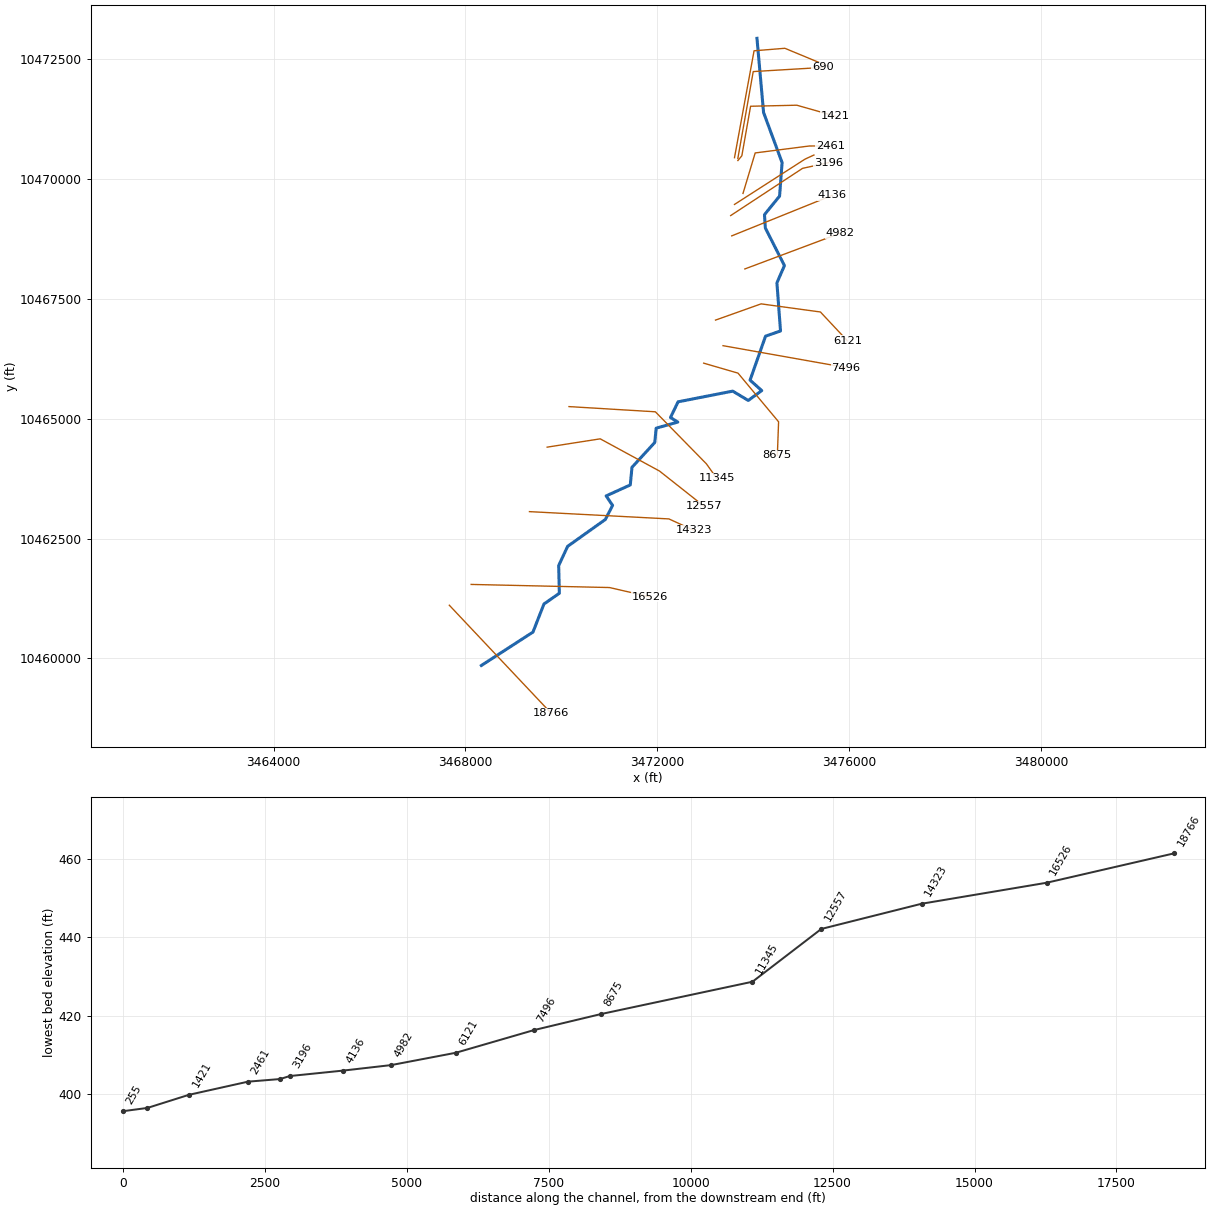
--- MOSS SPRINGS BRANCH.prj (project) ---

Proj Title=MOSS SPRINGS BRANCH Base Level Engineering
Current Plan=p01
Default Exp/Contr=0.3,0.1
English Units
Geom File=g01
Flow File=f01
Plan File=p01
Y Axis Title=Elevation
X Axis Title(PF)=Main Channel Distance
X Axis Title(XS)=Station
BEGIN DESCRIPTION:
MOSS SPRINGS BRANCH
END DESCRIPTION:
DSS Export Rating Curves= 0
DSS Export Rating Curve Sorted= 0
DSS Export Volume Flow Curves= 0
DXF OffsetX= 0
DXF OffsetY= 0
DXF ScaleX= 1
DXF ScaleY= 10

--- MOSS SPRINGS BRANCH.p01 (plan) ---

Plan Title=Multiple Run
Short Identifier=Multiple
Geom File=g01
Flow File=f01
Subcritical Flow
K Sum by GR= 0
Std Step Tol= 0.01
Critical Tol= 0.01
Num of Std Step Trials= 20
Max Error Tol= 0.3
Flow Tol Ratio= 0.001
Split Flow NTrial= 30
Split Flow Tol= 0.02
Split Flow Ratio= 0.02
Log Output Level= 0
Friction Slope Method= 1
Unsteady Friction Slope Method= 2
Unsteady Bridges Friction Slope Method= 1
Parabolic Critical Depth
Global Vel Dist=  1 , 1 , 1
Global Log Level= 0
CheckData=True
Encroach Param= -1, 0, 0, 0
BEGIN DESCRIPTION:
Multiple Run
END DESCRIPTION:

--- MOSS SPRINGS BRANCH.f01 (steady flow) ---

Flow Title=Multiple
Program Version=4.10
Number of Profiles= 7
Profile Names=10-year,25-year,50-year,1pct_min,100-year,1pct_plu,500-year
River Rch & RM=MOSS SPRINGS BRA,Reach-1         ,18766
    1718    2458    3093    2837    3836    5188    5891
River Rch & RM=MOSS SPRINGS BRA,Reach-1         ,14323
    2140    3080    3888    3573    4832    6535    7454
River Rch & RM=MOSS SPRINGS BRA,Reach-1         ,8675
    2427    3499    4423    4066    5499    7437    8489
Boundary for River Rch & Prof#=MOSS SPRINGS BRA,Reach-1         , 1
Up Type= 0
Dn Type= 3
Dn Slope=0.03
Boundary for River Rch & Prof#=MOSS SPRINGS BRA,Reach-1         , 2
Up Type= 0
Dn Type= 3
Dn Slope=0.03
Boundary for River Rch & Prof#=MOSS SPRINGS BRA,Reach-1         , 3
Up Type= 0
Dn Type= 3
Dn Slope=0.03
Boundary for River Rch & Prof#=MOSS SPRINGS BRA,Reach-1         , 4
Up Type= 0
Dn Type= 3
Dn Slope=0.03
Boundary for River Rch & Prof#=MOSS SPRINGS BRA,Reach-1         , 5
Up Type= 0
Dn Type= 3
Dn Slope=0.03
Boundary for River Rch & Prof#=MOSS SPRINGS BRA,Reach-1         , 6
Up Type= 0
Dn Type= 3
Dn Slope=0.03
Boundary for River Rch & Prof#=MOSS SPRINGS BRA,Reach-1         , 7
Up Type= 0
Dn Type= 3
Dn Slope=0.03
DSS Import GetInterval= 0
DSS Import GetPeak= 0
DSS Import FillOption= 0

--- MOSS SPRINGS BRANCH.g01 (geometry) ---

Geom Title=Existing Conditions
Program Version=4.10

River Reach=MOSS SPRINGS BRA,Reach-1
Reach XY= 30
      3468331.74     10459851.93      3469407.45     10460548.78
      3469636.85     10461134.86      3469957.93     10461359.17
      3469943.84     10461936.73      3470130.56     10462337.79
      3470917.22     10462898.93      3471068.12     10463192.53
      3470933.72     10463390.62      3471437.21     10463619.38
      3471471.95     10463986.78       3471947.6     10464505.48
      3471976.94     10464804.52       3472428.2     10464931.53
      3472275.31     10465026.28      3472433.35     10465354.02
      3473572.73     10465577.22        3473897.      10465382.4
      3474178.31     10465588.74      3473934.77     10465806.71
      3474257.54     10466724.11      3474569.58     10466832.84
      3474494.68     10467836.19      3474651.14     10468196.82
       3474253.2     10468981.73      3474235.54     10469260.13
      3474550.25     10469647.38       3474602.3      10470346.4
      3474216.38     10471391.55      3474078.73     10472939.22

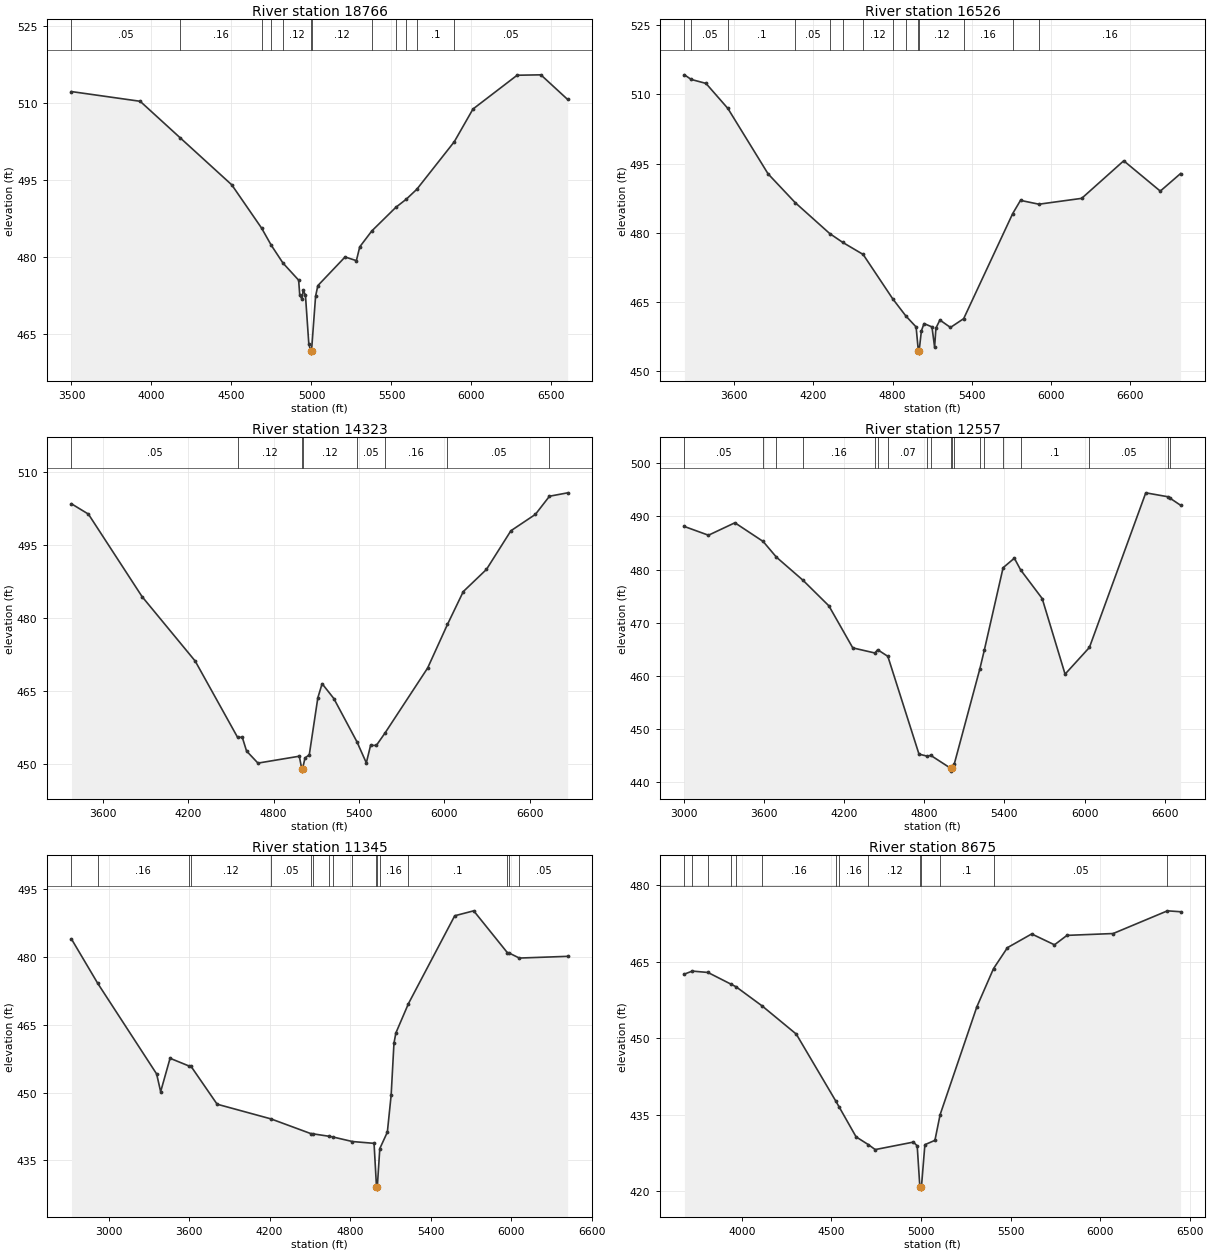
Type RM Length L Ch R = 1 ,18766   ,2240,2240,2240
BEGIN DESCRIPTION:
MOSS SPRINGS BRANCH 24.0
END DESCRIPTION:
XS GIS Cut Line= 2
      3467663.17     10461109.54      3469789.91     10458852.59
#Sta/Elev= 30
  3500.3  512.24  3929.6  510.35  4179.4  503.25  4502.4  494.08  4688.7  485.66
  4748.6  482.35  4822.1  478.87    4920  475.54  4926.9  472.68    4941  471.82
  4948.3  473.55  4962.5  472.65  4983.5  463.19  4994.7  461.84  4997.4  461.34
  5000.7  461.84    5026  472.43  5040.1  474.48  5210.1  480.05  5280.9  479.34
  5301.9  482.02  5377.4  485.12  5528.4  489.74  5591.8  491.27  5658.4  493.22
  5892.8  502.48  6009.5  508.84  6285.5  515.42  6433.9   515.5  6601.4   510.7
#Mann= 12 ,-1 , 0
  3500.3     .05       0  4179.4     .16       0  4688.7     .05       0
  4748.6     .16       0  4822.1     .12       0  4994.7     .07       0
  5000.7     .12       0  5377.4     .16       0  5528.4      .1       0
  5591.8     .05       0  5658.4      .1       0  5892.8     .05       0
Bank Sta=4994.7,5000.7
XS Rating Curve= 0 ,0
Exp/Cntr=0.3,0.1

Type RM Length L Ch R = 1 ,16526   ,2203,2203,2203
BEGIN DESCRIPTION:
MOSS SPRINGS BRANCH 23.0
END DESCRIPTION:
XS GIS Cut Line= 3
      3468118.91     10461543.53      3471005.22     10461478.43
      3471851.53     10461283.12
#Sta/Elev= 30
  3224.9  514.25  3276.3  513.25  3388.1  512.39    3554  506.95  3858.3  492.76
  4063.8  486.51  4324.4  479.82  4423.4  477.89  4577.6  475.28  4801.9  465.64
    4901  461.93  4978.5  459.55  4995.5  454.37  4998.3  453.87  5001.5  454.37
  5018.6  458.71  5038.6  460.28  5098.6  459.56  5118.6  455.17  5128.6   459.3
  5158.6  461.05  5238.6  459.44  5338.6  461.35  5709.9  484.16  5768.7  487.01
  5907.9  486.18  6231.9  487.45  6550.1   495.6  6826.7  489.02  6980.5  492.84
#Mann= 14 ,-1 , 0
  3224.9     .16       0  3276.3     .05       0    3554      .1       0
  4063.8     .05       0  4324.4      .1       0  4423.4     .16       0
  4577.6     .12       0  4801.9     .16       0    4901     .12       0
  4995.5     .07       0  5001.5     .12       0  5338.6     .16       0
  5709.9      .1       0  5907.9     .16       0
Bank Sta=4995.5,5001.5
XS Rating Curve= 0 ,0
Exp/Cntr=0.3,0.1

Type RM Length L Ch R = 1 ,14323   ,1766,1766,1766
BEGIN DESCRIPTION:
MOSS SPRINGS BRANCH 22.0
END DESCRIPTION:
XS GIS Cut Line= 3
      3469334.17     10463062.63       3472242.2     10462910.72
      3472763.01     10462672.01
#Sta/Elev= 30
  3381.1  503.55    3500  501.43    3877  484.44  4250.2  471.17  4547.8  455.47
  4580.7  455.49  4610.7  452.66  4690.8  450.17  4981.2  451.59  4998.2  449.02
    5001  448.52  5004.2  449.02  5021.3  451.23  5051.3  451.89  5111.4  463.62
  5141.4  466.52  5223.8  463.46  5385.1  454.61  5451.9  450.22  5481.9  453.84
    5522   453.8  5583.5  456.38  5882.4  469.74  6021.6  478.71  6132.8  485.48
  6295.8  490.05  6467.2     498  6639.2  501.37  6738.2  505.11    6866  505.81
#Mann= 8 ,-1 , 0
  3381.1     .05       0  4547.8     .12       0  4998.2     .07       0
  5004.2     .12       0  5385.1     .05       0  5583.5     .16       0
  6021.6     .05       0  6738.2     .16       0
Bank Sta=4998.2,5004.2
XS Rating Curve= 0 ,0
Exp/Cntr=0.3,0.1

Type RM Length L Ch R = 1 ,12557   ,1212,1212,1212
BEGIN DESCRIPTION:
MOSS SPRINGS BRANCH 21.0
END DESCRIPTION:
XS GIS Cut Line= 4
       3469703.1     10464408.11       3470809.9     10464581.73
      3472046.88     10463908.98      3472978.59     10463172.28
#Sta/Elev= 30
  3003.3  488.09  3183.4  486.45  3381.4  488.79  3592.8  485.28  3692.2  482.33
  3891.1  477.99  4085.4  473.17  4264.2  465.27  4429.7  464.31  4450.7  464.92
  4526.9  463.68  4760.1   445.3  4823.2   444.9  4847.8  445.07  4999.7   442.6
  5002.4   442.1  5005.7   442.6  5024.9  443.48  5216.3  461.36  5248.9  464.79
  5390.1  480.34  5474.4  482.13  5521.4  479.93  5682.8  474.55  5854.3  460.33
  6036.7  465.36  6458.6  494.42  6627.2  493.67  6639.3  493.43  6719.5  492.08
#Mann= 19 ,-1 , 0
  3003.3     .05       0  3592.8     .16       0  3692.2      .1       0
  3891.1     .16       0  4429.7     .05       0  4450.7     .16       0
  4526.9     .07       0  4823.2     .12       0  4847.8     .07       0
  4999.7     .07       0  5005.7     .07       0  5024.9     .05       0
  5216.3     .16       0  5248.9     .05       0  5390.1     .16       0
  5521.4      .1       0  6036.7     .05       0  6627.2      .1       0
  6639.3     .16       0
Bank Sta=4999.7,5005.7
XS Rating Curve= 0 ,0
Exp/Cntr=0.3,0.1

Type RM Length L Ch R = 1 ,11345   ,2670,2670,2670
BEGIN DESCRIPTION:
MOSS SPRINGS BRANCH 20.0
END DESCRIPTION:
XS GIS Cut Line= 4
      3470158.86     10465254.47      3471960.08     10465145.96
      3473023.45     10464060.89      3473240.46     10463757.08
#Sta/Elev= 30
  2724.1  483.94  2920.2  474.12  3358.5  454.12  3388.6   450.2  3458.7  457.58
  3599.3  455.88  3615.1  455.79  3809.3  447.43  4210.7  444.18  4508.5  440.92
  4520.8  440.89  4646.1  440.33  4671.2  440.19  4817.2  439.18  4978.6  438.78
  4996.8  429.16  4999.5  428.66  5002.8  429.16  5021.4  437.62  5077.6  441.25
  5105.9  449.41    5127  460.93  5141.2  463.18    5235  469.67  5579.7  489.08
  5721.1  490.17  5971.1  480.95  5982.2  480.88    6061  479.73  6421.2  480.11
#Mann= 17 ,-1 , 0
  2724.1     .05       0  2920.2     .16       0  3599.3      .1       0
  3615.1     .12       0  4210.7     .05       0  4508.5     .12       0
  4520.8      .1       0  4646.1     .12       0  4671.2      .1       0
  4817.2     .12       0  4996.8     .07       0  5002.8     .12       0
  5021.4     .16       0    5235      .1       0  5971.1     .05       0
  5982.2      .1       0    6061     .05       0
Bank Sta=4996.8,5002.8
XS Rating Curve= 0 ,0
Exp/Cntr=0.3,0.1

Type RM Length L Ch R = 1 ,8675    ,1179,1179,1179
BEGIN DESCRIPTION:
MOSS SPRINGS BRANCH 19.0
END DESCRIPTION:
XS GIS Cut Line= 4
      3472967.04     10466161.04      3473683.17     10465952.71
      3474529.52     10464937.09      3474503.53     10464235.33
#Sta/Elev= 30
  3679.4  462.56  3723.4  463.15  3810.8  462.88  3940.4  460.57  3967.9  460.07
    4113  456.33    4304   450.8  4524.5  437.68    4543  436.54  4637.9  430.66
  4706.8  429.13  4744.6  428.17  4958.1  429.64    4979  428.89  4993.3  421.15
  4996.8  420.92  4999.5  420.42  5002.8  420.92  5021.9  429.13  5077.9  429.98
    5107  435.02  5312.2  456.17    5405  463.63  5482.7  467.74  5618.1  470.43
  5745.4   468.3  5815.2  470.15  6072.9  470.51    6376  474.96  6449.5  474.78
#Mann= 14 ,-1 , 0
  3679.4     .05       0  3723.4      .1       0  3810.8     .05       0
  3940.4      .1       0  3967.9     .05       0    4113     .16       0
  4524.5     .05       0    4543     .16       0  4706.8     .12       0
  4996.8     .07       0  5002.8     .12       0    5107      .1       0
    5405     .05       0    6376     .16       0
Bank Sta=4996.8,5002.8
XS Rating Curve= 0 ,0
Exp/Cntr=0.3,0.1

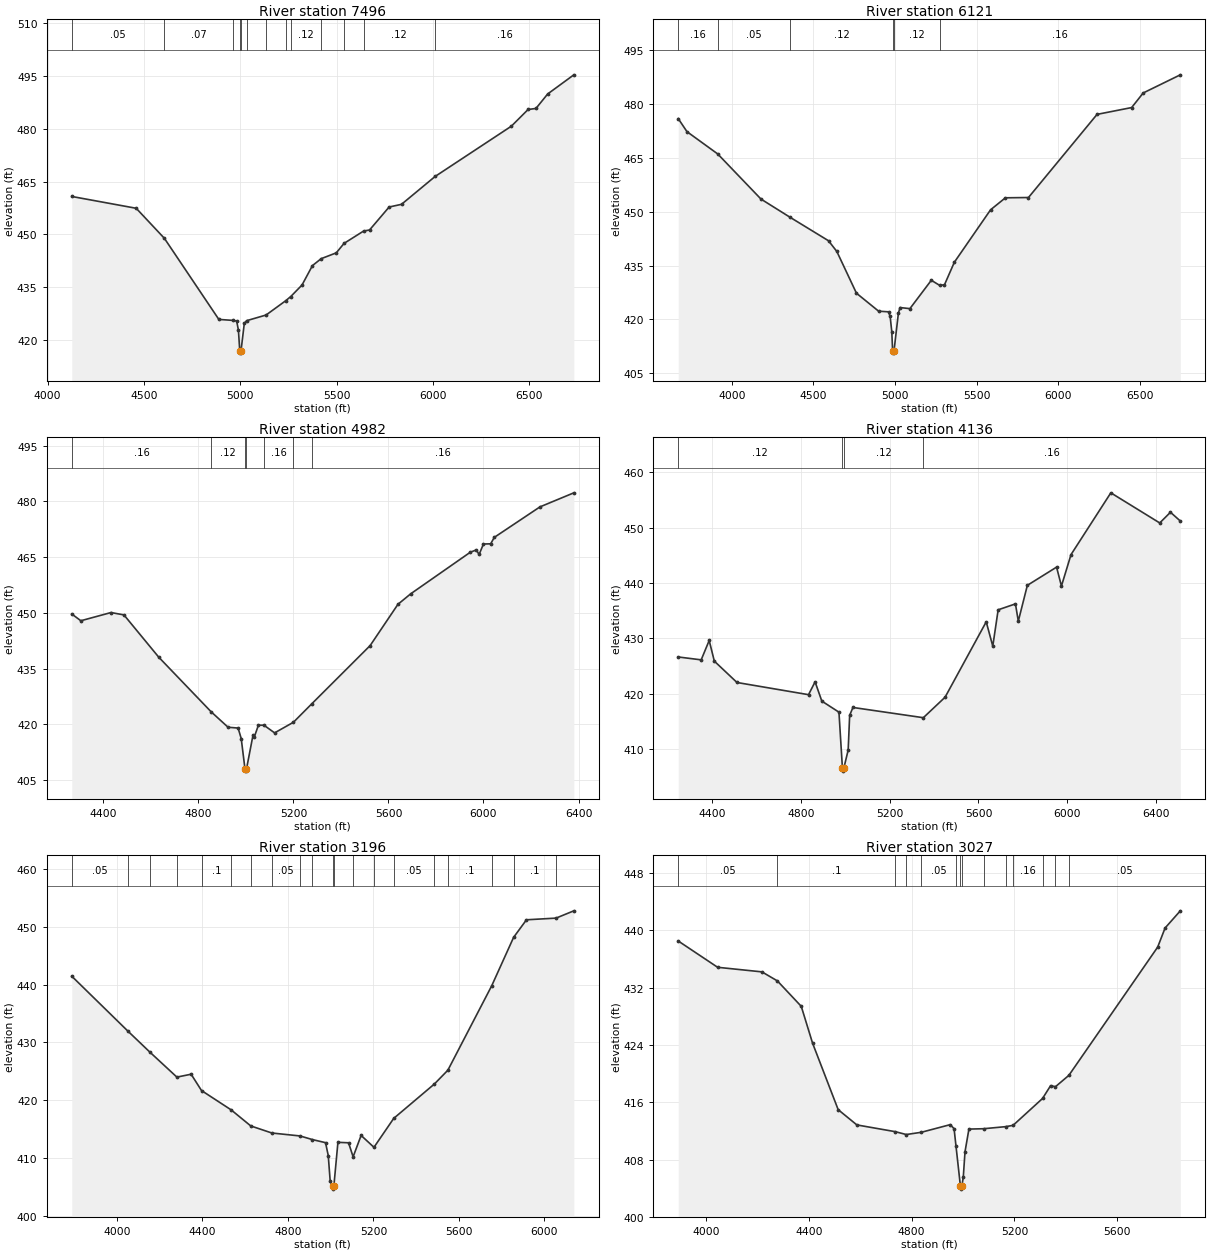
Type RM Length L Ch R = 1 ,7496    ,1375,1375,1375
BEGIN DESCRIPTION:
MOSS SPRINGS BRANCH 16.0
END DESCRIPTION:
XS GIS Cut Line= 2
      3473370.67     10466525.63       3475935.8     10466069.89
#Sta/Elev= 30
  4125.1  460.77  4459.5  457.42  4605.8  448.89  4888.3   425.9  4962.1  425.62
  4980.8  425.43  4989.9  422.85    4997  416.84  4999.8  416.34    5003  416.84
  5020.3  424.75  5032.3  425.54  5133.4  427.15  5234.5  431.17  5261.3  432.38
  5319.9  435.66  5373.9  441.16  5419.3  443.13  5497.7  444.78  5537.9  447.46
    5639  450.95  5670.4  451.27  5771.9  457.78  5836.1  458.54  6010.9  466.46
  6406.3  480.71    6493  485.44  6533.7  485.73  6594.6  489.84  6730.4  495.27
#Mann= 13 ,-1 , 0
  4125.1     .05       0  4605.8     .07       0  4962.1     .12       0
    4997     .07       0    5003     .12       0  5032.3      .1       0
  5133.4     .16       0  5234.5      .1       0  5261.3     .12       0
  5419.3      .1       0  5537.9     .16       0    5639     .12       0
  6010.9     .16       0
Bank Sta=4997,5003
XS Rating Curve= 0 ,0
Exp/Cntr=0.3,0.1

Type RM Length L Ch R = 1 ,6121    ,1139,1139,1139
BEGIN DESCRIPTION:
MOSS SPRINGS BRANCH 14.0
END DESCRIPTION:
XS GIS Cut Line= 4
      3473214.42     10467059.48      3474164.94     10467398.02
      3475401.92     10467228.75       3475961.8     10466629.81
#Sta/Elev= 30
  3671.4  475.98  3724.9  472.34  3913.2  466.13  4178.5  453.54  4356.1  448.48
  4592.5  441.91  4643.4  438.93  4763.8  427.28  4899.6  422.27  4960.2  422.09
  4970.3  420.81  4980.3  416.55  4985.5  411.17  4987.6  411.07  4990.3  410.57
  4993.6  411.07  5020.7  421.65  5030.8  423.28  5091.4  422.98  5222.6  430.89
  5273.6  429.47  5303.3  429.63  5363.9  435.93  5585.9  450.55  5676.8  453.89
  5818.1  453.97  6238.5  477.16  6450.5  479.06  6521.3  483.13  6748.8  488.19
#Mann= 6 ,-1 , 0
  3671.4     .16       0  3913.2     .05       0  4356.1     .12       0
  4987.6     .07       0  4993.6     .12       0  5273.6     .16       0
Bank Sta=4987.6,4993.6
XS Rating Curve= 0 ,0
Exp/Cntr=0.3,0.1

Type RM Length L Ch R = 1 ,4982    ,846,846,846
BEGIN DESCRIPTION:
MOSS SPRINGS BRANCH 12.0
END DESCRIPTION:
XS GIS Cut Line= 2
      3473826.38     10468127.19       3475805.6     10468869.39
#Sta/Elev= 30
  4266.6  449.71  4304.8  447.89  4431.8   450.1  4486.3  449.46  4632.9  438.08
  4853.6  423.38  4924.8  419.23  4966.9  419.02    4980   416.2    4996  407.93
  4998.7  407.43    5002  407.93  5029.8  417.16  5035.2  416.64  5052.4  419.79
  5075.8  419.78  5120.6  417.72  5199.8  420.58  5277.2  425.55  5522.9  441.22
  5639.8  452.31  5693.8  455.15  5944.8  466.34  5969.7  466.95  5981.5  465.72
  5999.9  468.54  6030.2  468.59  6045.6  470.33  6237.8  478.53  6380.4  482.31
#Mann= 7 ,-1 , 0
  4266.6     .16       0  4853.6     .12       0    4996     .07       0
    5002     .12       0  5075.8     .16       0  5199.8     .12       0
  5277.2     .16       0
Bank Sta=4996,5002
XS Rating Curve= 0 ,0
Exp/Cntr=0.3,0.1

Type RM Length L Ch R = 1 ,4136    ,940,940,940
BEGIN DESCRIPTION:
MOSS SPRINGS BRANCH 9.0
END DESCRIPTION:
XS GIS Cut Line= 2
      3473552.94     10468817.29      3475648.22     10469663.21
#Sta/Elev= 30
  4248.8  426.65  4352.1  426.13  4388.1  429.63  4411.2   425.9  4513.2  422.04
  4835.2  419.84  4864.7  422.16    4895  418.68  4972.1  416.68  4987.8  406.53
  4990.6  406.03  4993.8  406.53  5013.6  409.83  5020.3  416.11  5035.1  417.53
  5351.9  415.68  5449.7  419.38  5634.9     433  5664.4   428.6  5688.6  435.17
  5766.4  436.24  5779.3  433.12    5820  439.59  5951.5  442.88  5973.4  439.46
  6016.5  445.14  6195.7   456.3  6415.8  450.86  6464.1  452.79  6508.4  451.21
#Mann= 4 ,-1 , 0
  4248.8     .12       0  4987.8     .07       0  4993.8     .12       0
  5351.9     .16       0
Bank Sta=4987.8,4993.8
XS Rating Curve= 0 ,0
Exp/Cntr=0.3,0.1

Type RM Length L Ch R = 1 ,3196    ,169,169,169
BEGIN DESCRIPTION:
Mapping XS 45c0ae86
END DESCRIPTION:
XS GIS Cut Line= 3
       3473529.8     10469240.19      3475029.79      10470226.3
      3475571.48     10470344.36
#Sta/Elev= 30
  3788.3  441.44  4049.6     432  4154.1  428.31  4280.2     424  4346.8   424.5
  4395.4  421.68  4534.4  418.33    4626  415.56  4724.6  414.34  4856.6  413.83
  4914.7   413.2  4975.8  412.67  4988.5  410.45  4997.6  406.02  5008.7  405.14
  5011.5  404.64  5014.7  405.14  5033.8  412.73  5083.5  412.65  5104.9  410.22
  5142.3  413.92  5202.4  411.87    5295  416.87  5485.2  422.81  5548.2  425.19
  5753.4  439.78    5856  448.16  5916.1  451.19  6054.3  451.48  6137.8  452.74
#Mann= 20 ,-1 , 0
  3788.3     .05       0  4049.6     .16       0  4154.1     .05       0
  4280.2      .1       0  4395.4      .1       0  4534.4     .05       0
    4626     .12       0  4724.6     .05       0  4856.6     .12       0
  4914.7     .05       0  5008.7     .07       0  5014.7     .12       0
  5104.9     .05       0  5202.4     .16       0    5295     .05       0
  5485.2     .05       0  5548.2      .1       0  5753.4     .16       0
    5856      .1       0  6054.3     .16       0
Bank Sta=5008.7,5014.7
XS Rating Curve= 0 ,0
Exp/Cntr=0.3,0.1

Type RM Length L Ch R = 1 ,3027    ,566,566,566
BEGIN DESCRIPTION:
Mapping XS 802fa28d
END DESCRIPTION:
XS GIS Cut Line= 3
      3473609.67     10469472.84      3475078.41     10470417.27
      3475265.91     10470504.08
#Sta/Elev= 30
  3892.6  438.51  4045.8  434.84  4218.2   434.2  4278.2  432.94  4371.1  429.39
    4415  424.26  4514.7  414.97  4587.4  412.84  4736.5   411.9  4779.5   411.5
  4837.7  411.81  4950.6  412.88  4965.5  412.31  4972.9   409.9  4989.9  404.38
  4992.6  403.88  4995.9  404.38  5001.2  405.51    5008   409.1  5023.2  412.26
  5080.3  412.31  5166.3   412.6  5194.9  412.78  5309.5  416.53  5340.9  418.32
  5359.7  418.17    5412  419.76  5757.4  437.66  5786.1  440.32  5845.4  442.72
#Mann= 14 ,-1 , 0
  3892.6     .05       0  4278.2      .1       0  4736.5     .12       0
  4779.5      .1       0  4837.7     .05       0  4972.9     .12       0
  4989.9     .07       0  4995.9     .12       0  5080.3     .16       0
  5166.3     .12       0  5194.9     .16       0  5309.5     .05       0
  5359.7     .16       0    5412     .05       0
Bank Sta=4989.9,4995.9
XS Rating Curve= 0 ,0
Exp/Cntr=0.3,0.1

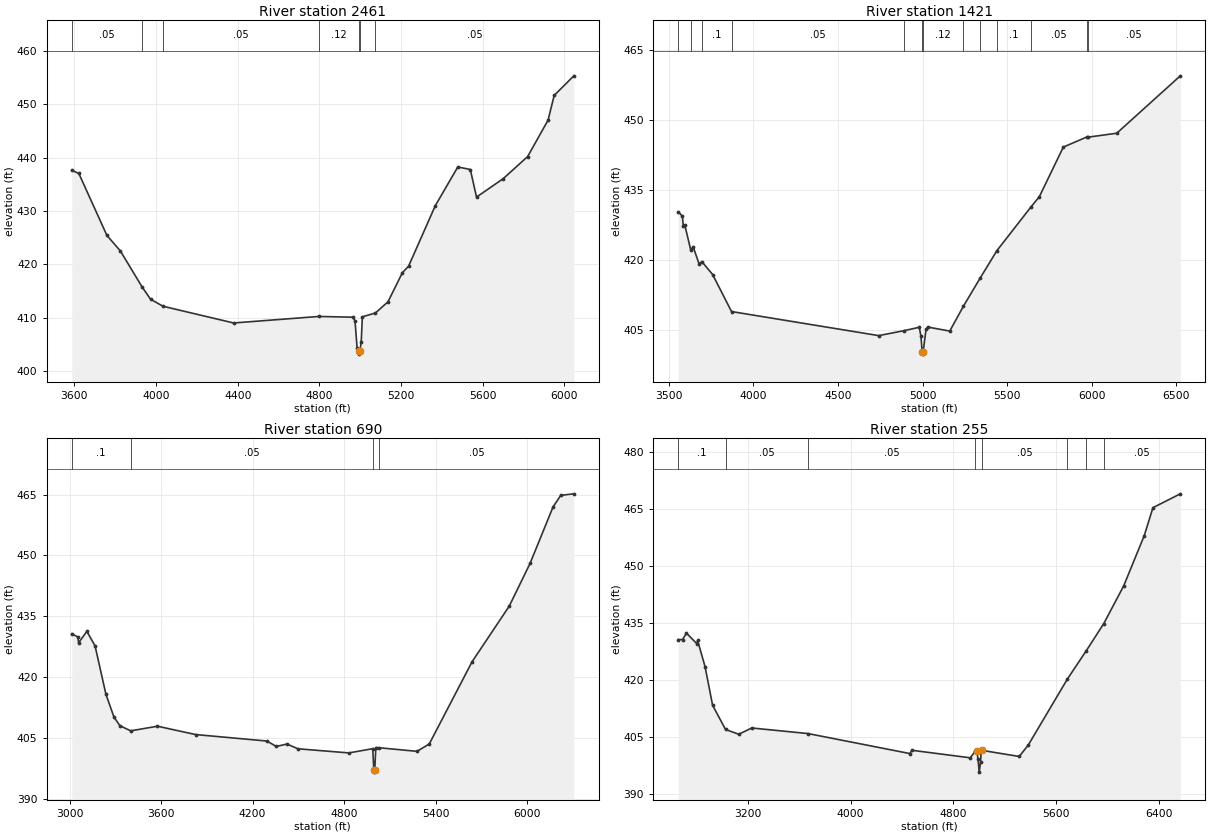
Type RM Length L Ch R = 1 ,2461    ,1040,1040,1040
BEGIN DESCRIPTION:
MOSS SPRINGS BRANCH 5.0
END DESCRIPTION:
XS GIS Cut Line= 4
      3473787.35     10469702.75      3474041.48     10470547.78
      3475167.54     10470692.29      3475608.43     10470695.04
#Sta/Elev= 30
  3587.2   437.6  3621.8  437.02  3759.2  425.43  3825.2  422.52    3931  415.82
    3973  413.48  4034.1  412.17  4379.7  409.04  4797.5  410.26  4964.3  410.12
  4974.3   409.4  4984.4   404.4  4991.5  403.71  4994.3  403.21  4997.5  403.71
  5004.6  405.49  5010.1  410.19  5074.1  410.91  5135.7     413  5206.2  418.45
  5236.5  419.67  5367.5     431  5477.7  438.24  5538.9  437.76  5569.2   432.6
  5699.5  436.03  5819.5  440.18  5919.5  446.99  5949.5  451.62  6045.8  455.29
#Mann= 7 ,-1 , 0
  3587.2     .05       0    3931      .1       0  4034.1     .05       0
  4797.5     .12       0  4991.5     .07       0  4997.5     .12       0
  5074.1     .05       0
Bank Sta=4991.5,4997.5
XS Rating Curve= 0 ,0
Exp/Cntr=0.3,0.1

Type RM Length L Ch R = 1 ,1421    ,731,731,731
BEGIN DESCRIPTION:
MOSS SPRINGS BRANCH 3.1
END DESCRIPTION:
XS GIS Cut Line= 5
      3473680.92     10470389.14      3473763.42       10470489.
      3473945.71     10471521.99      3474909.25     10471543.69
      3475703.55     10471317.99
#Sta/Elev= 30
    3556  430.35  3580.1  429.49  3586.5  427.26  3594.4  427.59  3630.3  422.14
  3643.9  422.92    3679  419.22  3695.8  419.69  3759.3  416.93    3871  408.99
  4740.9  403.83  4889.3  404.88  4980.9  405.62  4990.9  403.65  4997.9  400.36
  5000.7  399.86  5003.9  400.36  5020.9  405.21  5030.9  405.67    5161   404.8
  5242.2  410.16  5340.9  416.17  5439.7  422.05  5640.7   431.4  5691.1  433.65
  5832.5  444.26  5972.3  446.44  5979.3  446.39  6148.3  447.23    6524  459.54
#Mann= 13 ,-1 , 0
    3556      .1       0  3630.3     .05       0  3695.8      .1       0
    3871     .05       0  4889.3     .12       0  4997.9     .07       0
  5003.9     .12       0  5242.2      .1       0  5340.9     .05       0
  5439.7      .1       0  5640.7     .05       0  5972.3      .1       0
  5979.3     .05       0
Bank Sta=4997.9,5003.9
XS Rating Curve= 0 ,0
Exp/Cntr=0.3,0.1

Type RM Length L Ch R = 1 ,690     ,435,435,435
BEGIN DESCRIPTION:
MOSS SPRINGS BRANCH 3.0
END DESCRIPTION:
XS GIS Cut Line= 3
       3473679.5     10470431.09      3474000.68     10472245.37
       3475448.7     10472332.08
#Sta/Elev= 30
  3013.8  430.66  3053.7  429.88  3058.8  428.44  3112.8  431.26  3166.7  427.66
  3237.8  415.74  3290.3  410.13  3329.2  407.99  3400.1  406.71  3575.9  407.85
  3826.8  405.79    4294  404.19  4354.9  402.86    4426  403.45  4497.1  402.28
  4831.4  401.26  4987.9  402.31    4995  397.02  4997.7  396.52    5001  397.02
    5008  402.57    5028  402.54  5278.5  401.65  5358.6  403.47  5639.1  423.74
    5883  437.48  6019.8  448.03  6170.1  461.93  6220.6  464.82  6306.9   465.2
#Mann= 4 ,-1 , 0
  3013.8      .1       0  3400.1     .05       0  4987.9     .03       0
    5028     .05       0
Bank Sta=4995,5001
XS Rating Curve= 0 ,0
Exp/Cntr=0.3,0.1

Type RM Length L Ch R = 1 ,255     ,0,0,0
BEGIN DESCRIPTION:
MOSS SPRINGS BRANCH 1.0
END DESCRIPTION:
XS GIS Cut Line= 4
      3473610.05     10470448.47      3474018.04      10472679.4
      3474660.41     10472731.48      3475578.83     10472350.25
#Sta/Elev= 30
  2658.6  430.57  2692.3  430.62  2722.8   432.3    2804  429.49  2809.1  430.38
  2867.4  423.46  2926.1  413.28  3026.5  406.92  3129.5  405.66  3231.1  407.31
  3668.2  405.84  4461.2  400.57  4476.5  401.44  4931.1  399.45  4970.7  401.21
  4980.8   401.3  4990.8  399.27  5000.6  395.68  5010.9  398.26    5016  401.47
    5021  401.42  5311.8   399.8  5382.1   402.8  5687.2  420.23  5834.5   427.7
  5970.1  434.83    6125  444.76    6285  458.01  6352.4  465.35  6565.4     469
#Mann= 8 ,-1 , 0
  2658.6      .1       0  3026.5     .05       0  3668.2     .05       0
  4970.7     .03       0    5021     .05       0  5687.2     .16       0
  5834.5      .1       0  5970.1     .05       0
Bank Sta=4980.8,5021
XS Rating Curve= 0 ,0
Exp/Cntr=0.3,0.1

Chan Stop Cuts=-1
Use User Specified Reach Order=0
Composite Channel Slope=5