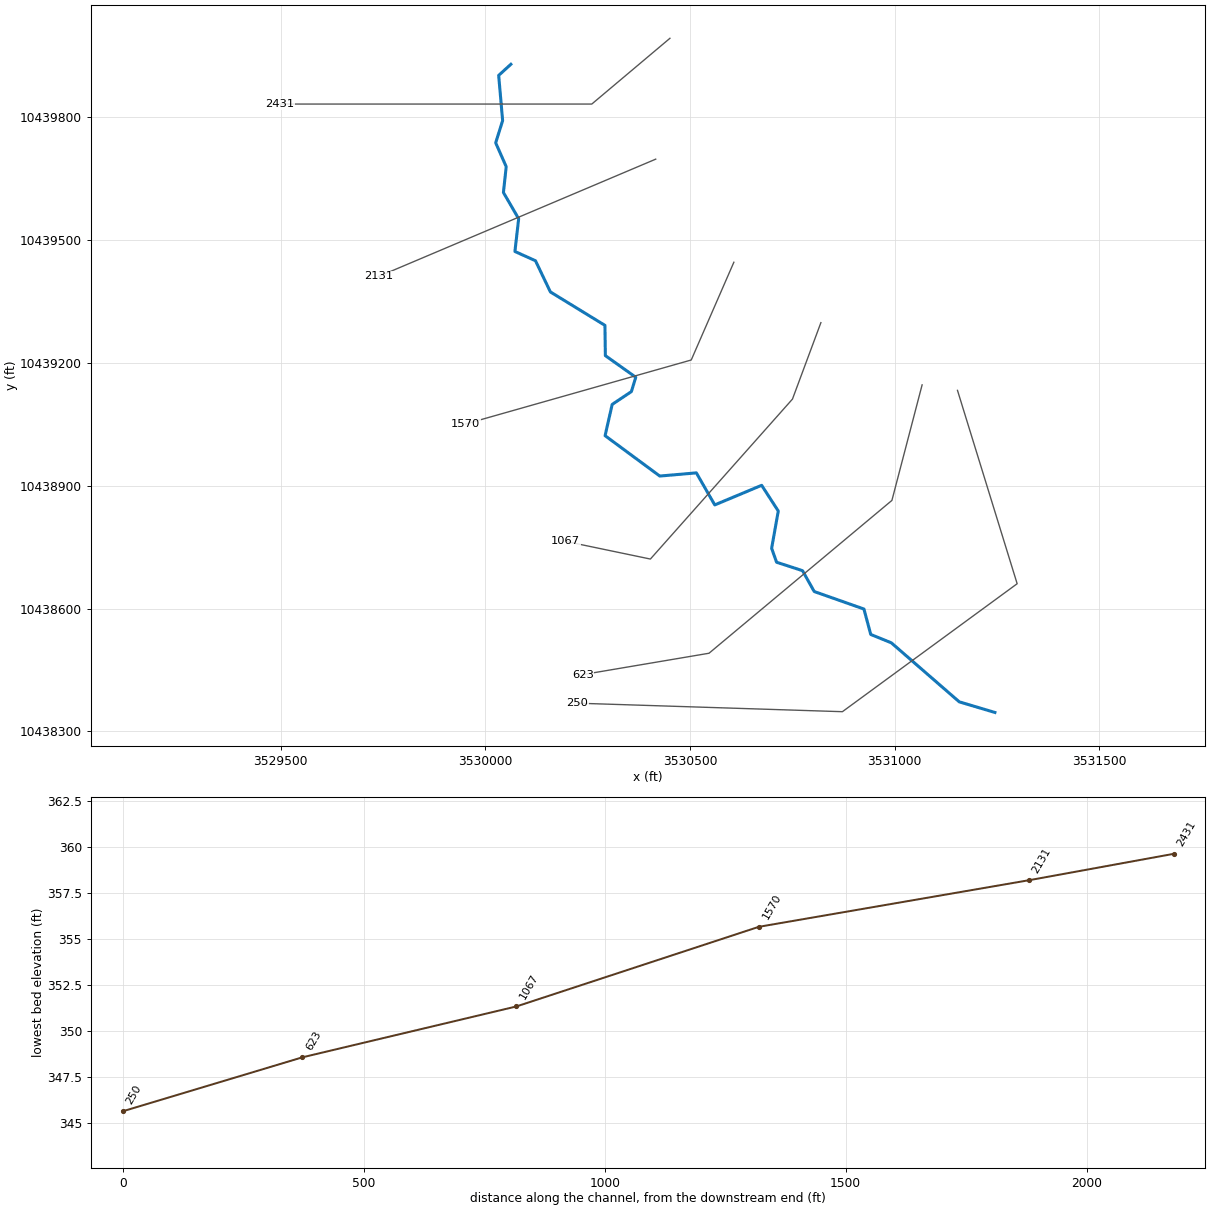
--- MULBERRY CREEK TRIB 2.prj (project) ---

Proj Title=MULBERRY CREEK TRIB 2 Base Level Engineering
Current Plan=p01
Default Exp/Contr=0.3,0.1
English Units
Geom File=g01
Flow File=f01
Plan File=p01
Y Axis Title=Elevation
X Axis Title(PF)=Main Channel Distance
X Axis Title(XS)=Station
BEGIN DESCRIPTION:
MULBERRY CREEK TRIB 2
END DESCRIPTION:
DSS Export Rating Curves= 0
DSS Export Rating Curve Sorted= 0
DSS Export Volume Flow Curves= 0
DXF OffsetX= 0
DXF OffsetY= 0
DXF ScaleX= 1
DXF ScaleY= 10

--- MULBERRY CREEK TRIB 2.p01 (plan) ---

Plan Title=Multiple Run
Short Identifier=Multiple
Geom File=g01
Flow File=f01
Subcritical Flow
K Sum by GR= 0
Std Step Tol= 0.01
Critical Tol= 0.01
Num of Std Step Trials= 20
Max Error Tol= 0.3
Flow Tol Ratio= 0.001
Split Flow NTrial= 30
Split Flow Tol= 0.02
Split Flow Ratio= 0.02
Log Output Level= 0
Friction Slope Method= 1
Unsteady Friction Slope Method= 2
Unsteady Bridges Friction Slope Method= 1
Parabolic Critical Depth
Global Vel Dist=  1 , 1 , 1
Global Log Level= 0
CheckData=True
Encroach Param= -1, 0, 0, 0
BEGIN DESCRIPTION:
Multiple Run
END DESCRIPTION:

--- MULBERRY CREEK TRIB 2.f01 (steady flow) ---

Flow Title=Multiple
Number of Profiles=7
Profile Names=10-year,25-year,50-year,1pct_min,100-year,1pct_plu,500-year
River Rch & RM= MULBERRY CREEK T,Reach-1,2431
     369     478     564     487     659     891     894
Boundary for River Rch & Prof#=MULBERRY CREEK T,Reach-1,1
Up Type=0
Dn Type=3
Dn Slope=0.005
Boundary for River Rch & Prof#=MULBERRY CREEK T,Reach-1,2
Up Type=0
Dn Type=3
Dn Slope=0.005
Boundary for River Rch & Prof#=MULBERRY CREEK T,Reach-1,3
Up Type=0
Dn Type=3
Dn Slope=0.005
Boundary for River Rch & Prof#=MULBERRY CREEK T,Reach-1,4
Up Type=0
Dn Type=3
Dn Slope=0.005
Boundary for River Rch & Prof#=MULBERRY CREEK T,Reach-1,5
Up Type=0
Dn Type=3
Dn Slope=0.005
Boundary for River Rch & Prof#=MULBERRY CREEK T,Reach-1,6
Up Type=0
Dn Type=3
Dn Slope=0.005
Boundary for River Rch & Prof#=MULBERRY CREEK T,Reach-1,7
Up Type=0
Dn Type=3
Dn Slope=0.005

--- MULBERRY CREEK TRIB 2.g01 (geometry) ---

Geom Title=Existing Conditions
Program Version=4.10

River Reach=MULBERRY CREEK T,Reach-1
Reach XY= 30
      3530062.28     10439929.18      3530032.42      10439902.1
      3530042.11     10439791.64      3530025.13     10439737.51
      3530050.82     10439679.18      3530044.05     10439616.07
      3530081.29     10439552.01      3530072.15     10439472.04
      3530122.43      10439449.4      3530158.81     10439373.27
      3530292.11     10439291.64      3530293.18     10439217.72
      3530367.49     10439164.94      3530356.72     10439129.87
      3530309.85     10439098.62      3530292.49     10439022.23
      3530426.17     10438923.62      3530515.54     10438931.39
      3530560.54     10438853.13      3530675.13     10438901.05
      3530715.75      10438838.2      3530699.53     10438747.23
      3530711.58      10438713.2        3530775.     10438692.58
       3530803.6     10438641.64      3530925.03     10438598.93
      3530941.79     10438536.81      3530992.14     10438516.33
      3531158.11     10438372.23      3531245.17     10438346.32

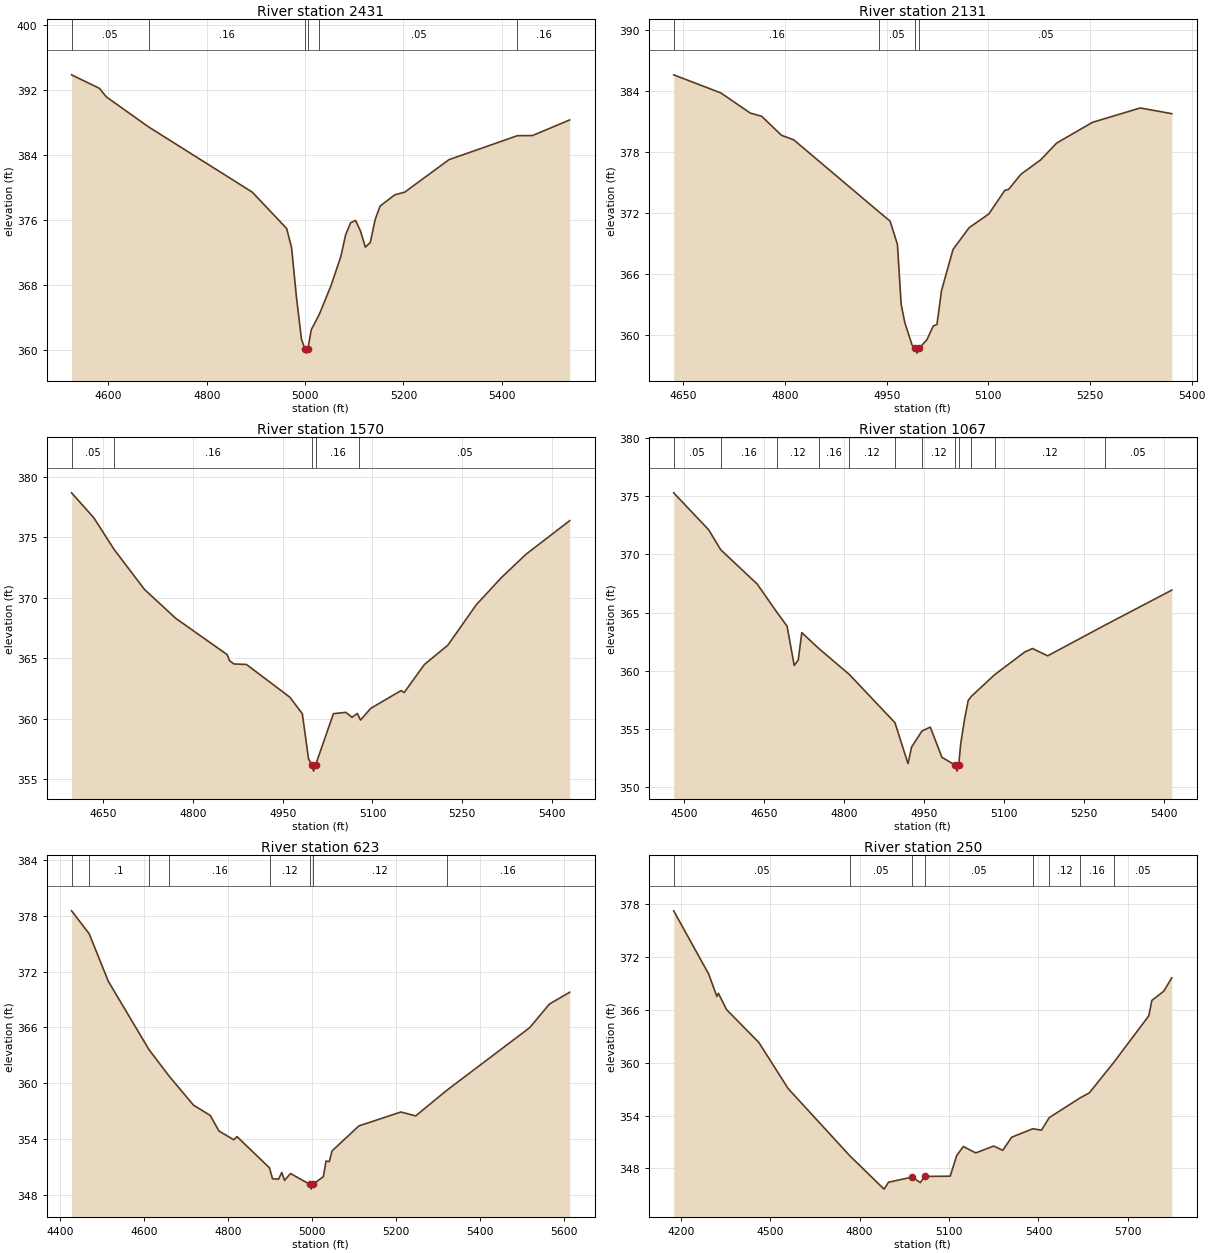
Type RM Length L Ch R = 1 ,2431    ,300,300,300
BEGIN DESCRIPTION:
MULBERRY CREEK TRIB 2 5.0
END DESCRIPTION:
XS GIS Cut Line= 3
      3530450.97     10439992.67      3530259.99     10439832.07
      3529496.62     10439832.07
#Sta/Elev= 30
  4525.1  393.86  4581.7   392.2    4596  391.14  4681.8  387.45  4892.5  379.43
  4962.5  374.95  4972.5  372.58  4982.5  366.44  4992.5  361.36  4999.5  360.12
  5002.3  359.62  5005.5  360.12  5012.5   362.5    5029  364.41  5052.5   367.9
  5072.5  371.47  5082.5  374.21  5092.5  375.65  5102.5  375.95  5112.5  374.66
  5122.5  372.66  5132.5  373.23  5142.5  376.07  5152.5  377.72  5182.5   379.1
  5202.5  379.42  5292.5  383.42  5431.5  386.37  5462.5  386.39    5538  388.31
#Mann= 6 ,-1 , 0
  4525.1     .05       0  4681.8     .16       0  4999.5     .07       0
  5005.5     .16       0    5029     .05       0  5431.5     .16       0
Bank Sta=4999.5,5005.5
XS Rating Curve= 0 ,0
Exp/Cntr=0.3,0.1

Type RM Length L Ch R = 1 ,2131    ,561,561,561
BEGIN DESCRIPTION:
MULBERRY CREEK TRIB 2 4.0
END DESCRIPTION:
XS GIS Cut Line= 2
       3530416.2     10439697.51       3529739.2     10439411.08
#Sta/Elev= 30
  4635.6  385.56  4705.2  383.78  4748.6   381.8  4765.5  381.48  4794.6  379.62
  4812.9  379.16  4938.8  372.07  4954.9  371.18  4965.8  368.89  4971.3  362.99
  4976.8  361.17  4987.5  358.97    4992  358.69  4994.8  358.19    4998  358.69
  5009.2   359.5  5018.7  360.86  5024.1     361  5030.9  364.35  5047.8  368.38
  5071.5  370.52  5100.7  371.88  5124.3   374.2  5129.8  374.29    5148  375.78
  5177.2   377.2  5200.8  378.85  5253.7  380.89  5324.1   382.3  5370.7  381.74
#Mann= 4 ,-1 , 0
  4635.6     .16       0  4938.8     .05       0    4992     .03       0
    4998     .05       0
Bank Sta=4992,4998
XS Rating Curve= 0 ,0
Exp/Cntr=0.3,0.1

Type RM Length L Ch R = 1 ,1570    ,503,503,503
BEGIN DESCRIPTION:
MULBERRY CREEK TRIB 2 3.0
END DESCRIPTION:
XS GIS Cut Line= 3
       3530607.2     10439445.76      3530503.05     10439207.07
      3529951.79     10439050.81
#Sta/Elev= 30
  4596.6  378.67  4633.8  376.61  4667.6     374  4718.8  370.67    4771  368.29
    4857  365.29  4860.9  364.79  4868.4  364.52  4889.2  364.48  4961.9  361.77
  4982.7   360.4  4993.1  356.67  4998.8  356.16  5001.5  355.66  5004.8  356.16
  5034.7  360.41  5055.5  360.52  5065.9  360.11  5074.8  360.43  5078.2  360.07
    5080  359.88  5097.1  360.85  5147.9  362.32  5153.1  362.16    5187  364.48
  5226.1  366.07  5273.8  369.42  5315.3  371.64  5356.9  373.59    5430  376.37
#Mann= 5 ,-1 , 0
  4596.6     .05       0  4667.6     .16       0  4998.8     .07       0
  5004.8     .16       0  5078.2     .05       0
Bank Sta=4998.8,5004.8
XS Rating Curve= 0 ,0
Exp/Cntr=0.3,0.1

Type RM Length L Ch R = 1 ,1067    ,444,444,444
BEGIN DESCRIPTION:
MULBERRY CREEK TRIB 2 2.0
END DESCRIPTION:
XS GIS Cut Line= 4
       3530819.9     10439298.24      3530750.44     10439111.58
      3530403.22     10438720.96      3530195.97     10438764.14
#Sta/Elev= 30
    4481  375.31  4546.5  372.13  4569.1  370.41  4637.6  367.45  4675.4  364.96
  4693.5  363.83  4706.9  360.44  4714.4  360.91  4721.1  363.27  4753.3  361.89
  4810.1  359.67  4895.7  355.51  4920.1  351.99  4926.8  353.41  4946.2  354.79
  4961.9  355.13  4983.7  352.53  5009.1  351.84  5011.9  351.34  5015.1  351.84
  5018.8  353.66  5026.3  355.86    5033  357.43  5038.2  357.75  5082.3  359.64
  5139.2  361.61  5153.4   361.9  5181.9  361.27  5288.7   363.9  5414.5  366.93
#Mann= 12 ,-1 , 0
    4481     .05       0  4569.1     .16       0  4675.4     .12       0
  4753.3     .16       0  4810.1     .12       0  4895.7     .16       0
  4946.2     .12       0  5009.1     .07       0  5015.1     .12       0
  5038.2     .16       0  5082.3     .12       0  5288.7     .05       0
Bank Sta=5009.1,5015.1
XS Rating Curve= 0 ,0
Exp/Cntr=0.3,0.1

Type RM Length L Ch R = 1 ,623     ,373,373,373
BEGIN DESCRIPTION:
MULBERRY CREEK TRIB 2 1.1
END DESCRIPTION:
XS GIS Cut Line= 4
      3531067.29     10439146.33       3530993.5     10438864.19
      3530546.45     10438490.92      3530238.24     10438438.83
#Sta/Elev= 30
  4427.5  378.53  4469.4  376.07    4515  370.95    4612  363.59  4660.6   360.7
  4717.9  357.62  4757.8  356.51  4778.6  354.84  4813.8  353.89  4821.6  354.23
    4899  350.87  4906.2   349.7  4920.5  349.65  4928.3  350.38  4934.8  349.52
  4949.1  350.26  4995.6  349.08  4998.3  348.58  5001.6  349.08  5027.2  349.91
  5033.7   351.6  5041.5  351.54    5048  352.69  5111.8  355.38    5212  356.88
  5247.2  356.46  5321.5  359.22  5518.9  365.96  5565.9   368.5  5614.1  369.77
#Mann= 8 ,-1 , 0
  4427.5     .05       0  4469.4      .1       0    4612     .05       0
  4660.6     .16       0    4899     .12       0  4995.6     .07       0
  5001.6     .12       0  5321.5     .16       0
Bank Sta=4995.6,5001.6
XS Rating Curve= 0 ,0
Exp/Cntr=0.3,0.1

Type RM Length L Ch R = 1 ,250     ,0,0,0
BEGIN DESCRIPTION:
MULBERRY CREEK TRIB 2 1.0
END DESCRIPTION:
XS GIS Cut Line= 4
      3531153.73     10439132.88      3531299.55     10438660.69
      3530872.47     10438348.19       3530225.1     10438368.96
#Sta/Elev= 30
  4176.3  377.23  4293.7  370.06  4321.1  367.52  4326.3  367.87  4353.7  366.02
  4462.1  362.29  4560.1  357.07  4767.3  349.43  4882.1  345.65    4897  346.43
  4976.5  347.02  5003.6  346.39  5018.3  347.09    5104  347.12  5125.8  349.46
    5148  350.49  5189.7  349.76  5250.1  350.54  5280.1  350.05  5310.1  351.54
  5381.3   352.5  5410.2  352.34  5436.3  353.77  5540.6  356.02  5570.3  356.56
    5653  360.04  5770.2  365.32  5780.4  367.06  5820.4  368.11  5847.4  369.63
#Mann= 8 ,-1 , 0
  4176.3     .05       0  4767.3     .05       0  4976.5     .03       0
  5018.3     .05       0  5381.3     .16       0  5436.3     .12       0
  5540.6     .16       0    5653     .05       0
Bank Sta=4976.5,5018.3
XS Rating Curve= 0 ,0
Exp/Cntr=0.3,0.1

Chan Stop Cuts=-1
Use User Specified Reach Order=0
Composite Channel Slope=5