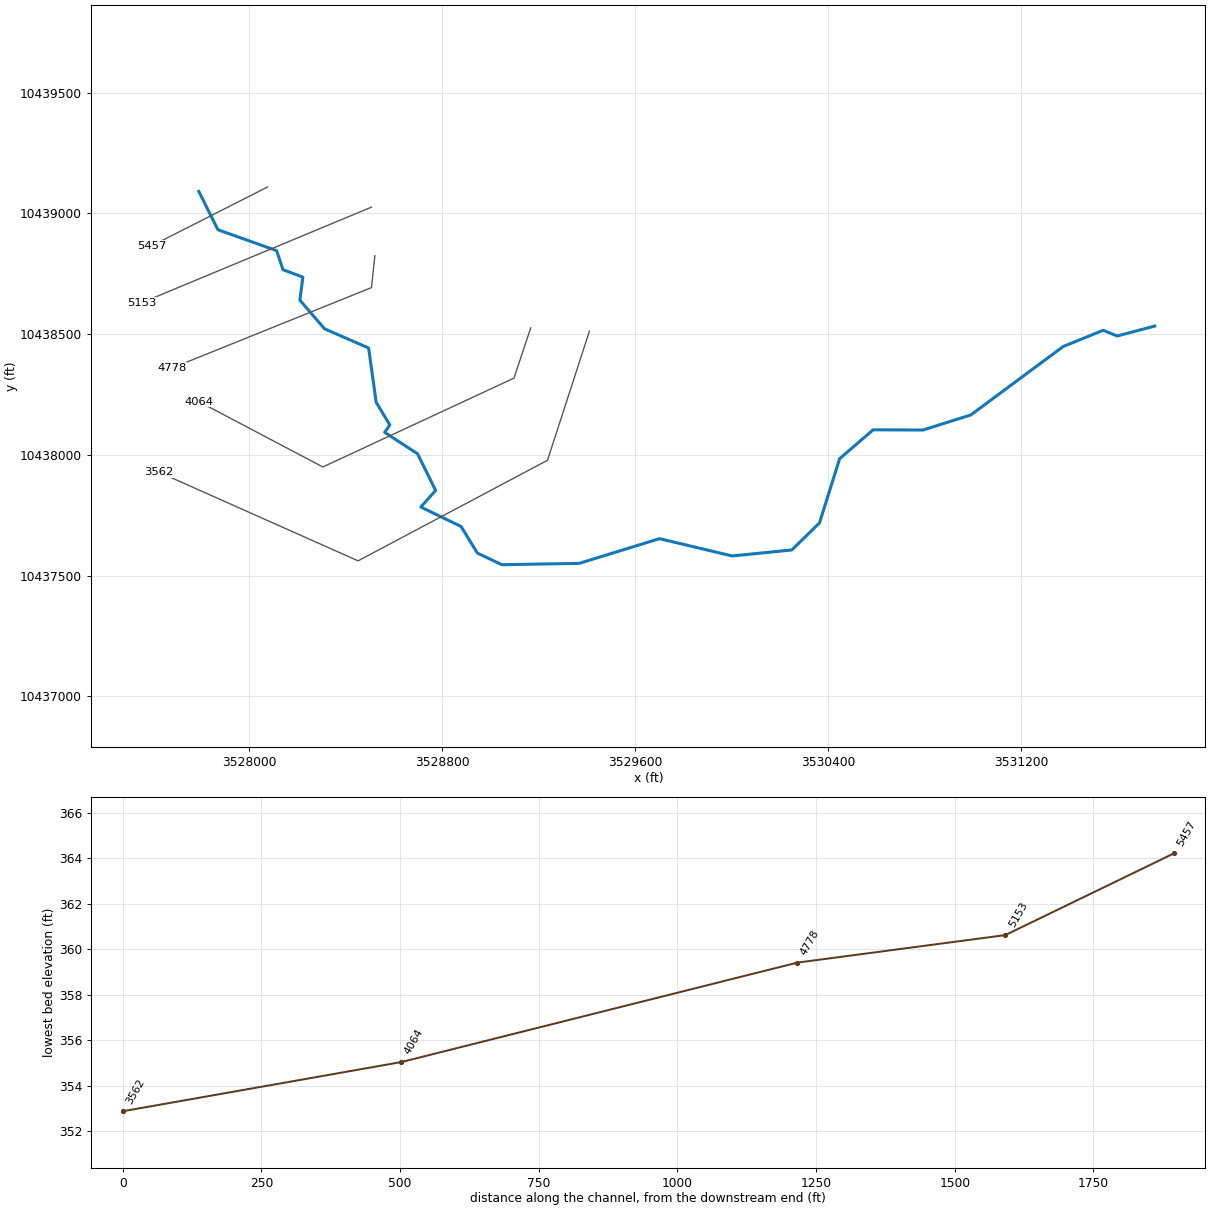
--- MULBERRY CREEK TRIB 3.prj (project) ---

Proj Title=MULBERRY CREEK TRIB 3 Base Level Engineering
Current Plan=p01
Default Exp/Contr=0.3,0.1
English Units
Geom File=g01
Flow File=f01
Plan File=p01
BEGIN DESCRIPTION:
MULBERRY CREEK TRIB 3
END DESCRIPTION:

--- MULBERRY CREEK TRIB 3.p01 (plan) ---

Plan Title=Multiple Run
Short Identifier=Multiple
Geom File=g01
Flow File=f01
Subcritical Flow
K Sum by GR= 0
Std Step Tol= 0.01
Critical Tol= 0.01
Num of Std Step Trials= 20
Max Error Tol= 0.3
Flow Tol Ratio= 0.001
Split Flow NTrial= 30
Split Flow Tol= 0.02
Split Flow Ratio= 0.02
Log Output Level= 0
Friction Slope Method= 1
Unsteady Friction Slope Method= 2
Unsteady Bridges Friction Slope Method= 1
Parabolic Critical Depth
Global Vel Dist=  1 , 1 , 1
Global Log Level= 0
CheckData=True
Encroach Param= -1, 0, 0, 0
BEGIN DESCRIPTION:
Multiple Run
END DESCRIPTION:

--- MULBERRY CREEK TRIB 3.f01 (steady flow) ---

Flow Title=Multiple
Number of Profiles=7
Profile Names=10-year,25-year,50-year,1pct_min,100-year,1pct_plu,500-year
River Rch & RM= MULBERRY CREEK T,Reach-1,5457
     467     614     729     634     858    1160    1181
Boundary for River Rch & Prof#=MULBERRY CREEK T,Reach-1,1
Up Type=0
Dn Type=3
Dn Slope=0.005
Boundary for River Rch & Prof#=MULBERRY CREEK T,Reach-1,2
Up Type=0
Dn Type=3
Dn Slope=0.005
Boundary for River Rch & Prof#=MULBERRY CREEK T,Reach-1,3
Up Type=0
Dn Type=3
Dn Slope=0.005
Boundary for River Rch & Prof#=MULBERRY CREEK T,Reach-1,4
Up Type=0
Dn Type=3
Dn Slope=0.005
Boundary for River Rch & Prof#=MULBERRY CREEK T,Reach-1,5
Up Type=0
Dn Type=3
Dn Slope=0.005
Boundary for River Rch & Prof#=MULBERRY CREEK T,Reach-1,6
Up Type=0
Dn Type=3
Dn Slope=0.005
Boundary for River Rch & Prof#=MULBERRY CREEK T,Reach-1,7
Up Type=0
Dn Type=3
Dn Slope=0.005

--- MULBERRY CREEK TRIB 3.g01 (geometry) ---

Geom Title=Existing Conditions

River Reach=MULBERRY CREEK T,Reach-1
Reach XY= 30
      3527792.04     10439091.62      3527871.37     10438932.65
      3528114.58     10438846.05      3528140.92     10438767.17
      3528223.25     10438736.39      3528211.03     10438640.84
      3528312.99     10438522.37      3528495.75     10438442.61
      3528526.91     10438218.21      3528583.42     10438123.85
      3528562.28     10438093.20      3528698.33     10438004.64
      3528773.21     10437852.61      3528712.01     10437783.94
      3528878.67     10437703.38      3528946.07     10437593.26
      3529047.79     10437545.08      3529367.88     10437550.51
      3529700.64     10437652.94      3530001.42     10437581.32
      3530248.82     10437606.06      3530363.40     10437718.04
      3530447.01     10437984.39      3530585.99     10438103.89
      3530791.88     10438102.91      3530990.51     10438165.47
      3531373.04     10438448.93      3531538.85     10438516.20
      3531596.70     10438492.50      3531752.38     10438533.63

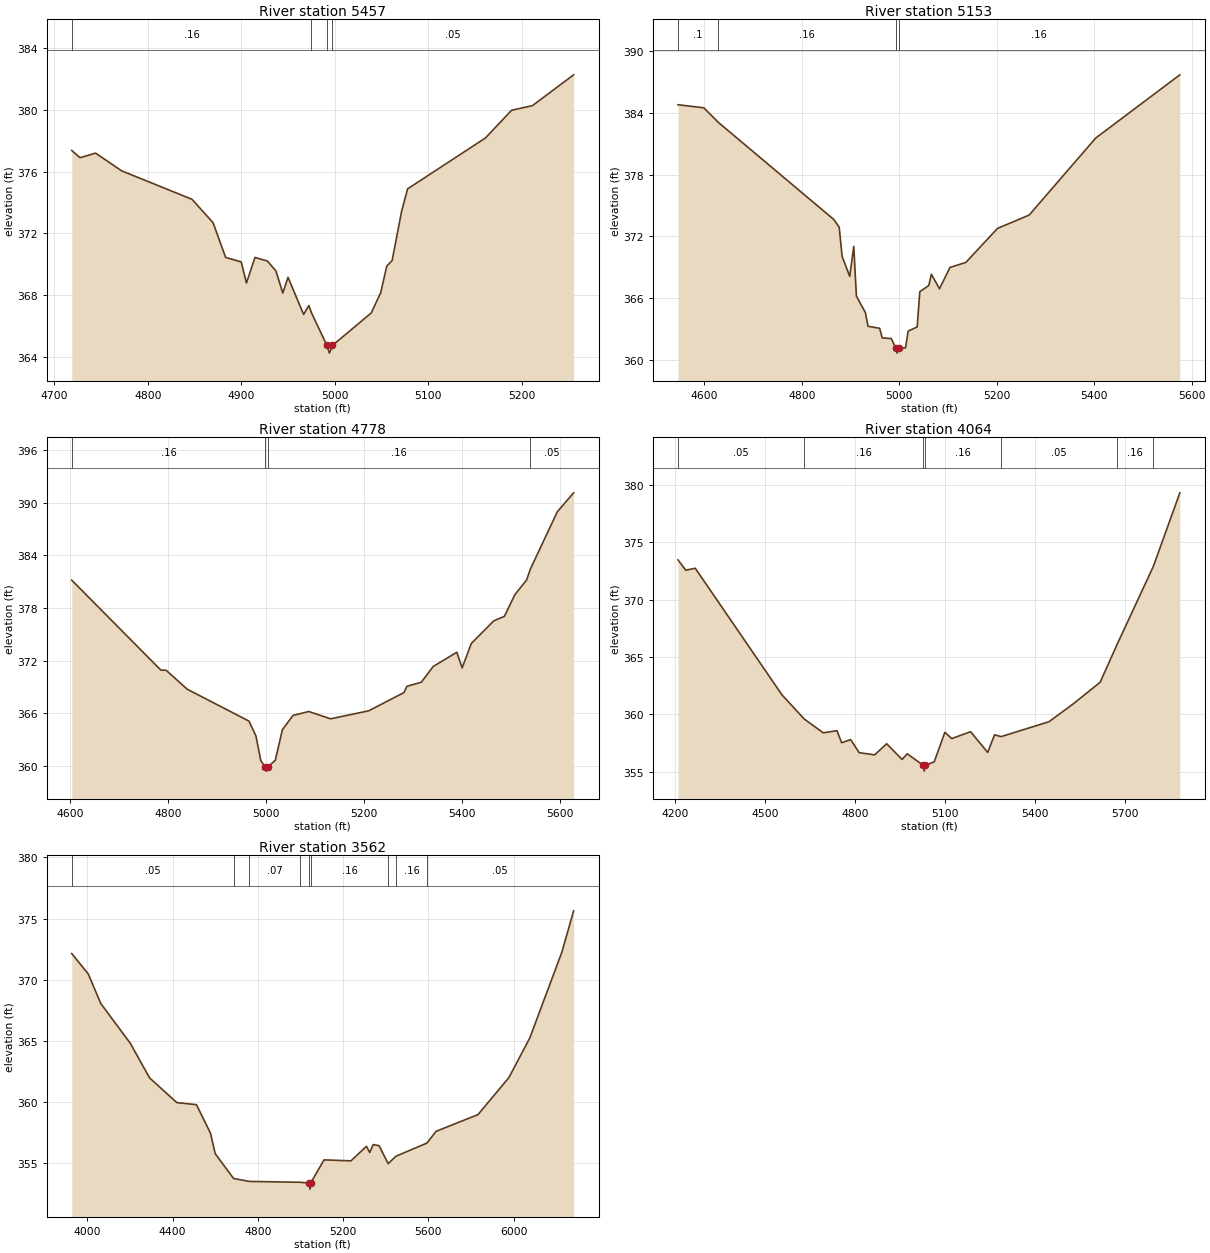
Type RM Length L Ch R = 1,5457,304,304,304
BEGIN DESCRIPTION:
MULBERRY CREEK TRIB 3 5.0
END DESCRIPTION:
XS GIS Cut Line= 2
      3528077.01     10439109.65      3527597.92     10438866.63
#Sta/Elev= 30
  4718.5  377.37  4727.4  376.90  4744.0  377.20  4771.9  376.05  4847.3  374.20
  4869.8  372.68  4883.2  370.43  4899.9  370.14  4905.5  368.77  4914.6  370.43
  4927.8  370.20  4937.0  369.56  4944.4  368.12  4950.0  369.14  4966.7  366.73
  4972.3  367.31  4975.1  366.84  4991.6  364.72  4994.3  364.22  4997.6  364.72
  5039.1  366.83  5049.2  368.14  5055.7  369.87  5061.4  370.22  5071.6  373.43
  5078.0  374.88  5161.3  378.18  5189.3  379.98  5211.6  380.28  5255.7  382.28
#Mann=4,-1,0
  4718.5    0.16       0  4975.1    0.05       0  4991.6    0.03       0
  4997.6    0.05       0
Bank Sta=4991.6,4997.6
Exp/Cntr=0.3,0.1

Type RM Length L Ch R = 1,5153,375,375,375
BEGIN DESCRIPTION:
MULBERRY CREEK TRIB 3 4.0
END DESCRIPTION:
XS GIS Cut Line= 2
      3528507.59     10439026.32      3527556.62     10438630.66
#Sta/Elev= 30
  4545.8  384.81  4598.8  384.51  4628.7  383.09  4865.8  373.63  4876.7  372.88
  4882.7  370.04  4898.3  368.10  4906.6  371.02  4912.0  366.18  4930.4  364.58
  4935.9  363.24  4959.7  363.05  4965.1  362.11  4983.5  362.05  4992.8  361.13
  4995.6  360.63  4998.8  361.13  5012.8  361.14  5018.2  362.77  5036.7  363.18
  5042.1  366.61  5060.5  367.21  5065.9  368.31  5082.5  366.89  5104.1  368.97
  5136.6  369.46  5201.6  372.77  5266.6  374.07  5403.0  381.56  5575.8  387.72
#Mann=4,-1,0
  4545.8     0.1       0  4628.7    0.16       0  4992.8    0.07       0
  4998.8    0.16       0
Bank Sta=4992.8,4998.8
Exp/Cntr=0.3,0.1

Type RM Length L Ch R = 1,4778,714,714,714
BEGIN DESCRIPTION:
MULBERRY CREEK TRIB 3 3.0
END DESCRIPTION:
XS GIS Cut Line= 3
      3528521.44     10438824.92      3528507.55     10438692.98
      3527681.13     10438359.63
#Sta/Elev= 30
  4603.4  381.17  4785.1  370.93  4795.9  370.91  4839.0  368.75  4964.9  365.12
  4979.2  363.42  4989.1  360.60  4997.7  359.92  5000.5  359.42  5003.7  359.92
  5018.6  360.65  5033.1  364.14  5054.7  365.76  5087.0  366.21  5131.4  365.38
  5209.2  366.29  5281.1  368.37  5287.1  369.08  5316.6  369.55  5340.8  371.34
  5388.9  372.96  5399.8  371.18  5418.6  373.97  5464.4  376.54  5486.0  377.05
  5507.5  379.53  5531.4  381.20  5538.9  382.42  5593.8  388.95  5627.2  391.12
#Mann=4,-1,0
  4603.4    0.16       0  4997.7    0.07       0  5003.7    0.16       0
  5538.9    0.05       0
Bank Sta=4997.7,5003.7
Exp/Cntr=0.3,0.1

Type RM Length L Ch R = 1,4064,502,502,502
BEGIN DESCRIPTION:
MULBERRY CREEK TRIB 3 2.0
END DESCRIPTION:
XS GIS Cut Line= 4
      3529167.27     10438526.29      3529097.83     10438317.98
      3528306.16     10437949.92      3527792.29     10438220.75
#Sta/Elev= 30
  4209.4  373.48  4235.4  372.58  4267.0  372.75  4556.6  361.69  4630.4  359.60
  4693.8  358.39  4739.5  358.58  4755.1  357.53  4785.3  357.80  4813.7  356.66
  4865.4  356.47  4905.3  357.44  4956.6  356.07  4973.9  356.56  5027.8  355.55
  5030.6  355.05  5033.8  355.55  5063.9  355.86  5099.4  358.44  5122.3  357.89
  5185.2  358.49  5242.2  356.68  5265.1  358.22  5286.9  358.06  5446.5  359.36
  5529.0  360.95  5617.1  362.80  5673.3  366.08  5794.7  372.92  5882.9  379.33
#Mann=7,-1,0
  4209.4    0.05       0  4630.4    0.16       0  5027.8    0.07       0
  5033.8    0.16       0  5286.9    0.05       0  5673.3    0.16       0
  5794.7    0.05       0
Bank Sta=5027.8,5033.8
Exp/Cntr=0.3,0.1

Type RM Length L Ch R = 1,3562,0,0,0
BEGIN DESCRIPTION:
MULBERRY CREEK TRIB 3 1.0
END DESCRIPTION:
XS GIS Cut Line= 4
      3529410.34     10438512.44      3529236.72     10437977.70
      3528452.00     10437561.03      3527626.38     10437928.74
#Sta/Elev= 30
  3926.8  372.14  4004.3  370.47  4062.9  368.06  4201.3  364.81  4291.9  361.98
  4419.8  359.96  4511.9  359.79  4577.9  357.45  4599.8  355.79  4686.0  353.76
  4760.2  353.52  4997.5  353.45  5041.5  353.39  5044.3  352.89  5047.5  353.39
  5110.5  355.28  5236.7  355.20  5309.4  356.39  5324.7  355.88  5341.0  356.53
  5368.6  356.44  5411.4  354.97  5447.7  355.58  5592.9  356.65  5635.9  357.61
  5832.7  358.98  5977.6  362.00  6076.0  365.25  6226.4  372.26  6281.3  375.63
#Mann=9,-1,0
  3926.8    0.05       0  4686.0    0.16       0  4760.2    0.07       0
  4997.5    0.16       0  5041.5    0.07       0  5047.5    0.16       0
  5411.4    0.05       0  5447.7    0.16       0  5592.9    0.05       0
Bank Sta=5041.5,5047.5
Exp/Cntr=0.3,0.1

Chan Stop Cuts=-1