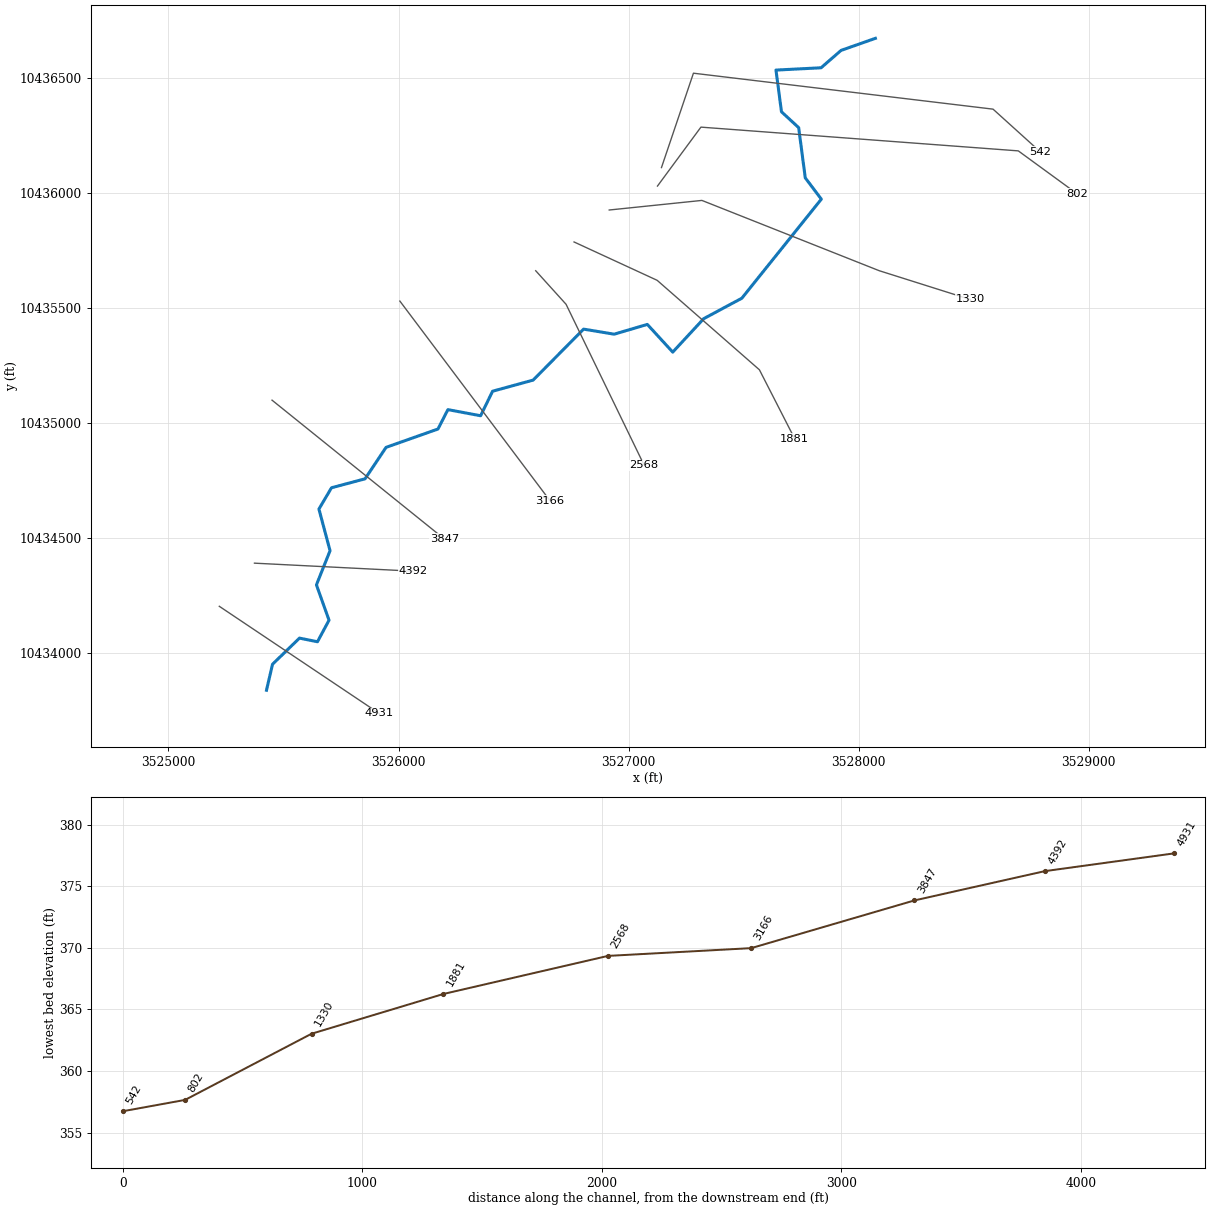
--- MULBERRY CREEK TRIB 4.prj (project) ---

Proj Title=MULBERRY CREEK TRIB 4 Base Level Engineering
Current Plan=p01
Default Exp/Contr=0.3,0.1
English Units
Geom File=g01
Flow File=f01
Plan File=p01
BEGIN DESCRIPTION:
MULBERRY CREEK TRIB 4
END DESCRIPTION:

--- MULBERRY CREEK TRIB 4.p01 (plan) ---

Plan Title=Multiple Run
Short Identifier=Multiple
Geom File=g01
Flow File=f01
Subcritical Flow
K Sum by GR= 0
Std Step Tol= 0.01
Critical Tol= 0.01
Num of Std Step Trials= 20
Max Error Tol= 0.3
Flow Tol Ratio= 0.001
Split Flow NTrial= 30
Split Flow Tol= 0.02
Split Flow Ratio= 0.02
Log Output Level= 0
Friction Slope Method= 1
Unsteady Friction Slope Method= 2
Unsteady Bridges Friction Slope Method= 1
Parabolic Critical Depth
Global Vel Dist=  1 , 1 , 1
Global Log Level= 0
CheckData=True
Encroach Param= -1, 0, 0, 0
BEGIN DESCRIPTION:
Multiple Run
END DESCRIPTION:

--- MULBERRY CREEK TRIB 4.f01 (steady flow) ---

Flow Title=Multiple
Number of Profiles=7
Profile Names=10-year,25-year,50-year,1pct_min,100-year,1pct_plu,500-year
River Rch & RM= MULBERRY CREEK T,Reach-1,4931
     789    1074    1307    1161    1570    2123    2258
Boundary for River Rch & Prof#=MULBERRY CREEK T,Reach-1,1
Up Type=0
Dn Type=3
Dn Slope=0.005
Boundary for River Rch & Prof#=MULBERRY CREEK T,Reach-1,2
Up Type=0
Dn Type=3
Dn Slope=0.005
Boundary for River Rch & Prof#=MULBERRY CREEK T,Reach-1,3
Up Type=0
Dn Type=3
Dn Slope=0.005
Boundary for River Rch & Prof#=MULBERRY CREEK T,Reach-1,4
Up Type=0
Dn Type=3
Dn Slope=0.005
Boundary for River Rch & Prof#=MULBERRY CREEK T,Reach-1,5
Up Type=0
Dn Type=3
Dn Slope=0.005
Boundary for River Rch & Prof#=MULBERRY CREEK T,Reach-1,6
Up Type=0
Dn Type=3
Dn Slope=0.005
Boundary for River Rch & Prof#=MULBERRY CREEK T,Reach-1,7
Up Type=0
Dn Type=3
Dn Slope=0.005

--- MULBERRY CREEK TRIB 4.g01 (geometry) ---

Geom Title=Existing Conditions

River Reach=MULBERRY CREEK T,Reach-1
Reach XY= 30
      3525426.12     10433838.52      3525452.35     10433951.65
      3525569.58     10434065.15      3525647.75     10434049.38
      3525697.91     10434143.04      3525643.20     10434296.55
      3525702.37     10434444.91      3525654.00     10434625.96
      3525708.72     10434718.54      3525854.56     10434757.43
      3525945.71     10434894.07      3526171.46     10434973.91
      3526214.52     10435058.11      3526356.74     10435031.49
      3526408.73     10435138.07      3526584.98     10435186.41
      3526804.19     10435407.95      3526937.00     10435385.92
      3527081.23     10435428.42      3527191.62     10435308.01
      3527326.31     10435453.47      3527491.91     10435542.25
      3527837.30     10435972.76      3527767.65     10436065.16
      3527738.81     10436283.68      3527664.19     10436352.43
      3527640.21     10436533.66      3527836.22     10436543.68
      3527923.13     10436619.18      3528072.11     10436671.64

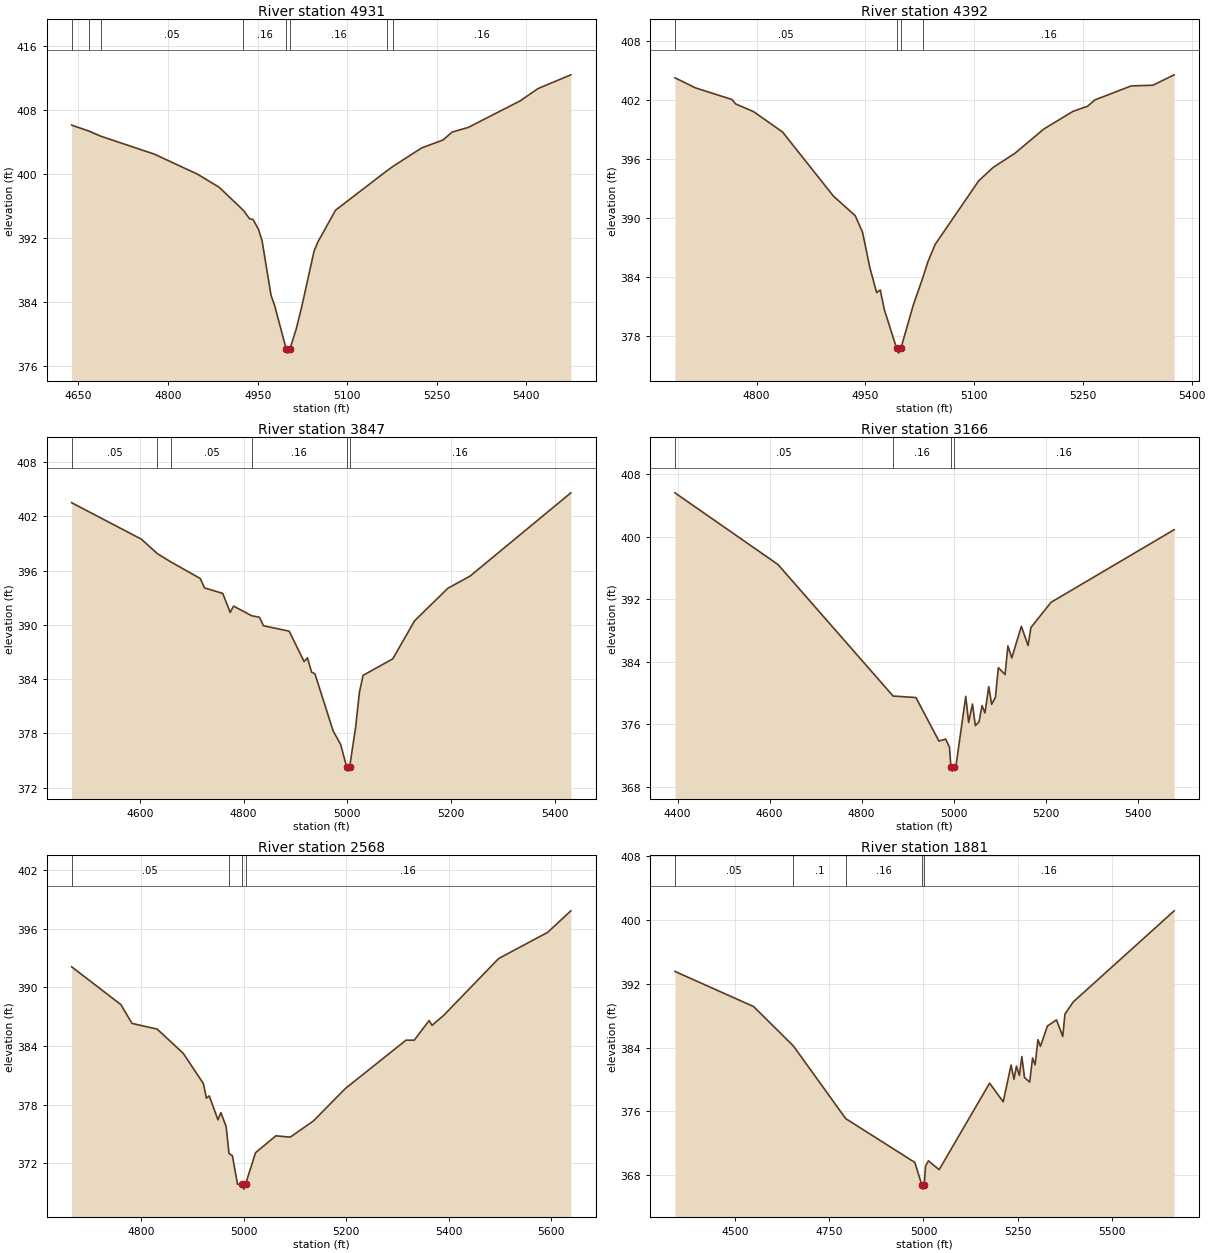
Type RM Length L Ch R = 1,4931,539,539,539
BEGIN DESCRIPTION:
MULBERRY CREEK TRIB 4 11.0
END DESCRIPTION:
XS GIS Cut Line= 2
      3525221.05     10434203.42      3525915.58     10433738.09
#Sta/Elev= 30
  4638.5  406.13  4667.7  405.38  4687.2  404.75  4777.3  402.50  4849.4  400.00
  4885.4  398.38  4926.0  395.50  4936.4  394.45  4942.4  394.34  4951.4  393.12
  4957.4  391.71  4972.4  384.89  4978.4  383.62  4997.9  378.16  5000.6  377.66
  5003.9  378.16  5014.5  380.64  5023.4  383.31  5044.5  390.40  5050.5  391.49
  5080.5  395.51  5167.2  400.47  5176.1  400.95  5224.6  403.28  5260.6  404.28
  5275.6  405.26  5302.6  405.84  5389.7  409.16  5419.7  410.70  5474.5  412.41
#Mann=8,-1,0
  4638.5    0.05       0  4667.7     0.1       0  4687.2    0.05       0
  4926.0    0.16       0  4997.9    0.07       0  5003.9    0.16       0
  5167.2    0.12       0  5176.1    0.16       0
Bank Sta=4997.9,5003.9
Exp/Cntr=0.3,0.1

Type RM Length L Ch R = 1,4392,545,545,545
BEGIN DESCRIPTION:
MULBERRY CREEK TRIB 4 10.0
END DESCRIPTION:
XS GIS Cut Line= 2
      3525373.85     10434390.89      3526061.38     10434356.17
#Sta/Elev= 30
  4687.5  404.29  4715.8  403.26  4765.9  402.08  4771.3  401.62  4795.9  400.84
  4835.9  398.76  4906.0  392.23  4936.1  390.23  4946.1  388.56  4956.1  384.99
  4965.6  382.39  4970.6  382.66  4976.1  380.69  4993.1  376.72  4995.9  376.22
  4999.1  376.72  5016.2  381.13  5029.3  383.91  5036.2  385.51  5046.2  387.29
  5106.3  393.78  5126.3  395.15  5156.3  396.59  5196.4  399.08  5236.5  400.87
  5256.5  401.39  5266.5  402.03  5316.6  403.46  5346.6  403.53  5375.9  404.59
#Mann=4,-1,0
  4687.5    0.05       0  4993.1    0.03       0  4999.1    0.05       0
  5029.3    0.16       0
Bank Sta=4993.1,4999.1
Exp/Cntr=0.3,0.1

Type RM Length L Ch R = 1,3847,681,681,681
BEGIN DESCRIPTION:
MULBERRY CREEK TRIB 4 9.0
END DESCRIPTION:
XS GIS Cut Line= 2
      3525450.27     10435099.22      3526199.28     10434495.85
#Sta/Elev= 30
  4468.7  403.49  4603.1  399.46  4634.0  397.86  4660.1  396.94  4716.7  395.11
  4724.7  394.08  4759.9  393.47  4774.2  391.37  4780.7  392.07  4815.7  391.00
  4830.6  390.84  4838.2  389.90  4887.8  389.30  4916.6  385.94  4923.0  386.35
  4931.0  384.77  4937.4  384.60  4972.6  378.27  4987.0  376.79  4998.4  374.34
  5001.1  373.84  5004.4  374.34  5015.8  378.66  5023.2  382.56  5030.2  384.42
  5087.4  386.24  5129.4  390.44  5193.4  394.03  5236.5  395.39  5430.5  404.58
#Mann=6,-1,0
  4468.7    0.05       0  4634.0    0.16       0  4660.1    0.05       0
  4815.7    0.16       0  4998.4    0.07       0  5004.4    0.16       0
Bank Sta=4998.4,5004.4
Exp/Cntr=0.3,0.1

Type RM Length L Ch R = 1,3166,598,598,598
BEGIN DESCRIPTION:
MULBERRY CREEK TRIB 4 7.0
END DESCRIPTION:
XS GIS Cut Line= 2
      3526005.80     10435529.80      3526657.85     10434662.71
#Sta/Elev= 30
  4394.3  405.63  4618.1  396.45  4868.4  379.59  4918.0  379.40  4968.0  373.82
  4982.6  374.08  4990.9  373.03  4994.1  370.47  4996.9  369.97  5000.1  370.47
  5005.1  370.68  5026.3  379.55  5032.5  376.21  5040.9  378.57  5047.1  375.80
  5055.1  376.28  5061.7  378.37  5068.0  377.43  5076.3  380.80  5082.5  378.53
  5090.8  379.44  5097.1  383.23  5111.7  382.35  5117.9  386.02  5126.3  384.48
  5147.1  388.53  5161.7  386.07  5167.9  388.37  5211.6  391.60  5479.2  400.91
#Mann=4,-1,0
  4394.3    0.05       0  4868.4    0.16       0  4994.1    0.07       0
  5000.1    0.16       0
Bank Sta=4994.1,5000.1
Exp/Cntr=0.3,0.1

Type RM Length L Ch R = 1,2568,687,687,687
BEGIN DESCRIPTION:
MULBERRY CREEK TRIB 4 6.0
END DESCRIPTION:
XS GIS Cut Line= 3
      3526596.12     10435661.70      3526728.04     10435515.89
      3527067.18     10434816.84
#Sta/Elev= 30
  4664.8  392.12  4760.9  388.24  4782.5  386.32  4831.8  385.73  4882.5  383.25
  4921.7  380.16  4927.7  378.66  4933.2  378.89  4950.2  376.44  4955.8  377.18
  4966.2  375.74  4971.7  373.00  4978.3  372.76  4988.4  369.84  4997.9  369.84
  5000.7  369.34  5003.9  369.84  5023.5  373.07  5063.1  374.80  5091.2  374.67
  5136.3  376.32  5198.5  379.64  5316.9  384.60  5333.0  384.60  5362.0  386.61
  5367.6  386.12  5390.2  387.13  5497.5  392.96  5593.3  395.65  5638.4  397.85
#Mann=4,-1,0
  4664.8    0.05       0  4971.7    0.16       0  4997.9    0.07       0
  5003.9    0.16       0
Bank Sta=4997.9,5003.9
Exp/Cntr=0.3,0.1

Type RM Length L Ch R = 1,1881,551,551,551
BEGIN DESCRIPTION:
MULBERRY CREEK TRIB 4 5.0
END DESCRIPTION:
XS GIS Cut Line= 4
      3526762.73     10435786.74      3527123.87     10435620.06
      3527568.32     10435231.17      3527721.07     10434932.60
#Sta/Elev= 30
  4341.1  393.56  4549.7  389.15  4655.3  384.20  4793.8  375.10  4977.1  369.60
  4995.9  366.75  4998.7  366.25  5001.9  366.75  5005.6  369.15  5013.1  369.80
  5041.6  368.69  5175.4  379.54  5211.5  377.21  5232.4  381.81  5240.0  380.03
  5246.6  381.67  5254.2  380.51  5260.9  382.88  5268.0  380.25  5281.7  379.67
  5289.3  382.70  5296.0  381.84  5303.6  385.00  5310.2  384.16  5328.6  386.71
  5352.8  387.48  5369.4  385.40  5375.1  388.20  5397.3  389.74  5664.8  401.16
#Mann=5,-1,0
  4341.1    0.05       0  4655.3     0.1       0  4793.8    0.16       0
  4995.9    0.07       0  5001.9    0.16       0
Bank Sta=4995.9,5001.9
Exp/Cntr=0.3,0.1

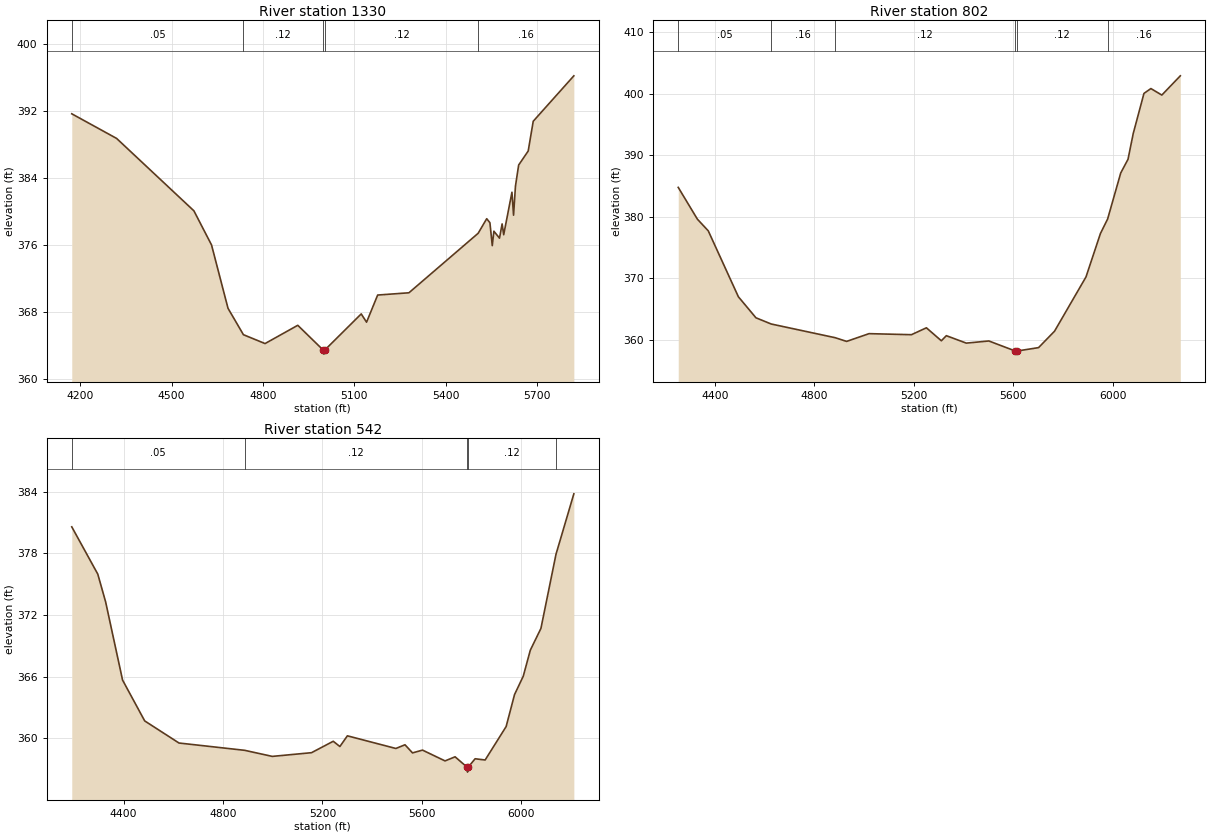
Type RM Length L Ch R = 1,1330,528,528,528
BEGIN DESCRIPTION:
MULBERRY CREEK TRIB 4 2.0
END DESCRIPTION:
XS GIS Cut Line= 4
      3526915.59     10435925.62      3527318.32     10435967.28
      3528089.15     10435661.73      3528485.02     10435536.71
#Sta/Elev= 30
  4172.1  391.70  4319.4  388.76  4573.3  380.12  4631.2  376.05  4685.3  368.49
  4735.9  365.34  4807.0  364.28  4914.5  366.46  4997.6  363.52  5000.3  363.02
  5003.6  363.52  5122.9  367.82  5140.4  366.83  5176.9  370.07  5279.6  370.34
  5507.0  377.44  5535.1  379.18  5545.6  378.70  5553.4  375.97  5558.6  377.69
  5577.1  376.86  5585.7  378.56  5590.9  377.27  5618.0  382.34  5623.3  379.60
  5629.5  383.06  5640.0  385.58  5671.4  387.26  5687.9  390.81  5821.3  396.23
#Mann=5,-1,0
  4172.1    0.05       0  4735.9    0.12       0  4997.6    0.07       0
  5003.6    0.12       0  5507.0    0.16       0
Bank Sta=4997.6,5003.6
Exp/Cntr=0.3,0.1

Type RM Length L Ch R = 1,802,260,260,260
BEGIN DESCRIPTION:
MULBERRY CREEK TRIB 4 1.1
END DESCRIPTION:
XS GIS Cut Line= 4
      3527125.27     10436029.66      3527314.09     10436285.76
      3528693.32     10436182.56      3528950.23     10435995.08
#Sta/Elev= 30
  4253.1  384.77  4330.1  379.60  4373.9  377.70  4495.0  366.98  4565.6  363.56
  4627.0  362.55  4884.4  360.32  4930.3  359.72  5020.5  360.98  5191.0  360.81
  5251.2  361.93  5311.4  359.82  5331.4  360.65  5411.6  359.44  5502.3  359.79
  5609.2  358.15  5611.9  357.65  5615.2  358.15  5702.4  358.71  5766.6  361.38
  5893.0  370.20  5951.2  377.27  5980.0  379.62  6032.8  387.11  6062.1  389.34
  6083.0  393.52  6126.2  400.05  6154.1  400.84  6198.1  399.78  6272.4  402.91
#Mann=6,-1,0
  4253.1    0.05       0  4627.0    0.16       0  4884.4    0.12       0
  5609.2    0.07       0  5615.2    0.12       0  5980.0    0.16       0
Bank Sta=5609.2,5615.2
Exp/Cntr=0.3,0.1

Type RM Length L Ch R = 1,542,0,0,0
BEGIN DESCRIPTION:
MULBERRY CREEK TRIB 4 1.0
END DESCRIPTION:
XS GIS Cut Line= 4
      3527142.65     10436109.97      3527281.54     10436520.14
      3528583.63     10436363.89      3528787.33     10436179.69
#Sta/Elev= 30
  4191.7  380.58  4296.4  375.98  4327.9  373.28  4396.0  365.68  4485.0  361.71
  4622.9  359.56  4887.0  358.85  4998.0  358.26  5155.9  358.62  5243.2  359.73
  5269.9  359.22  5300.1  360.26  5495.0  359.03  5531.8  359.39  5562.0  358.60
  5602.3  358.87  5692.9  357.82  5733.2  358.22  5780.6  357.23  5783.3  356.73
  5786.6  357.23  5813.8  358.03  5854.1  357.91  5938.5  361.16  5972.3  364.27
  6007.4  366.06  6035.8  368.59  6078.4  370.70  6139.0  377.91  6210.8  383.79
#Mann=5,-1,0
  4191.7    0.05       0  4887.0    0.12       0  5780.6    0.07       0
  5786.6    0.12       0  6139.0    0.16       0
Bank Sta=5780.6,5786.6
Exp/Cntr=0.3,0.1

Chan Stop Cuts=-1