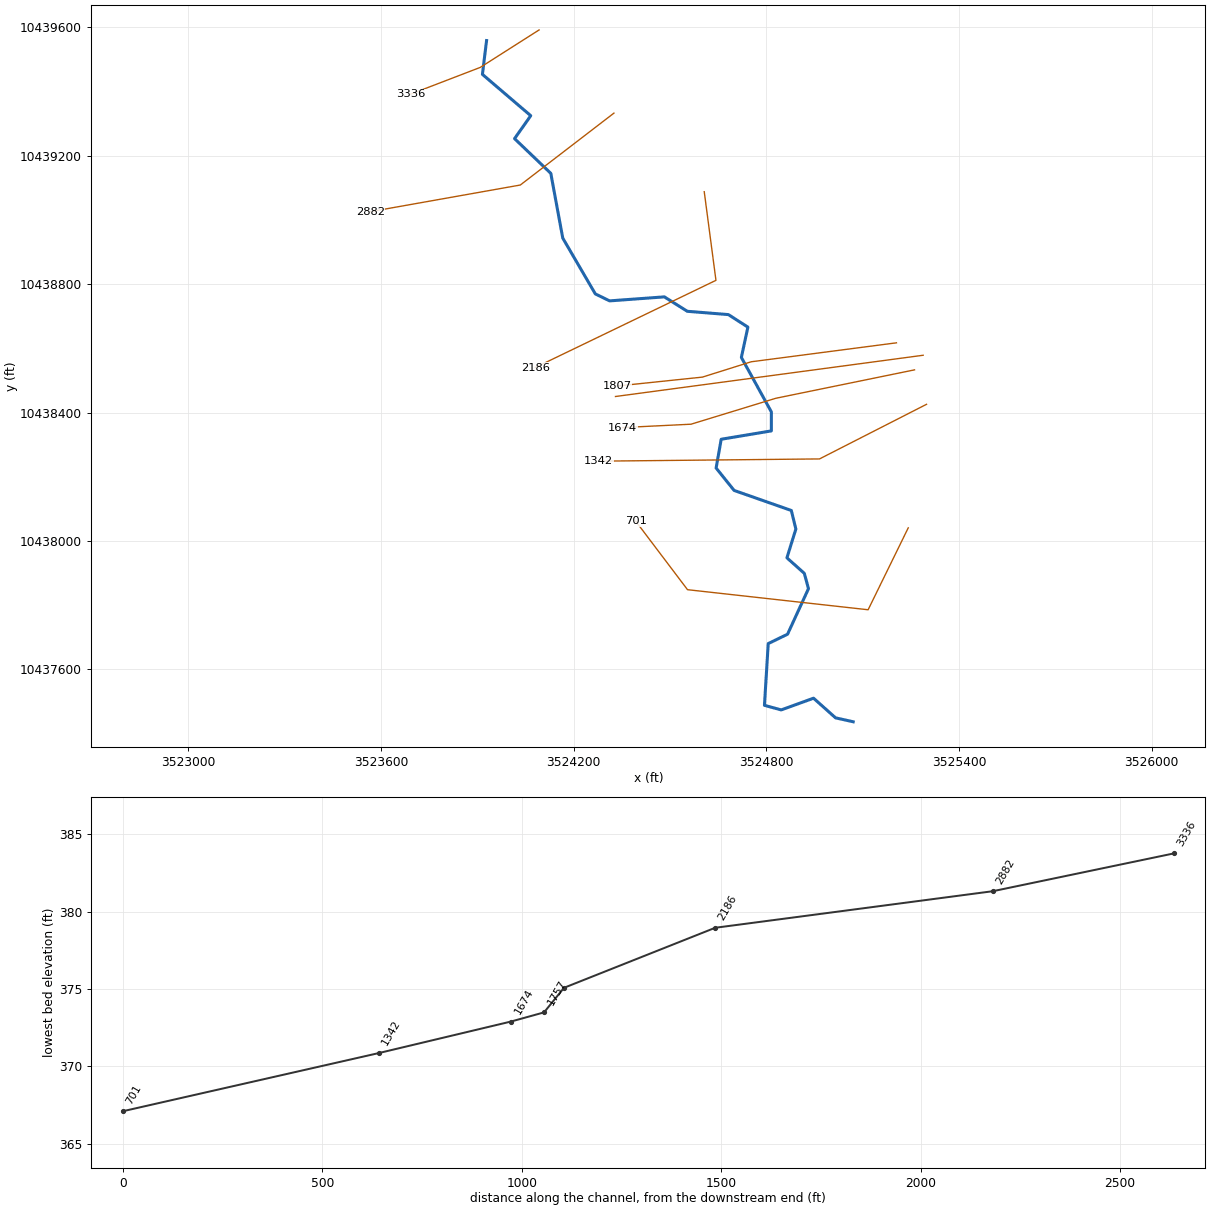
--- MULBERRY CREEK TRIB 5.prj (project) ---

Proj Title=MULBERRY CREEK TRIB 5 Base Level Engineering
Current Plan=p01
Default Exp/Contr=0.3,0.1
English Units
Geom File=g01
Flow File=f01
Plan File=p01
Y Axis Title=Elevation
X Axis Title(PF)=Main Channel Distance
X Axis Title(XS)=Station
BEGIN DESCRIPTION:
MULBERRY CREEK TRIB 5
END DESCRIPTION:
DSS Export Rating Curves= 0
DSS Export Rating Curve Sorted= 0
DSS Export Volume Flow Curves= 0
DXF OffsetX= 0
DXF OffsetY= 0
DXF ScaleX= 1
DXF ScaleY= 10

--- MULBERRY CREEK TRIB 5.p01 (plan) ---

Plan Title=Multiple Run
Short Identifier=Multiple
Geom File=g01
Flow File=f01
Subcritical Flow
K Sum by GR= 0
Std Step Tol= 0.01
Critical Tol= 0.01
Num of Std Step Trials= 20
Max Error Tol= 0.3
Flow Tol Ratio= 0.001
Split Flow NTrial= 30
Split Flow Tol= 0.02
Split Flow Ratio= 0.02
Log Output Level= 0
Friction Slope Method= 1
Unsteady Friction Slope Method= 2
Unsteady Bridges Friction Slope Method= 1
Parabolic Critical Depth
Global Vel Dist=  1 , 1 , 1
Global Log Level= 0
CheckData=True
Encroach Param= -1, 0, 0, 0
BEGIN DESCRIPTION:
Multiple Run
END DESCRIPTION:

--- MULBERRY CREEK TRIB 5.f01 (steady flow) ---

Flow Title=Multiple
Program Version=4.10
Number of Profiles= 7
Profile Names=10-year,25-year,50-year,1pct_min,100-year,1pct_plu,500-year
River Rch & RM=MULBERRY CREEK T,Reach-1         ,3336
     468     620     740     647     875    1184    1219
Boundary for River Rch & Prof#=MULBERRY CREEK T,Reach-1         , 1
Up Type= 0
Dn Type= 3
Dn Slope=0.006
Boundary for River Rch & Prof#=MULBERRY CREEK T,Reach-1         , 2
Up Type= 0
Dn Type= 3
Dn Slope=0.006
Boundary for River Rch & Prof#=MULBERRY CREEK T,Reach-1         , 3
Up Type= 0
Dn Type= 3
Dn Slope=0.006
Boundary for River Rch & Prof#=MULBERRY CREEK T,Reach-1         , 4
Up Type= 0
Dn Type= 3
Dn Slope=0.006
Boundary for River Rch & Prof#=MULBERRY CREEK T,Reach-1         , 5
Up Type= 0
Dn Type= 3
Dn Slope=0.006
Boundary for River Rch & Prof#=MULBERRY CREEK T,Reach-1         , 6
Up Type= 0
Dn Type= 3
Dn Slope=0.006
Boundary for River Rch & Prof#=MULBERRY CREEK T,Reach-1         , 7
Up Type= 0
Dn Type= 3
Dn Slope=0.006
DSS Import GetInterval= 0
DSS Import GetPeak= 0
DSS Import FillOption= 0

--- MULBERRY CREEK TRIB 5.g01 (geometry) ---

Geom Title=Existing Conditions
Program Version=4.10

River Reach=MULBERRY CREEK T,Reach-1
Reach XY= 30
       3523928.5     10439558.54       3523915.6     10439453.26
      3524066.13      10439324.5      3524015.68     10439253.08
      3524128.56       10439145.      3524165.87      10438943.2
      3524267.24     10438769.47      3524311.81     10438747.75
      3524482.33     10438760.22      3524553.62     10438715.33
      3524681.69     10438705.02      3524742.45     10438665.96
      3524722.11     10438571.64      3524815.58     10438401.85
      3524815.58     10438342.83      3524659.33     10438316.78
       3524643.5     10438227.11      3524699.55     10438157.38
      3524877.73     10438094.89      3524891.89     10438037.06
      3524864.01     10437947.47      3524918.14     10437899.12
      3524931.17     10437851.42        3524866.     10437709.54
      3524805.79     10437680.27      3524794.02     10437488.02
      3524846.26     10437473.74      3524946.93     10437510.22
      3525015.54     10437449.02      3525070.43     10437436.81

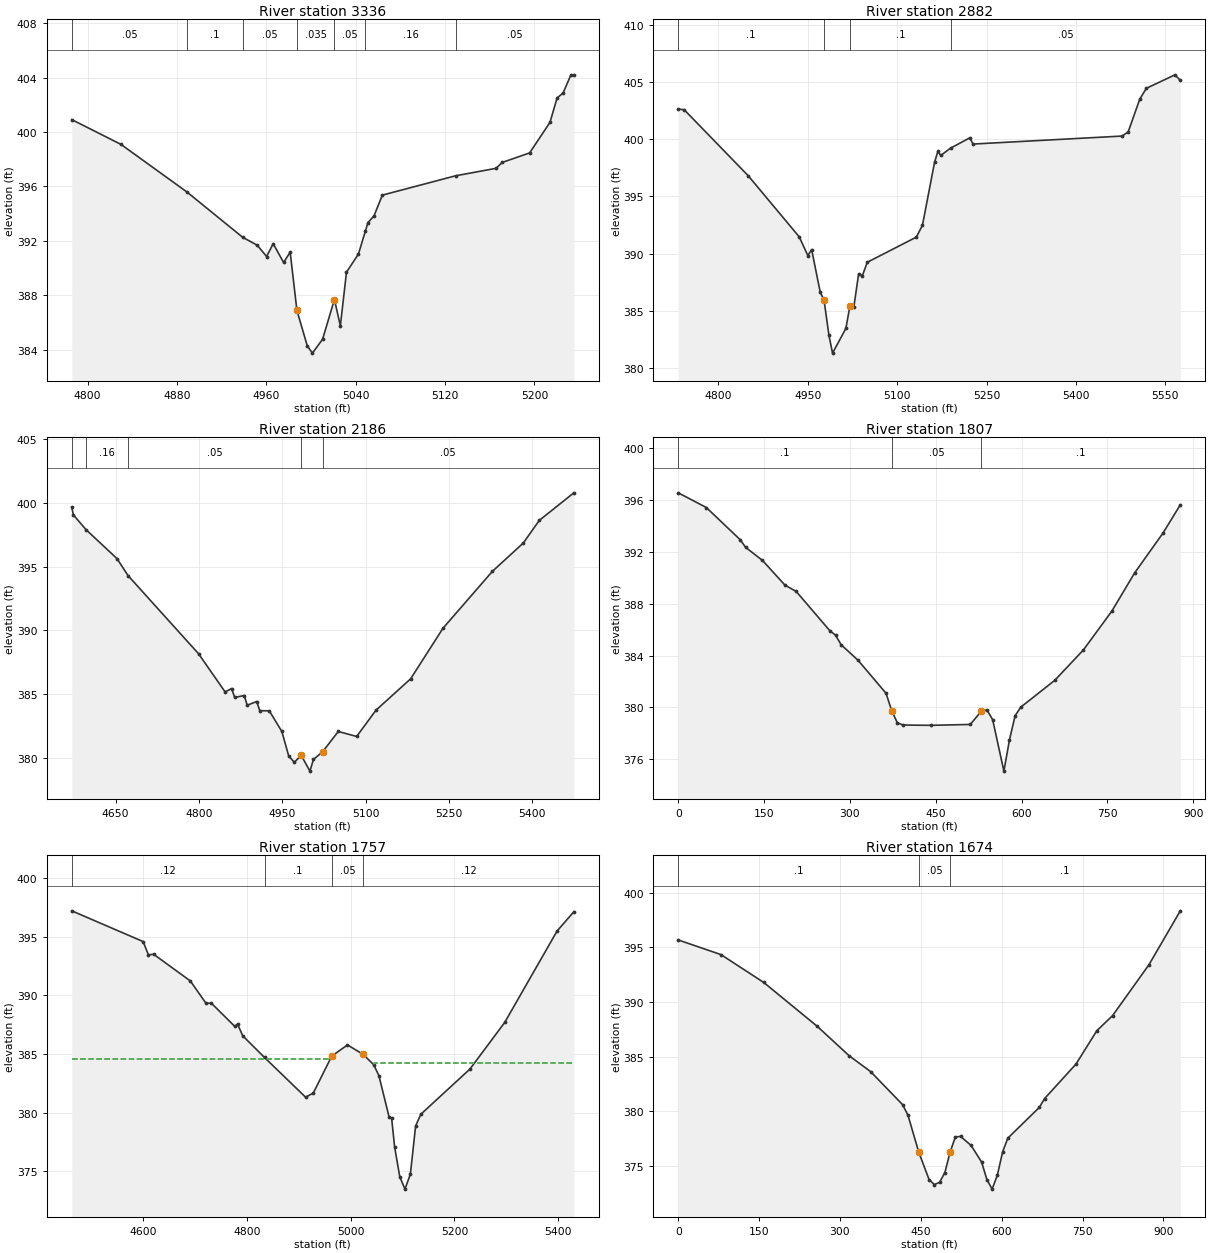
Type RM Length L Ch R = 1 ,3336    ,454,454,454
BEGIN DESCRIPTION:
MULBERRY CREEK TRIB 5 7.0
END DESCRIPTION:
XS GIS Cut Line= 3
      3524092.09     10439591.63      3523908.82     10439474.92
      3523692.14     10439391.66
#Sta/Elev= 30
  4785.9  400.91  4829.9  399.09    4889  395.59  4938.9  392.26  4951.9  391.68
  4960.3  390.85  4966.2  391.79  4975.5  390.41  4981.4  391.17  4987.4   386.9
  4996.7  384.28  5001.3  383.75  5010.4  384.77    5021  387.69  5026.3  385.76
  5031.8   389.7  5042.5  391.03  5048.8  392.74    5051  393.34  5056.4  393.83
  5063.9  395.36  5129.4  396.78  5165.7  397.33  5171.1  397.76  5195.7  398.46
  5213.9   400.7  5220.3   402.5  5225.7  402.87  5232.7   404.2  5235.3   404.2
#Mann= 7 ,-1 , 0
  4785.9     .05       0    4889      .1       0  4938.9     .05       0
  4987.4    .035       0    5021     .05       0  5048.8     .16       0
  5129.4     .05       0
Bank Sta=4987.4,5021
XS Rating Curve= 0 ,0
Exp/Cntr=0.3,0.1

Type RM Length L Ch R = 1 ,2882    ,696,696,696
BEGIN DESCRIPTION:
MULBERRY CREEK TRIB 5 5.0
END DESCRIPTION:
XS GIS Cut Line= 3
      3524325.27     10439332.57      3524033.59      10439108.6
      3523565.97     10439025.47
#Sta/Elev= 30
  4732.6  402.64  4742.6  402.58  4850.1  396.81  4935.7  391.47  4950.2  389.83
  4956.5  390.36    4971  386.62  4977.3  385.96  4985.5  382.88  4991.6  381.31
    5014  383.47  5020.9  385.47  5027.2   385.3  5035.4  388.24  5041.7  388.08
  5049.9  389.25  5132.3  391.45  5142.5  392.48  5162.8  397.98  5168.3  398.93
  5173.3  398.59  5189.6  399.22  5222.2  400.13  5227.3  399.58  5477.7  400.28
  5487.8  400.64  5507.3  403.51  5518.3  404.45  5566.3  405.63  5575.3  405.15
#Mann= 4 ,-1 , 0
  4732.6      .1       0  4977.3     .07       0  5020.9      .1       0
  5189.6     .05       0
Bank Sta=4977.3,5020.9
XS Rating Curve= 0 ,0
Exp/Cntr=0.3,0.1

Type RM Length L Ch R = 1 ,2186    ,379,379,379
BEGIN DESCRIPTION:
MULBERRY CREEK TRIB 5 4.0
END DESCRIPTION:
XS GIS Cut Line= 3
      3524606.51     10439087.79      3524642.97     10438811.73
       3524080.1     10438540.19
#Sta/Elev= 30
  4571.2  399.64  4574.1  399.05  4596.9  397.89  4652.6  395.62  4672.6  394.28
  4799.3  388.16  4847.2  385.16  4858.8  385.43  4864.3  384.73  4881.4  384.88
  4886.9  384.12    4904  384.41  4909.5  383.69  4926.6  383.68  4949.2  382.06
  4961.6  380.13  4971.8  379.64  4983.9   380.2  4999.7  378.95  5006.1  379.87
  5022.6  380.47  5050.8  382.06  5083.8  381.67  5118.6  383.73  5180.9  386.19
  5239.2  390.16    5328  394.62  5383.6  396.84  5412.5  398.62  5474.6  400.78
#Mann= 5 ,-1 , 0
  4571.2     .05       0  4596.9     .16       0  4672.6     .05       0
  4983.9    .035       0  5022.6     .05       0
Bank Sta=4983.9,5022.6
XS Rating Curve= 0 ,0
Exp/Cntr=0.3,0.1

Type RM Length L Ch R = 1 ,1807    ,50,50,50
XS GIS Cut Line= 4
       3525205.1    10438617.098     3524752.843     10438558.07
     3524600.934    10438510.327     3524335.309    10438482.549
#Sta/Elev= 30
       0 396.55749.07136395.4242 107.957392.9511117.7713392.3494147.2141391.3382
186.4712389.4342206.0997388.9455264.9853385.9087274.7996385.5758284.6139384.8326
314.0567383.6404363.1281381.0839372.9423379.7451382.7566378.8176392.5709378.6339
441.6422378.6109510.2389378.6787529.8331379.7116539.6301379.7893549.4272379.0443
569.0214375.0758578.8184377.4967588.6155379.3514598.4125380.0093658.0396382.0888
707.8696384.4263757.6995387.4284797.5635 390.381847.3935393.4737877.2914395.6373
#Mann= 3 ,-1 , 0
       0      .1       0372.9423     .05       0529.8331      .1       0
Bank Sta=372.9423,529.8331
XS Rating Curve= 0 ,0
Exp/Cntr=0.3,0.1

Type RM Length L Ch R = 1 ,1757    ,83,83,83
BEGIN DESCRIPTION:
Mapping XS c8ad91a0
END DESCRIPTION:
XS GIS Cut Line= 2
      3525288.41     10438578.39      3524330.08     10438449.91
#Sta/Elev= 30
  4463.1  397.19  4600.6  394.57  4610.7  393.44  4620.8  393.49  4691.4  391.22
  4721.7  389.31  4731.8  389.33  4777.2  387.34  4782.3  387.55  4792.3  386.55
  4834.3   384.7  4913.4  381.32  4928.2  381.67  4963.8  384.82  4994.1  385.77
  5024.4  384.96  5044.6  384.08  5054.6  383.15    5074  379.67  5079.1  379.52
  5084.9  377.07 5094.77  374.54  5104.8  373.49  5115.2  374.77  5125.3  378.87
  5135.4  379.87    5230  383.72  5296.8  387.68  5397.7  395.47    5430  397.11
#Mann= 4 ,-1 , 0
  4463.1     .12       0  4834.3      .1       0  4963.8     .05       0
  5024.4     .12       0
#XS Ineff= 2 , 0
       0 4958.41  384.53    5045       0  384.19
Permanent Ineff=
       T       T
Bank Sta=4963.8,5024.4
XS Rating Curve= 0 ,0
Exp/Cntr=0.3,0.1

Type RM Length L Ch R = 1 ,1674    ,332,332,332
XS GIS Cut Line= 4
     3525261.524    10438532.896     3524829.232    10438444.355
     3524565.343    10438363.626      3524352.67    10438353.209
#Sta/Elev= 30
       0395.673979.27061394.3353158.5412391.7904257.6295 387.787317.0824385.0862
356.7177383.6456416.1707380.6177426.0795379.6597445.8972376.3093 465.368 373.763
475.1034373.3122484.8388373.5195494.5742374.4158504.3096376.2901 514.045377.6713
523.7804377.7174543.2512376.8862 562.722375.3678572.4574373.7775582.1928372.8979
591.9282374.1825601.6636   376.3 611.399377.5639669.8115380.3702679.5469381.1754
737.8299384.3333776.5126387.3856805.5247388.7502873.2195393.4194931.2437398.3361
#Mann= 3 , 0 , 0
       0      .1       0445.8972     .05       0504.3096      .1       0
Bank Sta=445.8972,504.3096
XS Rating Curve= 0 ,0
Exp/Cntr=0.3,0.1

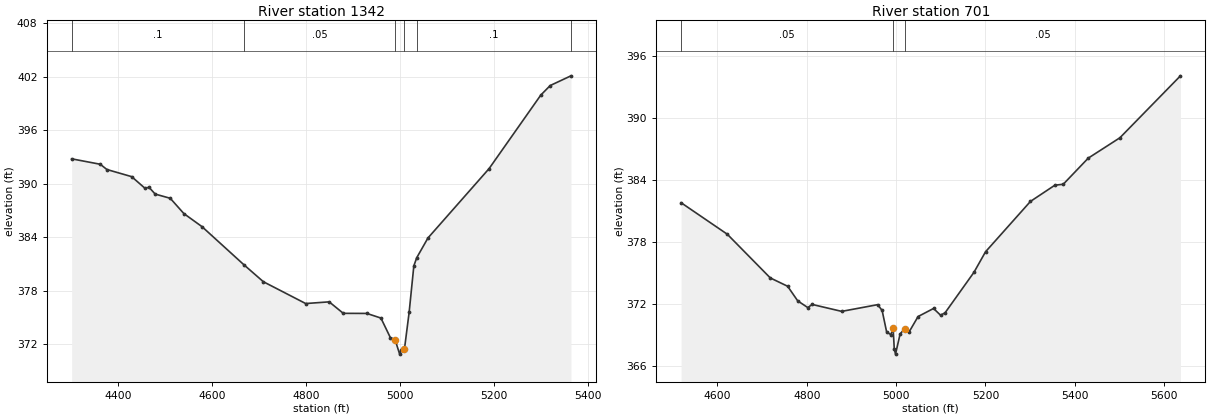
Type RM Length L Ch R = 1 ,1342    ,641,641,641
BEGIN DESCRIPTION:
MULBERRY CREEK TRIB 5 2.0
END DESCRIPTION:
XS GIS Cut Line= 3
      3525298.88     10438425.62      3524965.54     10438255.48
      3524278.03     10438248.53
#Sta/Elev= 30
  4301.5  392.79  4362.4  392.18  4376.5  391.59  4429.1  390.79  4456.9  389.51
  4466.3  389.58  4479.2  388.83  4511.2  388.36  4540.2  386.64  4578.6  385.18
  4667.5  380.91  4709.2  378.99  4799.2  376.54  4849.2  376.73  4879.2  375.44
  4929.2  375.43  4959.2  374.91  4979.2  372.72  4989.2   372.5    4999  370.86
  5002.2  371.36  5009.2  371.41  5019.2  375.55  5029.2  380.77  5035.4  381.69
  5059.2   383.9  5189.2  391.69  5299.2  399.95  5319.2  401.02  5363.3  402.11
#Mann= 6 ,-1 , 0
  4301.5      .1       0  4667.5     .05       0  4989.2    .035       0
  5009.2     .05       0  5035.4      .1       0  5363.3     .05       0
Bank Sta=4989.2,5009.2
XS Rating Curve= 0 ,0
Exp/Cntr=0.3,0.1

Type RM Length L Ch R = 1 ,701     ,0,0,0
BEGIN DESCRIPTION:
MULBERRY CREEK TRIB 5 1.0
END DESCRIPTION:
XS GIS Cut Line= 4
      3525241.94     10438040.91      3525116.93     10437785.68
      3524554.43     10437848.18      3524392.95     10438061.75
#Sta/Elev= 30
  4518.6  381.77    4622  378.72  4718.2  374.49  4757.1  373.68  4779.6  372.27
  4802.1  371.62  4812.1  371.92  4878.1  371.25  4958.6   371.9  4968.6  371.34
  4978.7  369.26  4988.2  368.99  4993.2  369.64  4995.8  367.61  4998.6  367.11
  5008.9  369.07  5018.9  369.56    5029  369.26  5049.1  370.75  5083.7  371.53
  5099.4  370.88  5109.5  371.11  5174.3  375.04  5200.1  377.02  5300.7   381.9
  5355.4  383.47  5374.1  383.56  5430.1  386.09  5500.9  388.06  5636.5  394.06
#Mann= 3 , 0 , 0
  4518.6     .05       0  4993.2    .035       0  5018.9     .05       0
Bank Sta=4993.2,5018.9
XS Rating Curve= 0 ,0
Exp/Cntr=0.3,0.1

Chan Stop Cuts=-1
Use User Specified Reach Order=0
Composite Channel Slope=5