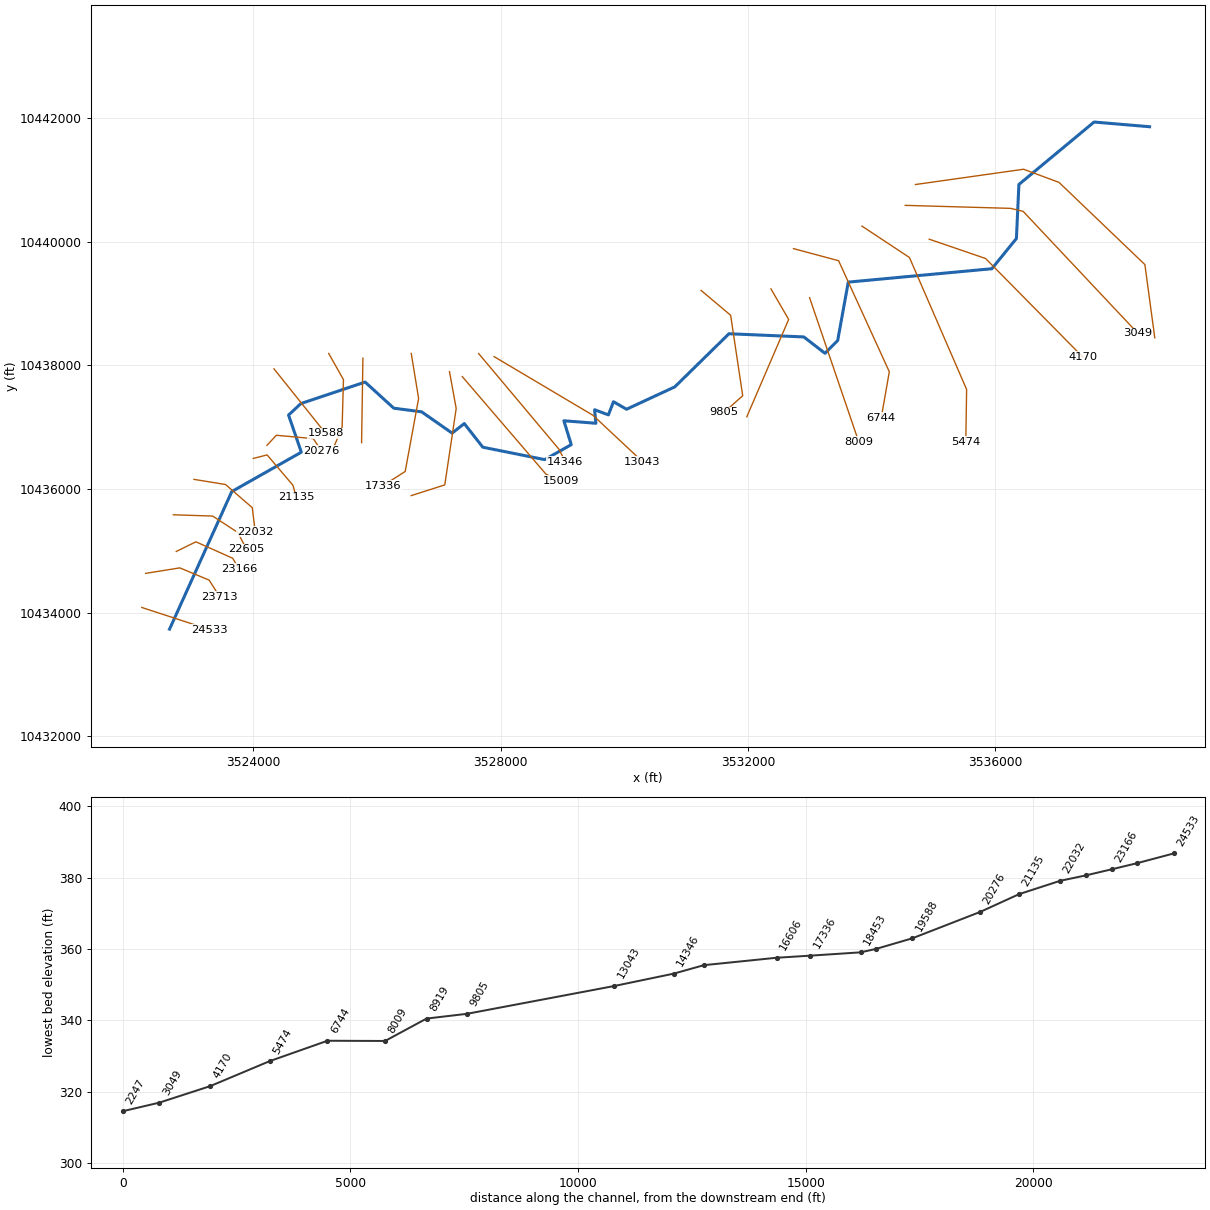
--- MULBERRY CREEK.prj (project) ---

Proj Title=MULBERRY CREEK Base Level Engineering
Current Plan=p01
Default Exp/Contr=0.3,0.1
English Units
Geom File=g01
Flow File=f01
Plan File=p01
Y Axis Title=Elevation
X Axis Title(PF)=Main Channel Distance
X Axis Title(XS)=Station
BEGIN DESCRIPTION:
MULBERRY CREEK
END DESCRIPTION:
DSS Export Rating Curves= 0
DSS Export Rating Curve Sorted= 0
DSS Export Volume Flow Curves= 0
DXF OffsetX= 0
DXF OffsetY= 0
DXF ScaleX= 1
DXF ScaleY= 10

--- MULBERRY CREEK.p01 (plan) ---

Plan Title=Multiple Run
Short Identifier=Multiple
Geom File=g01
Flow File=f01
Subcritical Flow
K Sum by GR= 0
Std Step Tol= 0.01
Critical Tol= 0.01
Num of Std Step Trials= 20
Max Error Tol= 0.3
Flow Tol Ratio= 0.001
Split Flow NTrial= 30
Split Flow Tol= 0.02
Split Flow Ratio= 0.02
Log Output Level= 0
Friction Slope Method= 1
Unsteady Friction Slope Method= 2
Unsteady Bridges Friction Slope Method= 1
Parabolic Critical Depth
Global Vel Dist=  1 , 1 , 1
Global Log Level= 0
CheckData=True
Encroach Param= -1, 0, 0, 0
BEGIN DESCRIPTION:
Multiple Run
END DESCRIPTION:

--- MULBERRY CREEK.f01 (steady flow) ---

Flow Title=Multiple
Number of Profiles=7
Profile Names=10-year,25-year,50-year,1pct_min,100-year,1pct_plu,500-year
River Rch & RM= MULBERRY CREEK,Reach-1,24533
     770    1050    1279    1139    1540    2083    2225
River Rch & RM= MULBERRY CREEK,Reach-1,18790
    1870    2661    3334    3040    4111    5560    6243
River Rch & RM= MULBERRY CREEK,Reach-1,15009
    2226    3184    4002    3659    4948    6692    7553
River Rch & RM= MULBERRY CREEK,Reach-1,9805
    2570    3698    4667    4281    5790    7830    8901
River Rch & RM= MULBERRY CREEK,Reach-1,8009
    3619    5275    6716    6209    8397   11356   13110
Boundary for River Rch & Prof#=MULBERRY CREEK,Reach-1,1
Up Type=0
Dn Type=3
Dn Slope=0.005
Boundary for River Rch & Prof#=MULBERRY CREEK,Reach-1,2
Up Type=0
Dn Type=3
Dn Slope=0.005
Boundary for River Rch & Prof#=MULBERRY CREEK,Reach-1,3
Up Type=0
Dn Type=3
Dn Slope=0.005
Boundary for River Rch & Prof#=MULBERRY CREEK,Reach-1,4
Up Type=0
Dn Type=3
Dn Slope=0.005
Boundary for River Rch & Prof#=MULBERRY CREEK,Reach-1,5
Up Type=0
Dn Type=3
Dn Slope=0.005
Boundary for River Rch & Prof#=MULBERRY CREEK,Reach-1,6
Up Type=0
Dn Type=3
Dn Slope=0.005
Boundary for River Rch & Prof#=MULBERRY CREEK,Reach-1,7
Up Type=0
Dn Type=3
Dn Slope=0.005

--- MULBERRY CREEK.g01 (geometry) ---

Geom Title=Existing Conditions
Program Version=4.10

River Reach=MULBERRY CREEK  ,Reach-1
Reach XY= 30
      3522643.67     10433731.22      3523650.24     10435957.74
      3524774.67     10436595.25      3524568.36     10437195.85
      3524767.14     10437381.67      3525806.15     10437729.86
      3526269.47     10437307.32      3526720.73     10437247.89
      3527213.19     10436903.79       3527409.8     10437058.25
       3527709.3     10436675.95      3528710.41     10436474.73
      3529140.02     10436717.17      3529020.66     10437103.46
      3529538.24     10437063.31      3529517.62     10437281.41
      3529741.15     10437198.95      3529822.53     10437411.62
      3530034.12     10437290.09      3530814.35     10437652.29
      3531690.01     10438511.66      3532900.55     10438460.12
      3533243.16     10438195.31      3533448.37     10438403.13
      3533619.29     10439347.18       3535941.3     10439563.92
      3536338.49     10440053.06      3536378.57     10440927.62
      3537594.17      10441937.7      3538492.11     10441861.64

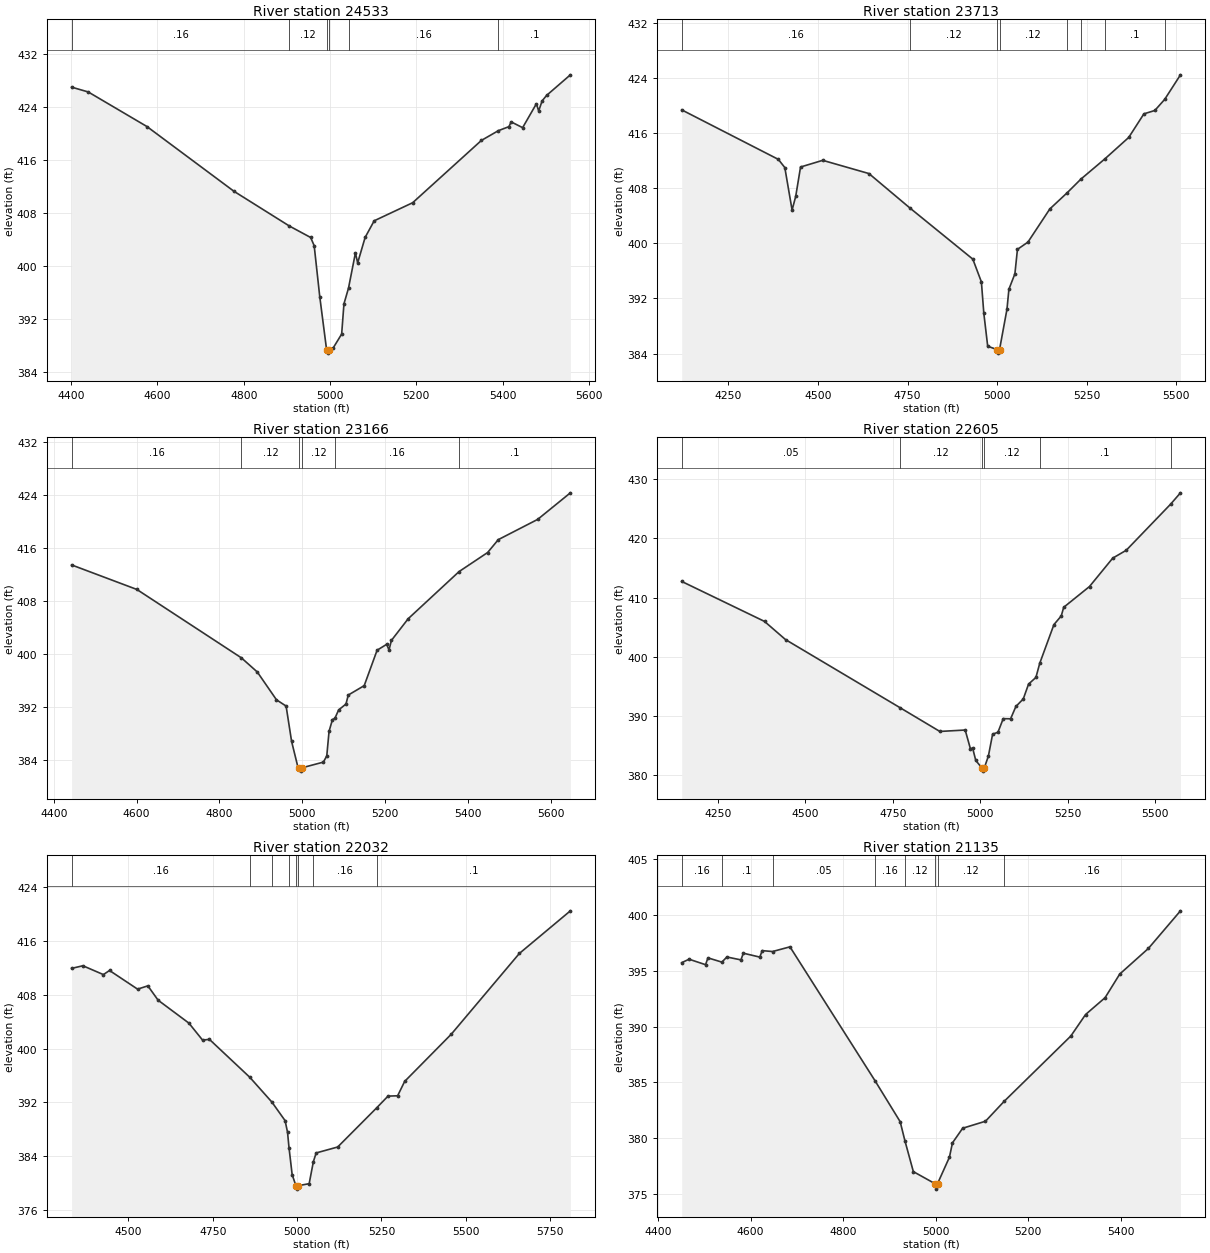
Type RM Length L Ch R = 1 ,24533   ,820,820,820
BEGIN DESCRIPTION:
MULBERRY CREEK 36.0
END DESCRIPTION:
XS GIS Cut Line= 2
      3522195.41     10434082.29      3523294.34     10433722.92
#Sta/Elev= 30
  4401.1  427.02  4439.7  426.29  4575.7  421.07  4777.4  411.29  4905.9  406.04
  4955.2  404.31  4963.4  403.07  4976.3  395.38  4992.2  387.34    4995  386.84
  4998.2  387.34  5007.8  387.66  5027.1  389.72  5032.4  394.28    5043  396.67
    5059  401.98  5064.2  400.47  5081.5  404.32  5102.5  406.83  5191.7  409.56
    5351  418.97  5390.2  420.44  5414.8  421.05    5420  421.77  5446.6   420.9
  5478.5  424.51  5483.8  423.42  5491.8  424.95  5502.3  425.78  5557.3  428.88
#Mann= 6 ,-1 , 0
  4401.1     .16       0  4905.9     .12       0  4992.2     .07       0
  4998.2     .12       0    5043     .16       0  5390.2      .1       0
Bank Sta=4992.2,4998.2
XS Rating Curve= 0 ,0
Exp/Cntr=0.3,0.1

Type RM Length L Ch R = 1 ,23713   ,547,547,547
BEGIN DESCRIPTION:
MULBERRY CREEK 35.0
END DESCRIPTION:
XS GIS Cut Line= 4
       3522257.9     10434634.39      3522809.96     10434722.93
      3523283.92     10434525.01      3523454.99     10434255.44
#Sta/Elev= 30
  4119.6  419.34  4389.3  412.16  4407.4  410.97  4427.7  404.81  4437.8  406.79
  4451.3  411.05  4513.2  412.02  4642.2   410.1  4757.1  405.08  4932.1  397.69
    4956  394.39  4962.8  389.83  4973.6  385.06  5000.6  384.56  5003.3  384.06
  5006.6  384.56  5027.4  390.43  5032.8  393.33  5049.5  395.56  5056.6  399.11
  5085.9  400.16    5147  404.97  5195.5  407.32  5233.8   409.3  5301.7  412.28
  5367.2  415.34  5409.5  418.76    5440  419.25  5467.4  420.85  5511.6  424.42
#Mann= 8 ,-1 , 0
  4119.6     .16       0  4757.1     .12       0  5000.6     .07       0
  5006.6     .12       0  5195.5      .1       0  5233.8     .12       0
  5301.7      .1       0  5467.4     .16       0
Bank Sta=5000.6,5006.6
XS Rating Curve= 0 ,0
Exp/Cntr=0.3,0.1

Type RM Length L Ch R = 1 ,23166   ,561,561,561
BEGIN DESCRIPTION:
MULBERRY CREEK 34.0
END DESCRIPTION:
XS GIS Cut Line= 4
      3522752.67     10434988.56      3523070.37      10435144.8
      3523664.12     10434879.18      3523767.68     10434708.31
#Sta/Elev= 30
  4443.2  413.47  4600.8  409.77  4853.1  399.46  4891.5  397.33  4937.9  393.13
  4961.1  392.19  4974.4  386.85  4989.8  382.94  4993.3  382.88  4996.1  382.38
  4999.3  382.88  5051.1  383.74  5059.3  384.67  5064.8  388.38    5073  390.15
  5078.8  390.33    5088  391.61  5105.7   392.5  5111.2  393.85  5149.7  395.27
  5180.8  400.61    5204   401.5  5209.5  400.64  5215.4  402.09  5255.9  405.36
  5378.8  412.47  5447.7  415.34  5473.4  417.28  5568.4  420.33  5647.5  424.34
#Mann= 6 ,-1 , 0
  4443.2     .16       0  4853.1     .12       0  4993.3     .07       0
  4999.3     .12       0  5078.8     .16       0  5378.8      .1       0
Bank Sta=4993.3,4999.3
XS Rating Curve= 0 ,0
Exp/Cntr=0.3,0.1

Type RM Length L Ch R = 1 ,22605   ,573,573,573
BEGIN DESCRIPTION:
MULBERRY CREEK 33.0
END DESCRIPTION:
XS GIS Cut Line= 4
      3522705.76      10435582.3      3523341.21     10435561.47
      3523747.46     10435295.84      3523887.19     10435026.73
#Sta/Elev= 30
  4147.2  412.72  4383.7  405.97  4443.7   402.9  4770.5  391.41  4884.4  387.39
  4956.8  387.63  4971.9  384.43  4977.9  384.62    4987  382.49  5005.1  381.19
  5007.8  380.69  5011.1  381.19    5023  383.22  5035.1  386.93  5050.3  387.25
  5065.4  389.55  5086.5  389.53  5101.6  391.61  5122.7  392.88  5137.8  395.39
  5158.8  396.51  5169.7   398.9  5210.2  405.43  5231.2   406.9  5238.1  408.35
  5311.8  411.86  5378.1  416.65  5416.7  417.98  5543.2  425.75  5571.6  427.68
#Mann= 6 ,-1 , 0
  4147.2     .05       0  4770.5     .12       0  5005.1     .07       0
  5011.1     .12       0  5169.7      .1       0  5543.2     .05       0
Bank Sta=5005.1,5011.1
XS Rating Curve= 0 ,0
Exp/Cntr=0.3,0.1

Type RM Length L Ch R = 1 ,22032   ,897,897,897
BEGIN DESCRIPTION:
MULBERRY CREEK 31.0
END DESCRIPTION:
XS GIS Cut Line= 4
      3523039.15     10436155.22      3523549.54     10436071.89
      3523981.83     10435696.89      3524028.71     10435311.46
#Sta/Elev= 30
    4332  411.89  4365.4  412.28  4426.2  410.97  4444.3  411.58  4527.5  408.81
  4557.9   409.3  4588.3  407.17  4679.5  403.77    4720  401.25  4740.3  401.36
  4859.8  395.74  4925.3  392.06  4964.5   389.3  4971.7  387.58  4976.1  385.28
  4985.4  381.29  4996.6  379.64  4999.4  379.14  5002.6  379.64  5035.8  379.95
  5048.3  383.23  5056.6  384.51  5120.3  385.39  5235.6  391.19  5269.4  392.94
  5297.9  392.99  5318.7  395.12  5456.9  402.13  5658.4   414.1  5809.7  420.43
#Mann= 8 ,-1 , 0
    4332     .16       0  4859.8     .12       0  4925.3     .16       0
  4976.1     .12       0  4996.6     .07       0  5002.6     .12       0
  5048.3     .16       0  5235.6      .1       0
Bank Sta=4996.6,5002.6
XS Rating Curve= 0 ,0
Exp/Cntr=0.3,0.1

Type RM Length L Ch R = 1 ,21135   ,859,859,859
BEGIN DESCRIPTION:
MULBERRY CREEK 29.0
END DESCRIPTION:
XS GIS Cut Line= 4
      3523997.44     10436493.76      3524221.42     10436551.05
      3524638.08     10436061.47      3524694.93      10435865.1
#Sta/Elev= 30
  4451.1  395.73  4467.1  396.04  4502.7  395.55  4507.9  396.16    4538  395.78
  4548.8  396.24  4579.2  395.98  4584.4  396.58    4620  396.23  4625.2  396.81
  4647.5  396.73  4685.2  397.15    4869  385.15  4923.5  381.47  4933.7  379.77
    4952  376.99  4998.4  375.92  5001.2  375.42  5004.4  375.92    5030  378.28
  5036.6  379.57  5058.6  380.88    5108  381.51  5148.5   383.3  5292.5  389.15
  5324.4  391.08  5366.6  392.59  5398.3  394.71  5460.3  397.01  5529.6  400.38
#Mann= 8 ,-1 , 0
  4451.1     .16       0    4538      .1       0  4647.5     .05       0
    4869     .16       0  4933.7     .12       0  4998.4     .07       0
  5004.4     .12       0  5148.5     .16       0
Bank Sta=4998.4,5004.4
XS Rating Curve= 0 ,0
Exp/Cntr=0.3,0.1

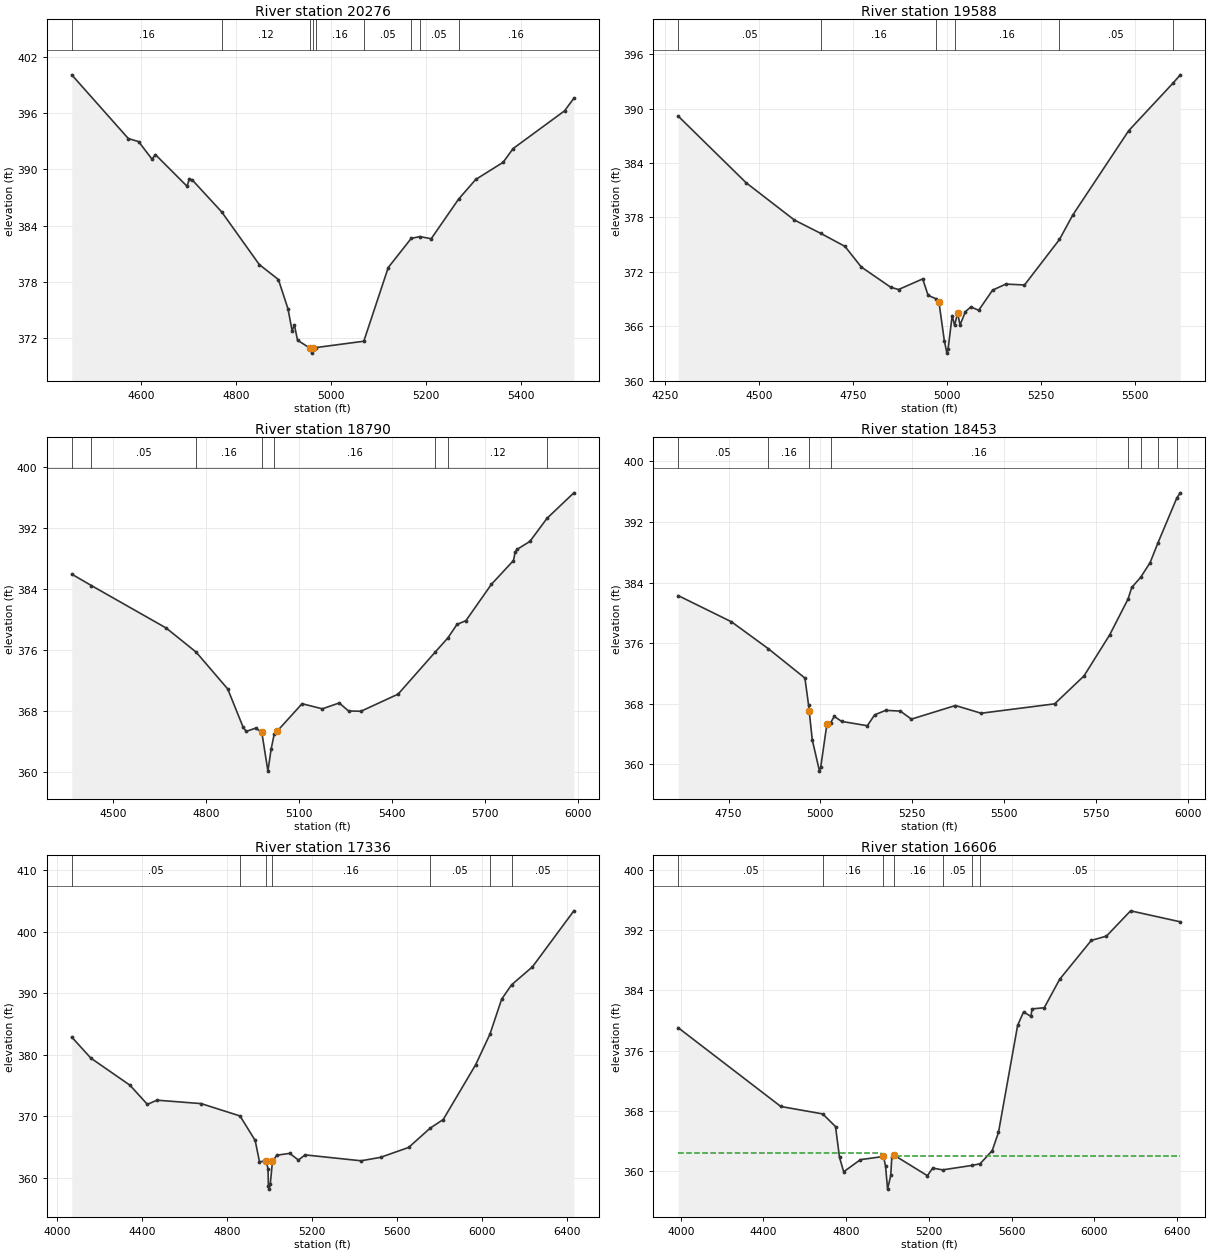
Type RM Length L Ch R = 1 ,20276   ,1486,1486,1486
BEGIN DESCRIPTION:
MULBERRY CREEK 27.0
END DESCRIPTION:
XS GIS Cut Line= 4
      3524219.28     10436706.03      3524371.16     10436868.76
      3524967.94     10436814.51      3525097.61     10436620.01
#Sta/Elev= 30
  4454.6  400.09  4573.6  393.29  4595.1  392.97  4623.4  391.09  4630.3  391.59
  4696.9  388.21  4701.9  388.99  4708.3  388.86  4769.8  385.47  4848.8  379.86
    4889  378.26  4909.1  375.15  4917.8  372.82  4922.8  373.39  4929.2  371.79
  4956.3  370.91    4959  370.41  4962.3  370.91    4969  371.01  5068.6  371.68
    5120  379.54  5168.2  382.64  5186.3  382.84  5210.3  382.61  5267.8  386.83
  5303.9  388.93  5361.5  390.76  5382.6  392.23  5490.7  396.25  5510.2  397.59
#Mann= 9 ,-1 , 0
  4454.6     .16       0  4769.8     .12       0  4956.3     .07       0
  4962.3     .12       0    4969     .16       0  5068.6     .05       0
  5168.2     .16       0  5186.3     .05       0  5267.8     .16       0
Bank Sta=4956.3,4962.3
XS Rating Curve= 0 ,0
Exp/Cntr=0.3,0.1

Type RM Length L Ch R = 1 ,19588   ,798,798,798
BEGIN DESCRIPTION:
MULBERRY CREEK 27.1
END DESCRIPTION:
XS GIS Cut Line= 2
      3524332.06     10437944.64       3525165.4     10436902.96
#Sta/Elev= 30
  4285.9  389.18  4466.3  381.83  4594.4  377.72  4664.8  376.24  4728.9  374.81
  4772.1  372.54  4850.5   370.3  4871.3  370.05  4935.4  371.22  4949.8  369.41
  4970.6  369.03  4978.6  368.67    4993  364.37  4999.8  363.03    5003  363.53
  5013.8  367.18  5020.2  366.08  5028.2  367.48  5034.6  366.14    5049  367.61
  5063.4  368.13  5084.2  367.76  5121.1  369.98  5156.3  370.65  5205.9  370.55
  5298.8  375.57    5334  378.26  5482.8  387.58  5599.9   392.8  5619.9  393.74
#Mann= 6 ,-1 , 0
  4285.9     .05       0  4664.8     .16       0  4970.6     .12       0
  5020.2     .16       0  5298.8     .05       0  5599.9     .16       0
Bank Sta=4978.6,5028.2
XS Rating Curve= 0 ,0
Exp/Cntr=0.3,0.1

Type RM Length L Ch R = 1 ,18790   ,337,337,337
BEGIN DESCRIPTION:
MULBERRY CREEK 26.0
END DESCRIPTION:
XS GIS Cut Line= 4
      3525217.51     10438192.54      3525456.22     10437769.37
      3525434.52     10436998.97      3525293.47     10436662.61
#Sta/Elev= 30
  4366.3  385.94  4429.8  384.44  4671.2  378.86    4768  375.69  4869.9  370.85
  4919.9   365.8  4929.9  365.27  4959.9   365.7  4979.9  365.17  4999.7  360.05
  5009.9  362.91    5020  364.92    5030  365.32    5110  368.91  5175.5  368.24
    5230  369.01    5260  367.96  5300.1  367.92  5420.1  370.17  5540.2  375.71
  5580.8  377.56  5610.2  379.33  5639.1  379.83  5721.3   384.6  5792.6  387.73
    5798  388.81  5804.3   389.2  5845.6  390.24  5901.2  393.29  5987.6  396.63
#Mann= 8 ,-1 , 0
  4366.3     .16       0  4429.8     .05       0    4768     .16       0
  4979.9     .12       0    5020     .16       0  5540.2     .05       0
  5580.8     .12       0  5901.2     .16       0
Bank Sta=4979.9,5030
XS Rating Curve= 0 ,0
Exp/Cntr=0.3,0.1

Type RM Length L Ch R = 1 ,18453   ,1117,1117,1117
BEGIN DESCRIPTION:
MULBERRY CREEK 25.0
END DESCRIPTION:
XS GIS Cut Line= 2
      3525770.89     10438116.58      3525749.19     10436749.35
#Sta/Elev= 30
    4613  382.28    4758  378.82    4858  375.28    4958  371.39    4968  367.81
  4969.7  367.03    4978  363.24  4997.7  359.09    5001  359.59    5018  365.34
    5028  365.49    5038  366.32    5058  365.66    5128  365.09    5148  366.53
    5178  367.12    5218  367.02    5248  365.96    5368  367.76    5438  366.74
  5638.1  367.98  5718.1  371.67  5788.1   377.1  5838.1  381.83  5848.1  383.36
  5872.5   384.7  5898.1  386.64    5919  389.19  5970.8  395.18  5980.4  395.86
#Mann= 8 ,-1 , 0
    4613     .05       0    4858     .16       0    4968     .12       0
    5028     .16       0  5838.1     .16       0  5872.5     .05       0
    5919     .16       0  5970.8      .1       0
Bank Sta=4969.7,5018
XS Rating Curve= 0 ,0
Exp/Cntr=0.3,0.1

Type RM Length L Ch R = 1 ,17336   ,730,730,730
BEGIN DESCRIPTION:
MULBERRY CREEK 23.0
END DESCRIPTION:
XS GIS Cut Line= 4
      3526552.14     10438192.56       3526671.5     10437465.55
      3526454.49     10436282.82      3526098.05       10436056.
#Sta/Elev= 30
  4070.1  382.89  4159.8  379.46  4343.6  375.06  4425.7  371.94  4471.2  372.62
  4679.1  372.06  4861.6  370.05  4932.8  366.07  4953.1   362.6  4983.7  362.74
  4993.1   361.5  4995.2  358.65  4997.9  358.15    5004  359.05  5014.2  362.65
  5034.5  363.67  5095.5  363.97  5136.2  362.88  5167.7  363.72    5431  362.76
  5522.5  363.32  5654.7  364.93  5756.3  368.08  5817.3  369.47  5969.8  378.38
    6037  383.35  6092.3  389.06  6138.7  391.38  6237.3  394.32  6431.8  403.42
#Mann= 7 ,-1 , 0
  4070.1     .05       0  4861.6     .16       0  4983.7     .12       0
  5014.2     .16       0  5756.3     .05       0    6037     .16       0
  6138.7     .05       0
Bank Sta=4983.7,5014.2
XS Rating Curve= 0 ,0
Exp/Cntr=0.3,0.1

Type RM Length L Ch R = 1 ,16606   ,1597,1597,1597
BEGIN DESCRIPTION:
MULBERRY CREEK 21.0
END DESCRIPTION:
XS GIS Cut Line= 4
      3527170.64     10437899.57      3527279.14     10437302.79
      3527094.68     10436065.81      3526552.11     10435892.19
#Sta/Elev= 30
  3987.9  379.03  4483.8  368.56  4686.5  367.57  4748.1  365.89  4767.5  361.78
  4787.7  359.88  4868.6  361.49  4979.8  361.91  4989.9  360.67  4999.8  357.57
  5015.1  359.39  5020.3  361.83  5030.4   362.1  5192.2  359.36    5218  360.37
  5265.6  360.13  5409.9  360.73  5447.2  360.95  5505.6  362.69  5535.9  365.12
  5628.6  379.37  5657.2  381.13  5692.9  380.54  5697.9  381.54  5757.1  381.69
  5831.4  385.47  5984.3  390.64  6057.8  391.22  6174.5  394.58  6414.8  393.12
#Mann= 7 ,-1 , 0
  3987.9     .05       0  4686.5     .16       0  4979.8     .12       0
  5030.4     .16       0  5265.6     .05       0  5409.9     .16       0
  5447.2     .05       0
#XS Ineff= 2 , 0
       0 4967.77  362.32 5041.06       0  361.96
Permanent Ineff=
       T       T
Bank Sta=4979.8,5030.4
XS Rating Curve= 0 ,0
Exp/Cntr=0.3,0.1

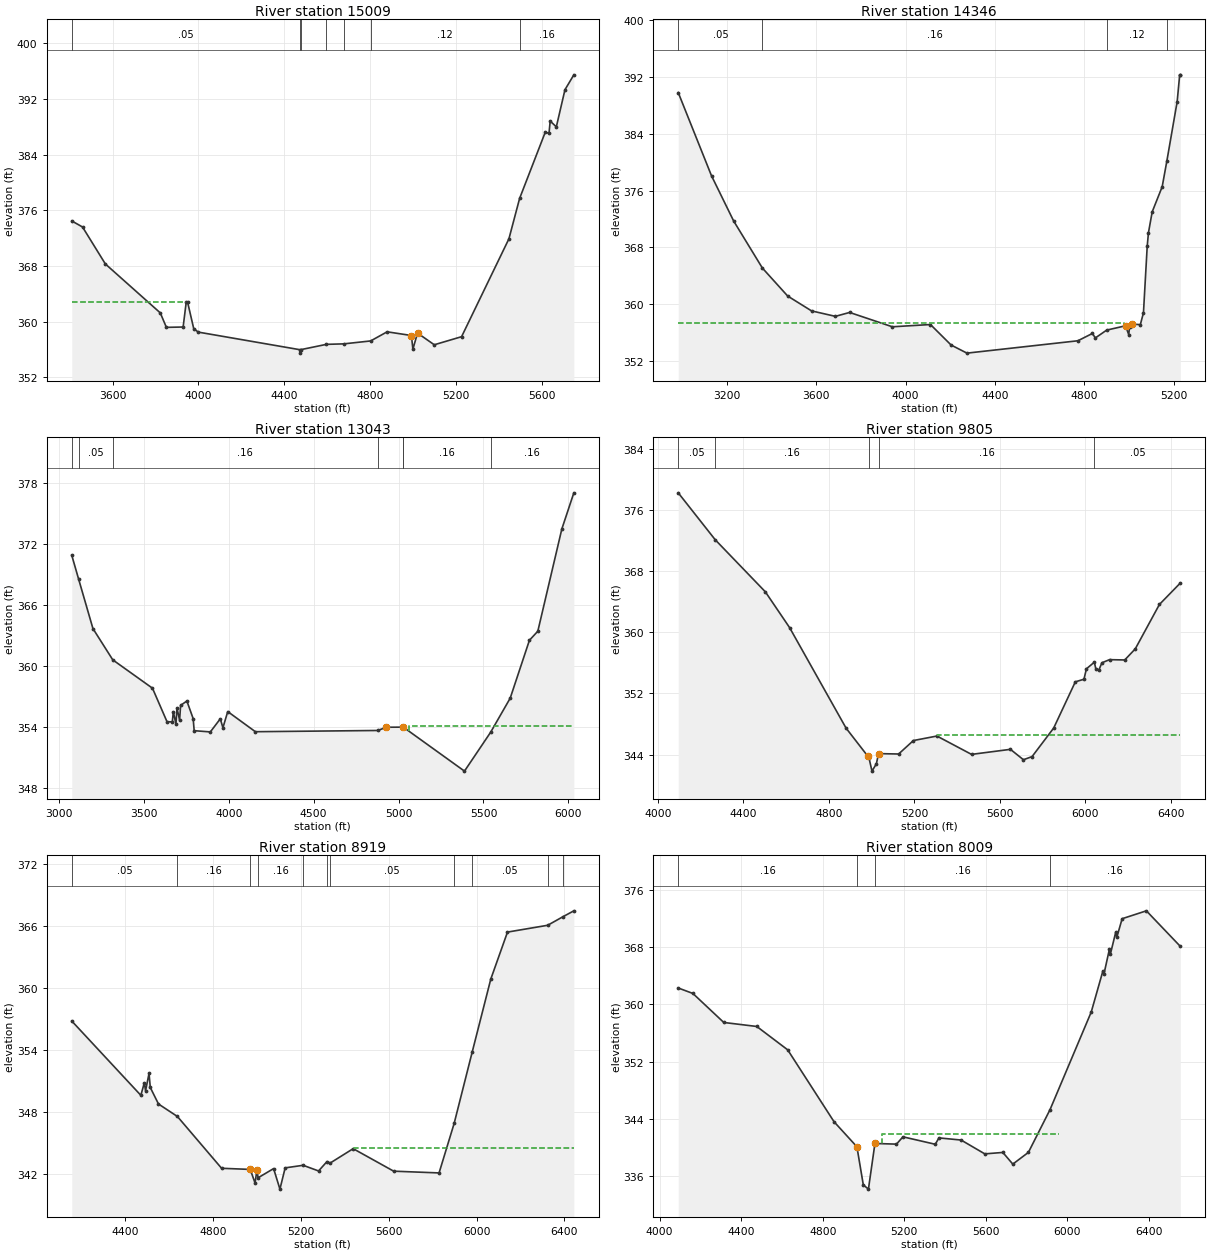
Type RM Length L Ch R = 1 ,15009   ,663,663,663
BEGIN DESCRIPTION:
MULBERRY CREEK 19.0
END DESCRIPTION:
XS GIS Cut Line= 3
      3527377.62     10437818.31       3528731.8     10436238.45
      3528966.19     10436129.93
#Sta/Elev= 30
    3410  374.47  3460.1   373.6  3566.6  368.29  3822.3  361.27  3850.8  359.19
  3928.8  359.24    3943  362.76  3949.6  362.81  3978.1  359.02    3999  358.51
  4471.2  355.99    4474  355.49  4477.2  355.99  4596.5  356.75  4677.4  356.82
  4802.5  357.24  4879.2  358.55  4992.3  358.02  4999.3  356.06  5020.8  358.37
  5098.8  356.69  5226.1  357.85  5446.7  371.91  5496.4   377.7    5616  387.22
  5633.4  387.05  5638.9  388.81  5667.5  387.98  5707.7  393.31  5749.1  395.45
#Mann= 7 ,-1 , 0
    3410     .05       0  4471.2     .07       0  4477.2     .05       0
  4596.5      .1       0  4677.4     .16       0  4802.5     .12       0
  5496.4     .16       0
#XS Ineff= 2 , 0
       0 3944.23  362.82               0
Permanent Ineff=
       T       F
Bank Sta=4992.3,5020.8
XS Rating Curve= 0 ,0
Exp/Cntr=0.3,0.1

Type RM Length L Ch R = 1 ,14346   ,1303,1303,1303
BEGIN DESCRIPTION:
MULBERRY CREEK 18.0
END DESCRIPTION:
XS GIS Cut Line= 3
       3527642.1     10438191.65      3528942.11     10436641.64
       3529042.1     10436441.65
#Sta/Elev= 30
  2982.5  389.81  3131.5  378.08  3230.5  371.72  3359.1  365.09  3472.3  361.15
    3579  359.06  3685.7  358.29  3749.4  358.84  3940.7  356.82  4111.1  357.14
  4203.5  354.25  4274.4  353.11  4770.7  354.85  4835.7  355.88  4848.9  355.25
  4899.5  356.35    4984  356.96  4998.3  355.72  5002.2  356.85  5013.9   357.2
  5050.2  357.12  5064.2  358.79    5081  368.17  5086.6  370.08  5103.3  373.01
    5148  376.55  5168.8  380.15  5215.1  388.55  5226.3  392.31  5229.1  392.31
#Mann= 4 ,-1 , 0
  2982.5     .05       0  3359.1     .16       0  4899.5     .12       0
  5168.8     .16       0
#XS Ineff= 2 , 0
       0 4977.46   357.4               0
Permanent Ineff=
       T       F
Bank Sta=4984,5013.9
XS Rating Curve= 0 ,0
Exp/Cntr=0.3,0.1

Type RM Length L Ch R = 1 ,13043   ,3238,3238,3238
BEGIN DESCRIPTION:
MULBERRY CREEK 17.0
END DESCRIPTION:
XS GIS Cut Line= 3
      3527892.14     10438141.62      3529492.11     10437191.64
      3530292.09     10436441.66
#Sta/Elev= 30
  3075.2  370.89  3115.5  368.55  3199.9  363.68  3316.8   360.6  3550.6  357.81
  3636.3  354.51  3667.5   354.5  3673.3   355.5  3688.9  354.28  3694.8  355.87
  3710.4  354.66  3716.2  356.12  3753.2  356.55  3790.2  354.82  3796.2  353.63
  3891.5  353.51    3950   354.8  3965.6  353.92  3993.9  355.51  4156.6  353.53
  4877.8  353.65  4928.1  353.97    5028  353.98  5388.3  349.65  5542.5  353.48
  5657.6  356.83  5770.9  362.53  5820.3  363.42  5961.9  373.49  6032.5  377.04
#Mann= 7 ,-1 , 0
  3075.2     .16       0  3115.5     .05       0  3316.8     .16       0
  4877.8     .12       0    5028     .07       0    5028     .16       0
  5542.5     .16       0
#XS Ineff= 2 , 0
       0                 5060.23       0  354.11
Permanent Ineff=
       F       T
Bank Sta=4928.1,5028
XS Rating Curve= 0 ,0
Exp/Cntr=0.3,0.1

Type RM Length L Ch R = 1 ,9805    ,886,886,886
BEGIN DESCRIPTION:
MULBERRY CREEK 16.0
END DESCRIPTION:
XS GIS Cut Line= 4
      3531239.68     10439212.48      3531717.08     10438811.04
      3531912.39     10437508.95      3531608.57     10437237.68
#Sta/Elev= 30
  4095.8  378.24  4268.8   372.1  4503.2  365.29  4616.3  360.62  4880.7  347.46
  4981.8  343.81  4988.2  343.51  5001.8  341.84  5022.3   342.8  5032.4  344.13
  5126.3  344.08  5195.4  345.84  5305.4  346.43  5467.2  344.03  5649.2  344.69
  5709.9  343.33  5750.3  343.74  5851.5  347.48  5952.6  353.52    5993  353.86
  6004.4  355.22  6041.5  356.09    6049  355.15  6063.2  355.09  6076.8  356.01
  6112.5  356.42  6183.6  356.38  6232.9  357.83  6345.8  363.64  6443.5  366.44
#Mann= 5 ,-1 , 0
  4095.8     .05       0  4268.8     .16       0  4988.2     .12       0
  5032.4     .16       0  6041.5     .05       0
#XS Ineff= 2 , 0
       0                  5305.4       0  346.56
Permanent Ineff=
       F       T
Bank Sta=4981.8,5032.4
XS Rating Curve= 0 ,0
Exp/Cntr=0.3,0.1

Type RM Length L Ch R = 1 ,8919    ,910,910,910
BEGIN DESCRIPTION:
MULBERRY CREEK 15.0
END DESCRIPTION:
XS GIS Cut Line= 3
        3532369.     10439238.02      3532655.47     10438743.22
      3531978.38     10437167.69
#Sta/Elev= 30
    4156   356.8  4470.6   349.6  4486.3   350.8  4492.1  350.05  4507.9  351.72
  4513.6  350.36  4550.9  348.76  4637.1  347.55  4838.3  342.53  4968.9  342.42
  4990.7   341.1  4999.2  342.34  5004.6  341.61  5075.2   342.5    5104  340.51
  5127.8  342.57  5209.7  342.82    5280  342.27  5318.3  343.18    5333  343.04
  5437.6  344.43    5622  342.25  5828.8  342.08  5897.5  346.88  5980.1  353.83
  6064.4  360.87  6140.4  365.42  6323.5  366.08  6393.1  366.91  6442.6  367.48
#Mann= 11 ,-1 , 0
    4156     .05       0  4637.1     .16       0  4968.9     .12       0
  5004.6     .16       0  5209.7     .05       0  5318.3      .1       0
    5333     .05       0  5897.5      .1       0  5980.1     .05       0
  6323.5     .16       0  6393.1     .05       0
#XS Ineff= 2 , 0
       0                 5440.34       0  344.54
Permanent Ineff=
       F       T
Bank Sta=4968.9,4999.2
XS Rating Curve= 0 ,0
Exp/Cntr=0.3,0.1

Type RM Length L Ch R = 1 ,8009    ,1265,1265,1265
BEGIN DESCRIPTION:
MULBERRY CREEK 13.0
END DESCRIPTION:
XS GIS Cut Line= 2
      3532993.99     10439094.82      3533788.28     10436764.04
#Sta/Elev= 30
  4091.5   362.3  4163.3  361.54  4314.8  357.49  4476.8  356.93  4628.3  353.67
  4855.5  343.64  4967.8  340.14  4999.2  334.82  5024.3  334.23  5056.2   340.6
  5161.9  340.51  5193.6  341.53  5352.1  340.49  5370.1  341.38  5478.8  341.08
    5595  339.15  5683.5  339.35  5732.4  337.72  5808.9  339.36  5914.9  345.32
  6117.1  358.95  6174.5   364.7  6179.8  364.29  6205.9  367.68  6211.2  367.06
  6237.2  370.09  6242.5  369.37  6268.6  371.97  6387.4  373.07  6553.9  368.11
#Mann= 4 ,-1 , 0
  4091.5     .16       0  4967.8     .12       0  5056.2     .16       0
  5914.9     .16       0
#XS Ineff= 1 ,-1
 5090.91 5958.52  341.89
Permanent Ineff=
       T
Bank Sta=4967.8,5056.2
XS Rating Curve= 0 ,0
Exp/Cntr=0.3,0.1

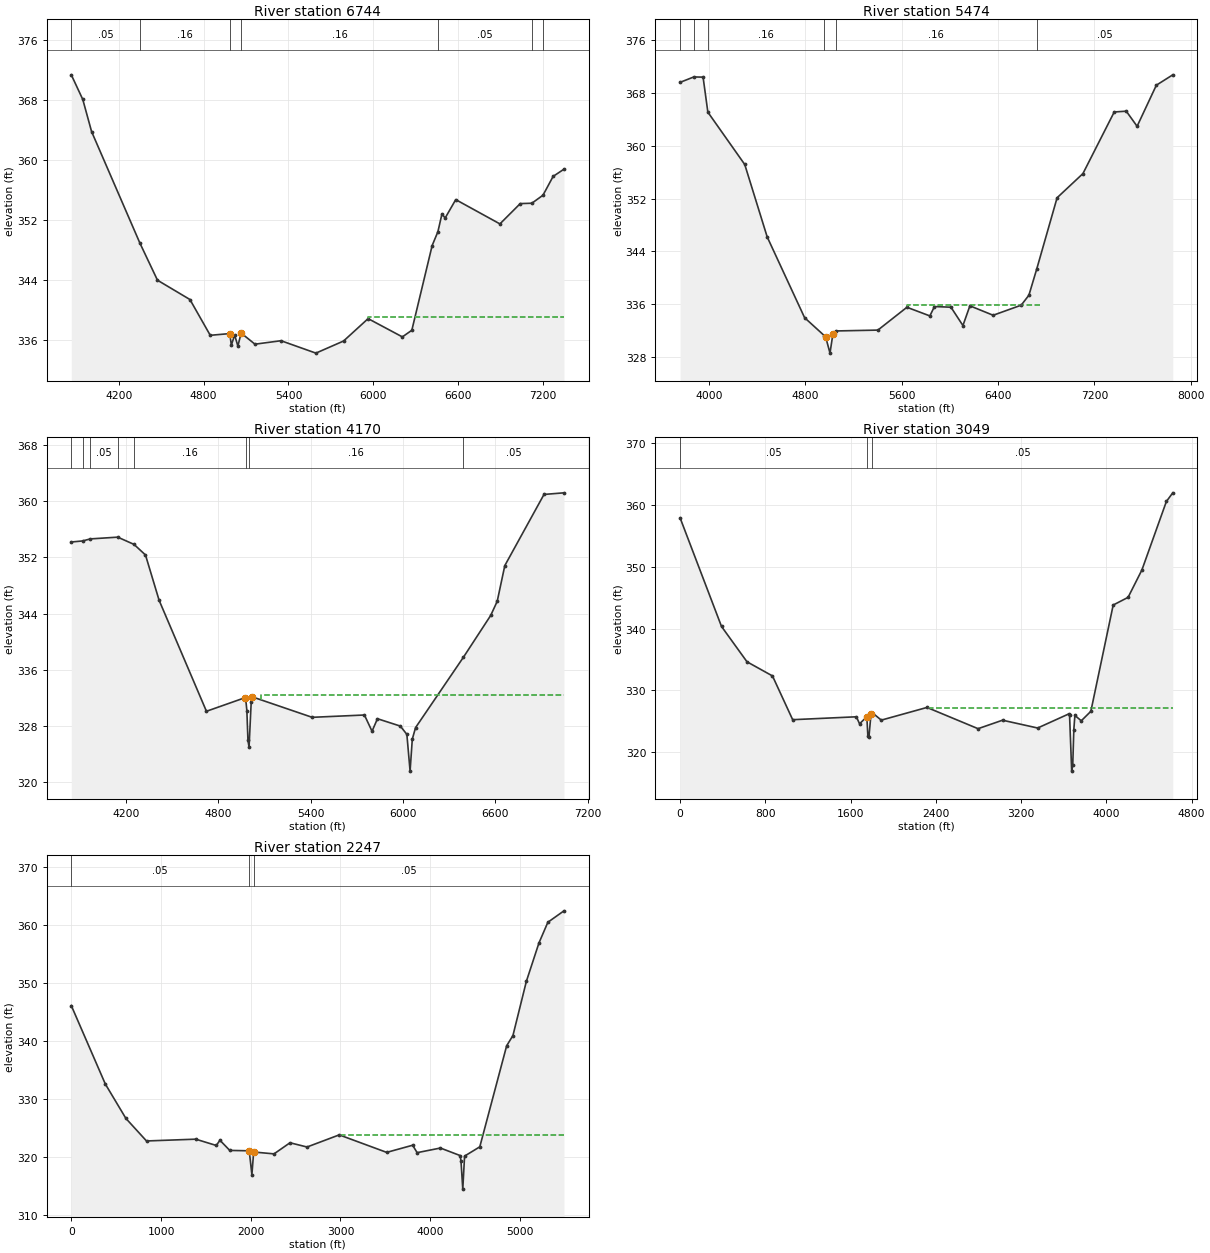
Type RM Length L Ch R = 1 ,6744    ,1270,1270,1270
BEGIN DESCRIPTION:
MULBERRY CREEK 12.0
END DESCRIPTION:
XS GIS Cut Line= 4
      3532733.64     10439889.04      3533462.76     10439693.74
      3534283.07     10437896.86      3534153.04     10437155.67
#Sta/Elev= 30
  3864.8  371.31    3946  368.03  4008.2  363.76  4349.8  348.92    4474  343.99
  4703.4  341.42    4847  336.66  4984.7  336.89  4996.2  335.35  5019.3   336.7
  5042.3  335.23  5065.3  336.96    5163  335.48  5347.2  335.94  5593.8  334.29
  5789.3   335.9    5963  338.88  6204.9  336.45  6271.9  337.33  6415.6   348.6
  6456.2  350.44  6484.7  352.79  6507.7  352.27  6582.3  354.71  6894.6  351.48
  7038.2  354.18  7120.4  354.23  7199.2   355.3  7270.7   357.8  7347.4  358.76
#Mann= 7 ,-1 , 0
  3864.8     .05       0  4349.8     .16       0  4984.7     .12       0
  5065.3     .16       0  6456.2     .05       0  7120.4     .16       0
  7199.2     .05       0
#XS Ineff= 2 , 0
       0                 5963.64       0  339.07
Permanent Ineff=
       F       T
Bank Sta=4984.7,5065.3
XS Rating Curve= 0 ,0
Exp/Cntr=0.3,0.1

Type RM Length L Ch R = 1 ,5474    ,1304,1304,1304
BEGIN DESCRIPTION:
MULBERRY CREEK 10.0
END DESCRIPTION:
XS GIS Cut Line= 4
      3533840.35     10440253.64      3534608.59     10439745.82
      3535533.07     10437610.41      3535520.07     10436765.36
#Sta/Elev= 30
  3758.2  369.61  3872.3  370.43  3949.2   370.4  3988.9  365.09  4295.3  357.16
  4481.8  346.18  4792.6  333.94  4956.9  331.21    4967  331.05  5003.6  328.57
  5027.3  331.45  5050.8  331.93  5401.4  332.06  5642.6  335.52  5833.2  334.21
  5871.4  335.63  6008.5  335.53  6107.9  332.75  6165.8  335.74  6359.1  334.31
  6592.2  335.84    6656  337.35  6721.4  341.34  6890.3  352.12  7104.8  355.78
  7364.9  365.12  7464.9  365.24  7554.9  362.95  7714.9  369.18  7851.2  370.75
#Mann= 6 ,-1 , 0
  3758.2     .05       0  3872.3      .1       0  3988.9     .16       0
  4956.9     .12       0  5050.8     .16       0  6721.4     .05       0
#XS Ineff= 1 ,-1
 5642.94 6746.09  335.85
Permanent Ineff=
       T
Bank Sta=4967,5027.3
XS Rating Curve= 0 ,0
Exp/Cntr=0.3,0.1

Type RM Length L Ch R = 1 ,4170    ,1121,1121,1121
BEGIN DESCRIPTION:
Mapping XS f771d645
END DESCRIPTION:
XS GIS Cut Line= 3
      3534927.99     10440041.88      3535839.47     10439729.37
      3537410.55     10438136.59
#Sta/Elev= 30
  3845.8  354.19  3919.6  354.34  3969.2  354.63  4147.3  354.88  4253.2  353.85
  4327.8  352.34  4416.3  345.89  4723.8  330.09  4972.3  332.01  4979.3  331.78
  4986.4  330.17  4993.5  325.95  5000.6  324.98  5014.7  331.45  5021.7  332.14
  5410.6  329.23  5750.1  329.56  5799.6  327.25  5834.9  329.03  5983.5  327.98
  6025.9   326.8  6046.8  321.57  6061.2  326.13  6082.5  327.77  6393.5  337.79
  6570.4  343.73  6612.8  345.74  6662.2  350.83  6916.8  360.96  7046.6  361.19
#Mann= 8 ,-1 , 0
  3845.8     .05       0  3919.6      .1       0  3969.2     .05       0
  4147.3      .1       0  4253.2     .16       0  4979.3     .12       0
  5000.6     .16       0  6393.5     .05       0
#XS Ineff= 2 , 0
       0                 5077.27       0  332.45
Permanent Ineff=
       F       T
Bank Sta=4972.3,5021.7
XS Rating Curve= 0 ,0
Exp/Cntr=0.3,0.1

Type RM Length L Ch R = 1 ,3049    ,802,802,802
XS GIS Cut Line= 4
     3534540.972    10440589.245     3536245.833    10440540.634
     3536447.222    10440492.023     3538304.861    10438516.328
#Sta/Elev= 30
       0357.9439388.6136340.3557627.7604334.6332866.9073332.34141056.232325.2541
1654.099 325.7251683.992324.58651752.348325.74341762.033322.54811771.719322.4189
1791.089326.13251800.775326.41511887.943325.1837 2316.63327.2382 2795.83323.7978
3025.447325.17213354.897323.90743644.414 326.1693654.397325.97363674.364316.9228
3684.347317.93963694.331323.63653704.314325.94733764.214325.07413854.064326.6096
4063.714343.82674203.481345.07144333.264349.51184562.881 360.6034622.781362.0026
#Mann= 3 ,-1 , 0
       0     .05       01752.348    .035       01800.775     .05       0
#XS Ineff= 2 , 0
       0                 2322.48       0  327.22
Permanent Ineff=
       F       T
Bank Sta=1752.348,1791.089
XS Rating Curve= 0 ,0
Exp/Cntr=0.3,0.1

Type RM Length L Ch R = 1 ,2247    ,0,0,0
XS GIS Cut Line= 5
     3534705.035     10440926.34     3536454.167    10441173.736
     3537027.083    10440961.062     3538415.972    10439630.912
     3538575.694    10438446.305
#Sta/Elev= 30
       0346.0827379.1651332.5981608.6599 326.677838.1545322.80251386.946323.1115
1616.441322.02551656.353322.93211766.111321.17731983.179321.11082012.779316.9884
2032.513320.90462259.447320.5823 2437.71322.49332627.275321.76232986.451323.8502
3515.237320.83853804.572322.07023854.458320.78964113.862321.5882 4333.37320.2958
4343.351319.38334363.313314.51914383.276 320.1994552.955321.79644852.389339.1771
4922.257340.93365071.974350.25715211.709356.83475311.521360.41625491.181362.3849
#Mann= 3 , 0 , 0
       0     .05       01983.179    .035       02032.513     .05       0
#XS Ineff= 2 , 0
       0                 2989.77       0  323.89
Permanent Ineff=
       F       T
Bank Sta=1983.179,2032.513
XS Rating Curve= 0 ,0
Exp/Cntr=0.3,0.1

Chan Stop Cuts=-1
Use User Specified Reach Order=0
Composite Channel Slope=5