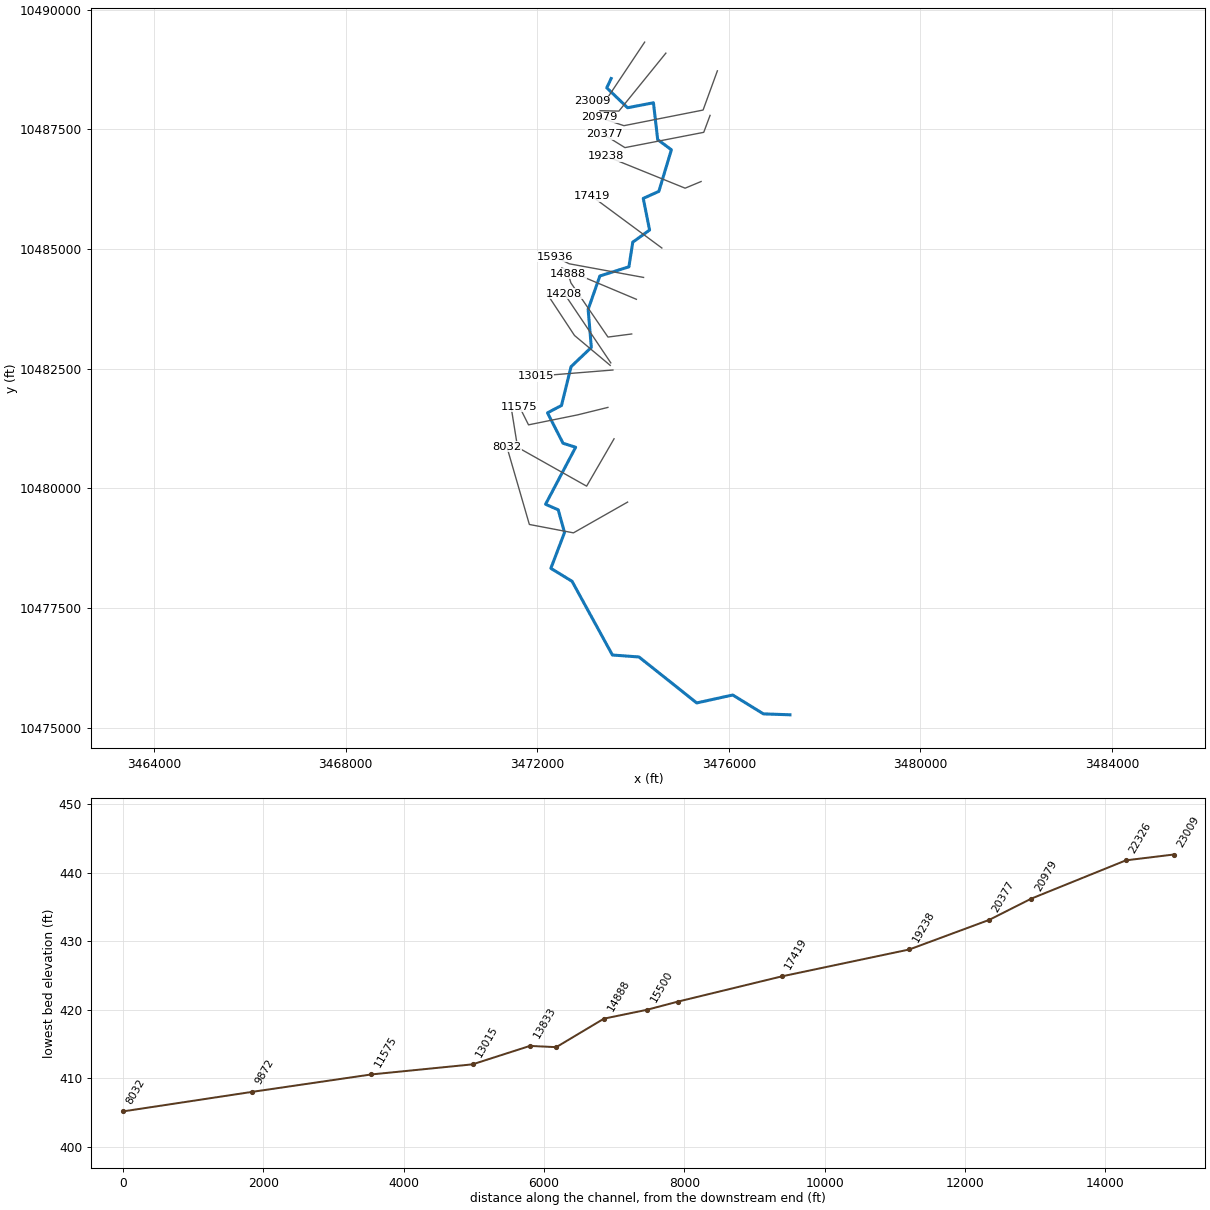
--- NANCE BRANCH.prj (project) ---

Proj Title=NANCE BRANCH Base Level Engineering
Current Plan=p01
Default Exp/Contr=0.3,0.1
English Units
Geom File=g01
Flow File=f01
Plan File=p01
BEGIN DESCRIPTION:
NANCE BRANCH
END DESCRIPTION:

--- NANCE BRANCH.p01 (plan) ---

Plan Title=Multiple Run
Short Identifier=Multiple
Geom File=g01
Flow File=f01
Subcritical Flow
K Sum by GR= 0
Std Step Tol= 0.01
Critical Tol= 0.01
Num of Std Step Trials= 20
Max Error Tol= 0.3
Flow Tol Ratio= 0.001
Split Flow NTrial= 30
Split Flow Tol= 0.02
Split Flow Ratio= 0.02
Log Output Level= 0
Friction Slope Method= 1
Unsteady Friction Slope Method= 2
Unsteady Bridges Friction Slope Method= 1
Parabolic Critical Depth
Global Vel Dist=  1 , 1 , 1
Global Log Level= 0
CheckData=True
Encroach Param= -1, 0, 0, 0
BEGIN DESCRIPTION:
Multiple Run
END DESCRIPTION:

--- NANCE BRANCH.f01 (steady flow) ---

Flow Title=Multiple
Number of Profiles=7
Profile Names=10-year,25-year,50-year,1pct_min,100-year,1pct_plu,500-year
River Rch & RM= NANCE BRANCH,Reach-1,23009
    1099    1510    1846    1645    2225    3009    3224
River Rch & RM= NANCE BRANCH,Reach-1,19238
    1383    1911    2347    2096    2834    3833    4129
Boundary for River Rch & Prof#=NANCE BRANCH,Reach-1,1
Up Type=0
Dn Type=3
Dn Slope=0.005
Boundary for River Rch & Prof#=NANCE BRANCH,Reach-1,2
Up Type=0
Dn Type=3
Dn Slope=0.005
Boundary for River Rch & Prof#=NANCE BRANCH,Reach-1,3
Up Type=0
Dn Type=3
Dn Slope=0.005
Boundary for River Rch & Prof#=NANCE BRANCH,Reach-1,4
Up Type=0
Dn Type=3
Dn Slope=0.005
Boundary for River Rch & Prof#=NANCE BRANCH,Reach-1,5
Up Type=0
Dn Type=3
Dn Slope=0.005
Boundary for River Rch & Prof#=NANCE BRANCH,Reach-1,6
Up Type=0
Dn Type=3
Dn Slope=0.005
Boundary for River Rch & Prof#=NANCE BRANCH,Reach-1,7
Up Type=0
Dn Type=3
Dn Slope=0.005

--- NANCE BRANCH.g01 (geometry) ---

Geom Title=Existing Conditions

River Reach=NANCE BRANCH,Reach-1
Reach XY= 30
      3473543.22     10488559.32      3473451.55     10488365.89
      3473885.95     10487949.50      3474426.50     10488053.15
      3474515.28     10487283.87      3474801.20     10487071.61
      3474539.65     10486202.65      3474213.58     10486055.63
      3474345.95     10485394.44      3473994.54     10485140.64
      3473914.34     10484626.77      3473307.32     10484434.55
      3473062.66     10483736.23      3473128.97     10482942.85
      3472705.74     10482540.09      3472506.26     10481729.43
      3472213.84     10481576.16      3472538.34     10480940.43
      3472801.60     10480856.94      3472173.77     10479665.79
      3472437.69     10479549.98      3472569.48     10479075.99
      3472284.25     10478327.57      3472726.91     10478056.57
      3473569.48     10476516.72      3474124.78     10476476.11
      3475330.39     10475515.82      3476083.05     10475681.64
      3476723.07     10475287.06      3477277.35     10475267.90

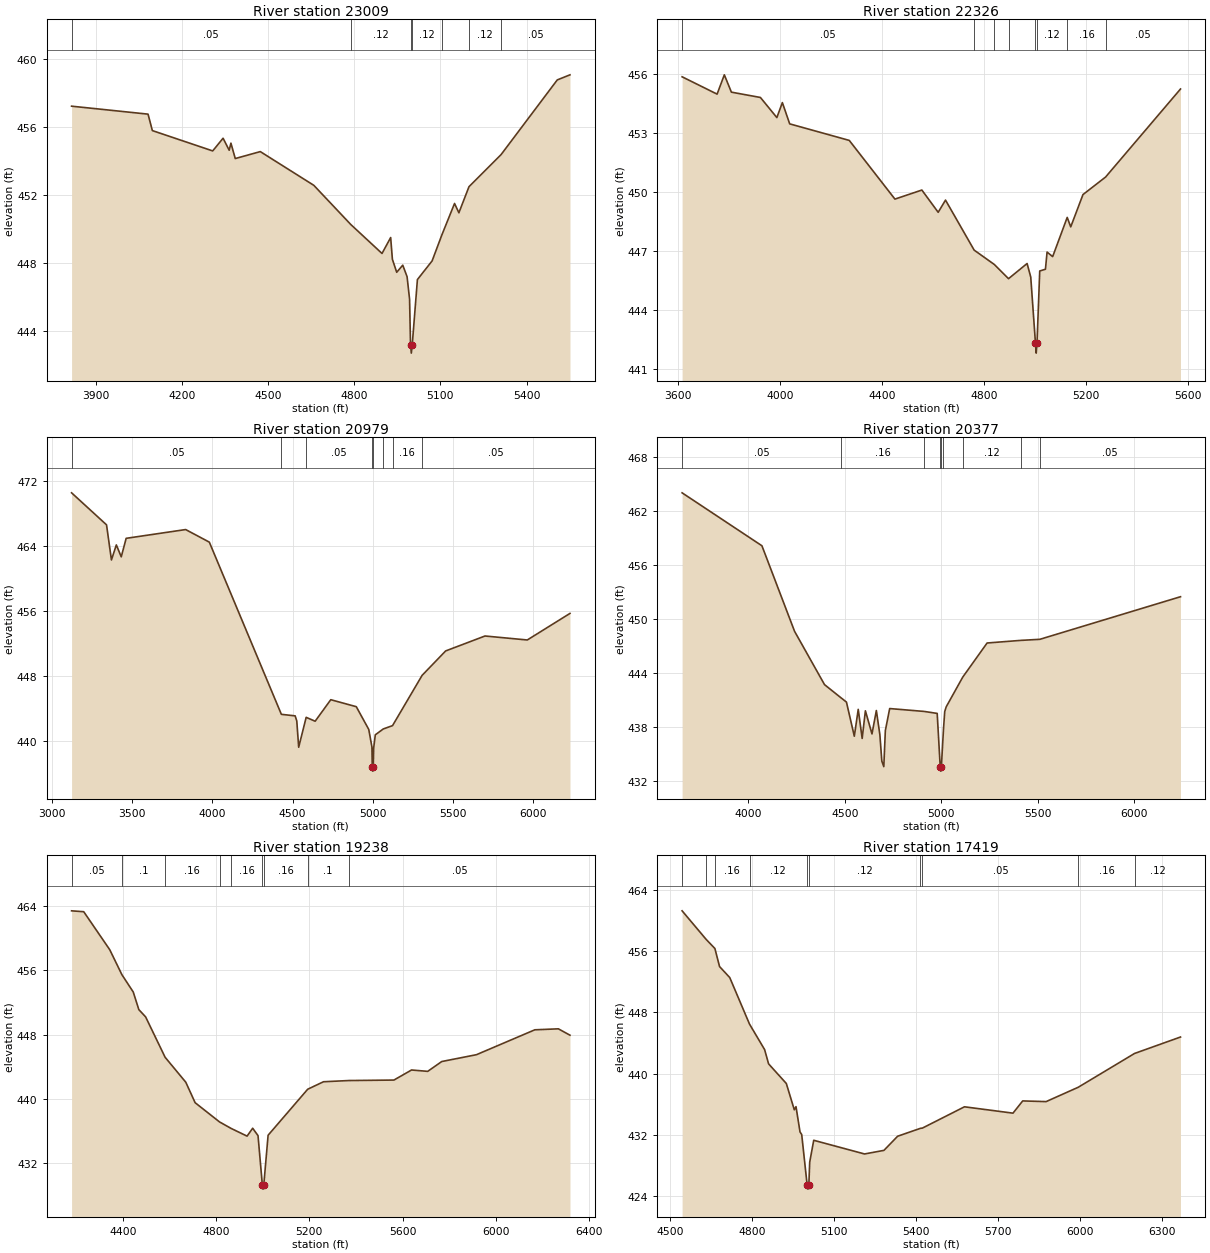
Type RM Length L Ch R = 1,23009,683,683,683
BEGIN DESCRIPTION:
NANCE BRANCH 28.0
END DESCRIPTION:
XS GIS Cut Line= 3
      3474243.20     10489320.30      3473435.89     10488109.33
      3473158.11     10488083.29
#Sta/Elev= 30
  3816.5  457.24  4082.6  456.77  4097.6  455.80  4307.6  454.60  4343.7  455.35
  4365.0  454.64  4371.0  455.06  4386.1  454.15  4473.2  454.56  4659.5  452.57
  4788.1  450.26  4896.8  448.55  4926.9  449.49  4932.9  448.21  4947.9  447.44
  4969.0  447.86  4984.0  447.18  4992.7  445.85  4996.0  443.17  4998.8  442.67
  5002.0  443.17  5020.0  447.01  5071.1  448.11  5105.0  449.64  5149.2  451.50
  5164.3  450.95  5199.5  452.49  5311.0  454.38  5506.7  458.79  5550.9  459.09
#Mann=7,-1,0
  3816.5    0.05       0  4788.1    0.12       0  4996.0    0.07       0
  5002.0    0.12       0  5105.0    0.16       0  5199.5    0.12       0
  5311.0    0.05       0
Bank Sta=4996,5002
Exp/Cntr=0.3,0.1

Type RM Length L Ch R = 1,22326,1347,1347,1347
BEGIN DESCRIPTION:
NANCE BRANCH 27.0
END DESCRIPTION:
XS GIS Cut Line= 3
      3474685.88     10489090.22      3473704.98     10487879.30
      3473310.04     10487887.98
#Sta/Elev= 30
  3616.3  455.85  3753.5  454.97  3781.8  455.95  3809.5  455.07  3923.3  454.80
  3987.7  453.78  4009.3  454.54  4038.0  453.46  4271.5  452.62  4450.5  449.64
  4556.0  450.10  4620.0  448.97  4648.7  449.59  4761.0  447.05  4840.1  446.32
  4895.7  445.60  4968.5  446.37  4982.8  445.68  5001.3  442.32  5004.1  441.82
  5007.3  442.32  5018.0  445.99  5040.4  446.08  5046.8  446.95  5068.7  446.72
  5125.7  448.71  5139.5  448.23  5187.5  449.87  5276.1  450.76  5569.7  455.23
#Mann=8,-1,0
  3616.3    0.05       0  4761.0    0.16       0  4840.1    0.05       0
  4895.7    0.12       0  5001.3    0.07       0  5007.3    0.12       0
  5125.7    0.16       0  5276.1    0.05       0
Bank Sta=5001.3,5007.3
Exp/Cntr=0.3,0.1

Type RM Length L Ch R = 1,20979,602,602,602
BEGIN DESCRIPTION:
NANCE BRANCH 26.0
END DESCRIPTION:
XS GIS Cut Line= 4
      3475761.94     10488720.58      3475463.34     10487901.17
      3473810.56     10487574.78      3473289.74     10487748.39
#Sta/Elev= 30
  3122.2  470.49  3340.0  466.55  3370.6  462.23  3401.1  464.08  3431.7  462.61
  3462.3  464.89  3833.1  465.97  3980.6  464.42  4429.5  443.23  4515.4  443.04
  4525.6  442.41  4537.4  439.18  4584.1  442.86  4640.0  442.38  4737.4  445.03
  4896.4  444.17  4974.1  441.37  4993.9  439.21  4996.0  436.74  4998.8  436.24
  5002.0  436.74  5004.7  439.09  5014.9  440.71  5064.7  441.43  5122.3  441.84
  5306.7  448.03  5453.2  451.03  5698.5  452.87  5962.0  452.38  6228.0  455.65
#Mann=8,-1,0
  3122.2    0.05       0  4429.5    0.16       0  4584.1    0.05       0
  4996.0   0.035       0  5002.0    0.05       0  5064.7    0.12       0
  5122.3    0.16       0  5306.7    0.05       0
Bank Sta=4996,5002
Exp/Cntr=0.3,0.1

Type RM Length L Ch R = 1,20377,1139,1139,1139
BEGIN DESCRIPTION:
NANCE BRANCH 25.0
END DESCRIPTION:
XS GIS Cut Line= 6
      3475609.16     10487790.03      3475477.23     10487435.90
      3473831.39     10487116.45      3473393.89     10487387.28
      3473393.89     10487394.23      3473393.89     10487401.18
#Sta/Elev= 30
  3657.4  464.04  4071.1  458.16  4240.2  448.66  4395.4  442.74  4480.6  441.28
  4509.1  440.80  4549.9  437.01  4570.2  439.99  4590.6  436.76  4607.3  439.83
  4641.5  437.26  4664.1  439.86  4682.3  437.18  4692.5  434.24  4702.7  433.63
  4710.7  437.63  4733.2  440.08  4911.9  439.76  4979.4  439.54  4995.1  433.63
  4997.8  433.13  5001.1  433.63  5011.9  437.75  5018.4  439.74  5026.1  440.27
  5111.8  443.57  5238.0  447.36  5411.6  447.65  5511.5  447.77  6240.3  452.50
#Mann=9,-1,0
  3657.4    0.05       0  4480.6    0.16       0  4911.9    0.12       0
  4995.1    0.07       0  5001.1    0.12       0  5011.9    0.16       0
  5111.8    0.12       0  5411.6    0.16       0  5511.5    0.05       0
Bank Sta=4995.1,5001.1
Exp/Cntr=0.3,0.1

Type RM Length L Ch R = 1,19238,1819,1819,1819
BEGIN DESCRIPTION:
NANCE BRANCH 23.0
END DESCRIPTION:
XS GIS Cut Line= 3
      3475421.71     10486408.13      3475088.34     10486269.23
      3473442.49     10486935.90
#Sta/Elev= 30
  4180.5  463.36  4232.6  463.25  4344.2  458.53  4396.1  455.44  4444.9  453.28
  4468.8  451.10  4498.0  450.19  4581.5  445.18  4670.2  442.08  4710.2  439.54
  4815.0  437.15  4864.3  436.35  4932.9  435.39  4957.0  436.37  4979.9  435.45
  4998.5  429.31  5001.3  428.81  5004.5  429.31  5023.1  435.50  5192.8  441.21
  5260.5  442.14  5369.0  442.29  5562.6  442.35  5638.1  443.60  5707.5  443.43
  5767.6  444.65  5916.5  445.50  6166.8  448.59  6267.7  448.71  6317.4  447.92
#Mann=9,-1,0
  4180.5    0.05       0  4396.1     0.1       0  4581.5    0.16       0
  4815.0    0.12       0  4864.3    0.16       0  4998.5    0.07       0
  5004.5    0.16       0  5192.8     0.1       0  5369.0    0.05       0
Bank Sta=4998.5,5004.5
Exp/Cntr=0.3,0.1

Type RM Length L Ch R = 1,17419,1483,1483,1483
BEGIN DESCRIPTION:
NANCE BRANCH 21.0
END DESCRIPTION:
XS GIS Cut Line= 2
      3474602.21     10485019.24      3473137.06     10486102.48
#Sta/Elev= 30
  4543.7  461.29  4631.7  457.55  4663.6  456.36  4680.6  454.00  4717.9  452.56
  4790.3  446.46  4845.3  443.14  4859.9  441.27  4924.7  438.70  4953.9  435.26
  4960.1  435.67  4974.8  432.36  4981.0  432.02  5001.0  425.38  5003.7  424.88
  5007.0  425.38  5010.2  428.40  5024.9  431.27  5210.7  429.48  5281.6  429.95
  5331.7  431.80  5414.8  432.83  5422.5  432.87  5576.0  435.65  5753.4  434.82
  5788.9  436.42  5874.5  436.33  5992.1  438.21  6197.9  442.63  6365.8  444.78
#Mann=10,-1,0
  4543.7     0.1       0  4631.7    0.05       0  4663.6    0.16       0
  4790.3    0.12       0  5001.0    0.07       0  5007.0    0.12       0
  5414.8     0.1       0  5422.5    0.05       0  5992.1    0.16       0
  6197.9    0.12       0
Bank Sta=5001,5007
Exp/Cntr=0.3,0.1

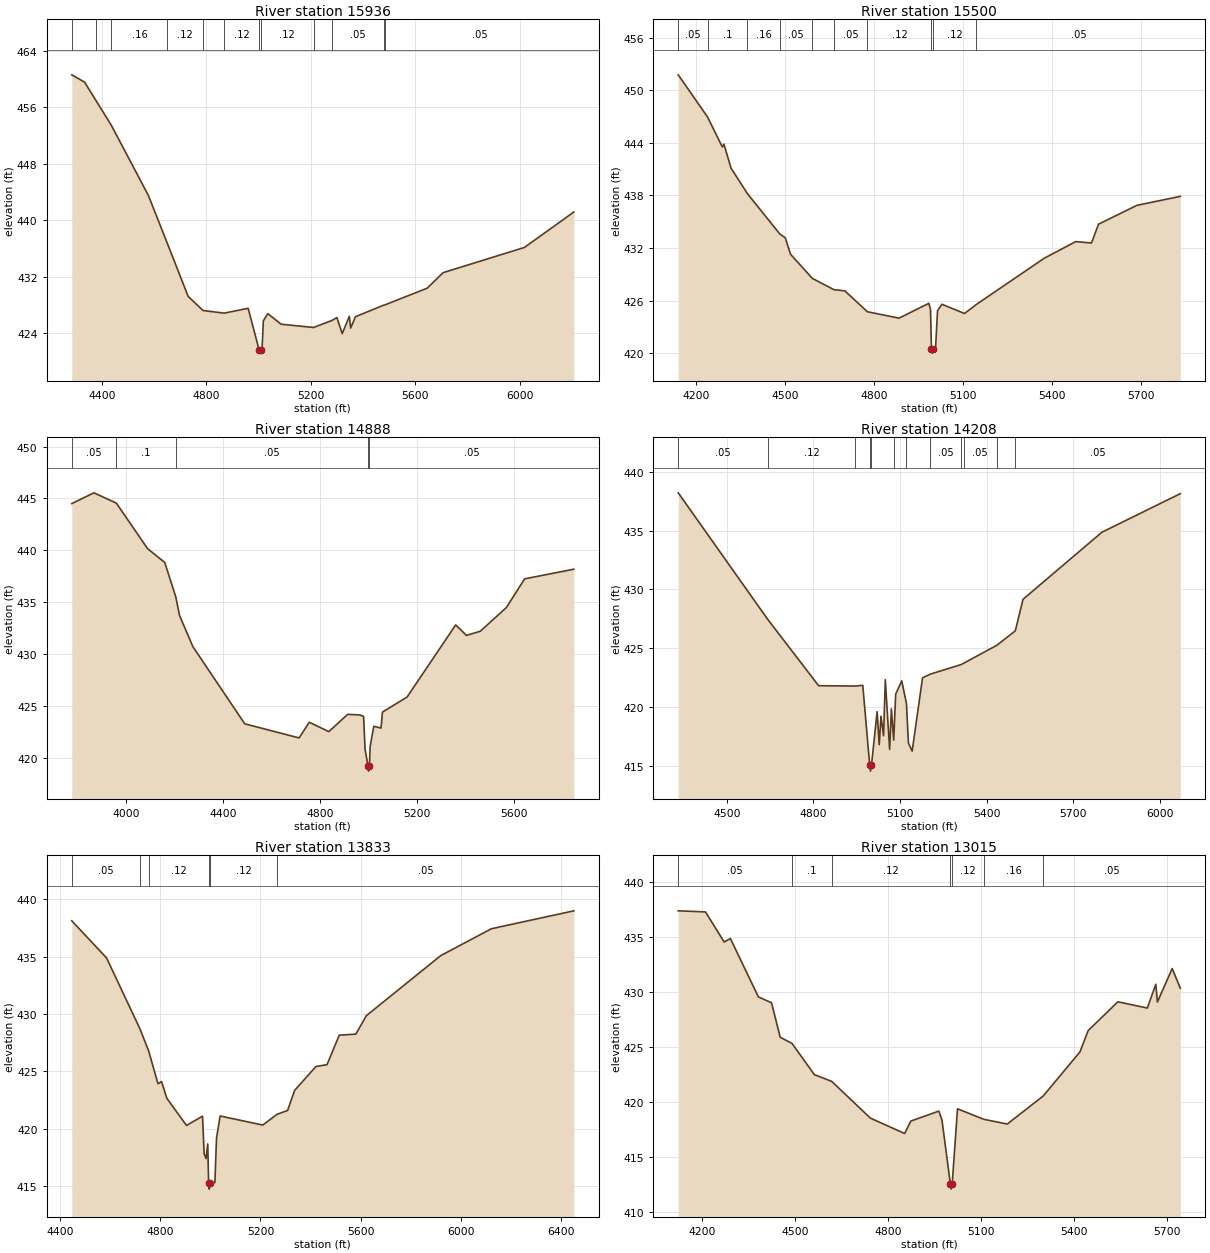
Type RM Length L Ch R = 1,15936,436,436,436
BEGIN DESCRIPTION:
NANCE BRANCH 18.0
END DESCRIPTION:
XS GIS Cut Line= 4
      3474220.33     10484404.64      3472668.20     10484689.37
      3472366.12     10484838.67      3472373.02     10484838.67
#Sta/Elev= 30
  4285.2  460.57  4334.2  459.54  4378.1  456.92  4436.5  453.44  4578.4  443.51
  4651.6  436.67  4730.7  429.22  4787.7  427.22  4868.6  426.85  4960.4  427.53
  5002.2  421.69  5005.0  421.19  5008.2  421.69  5013.6  421.77  5018.6  425.76
  5035.7  426.78  5086.6  425.28  5210.6  424.82  5281.1  425.81  5300.1  426.22
  5320.4  423.95  5347.6  426.39  5352.7  424.74  5371.2  426.34  5478.5  427.97
  5483.4  428.01  5645.8  430.38  5706.8  432.58  6017.8  436.14  6207.1  441.16
#Mann=12,-1,0
  4285.2    0.16       0  4378.1     0.1       0  4436.5    0.16       0
  4651.6    0.12       0  4787.7     0.1       0  4868.6    0.12       0
  5002.2    0.07       0  5008.2    0.12       0  5210.6    0.16       0
  5281.1    0.05       0  5478.5    0.16       0  5483.4    0.05       0
Bank Sta=5002.2,5008.2
Exp/Cntr=0.3,0.1

Type RM Length L Ch R = 1,15500,612,612,612
BEGIN DESCRIPTION:
Mapping XS 075b0b33
END DESCRIPTION:
XS GIS Cut Line= 2
      3474070.66     10483947.67      3472512.57     10484603.02
#Sta/Elev= 30
  4140.7  451.75  4239.4  446.94  4289.2  443.52  4294.6  443.84  4318.4  441.11
  4373.8  438.19  4482.9  433.59  4500.9  433.17  4518.8  431.29  4592.0  428.54
  4664.7  427.25  4701.7  427.11  4777.5  424.73  4884.1  424.00  4984.5  425.69
  4990.0  425.00  4993.2  420.51  4995.9  420.01  4999.2  420.51  5007.0  420.62
  5013.7  424.85  5028.7  425.58  5104.6  424.53  5144.7  425.57  5373.3  430.84
  5479.1  432.73  5532.0  432.57  5555.8  434.72  5685.3  436.87  5831.0  437.89
#Mann=10,-1,0
  4140.7    0.05       0  4239.4     0.1       0  4373.8    0.16       0
  4482.9    0.05       0  4592.0    0.12       0  4664.7    0.05       0
  4777.5    0.12       0  4993.2    0.07       0  4999.2    0.12       0
  5144.7    0.05       0
Bank Sta=4993.2,4999.2
Exp/Cntr=0.3,0.1

Type RM Length L Ch R = 1,14888,680,680,680
BEGIN DESCRIPTION:
NANCE BRANCH 15.0
END DESCRIPTION:
XS GIS Cut Line= 4
      3473972.63     10483223.50      3473476.69     10483158.81
      3472703.10     10484290.90      3472643.78     10484482.33
#Sta/Elev= 30
  3776.4  444.50  3867.7  445.54  3960.3  444.55  4089.6  440.15  4160.1  438.83
  4206.0  435.48  4220.9  433.73  4276.3  430.71  4490.2  423.28  4714.4  421.92
  4756.4  423.43  4837.0  422.53  4914.9  424.19  4965.7  424.13  4980.6  423.99
  4986.6  420.85  4998.6  419.22  5001.3  418.72  5004.6  419.22  5007.6  421.09
  5022.5  423.04  5052.4  422.87  5058.4  424.41  5160.0  425.86  5360.5  432.81
  5405.2  431.80  5462.1  432.20  5569.8  434.49  5645.1  437.25  5848.1  438.18
#Mann=5,-1,0
  3776.4    0.05       0  3960.3     0.1       0  4206.0    0.05       0
  4998.6    0.04       0  5004.6    0.05       0
Bank Sta=4998.6,5004.6
Exp/Cntr=0.3,0.1

Type RM Length L Ch R = 1,14208,375,375,375
BEGIN DESCRIPTION:
NANCE BRANCH 14.0
END DESCRIPTION:
XS GIS Cut Line= 2
      3473535.98     10482619.74      3472566.39     10484063.35
#Sta/Elev= 30
  4331.8  438.21  4641.1  427.48  4818.0  421.82  4945.7  421.79  4971.0  421.85
  4995.0  415.06  4997.8  414.56  5001.0  415.06  5020.7  419.61  5028.0  416.81
  5034.0  419.23  5043.0  417.57  5049.0  422.33  5064.0  416.40  5070.0  419.85
  5078.1  417.20  5085.0  421.11  5106.0  422.23  5122.3  420.30  5129.1  416.95
  5142.0  416.26  5178.0  422.49  5204.7  422.80  5310.8  423.61  5319.9  423.72
  5435.0  425.25  5499.3  426.48  5526.0  429.16  5799.1  434.86  6070.8  438.14
#Mann=12,-1,0
  4331.8    0.05       0  4641.1    0.12       0  4945.7     0.1       0
  4995.0    0.07       0  5001.0     0.1       0  5078.1    0.12       0
  5122.3     0.1       0  5204.7    0.05       0  5310.8     0.1       0
  5319.9    0.05       0  5435.0     0.1       0  5499.3    0.05       0
Bank Sta=4995,5001
Exp/Cntr=0.3,0.1

Type RM Length L Ch R = 1,13833,818,818,818
BEGIN DESCRIPTION:
Mapping XS 49924327
END DESCRIPTION:
XS GIS Cut Line= 3
      3473523.82     10482567.44      3472777.28     10483192.44
      3472208.70     10484056.17
#Sta/Elev= 30
  4445.4  438.11  4584.5  434.88  4718.7  428.67  4753.4  426.74  4790.1  423.92
  4804.4  424.11  4825.9  422.64  4904.1  420.29  4968.3  421.09  4974.8  417.82
  4982.4  417.40  4989.1  418.68  4992.7  415.24  4995.4  414.74  4998.7  415.24
  5017.7  415.31  5024.3  419.19  5038.6  421.11  5209.0  420.32  5266.6  421.26
  5308.4  421.59  5336.6  423.34  5421.7  425.42  5466.0  425.58  5515.1  428.15
  5581.4  428.24  5623.5  429.85  5920.9  435.08  6123.5  437.42  6453.1  438.98
#Mann=6,-1,0
  4445.4    0.05       0  4718.7     0.1       0  4753.4    0.12       0
  4992.7    0.07       0  4998.7    0.12       0  5266.6    0.05       0
Bank Sta=4992.7,4998.7
Exp/Cntr=0.3,0.1

Type RM Length L Ch R = 1,13015,1440,1440,1440
BEGIN DESCRIPTION:
NANCE BRANCH 11.0
END DESCRIPTION:
XS GIS Cut Line= 2
      3473579.70     10482470.62      3471966.04     10482340.49
#Sta/Elev= 30
  4124.2  437.41  4212.1  437.31  4272.3  434.57  4292.3  434.89  4382.6  429.57
  4425.1  429.03  4452.9  425.89  4491.0  425.33  4563.2  422.48  4619.0  421.87
  4743.8  418.52  4854.2  417.12  4874.2  418.25  4964.5  419.16  4974.6  418.34
  5001.6  412.55  5004.4  412.05  5007.6  412.55  5024.7  419.37  5109.7  418.41
  5185.2  417.98  5301.1  420.54  5419.4  424.55  5446.1  426.50  5541.8  429.12
  5636.7  428.55  5664.2  430.72  5669.2  429.10  5717.0  432.15  5743.1  430.36
#Mann=7,-1,0
  4124.2    0.05       0  4491.0     0.1       0  4619.0    0.12       0
  5001.6    0.07       0  5007.6    0.12       0  5109.7    0.16       0
  5301.1    0.05       0
Bank Sta=5001.6,5007.6
Exp/Cntr=0.3,0.1

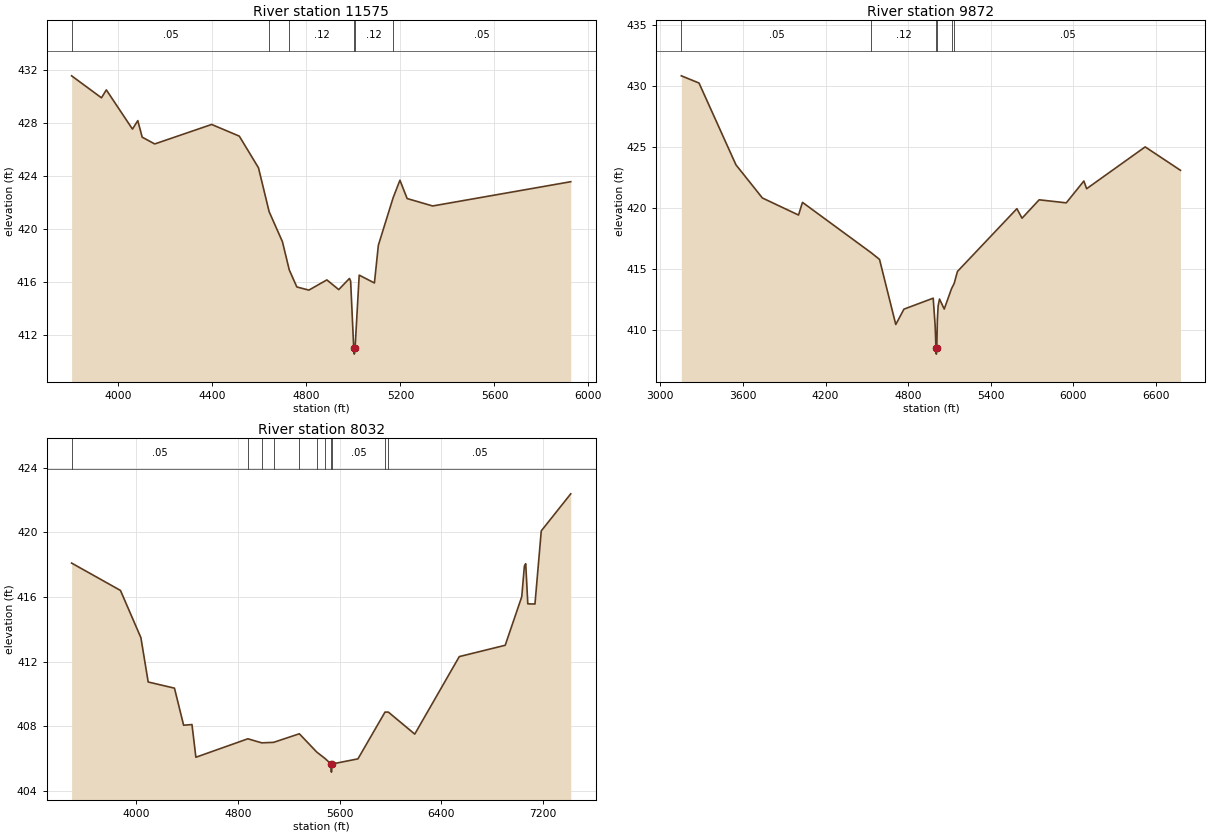
Type RM Length L Ch R = 1,11575,1703,1703,1703
BEGIN DESCRIPTION:
NANCE BRANCH 9.0
END DESCRIPTION:
XS GIS Cut Line= 4
      3473475.53     10481689.38      3472841.81     10481533.12
      3471817.51     10481324.78      3471626.85     10481706.10
#Sta/Elev= 30
  3800.5  431.58  3927.6  429.92  3948.2  430.52  4059.5  427.56  4082.1  428.20
  4100.9  426.95  4154.2  426.44  4396.5  427.91  4514.1  427.03  4595.8  424.64
  4641.1  421.33  4697.8  419.06  4726.7  416.94  4759.0  415.65  4810.1  415.41
  4886.8  416.18  4937.4  415.45  4982.9  416.29  4988.0  416.09  5001.0  411.08
  5003.7  410.58  5007.0  411.08  5024.4  416.54  5089.2  415.95  5106.0  418.80
  5168.8  422.38  5197.8  423.70  5228.5  422.32  5337.1  421.76  5924.8  423.59
#Mann=6,-1,0
  3800.5    0.05       0  4641.1    0.16       0  4726.7    0.12       0
  5001.0    0.07       0  5007.0    0.12       0  5168.8    0.05       0
Bank Sta=5001,5007
Exp/Cntr=0.3,0.1

Type RM Length L Ch R = 1,9872,1840,1840,1840
BEGIN DESCRIPTION:
NANCE BRANCH 1.0
END DESCRIPTION:
XS GIS Cut Line= 4
      3473603.96     10481033.73      3473031.04     10480044.14
      3471589.26     10480855.41      3471457.32     10481674.83
#Sta/Elev= 30
  3152.1  430.86  3280.7  430.27  3549.1  423.56  3741.3  420.84  4003.9  419.44
  4032.7  420.48  4533.1  416.34  4592.7  415.80  4710.8  410.46  4770.1  411.72
  4982.8  412.62  4997.0  410.36  5002.8  408.53  5005.5  408.03  5008.8  408.53
  5013.0  410.82  5018.7  411.99  5028.7  412.55  5063.1  411.73  5116.0  413.40
  5135.3  413.83  5158.9  414.81  5591.0  419.96  5628.6  419.18  5752.9  420.69
  5949.9  420.44  6077.8  422.23  6098.0  421.60  6523.5  425.03  6779.9  423.11
#Mann=6,-1,0
  3152.1    0.05       0  4533.1    0.12       0  5002.8    0.07       0
  5008.8    0.12       0  5116.0    0.16       0  5135.3    0.05       0
Bank Sta=5002.8,5008.8
Exp/Cntr=0.3,0.1

Type RM Length L Ch R = 1,8032,0,0,0
BEGIN DESCRIPTION:
NANCE BRANCH 2.0
END DESCRIPTION:
XS GIS Cut Line= 4
      3473886.75     10479711.57      3472755.71     10479068.60
      3471835.11     10479243.96      3471363.21     10480872.59
#Sta/Elev= 30
  3488.7  418.10  3873.6  416.41  4034.7  413.49  4092.2  410.75  4299.2  410.37
  4371.4  408.08  4437.3  408.12  4468.0  406.10  4877.7  407.24  4986.9  406.99
  5080.6  407.02  5283.4  407.55  5420.7  406.42  5486.2  406.02  5533.5  405.68
  5536.3  405.18  5539.5  405.68  5745.3  406.00  5958.6  408.89  5985.0  408.89
  6193.0  407.53  6543.9  412.32  6905.8  413.02  7036.3  416.02  7057.1  417.92
  7067.5  418.06  7084.1  415.58  7140.4  415.57  7190.1  420.09  7422.5  422.38
#Mann=11,-1,0
  3488.7    0.05       0  4877.7    0.16       0  4986.9    0.05       0
  5080.6    0.16       0  5283.4    0.05       0  5420.7    0.16       0
  5486.2    0.05       0  5533.5    0.03       0  5539.5    0.05       0
  5958.6     0.1       0  5985.0    0.05       0
Bank Sta=5533.5,5539.5
Exp/Cntr=0.3,0.1

Chan Stop Cuts=-1