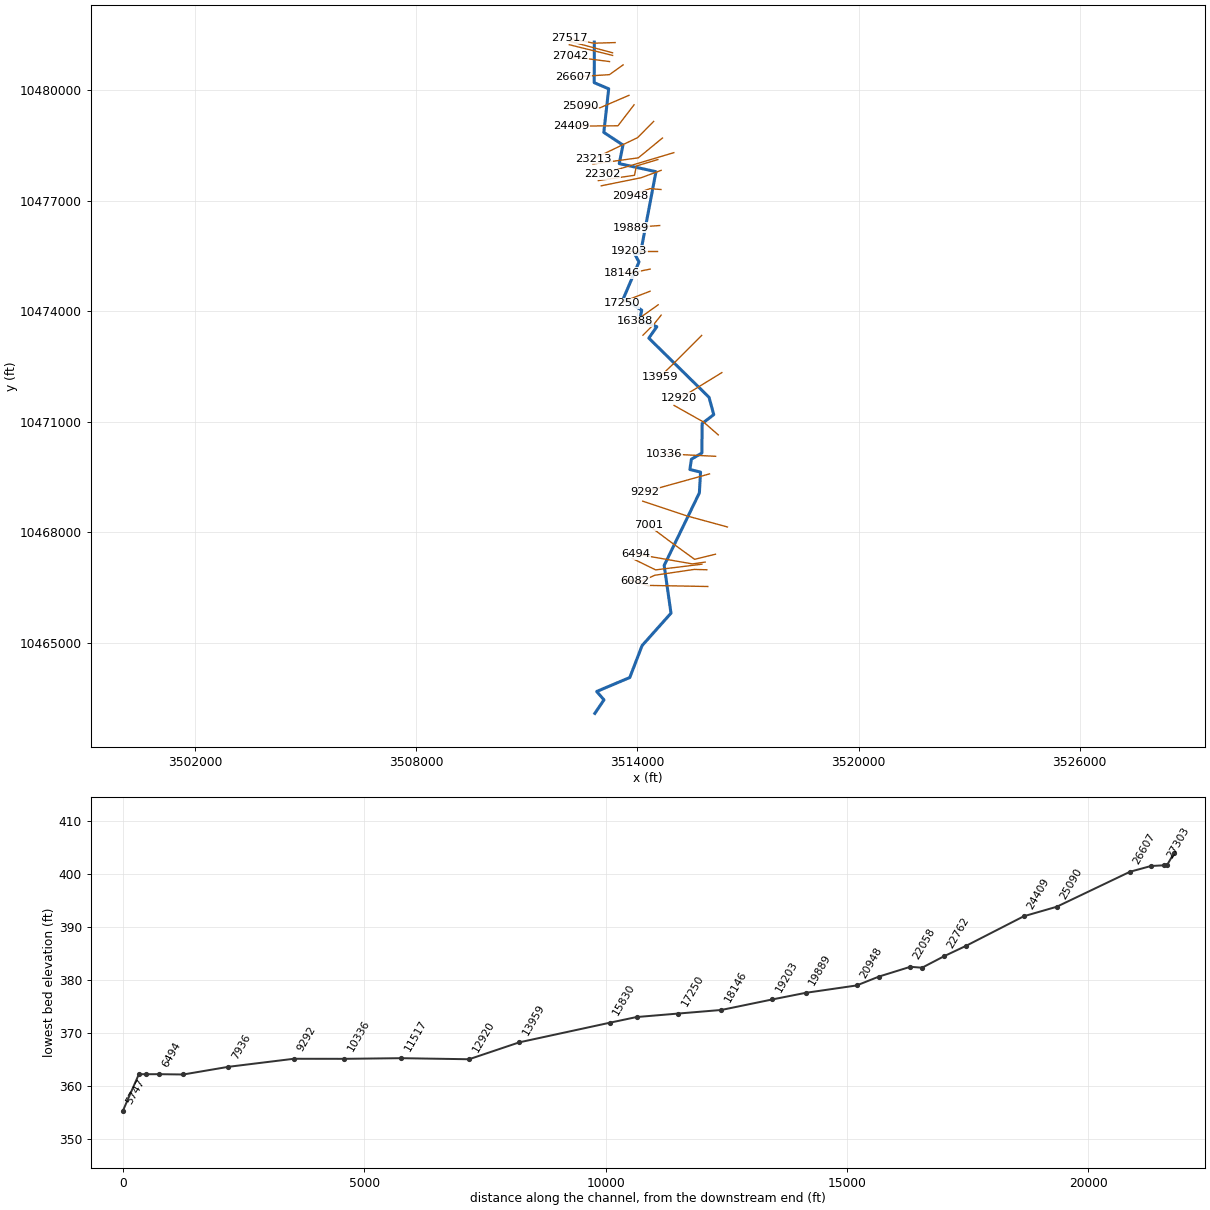
--- OWENS CREEK.prj (project) ---

Proj Title=OWENS CREEK Base Level Engineering
Current Plan=p01
Default Exp/Contr=0.3,0.1
English Units
Geom File=g01
Flow File=f01
Plan File=p01
BEGIN DESCRIPTION:
OWENS CREEK
END DESCRIPTION:

--- OWENS CREEK.p01 (plan) ---

Plan Title=Multiple Run
Short Identifier=Multiple
Geom File=g01
Flow File=f01
Subcritical Flow
K Sum by GR= 0
Std Step Tol= 0.01
Critical Tol= 0.01
Num of Std Step Trials= 20
Max Error Tol= 0.3
Flow Tol Ratio= 0.001
Split Flow NTrial= 30
Split Flow Tol= 0.02
Split Flow Ratio= 0.02
Log Output Level= 0
Friction Slope Method= 1
Unsteady Friction Slope Method= 2
Unsteady Bridges Friction Slope Method= 1
Parabolic Critical Depth
Global Vel Dist=  1 , 1 , 1
Global Log Level= 0
CheckData=True
Encroach Param= -1, 0, 0, 0
BEGIN DESCRIPTION:
Multiple Run
END DESCRIPTION:

--- OWENS CREEK.f01 (steady flow) ---

Flow Title=Multiple
Number of Profiles=7
Profile Names=10-year,25-year,50-year,1pct_min,100-year,1pct_plu,500-year
River Rch & RM= OWENS CREEK,Reach-1,27517
     850    1154    1401    1241    1678    2270    2402
River Rch & RM= OWENS CREEK,Reach-1,23213
    1409    1970    2439    2200    2975    4023    4417
River Rch & RM= OWENS CREEK,Reach-1,22302
    1770    2493    3101    2807    3796    5134    5679
River Rch & RM= OWENS CREEK,Reach-1,13959
    2092    2960    3693    3351    4532    6129    6812
River Rch & RM= OWENS CREEK,Reach-1,7936
    2656    3796    4768    4351    5885    7958    8950
Boundary for River Rch & Prof#=OWENS CREEK,Reach-1,1
Up Type=0
Dn Type=3
Dn Slope=0.005
Boundary for River Rch & Prof#=OWENS CREEK,Reach-1,2
Up Type=0
Dn Type=3
Dn Slope=0.005
Boundary for River Rch & Prof#=OWENS CREEK,Reach-1,3
Up Type=0
Dn Type=3
Dn Slope=0.005
Boundary for River Rch & Prof#=OWENS CREEK,Reach-1,4
Up Type=0
Dn Type=3
Dn Slope=0.005
Boundary for River Rch & Prof#=OWENS CREEK,Reach-1,5
Up Type=0
Dn Type=3
Dn Slope=0.005
Boundary for River Rch & Prof#=OWENS CREEK,Reach-1,6
Up Type=0
Dn Type=3
Dn Slope=0.005
Boundary for River Rch & Prof#=OWENS CREEK,Reach-1,7
Up Type=0
Dn Type=3
Dn Slope=0.005

--- OWENS CREEK.g01 (geometry) ---

Geom Title=Existing Conditions

River Reach=OWENS CREEK,Reach-1
Reach XY= 30
      3512828.37     10481304.15      3512825.54     10480203.05
      3513218.07     10480036.63      3513085.38     10478853.72
      3513605.66     10478510.31      3513504.45     10478005.95
      3514501.62     10477787.02      3514080.53     10475567.01
      3513912.98     10475571.70      3514040.09     10475337.29
      3513614.20     10474337.03      3514114.63     10474027.77
      3514058.50     10473754.65      3514524.42     10473577.41
      3514307.51     10473268.84      3515942.10     10471661.73
      3516070.29     10471191.51      3515755.52     10470950.21
      3515747.33     10470148.95      3515463.42     10469981.67
      3515422.20     10469701.79      3515711.58     10469631.13
      3515679.96     10469067.23      3514724.07     10467095.83
      3514909.03     10465801.24      3514124.39     10464921.03
      3513790.36     10464054.71      3512892.53     10463676.03
      3513089.94     10463448.80      3512842.11     10463081.64

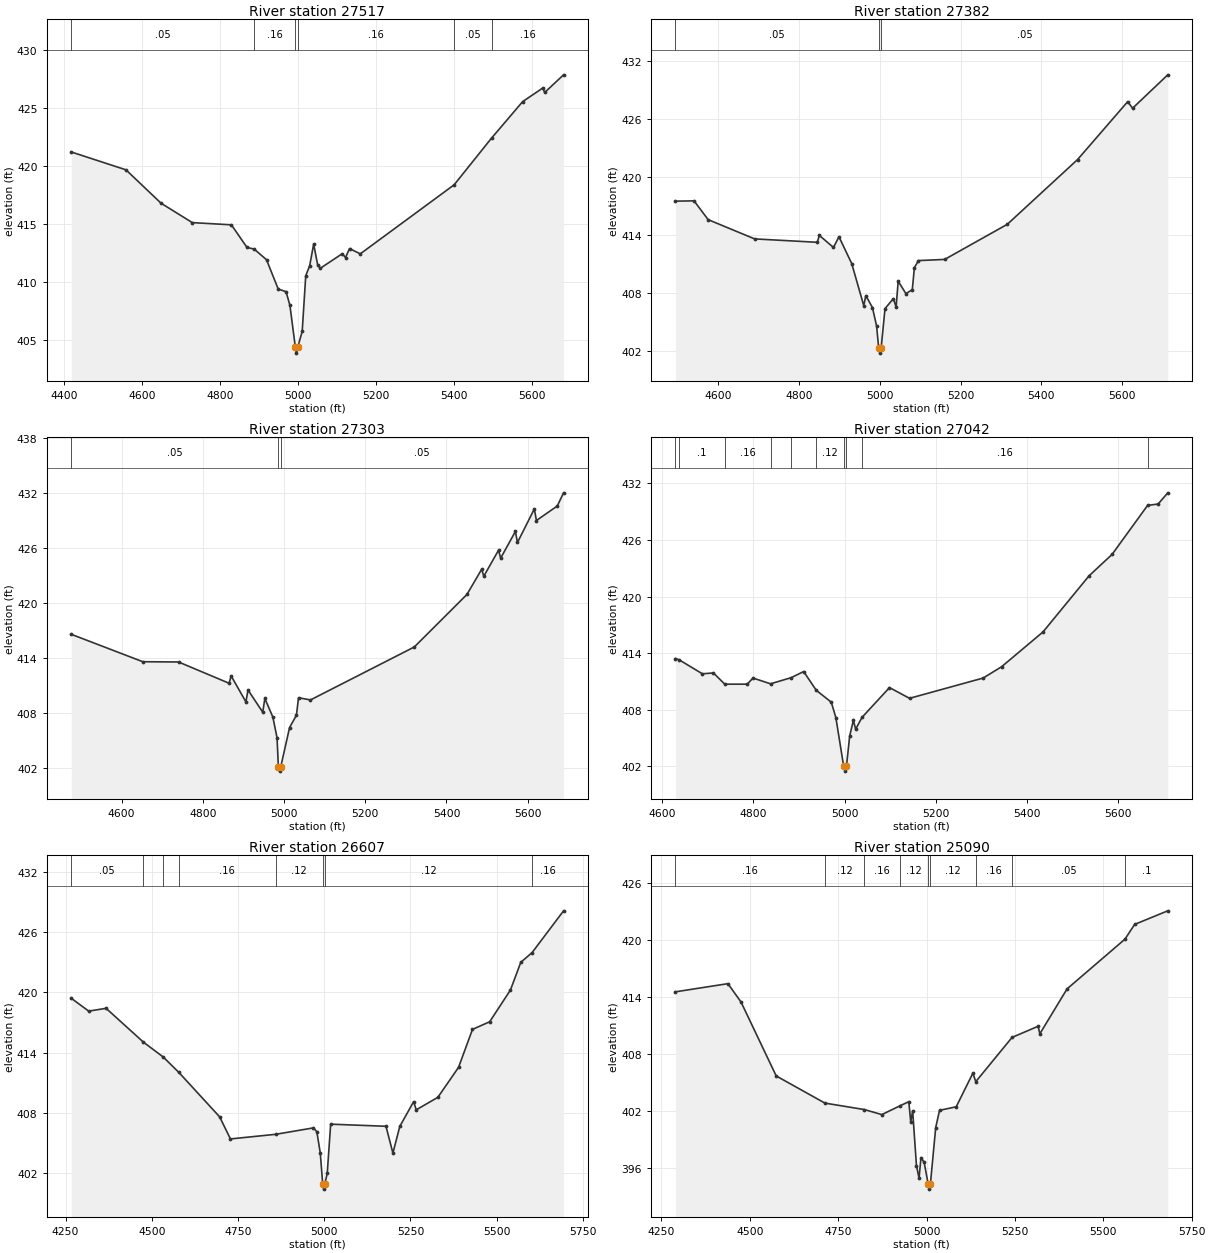
Type RM Length L Ch R = 1,27517,135,135,135
BEGIN DESCRIPTION:
OWENS CREEK 46.0
END DESCRIPTION:
XS GIS Cut Line= 3
      3513392.11     10481291.64      3512813.38     10481274.98
      3512144.02     10481406.84
#Sta/Elev= 30
  4419.0  421.22  4559.1  419.68  4649.1  416.80  4729.1  415.13  4829.2  414.94
  4869.2  412.99  4887.6  412.85  4919.2  411.93  4949.2  409.40  4969.2  409.18
  4979.2  407.99  4993.1  404.38  4995.9  403.88  4999.1  404.38  5010.6  405.75
  5019.7  410.55  5029.8  411.42  5040.0  413.28  5050.2  411.49  5056.8  411.19
  5113.3  412.45  5121.6  412.12  5131.8  412.89  5159.5  412.44  5399.9  418.39
  5495.6  422.41  5575.4  425.56  5626.8  426.73  5631.9  426.35  5680.2  427.87
#Mann=6,-1,0
  4419.0    0.05       0  4887.6    0.16       0  4993.1    0.07       0
  4999.1    0.16       0  5399.9    0.05       0  5495.6    0.16       0
Bank Sta=4993.1,4999.1
Exp/Cntr=0.3,0.1

Type RM Length L Ch R = 1,27382,79,79,79
BEGIN DESCRIPTION:
Mapping XS 1624acd7
END DESCRIPTION:
XS GIS Cut Line= 2
      3513322.75     10481015.10      3512146.37     10481330.01
#Sta/Elev= 30
  4494.9  417.48  4540.8  417.51  4575.7  415.57  4690.7  413.58  4845.6  413.23
  4850.8  413.94  4885.7  412.70  4899.3  413.80  4930.9  411.03  4960.6  406.69
  4965.8  407.72  4982.1  406.49  4992.5  404.56  4997.6  402.28  5000.4  401.78
  5003.6  402.28  5013.2  406.38  5033.9  407.41  5040.7  406.54  5045.8  409.21
  5064.9  407.93  5080.7  408.33  5085.9  410.61  5096.0  411.34  5160.8  411.46
  5315.8  415.09  5489.4  421.77  5613.6  427.76  5625.7  427.08  5712.7  430.53
#Mann=3,-1,0
  4494.9    0.05       0  4997.6    0.04       0  5003.6    0.05       0
Bank Sta=4997.6,5003.6
Exp/Cntr=0.3,0.1

Type RM Length L Ch R = 1,27303,261,261,261
BEGIN DESCRIPTION:
Mapping XS 598ebf4c
END DESCRIPTION:
XS GIS Cut Line= 2
      3513324.04     10480943.49      3512147.02     10481233.84
#Sta/Elev= 30
  4476.1  416.56  4652.2  413.57  4740.3  413.54  4864.7  411.22  4869.8  412.02
  4906.2  409.18  4911.3  410.49  4947.6  408.06  4952.8  409.56  4972.5  407.53
  4982.8  405.28  4986.1  402.13  4988.9  401.63  4992.1  402.13  5013.7  406.39
  5030.6  407.73  5035.7  409.64  5065.2  409.40  5320.9  415.18  5450.5  420.91
  5486.8  423.66  5492.0  422.90  5528.3  425.74  5533.5  424.87  5569.8  427.78
  5574.9  426.58  5616.4  430.24  5621.6  428.98  5672.9  430.56  5688.4  432.00
#Mann=3,-1,0
  4476.1    0.05       0  4986.1    0.04       0  4992.1    0.05       0
Bank Sta=4986.1,4992.1
Exp/Cntr=0.3,0.1

Type RM Length L Ch R = 1,27042,435,435,435
BEGIN DESCRIPTION:
OWENS CREEK 45.0
END DESCRIPTION:
XS GIS Cut Line= 2
      3513240.53     10480776.07      3512171.11     10480914.96
#Sta/Elev= 30
  4629.7  413.44  4637.5  413.31  4688.6  411.82  4712.8  411.91  4737.7  410.72
  4786.9  410.72  4799.5  411.37  4837.9  410.76  4883.1  411.41  4910.5  412.06
  4938.1  410.07  4971.0  408.81  4981.0  407.18  4998.2  402.00  5001.0  401.50
  5004.2  402.00  5011.3  405.23  5019.4  406.89  5024.4  405.95  5038.3  407.20
  5098.5  410.36  5142.4  409.22  5303.7  411.37  5344.1  412.57  5434.8  416.26
  5535.7  422.21  5586.1  424.48  5664.0  429.68  5686.9  429.82  5708.1  431.01
#Mann=10,-1,0
  4629.7    0.05       0  4637.5     0.1       0  4737.7    0.16       0
  4837.9    0.12       0  4883.1    0.16       0  4938.1    0.12       0
  4998.2    0.07       0  5004.2    0.12       0  5038.3    0.16       0
  5664.0     0.1       0
Bank Sta=4998.2,5004.2
Exp/Cntr=0.3,0.1

Type RM Length L Ch R = 1,26607,1517,1517,1517
BEGIN DESCRIPTION:
OWENS CREEK 44.0
END DESCRIPTION:
XS GIS Cut Line= 3
      3513608.64     10480685.80      3513240.57     10480421.90
      3512268.38     10480359.40
#Sta/Elev= 30
  4266.7  419.42  4317.3  418.14  4367.6  418.42  4475.5  415.06  4533.6  413.56
  4578.7  412.03  4696.8  407.61  4728.1  405.41  4859.2  405.87  4968.6  406.51
  4978.6  406.13  4988.6  403.99  4995.6  400.91  4998.4  400.41  5001.6  400.91
  5008.7  401.98  5018.7  406.88  5179.0  406.67  5199.1  404.00  5219.1  406.66
  5259.2  409.12  5266.7  408.31  5329.3  409.55  5389.4  412.54  5429.8  416.32
  5479.6  417.08  5539.8  420.24  5569.8  423.00  5602.6  423.97  5693.8  428.13
#Mann=8,-1,0
  4266.7    0.05       0  4475.5     0.1       0  4533.6    0.05       0
  4578.7    0.16       0  4859.2    0.12       0  4995.6    0.07       0
  5001.6    0.12       0  5602.6    0.16       0
Bank Sta=4995.6,5001.6
Exp/Cntr=0.3,0.1

Type RM Length L Ch R = 1,25090,681,681,681
BEGIN DESCRIPTION:
OWENS CREEK 41.0
END DESCRIPTION:
XS GIS Cut Line= 3
      3513768.35     10479859.40      3512976.68     10479519.12
      3512448.89     10479574.68
#Sta/Elev= 30
  4290.0  414.58  4438.3  415.44  4475.3  413.51  4574.9  405.72  4712.7  402.86
  4824.2  402.18  4873.7  401.65  4925.8  402.59  4949.9  403.01  4955.4  400.88
  4960.8  402.06  4971.6  396.26  4978.9  394.96  4984.3  397.12  4993.4  396.62
  5004.9  394.30  5007.6  393.80  5010.9  394.30  5026.0  400.28  5036.9  402.10
  5084.0  402.47  5131.1  406.01  5139.4  405.12  5242.0  409.78  5315.6  410.95
  5320.6  410.16  5397.6  414.89  5561.4  420.13  5588.7  421.68  5682.4  423.11
#Mann=9,-1,0
  4290.0    0.16       0  4712.7    0.12       0  4824.2    0.16       0
  4925.8    0.12       0  5004.9    0.07       0  5010.9    0.12       0
  5139.4    0.16       0  5242.0    0.05       0  5561.4     0.1       0
Bank Sta=5004.9,5010.9
Exp/Cntr=0.3,0.1

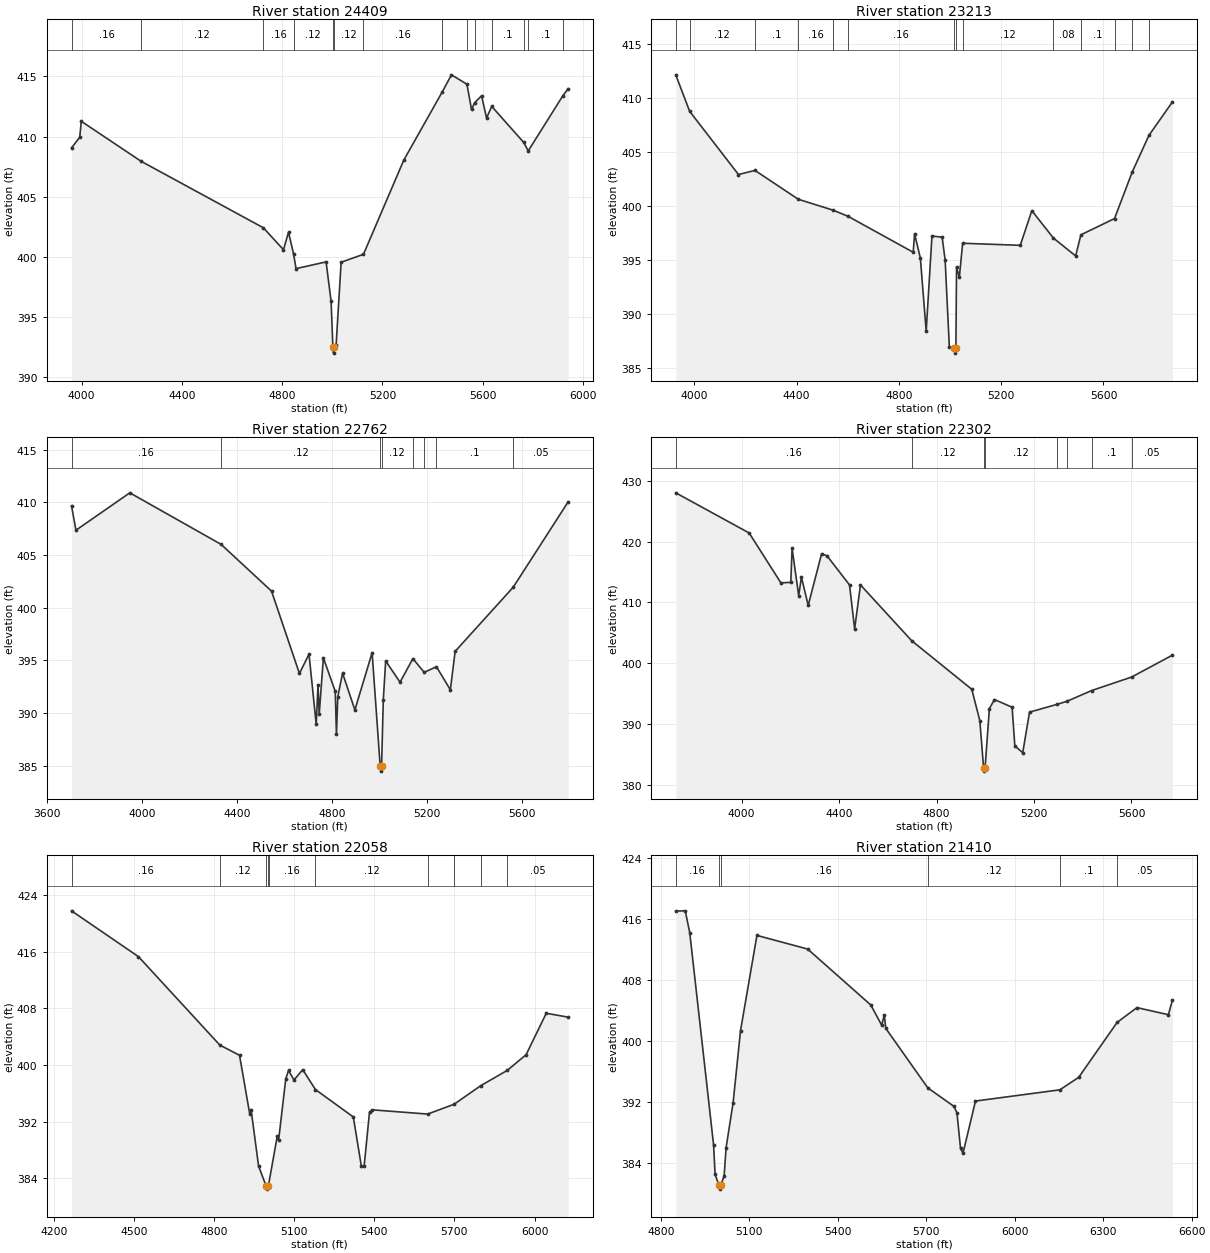
Type RM Length L Ch R = 1,24409,1196,1196,1196
BEGIN DESCRIPTION:
OWENS CREEK 39.0
END DESCRIPTION:
XS GIS Cut Line= 4
      3513907.23     10479602.46      3513469.73     10479033.01
      3512566.95     10479026.07      3512206.43     10479019.13
#Sta/Elev= 30
  3959.6  409.06  3992.4  409.94  3998.7  411.27  4237.9  407.94  4725.2  402.42
  4805.3  400.60  4825.3  402.06  4845.4  400.26  4855.3  399.03  4975.3  399.59
  4995.3  396.30  5002.3  392.51  5005.1  392.01  5008.3  392.51  5015.3  392.68
  5035.3  399.56  5124.4  400.22  5285.4  408.05  5438.4  413.70  5475.4  415.13
  5537.2  414.35  5555.4  412.25  5567.8  412.81  5595.4  413.39  5615.4  411.54
  5636.0  412.51  5763.0  409.53  5781.7  408.81  5919.7  413.39  5941.1  413.98
#Mann=14,-1,0
  3959.6    0.16       0  4237.9    0.12       0  4725.2    0.16       0
  4845.4    0.12       0  5002.3    0.07       0  5008.3    0.12       0
  5124.4    0.16       0  5438.4    0.05       0  5537.2     0.1       0
  5567.8    0.05       0  5636.0     0.1       0  5763.0    0.05       0
  5781.7     0.1       0  5919.7    0.05       0
Bank Sta=5002.3,5008.3
Exp/Cntr=0.3,0.1

Type RM Length L Ch R = 1,23213,451,451,451
BEGIN DESCRIPTION:
OWENS CREEK 38.0
END DESCRIPTION:
XS GIS Cut Line= 3
      3514438.63     10479151.91      3514003.76     10478711.83
      3512811.02     10478138.90
#Sta/Elev= 30
  3927.7  412.13  3982.0  408.76  4172.9  402.92  4237.3  403.30  4407.1  400.63
  4542.3  399.63  4601.2  399.06  4856.0  395.74  4861.5  397.44  4884.1  395.19
  4906.8  388.44  4929.4  397.24  4969.2  397.13  4980.9  395.02  4997.4  386.97
  5017.0  386.92  5019.7  386.42  5023.0  386.92  5025.5  394.40  5036.4  393.42
  5049.4  396.57  5274.6  396.38  5319.9  399.58  5404.1  397.05  5491.2  395.40
  5511.7  397.35  5643.1  398.85  5711.8  403.12  5777.5  406.53  5869.6  409.63
#Mann=14,-1,0
  3927.7    0.05       0  3982.0    0.12       0  4237.3     0.1       0
  4407.1    0.16       0  4542.3    0.12       0  4601.2    0.16       0
  5017.0    0.07       0  5023.0    0.16       0  5049.4    0.12       0
  5404.1    0.08       0  5511.7     0.1       0  5643.1    0.05       0
  5711.8     0.1       0  5777.5    0.05       0
Bank Sta=5017,5023
Exp/Cntr=0.3,0.1

Type RM Length L Ch R = 1,22762,460,460,460
BEGIN DESCRIPTION:
OWENS CREEK 37.0
END DESCRIPTION:
XS GIS Cut Line= 3
      3514678.22     10478701.39      3514021.99     10478162.35
      3512790.25     10477995.69
#Sta/Elev= 30
  3702.7  409.67  3721.5  407.35  3948.3  410.90  4332.6  406.01  4545.2  401.57
  4662.8  393.75  4703.2  395.58  4733.5  388.92  4741.1  392.69  4746.1  389.88
  4763.7  395.23  4813.7  392.05  4818.7  387.96  4824.3  391.53  4844.5  393.78
  4896.4  390.29  4969.0  395.72  5002.9  384.98  5005.7  384.48  5008.9  384.98
  5016.0  391.22  5026.1  394.94  5086.6  392.92  5140.7  395.16  5188.3  393.86
  5240.0  394.39  5298.6  392.20  5318.7  395.85  5563.4  401.94  5794.9  410.05
#Mann=8,-1,0
  3702.7    0.16       0  4332.6    0.12       0  5002.9    0.07       0
  5008.9    0.12       0  5140.7     0.1       0  5188.3    0.08       0
  5240.0     0.1       0  5563.4    0.05       0
Bank Sta=5002.9,5008.9
Exp/Cntr=0.3,0.1

Type RM Length L Ch R = 1,22302,244,244,244
BEGIN DESCRIPTION:
OWENS CREEK 36.0
END DESCRIPTION:
XS GIS Cut Line= 2
      3514985.51     10478302.97      3513032.36     10477719.63
#Sta/Elev= 30
  3729.8  428.02  4031.1  421.42  4161.2  413.23  4202.0  413.31  4207.2  418.92
  4234.3  411.12  4245.5  414.17  4273.4  409.52  4328.2  417.99  4350.1  417.69
  4443.0  412.88  4463.9  405.66  4487.9  412.89  4698.0  403.72  4944.6  395.74
  4977.7  390.59  4993.2  382.79  4995.9  382.29  4999.2  382.79  5017.0  392.58
  5037.9  394.05  5110.2  392.79  5121.4  386.43  5153.8  385.32  5181.7  391.98
  5292.6  393.24  5334.4  393.75  5436.4  395.53  5600.7  397.75  5768.2  401.35
#Mann=8,-1,0
  3729.8    0.16       0  4698.0    0.12       0  4993.2    0.07       0
  4999.2    0.12       0  5292.6     0.1       0  5334.4    0.05       0
  5436.4     0.1       0  5600.7    0.05       0
Bank Sta=4993.2,4999.2
Exp/Cntr=0.3,0.1

Type RM Length L Ch R = 1,22058,648,648,648
BEGIN DESCRIPTION:
Mapping XS 20e09734
END DESCRIPTION:
XS GIS Cut Line= 4
      3514552.39     10478115.94      3513968.67     10477940.96
      3513919.46     10477689.43      3512936.14     10477544.66
#Sta/Elev= 30
  4266.5  421.80  4517.3  415.32  4821.9  402.82  4895.6  401.38  4933.7  393.11
  4938.8  393.71  4966.9  385.72  4994.5  382.96  4997.2  382.46  5000.5  382.96
  5004.1  383.02  5036.7  389.91  5041.8  389.35  5068.8  398.06  5079.0  399.24
  5099.4  397.89  5132.2  399.35  5179.7  396.54  5321.6  392.66  5351.9  385.66
  5362.2  385.73  5382.2  393.33  5392.3  393.67  5599.8  393.07  5699.1  394.46
  5798.5  397.08  5897.8  399.24  5968.5  401.46  6044.0  407.32  6126.1  406.77
#Mann=10,-1,0
  4266.5    0.16       0  4821.9    0.12       0  4994.5    0.07       0
  5000.5    0.12       0  5004.1    0.16       0  5179.7    0.12       0
  5599.8     0.1       0  5699.1    0.05       0  5798.5     0.1       0
  5897.8    0.05       0
Bank Sta=4994.5,5000.5
Exp/Cntr=0.3,0.1

Type RM Length L Ch R = 1,21410,462,462,462
BEGIN DESCRIPTION:
Mapping XS c5098f41
END DESCRIPTION:
XS GIS Cut Line= 3
      3514642.33     10477822.80      3514098.48     10477622.65
      3513016.07     10477403.41
#Sta/Elev= 30
  4851.0  417.05  4883.2  417.08  4898.5  414.20  4979.1  386.46  4984.5  382.54
  4997.4  381.12  5000.2  380.62  5003.4  381.12  5015.0  382.33  5021.7  386.05
  5045.5  391.95  5070.6  401.39  5126.2  413.86  5298.3  412.07  5512.3  404.74
  5549.2  402.09  5557.9  403.45  5563.0  401.68  5705.4  393.89  5794.1  391.46
  5804.3  390.62  5816.5  385.96  5824.7  385.31  5867.2  392.16  6153.2  393.63
  6217.0  395.26  6347.5  402.47  6414.6  404.40  6521.1  403.47  6534.9  405.39
#Mann=6,-1,0
  4851.0    0.16       0  4997.4    0.07       0  5003.4    0.16       0
  5705.4    0.12       0  6153.2     0.1       0  6347.5    0.05       0
Bank Sta=4997.4,5003.4
Exp/Cntr=0.3,0.1

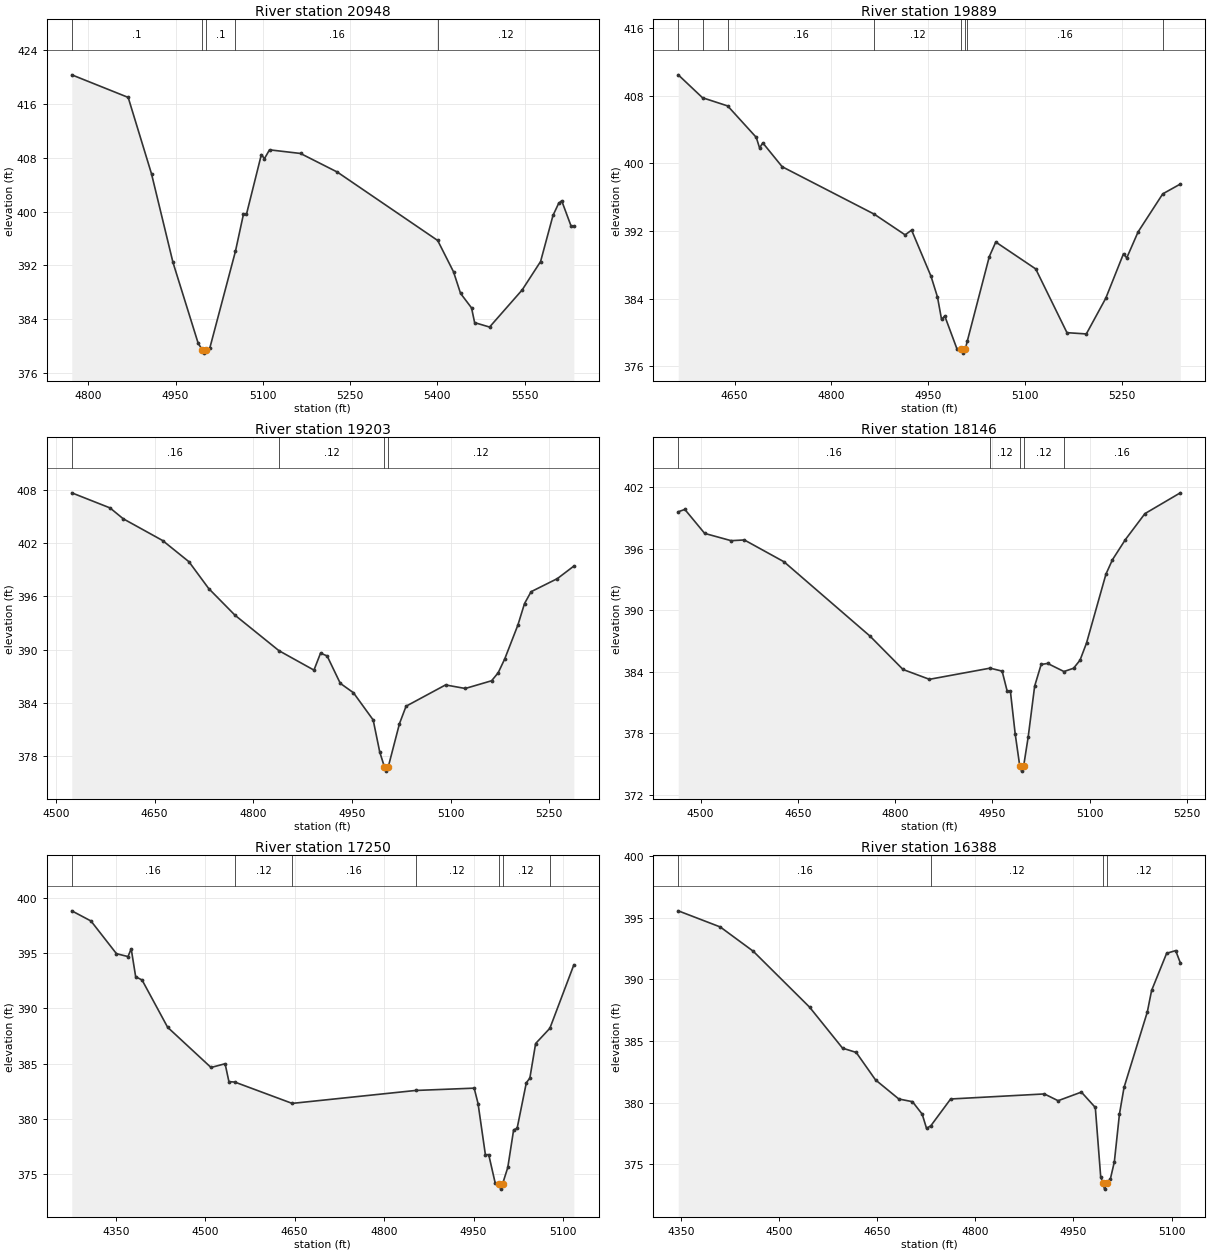
Type RM Length L Ch R = 1,20948,1059,1059,1059
BEGIN DESCRIPTION:
OWENS CREEK 33.0
END DESCRIPTION:
XS GIS Cut Line= 3
      3514638.75     10477302.30      3514341.89     10477326.61
      3513808.34     10477139.39
#Sta/Elev= 30
  4771.5  420.35  4868.5  416.99  4908.6  405.62  4945.5  392.44  4988.9  380.39
  4995.9  379.44  4998.7  378.94  5001.9  379.44  5008.9  379.71  5052.9  394.08
  5066.7  399.61  5071.9  399.61  5097.5  408.48  5102.8  407.88  5111.5  409.19
  5164.8  408.65  5228.1  405.88  5400.7  395.70  5427.9  391.04  5440.0  387.83
  5458.9  385.67  5464.2  383.48  5489.9  382.82  5546.0  388.35  5577.6  392.57
  5599.0  399.44  5608.6  401.21  5613.9  401.61  5630.2  397.81  5634.8  397.81
#Mann=5,-1,0
  4771.5     0.1       0  4995.9    0.07       0  5001.9     0.1       0
  5052.9    0.16       0  5400.7    0.12       0
Bank Sta=4995.9,5001.9
Exp/Cntr=0.3,0.1

Type RM Length L Ch R = 1,19889,686,686,686
BEGIN DESCRIPTION:
OWENS CREEK 31.0
END DESCRIPTION:
XS GIS Cut Line= 2
      3514602.75     10476325.55      3513826.90     10476270.59
#Sta/Elev= 30
  4562.6  410.46  4600.2  407.75  4639.2  406.78  4683.5  403.06  4688.6  401.81
  4693.6  402.41  4723.6  399.59  4866.2  393.98  4914.1  391.53  4924.1  392.09
  4954.2  386.63  4964.2  384.18  4970.5  381.54  4975.5  381.93  4994.3  378.06
  5001.4  378.04  5004.1  377.54  5007.4  378.04  5010.4  378.96  5044.5  388.96
  5054.5  390.68  5116.4  387.50  5164.8  379.96  5194.8  379.81  5224.9  384.03
  5252.4  389.30  5257.4  388.80  5275.0  391.88  5313.2  396.38  5340.4  397.54
#Mann=8,-1,0
  4562.6    0.16       0  4600.2    0.05       0  4639.2    0.16       0
  4866.2    0.12       0  5001.4    0.07       0  5007.4    0.12       0
  5010.4    0.16       0  5313.2    0.12       0
Bank Sta=5001.4,5007.4
Exp/Cntr=0.3,0.1

Type RM Length L Ch R = 1,19203,1057,1057,1057
BEGIN DESCRIPTION:
OWENS CREEK 29.0
END DESCRIPTION:
XS GIS Cut Line= 2
      3514540.24     10475638.04      3513777.14     10475638.04
#Sta/Elev= 30
  4524.1  407.68  4582.2  405.98  4602.2  404.76  4662.2  402.30  4702.2  399.91
  4732.2  396.89  4772.2  393.88  4839.0  389.88  4892.2  387.69  4902.2  389.60
  4912.2  389.29  4932.2  386.20  4952.2  385.14  4982.2  382.07  4992.2  378.45
  4999.2  376.80  5002.0  376.30  5005.2  376.80  5022.2  381.66  5032.2  383.62
  5092.2  386.02  5122.2  385.62  5162.2  386.49  5172.2  387.39  5182.2  388.96
  5202.2  392.78  5212.2  395.19  5222.2  396.53  5262.2  398.01  5287.2  399.42
#Mann=4,-1,0
  4524.1    0.16       0  4839.0    0.12       0  4999.2    0.07       0
  5005.2    0.12       0
Bank Sta=4999.2,5005.2
Exp/Cntr=0.3,0.1

Type RM Length L Ch R = 1,18146,896,896,896
BEGIN DESCRIPTION:
OWENS CREEK 27.0
END DESCRIPTION:
XS GIS Cut Line= 3
      3514342.12     10475141.65      3513842.11     10475041.64
      3513577.47     10475036.79
#Sta/Elev= 30
  4465.5  399.62  4475.7  399.85  4506.3  397.51  4547.1  396.80  4567.5  396.87
  4628.7  394.74  4761.3  387.49  4812.3  384.23  4853.0  383.27  4946.6  384.36
  4965.2  384.07  4972.9  382.14  4977.9  382.14  4985.4  377.92  4992.4  374.81
  4995.2  374.31  4998.4  374.81  5005.4  377.64  5015.4  382.61  5025.4  384.72
  5035.4  384.82  5060.6  384.03  5075.4  384.35  5085.4  385.14  5095.4  386.81
  5125.4  393.54  5135.4  394.94  5155.4  396.91  5185.5  399.44  5240.1  401.47
#Mann=5,-1,0
  4465.5    0.16       0  4946.6    0.12       0  4992.4    0.07       0
  4998.4    0.12       0  5060.6    0.16       0
Bank Sta=4992.4,4998.4
Exp/Cntr=0.3,0.1

Type RM Length L Ch R = 1,17250,862,862,862
BEGIN DESCRIPTION:
OWENS CREEK 25.0
END DESCRIPTION:
XS GIS Cut Line= 3
      3514342.14     10474541.66      3513692.11     10474291.64
      3513567.13     10474216.66
#Sta/Elev= 30
  4276.1  398.82  4308.3  397.90  4351.1  394.94  4370.4  394.68  4375.8  395.38
  4383.3  392.85  4394.0  392.56  4436.9  388.28  4509.7  384.64  4533.3  384.98
  4539.7  383.36  4549.6  383.32  4645.8  381.39  4852.8  382.56  4951.1  382.77
  4957.6  381.38  4969.9  376.75  4975.5  376.75  4986.2  374.22  4992.9  374.13
  4995.6  373.63  4998.9  374.13  5007.5  375.59  5017.3  379.00  5023.1  379.12
  5038.6  383.26  5044.5  383.68  5054.2  386.81  5078.1  388.19  5118.3  393.93
#Mann=7,-1,0
  4276.1    0.16       0  4549.6    0.12       0  4645.8    0.16       0
  4852.8    0.12       0  4992.9    0.07       0  4998.9    0.12       0
  5078.1     0.1       0
Bank Sta=4992.9,4998.9
Exp/Cntr=0.3,0.1

Type RM Length L Ch R = 1,16388,558,558,558
BEGIN DESCRIPTION:
OWENS CREEK 23.0
END DESCRIPTION:
XS GIS Cut Line= 2
      3514561.04     10474172.76      3513936.35     10473727.21
#Sta/Elev= 30
  4346.1  395.57  4410.3  394.26  4460.7  392.29  4546.8  387.75  4597.2  384.42
  4618.1  384.07  4647.6  381.84  4683.2  380.29  4704.1  380.07  4718.9  379.06
  4725.6  377.90  4732.2  378.12  4762.4  380.29  4905.7  380.70  4926.6  380.15
  4962.2  380.85  4983.5  379.60  4991.7  373.99  4994.9  373.47  4997.6  372.97
  5000.9  373.47  5006.5  373.79  5012.6  375.19  5020.4  379.07  5027.4  381.23
  5063.0  387.36  5069.5  389.10  5092.5  392.12  5106.3  392.34  5113.4  391.35
#Mann=4,-1,0
  4346.1    0.16       0  4732.2    0.12       0  4994.9    0.07       0
  5000.9    0.12       0
Bank Sta=4994.9,5000.9
Exp/Cntr=0.3,0.1

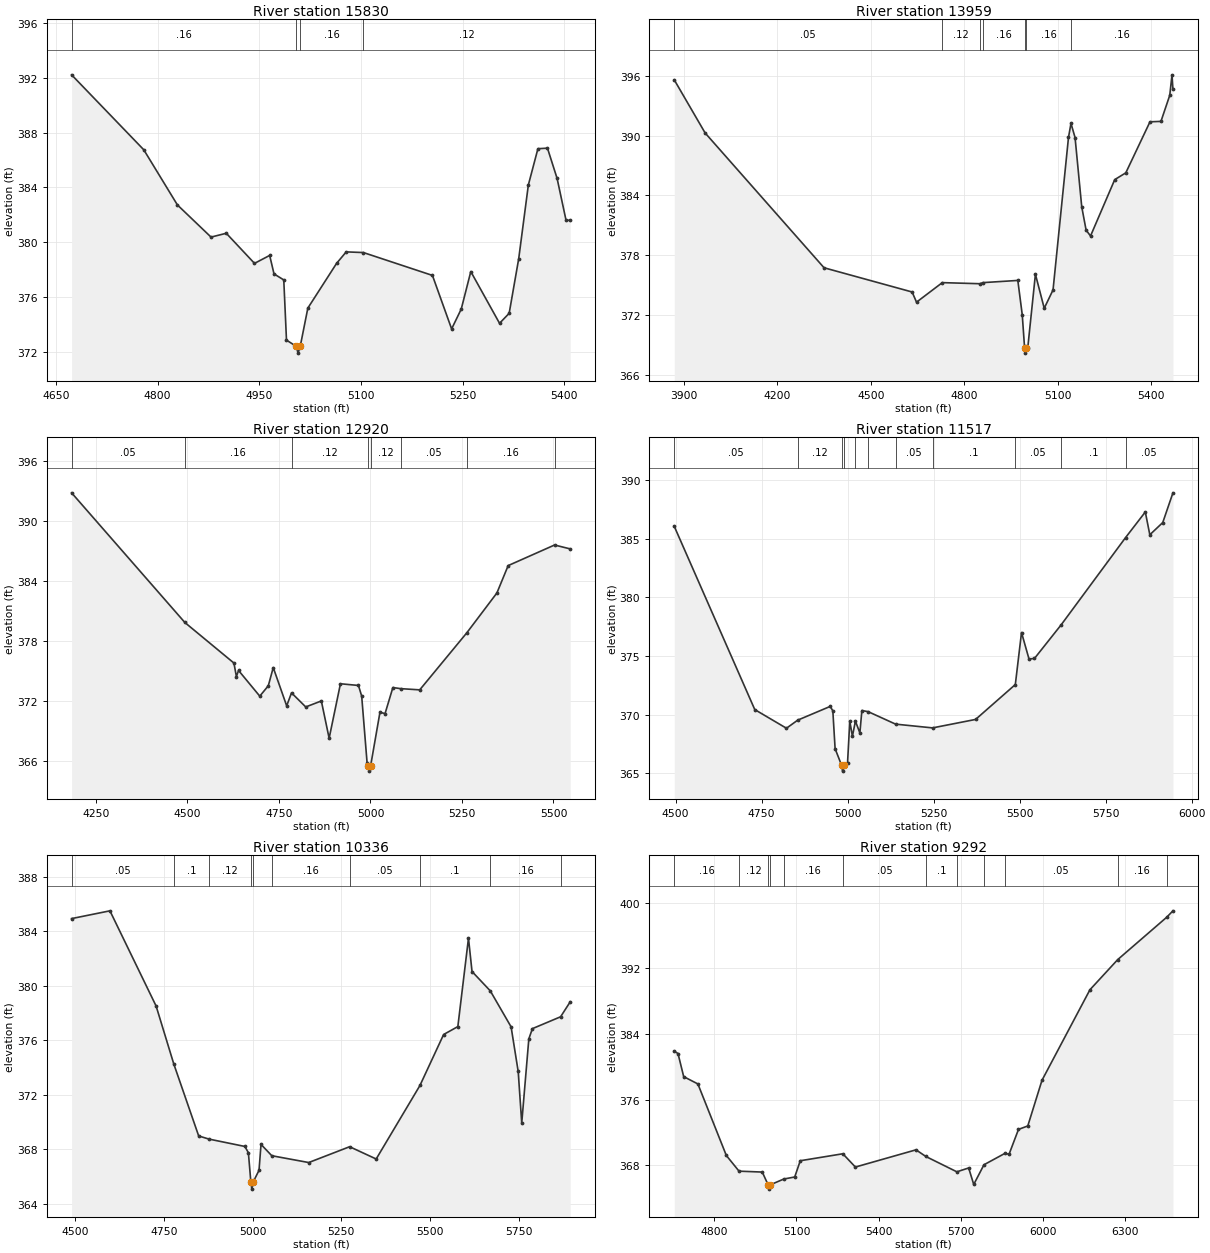
Type RM Length L Ch R = 1,15830,1871,1871,1871
BEGIN DESCRIPTION:
OWENS CREEK 22.0
END DESCRIPTION:
XS GIS Cut Line= 3
      3514642.13     10473891.68      3514442.11     10473641.64
      3514148.37     10473347.91
#Sta/Elev= 30
  4673.2  392.23  4779.7  386.75  4829.3  382.72  4878.9  380.37  4901.4  380.65
  4943.0  378.45  4965.4  379.03  4971.8  377.68  4986.2  377.24  4990.2  372.84
  5004.5  372.39  5007.3  371.89  5010.5  372.39  5021.7  375.18  5064.1  378.45
  5078.3  379.29  5103.7  379.24  5205.5  377.57  5233.8  373.66  5248.0  375.11
  5262.1  377.85  5304.5  374.07  5318.7  374.80  5332.8  378.80  5347.0  384.18
  5361.1  386.83  5375.2  386.87  5389.4  384.66  5402.6  381.60  5408.8  381.60
#Mann=4,-1,0
  4673.2    0.16       0  5004.5    0.07       0  5010.5    0.16       0
  5103.7    0.12       0
Bank Sta=5004.5,5010.5
Exp/Cntr=0.3,0.1

Type RM Length L Ch R = 1,13959,1039,1039,1039
BEGIN DESCRIPTION:
OWENS CREEK 20.0
END DESCRIPTION:
XS GIS Cut Line= 3
      3515742.13     10473341.66      3514942.11     10472541.64
      3514603.89     10472215.57
#Sta/Elev= 30
  3868.6  395.59  3967.6  390.27  4349.5  376.75  4632.3  374.32  4646.4  373.30
  4729.2  375.26  4850.6  375.15  4859.5  375.26  4971.7  375.48  4985.9  372.04
  4993.5  368.69  4996.2  368.19  4999.5  368.69  5003.5  368.69  5028.2  376.10
  5056.5  372.69  5084.8  374.53  5134.4  389.82  5142.4  391.23  5155.5  389.81
  5176.9  382.87  5191.0  380.52  5205.2  379.94  5282.9  385.59  5318.4  386.27
  5396.1  391.39  5431.3  391.43  5459.6  394.05  5466.8  396.10  5469.8  394.63
#Mann=7,-1,0
  3868.6    0.05       0  4729.2    0.12       0  4850.6    0.05       0
  4859.5    0.16       0  4993.5    0.07       0  4999.5    0.16       0
  5142.4    0.16       0
Bank Sta=4993.5,4999.5
Exp/Cntr=0.3,0.1

Type RM Length L Ch R = 1,12920,1403,1403,1403
BEGIN DESCRIPTION:
OWENS CREEK 19.0
END DESCRIPTION:
XS GIS Cut Line= 3
      3516290.20     10472332.48      3515248.55     10471693.60
      3515116.87     10471645.09
#Sta/Elev= 30
  4183.5  392.84  4492.9  379.87  4627.0  375.81  4633.7  374.46  4639.6  375.07
  4697.6  372.50  4720.9  373.54  4734.4  375.36  4771.1  371.53  4784.3  372.83
  4823.2  371.42  4865.8  372.02  4887.1  368.29  4918.0  373.74  4967.2  373.57
  4976.0  372.51  4990.7  365.86  4994.3  365.50  4997.0  365.00  5000.3  365.50
  5025.9  370.88  5039.9  370.76  5061.2  373.36  5082.9  373.25  5134.6  373.13
  5263.5  378.85  5345.4  382.82  5376.2  385.56  5502.9  387.62  5545.8  387.23
#Mann=8,-1,0
  4183.5    0.05       0  4492.9    0.16       0  4784.3    0.12       0
  4994.3    0.07       0  5000.3    0.12       0  5082.9    0.05       0
  5263.5    0.16       0  5502.9     0.1       0
Bank Sta=4994.3,5000.3
Exp/Cntr=0.3,0.1

Type RM Length L Ch R = 1,11517,1181,1181,1181
BEGIN DESCRIPTION:
OWENS CREEK 17.0
END DESCRIPTION:
XS GIS Cut Line= 3
      3516192.08     10470641.67      3515792.11     10470991.64
      3514992.14     10471441.62
#Sta/Elev= 30
  4496.3  386.03  4730.2  370.44  4822.3  368.85  4855.0  369.54  4949.5  370.71
  4957.1  370.33  4963.7  367.11  4982.5  365.70  4985.3  365.20  4988.5  365.70
  4999.8  365.89  5006.4  369.45  5014.0  368.16  5022.7  369.46  5035.7  368.45
  5041.5  370.36  5059.9  370.26  5139.5  369.20  5246.9  368.88  5372.0  369.60
  5487.5  372.57  5505.5  377.00  5527.2  374.75  5543.1  374.79  5620.9  377.66
  5807.9  385.08  5865.3  387.26  5878.4  385.32  5916.0  386.36  5945.6  388.89
#Mann=11,-1,0
  4496.3    0.05       0  4855.0    0.12       0  4982.5    0.07       0
  4988.5    0.12       0  5022.7    0.05       0  5059.9    0.16       0
  5139.5    0.05       0  5246.9     0.1       0  5487.5    0.05       0
  5620.9     0.1       0  5807.9    0.05       0
Bank Sta=4982.5,4988.5
Exp/Cntr=0.3,0.1

Type RM Length L Ch R = 1,10336,1044,1044,1044
BEGIN DESCRIPTION:
OWENS CREEK 14.0
END DESCRIPTION:
XS GIS Cut Line= 2
      3516120.08     10470060.27      3514715.49     10470129.63
#Sta/Elev= 30
  4489.2  384.92  4597.3  385.49  4727.5  378.51  4777.5  374.25  4847.6  368.98
  4876.6  368.75  4977.8  368.21  4987.8  367.75  4994.8  365.58  4997.5  365.08
  5000.8  365.58  5017.8  366.46  5023.4  368.36  5053.8  367.53  5158.0  367.03
  5273.3  368.19  5348.2  367.29  5471.6  372.68  5538.4  376.42  5578.5  377.00
  5608.5  383.48  5618.5  381.04  5670.0  379.62  5728.7  376.98  5748.7  373.71
  5758.7  369.93  5778.7  376.10  5788.8  376.85  5868.3  377.72  5895.5  378.82
#Mann=10,-1,0
  4489.2    0.05       0  4777.5     0.1       0  4876.6    0.12       0
  4994.8    0.07       0  5000.8    0.12       0  5053.8    0.16       0
  5273.3    0.05       0  5471.6     0.1       0  5670.0    0.16       0
  5868.3    0.05       0
Bank Sta=4994.8,5000.8
Exp/Cntr=0.3,0.1

Type RM Length L Ch R = 1,9292,1356,1356,1356
BEGIN DESCRIPTION:
OWENS CREEK 13.0
END DESCRIPTION:
XS GIS Cut Line= 2
      3515955.12     10469582.83      3514201.66     10469096.72
#Sta/Elev= 30
  4654.2  381.90  4667.7  381.62  4688.5  378.80  4740.3  377.91  4844.1  369.19
  4890.4  367.28  4975.3  367.17  4996.8  365.59  4999.5  365.09  5002.8  365.59
  5053.7  366.32  5093.7  366.57  5113.9  368.55  5269.2  369.40  5315.0  367.78
  5536.2  369.88  5572.1  369.07  5685.3  367.20  5728.4  367.67  5746.9  365.66
  5784.2  368.06  5860.3  369.44  5875.9  369.35  5910.2  372.37  5944.1  372.79
  5996.0  378.36  6170.9  389.39  6272.4  393.07  6451.1  398.23  6473.8  399.01
#Mann=12,-1,0
  4654.2    0.16       0  4890.4    0.12       0  4996.8    0.07       0
  5002.8    0.12       0  5053.7    0.16       0  5269.2    0.05       0
  5572.1     0.1       0  5685.3    0.05       0  5784.2    0.16       0
  5860.3    0.05       0  6272.4    0.16       0  6451.1    0.05       0
Bank Sta=4996.8,5002.8
Exp/Cntr=0.3,0.1

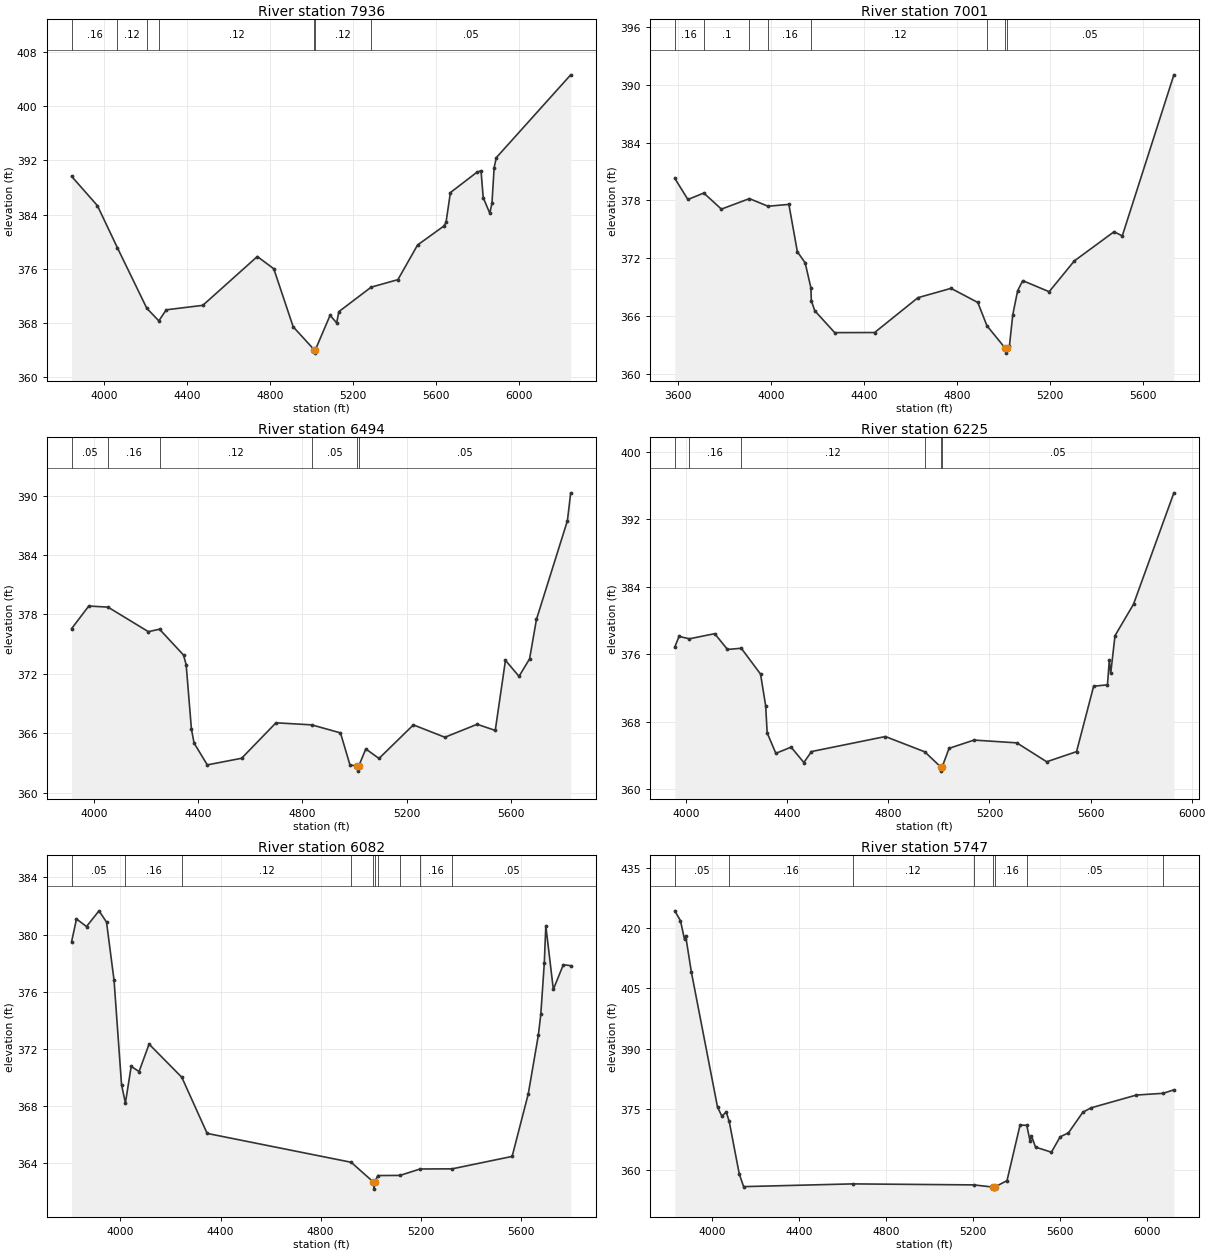
Type RM Length L Ch R = 1,7936,935,935,935
BEGIN DESCRIPTION:
OWENS CREEK 11.0
END DESCRIPTION:
XS GIS Cut Line= 3
      3516442.11     10468141.64      3515342.11     10468441.64
      3514142.10     10468841.64
#Sta/Elev= 30
  3844.1  389.65  3968.5  385.32  4065.1  379.09  4206.3  370.19  4264.4  368.33
  4300.2  369.96  4476.4  370.62  4739.0  377.82  4818.4  376.01  4911.7  367.46
  5012.9  364.07  5015.7  363.57  5018.9  364.07  5089.7  369.15  5121.3  368.03
  5131.9  369.69  5287.6  373.30  5416.5  374.41  5511.3  379.52  5637.8  382.31
  5648.4  382.85  5669.4  387.25  5795.9  390.22  5817.0  390.48  5827.6  386.51
  5859.2  384.21  5869.7  385.67  5880.3  390.94  5890.8  392.41  6249.2  404.62
#Mann=7,-1,0
  3844.1    0.16       0  4065.1    0.12       0  4206.3    0.16       0
  4264.4    0.12       0  5012.9    0.07       0  5018.9    0.12       0
  5287.6    0.05       0
Bank Sta=5012.9,5018.9
Exp/Cntr=0.3,0.1

Type RM Length L Ch R = 1,7001,507,507,507
BEGIN DESCRIPTION:
OWENS CREEK 9.0
END DESCRIPTION:
XS GIS Cut Line= 4
      3516116.79     10467402.12      3515550.62     10467264.06
      3514892.11     10467741.64      3514292.12     10468191.63
#Sta/Elev= 30
  3585.0  380.28  3641.3  378.08  3709.7  378.75  3785.4  377.08  3905.8  378.17
  3985.8  377.38  4075.6  377.57  4112.1  372.65  4145.6  371.50  4170.2  368.91
  4172.1  367.58  4186.8  366.53  4272.6  364.25  4444.3  364.26  4630.6  367.88
  4772.9  368.85  4888.1  367.38  4927.2  364.97  5006.3  362.62  5009.1  362.12
  5012.3  362.62  5023.9  362.85  5038.5  366.12  5059.3  368.60  5081.2  369.65
  5194.8  368.50  5303.1  371.70  5473.9  374.73  5509.3  374.30  5731.2  391.03
#Mann=8,-1,0
  3585.0    0.16       0  3709.7     0.1       0  3905.8    0.05       0
  3985.8    0.16       0  4170.2    0.12       0  4927.2    0.05       0
  5006.3    0.03       0  5012.3    0.05       0
Bank Sta=5006.3,5012.3
Exp/Cntr=0.3,0.1

Type RM Length L Ch R = 1,6494,269,269,269
BEGIN DESCRIPTION:
Mapping XS 92d46916
END DESCRIPTION:
XS GIS Cut Line= 3
      3515837.35     10467188.59      3515490.96     10467139.11
      3513946.50     10467409.17
#Sta/Elev= 30
  3913.1  376.57  3979.0  378.85  4052.9  378.74  4208.0  376.26  4250.9  376.51
  4343.1  373.90  4353.2  372.93  4373.5  366.42  4383.7  365.01  4434.4  362.81
  4566.4  363.48  4698.4  367.06  4836.1  366.85  4946.2  366.04  4982.6  362.81
  5010.1  362.68  5012.8  362.18  5016.1  362.68  5043.5  364.42  5094.3  363.46
  5226.3  366.85  5347.4  365.60  5471.4  366.91  5541.0  366.29  5580.2  373.37
  5632.3  371.75  5672.9  373.52  5699.2  377.49  5818.2  387.46  5830.9  390.28
#Mann=6,-1,0
  3913.1    0.05       0  4052.9    0.16       0  4250.9    0.12       0
  4836.1    0.05       0  5010.1   0.035       0  5016.1    0.05       0
Bank Sta=5010.1,5016.1
Exp/Cntr=0.3,0.1

Type RM Length L Ch R = 1,6225,143,143,143
BEGIN DESCRIPTION:
Mapping XS 2e6f8531
END DESCRIPTION:
XS GIS Cut Line= 3
      3515748.82     10467131.30      3514492.69     10466977.00
      3513856.03     10467287.94
#Sta/Elev= 30
  3955.6  376.88  3972.4  378.14  4013.0  377.85  4113.5  378.46  4163.9  376.59
  4218.6  376.73  4294.8  373.67  4315.0  369.92  4321.0  366.70  4355.3  364.28
  4415.7  365.01  4466.1  363.19  4496.3  364.49  4788.5  366.27  4944.3  364.46
  5007.2  362.67  5009.9  362.17  5013.2  362.67  5040.4  364.87  5139.1  365.85
  5308.4  365.52  5426.6  363.28  5544.7  364.48  5612.3  372.23  5667.0  372.40
  5674.3  375.30  5679.9  373.77  5696.8  378.22  5770.0  381.95  5929.7  395.15
#Mann=6,-1,0
  3955.6    0.05       0  4013.0    0.16       0  4218.6    0.12       0
  4944.3    0.05       0  5007.2    0.03       0  5013.2    0.05       0
Bank Sta=5007.2,5013.2
Exp/Cntr=0.3,0.1

Type RM Length L Ch R = 1,6082,335,335,335
BEGIN DESCRIPTION:
Mapping XS 5fef6047
END DESCRIPTION:
XS GIS Cut Line= 5
      3515881.60     10466980.25      3515536.19     10466989.39
      3514469.25     10466831.17      3514115.09     10466672.31
      3513932.78     10466682.73
#Sta/Elev= 30
  3804.8  379.51  3824.3  381.09  3864.3  380.56  3914.3  381.66  3944.3  380.87
  3974.4  376.80  4004.4  369.48  4019.8  368.21  4042.9  370.77  4074.4  370.41
  4114.4  372.33  4245.2  370.01  4346.5  366.08  4922.1  364.06  5010.8  362.68
  5013.5  362.18  5016.8  362.68  5028.6  363.13  5117.3  363.14  5197.8  363.59
  5325.9  363.60  5565.6  364.47  5630.1  368.85  5670.2  372.94  5680.2  374.42
  5694.1  377.99  5700.2  380.61  5730.3  376.16  5770.3  377.89  5799.7  377.82
#Mann=10,-1,0
  3804.8    0.05       0  4019.8    0.16       0  4245.2    0.12       0
  4922.1    0.05       0  5010.8    0.03       0  5016.8    0.05       0
  5028.6    0.16       0  5117.3    0.05       0  5197.8    0.16       0
  5325.9    0.05       0
Bank Sta=5010.8,5016.8
Exp/Cntr=0.3,0.1

Type RM Length L Ch R = 1,5747,779,779,779
BEGIN DESCRIPTION:
OWENS CREEK 7.0
END DESCRIPTION:
XS GIS Cut Line= 3
      3515908.33     10466525.75      3514274.75     10466556.00
      3513643.53     10466746.87
#Sta/Elev= 30
  3830.1  424.25  3856.3  421.79  3874.8  417.14  3879.8  418.09  3906.3  409.05
  4026.4  375.54  4046.4  373.29  4066.4  374.31  4080.0  372.01  4126.4  358.93
  4146.4  355.80  4646.7  356.48  5204.1  356.23  5293.6  355.68  5296.3  355.18
  5299.6  355.68  5356.6  357.29  5416.6  371.09  5447.4  371.01  5462.8  367.06
  5469.1  368.37  5487.6  365.61  5560.7  364.35  5600.8  368.16  5639.0  369.15
  5704.9  374.25  5743.1  375.36  5951.2  378.53  6073.7  378.96  6123.4  379.81
#Mann=8,-1,0
  3830.1    0.05       0  4080.0    0.16       0  4646.7    0.12       0
  5204.1    0.16       0  5293.6    0.07       0  5299.6    0.16       0
  5447.4    0.05       0  6073.7    0.16       0
Bank Sta=5293.6,5299.6
Exp/Cntr=0.3,0.1