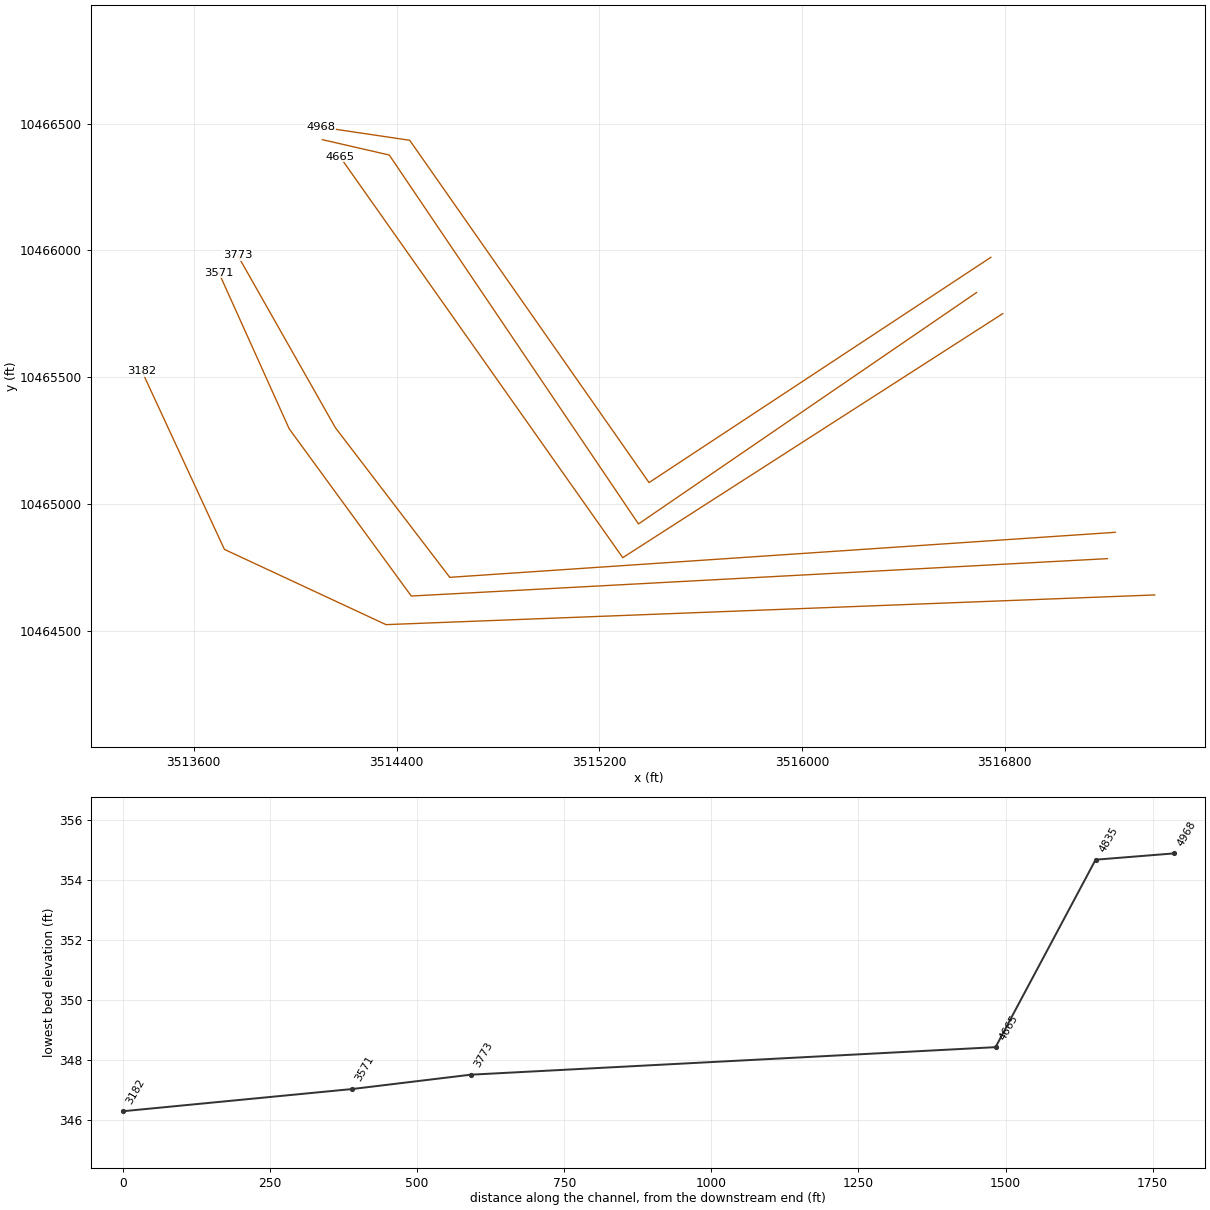
HEC-RAS study OWENS CREEK.prj: OWENS CREEK Base Level Engineering

--- OWENS CREEK.g01 (geometry) --- (continued)

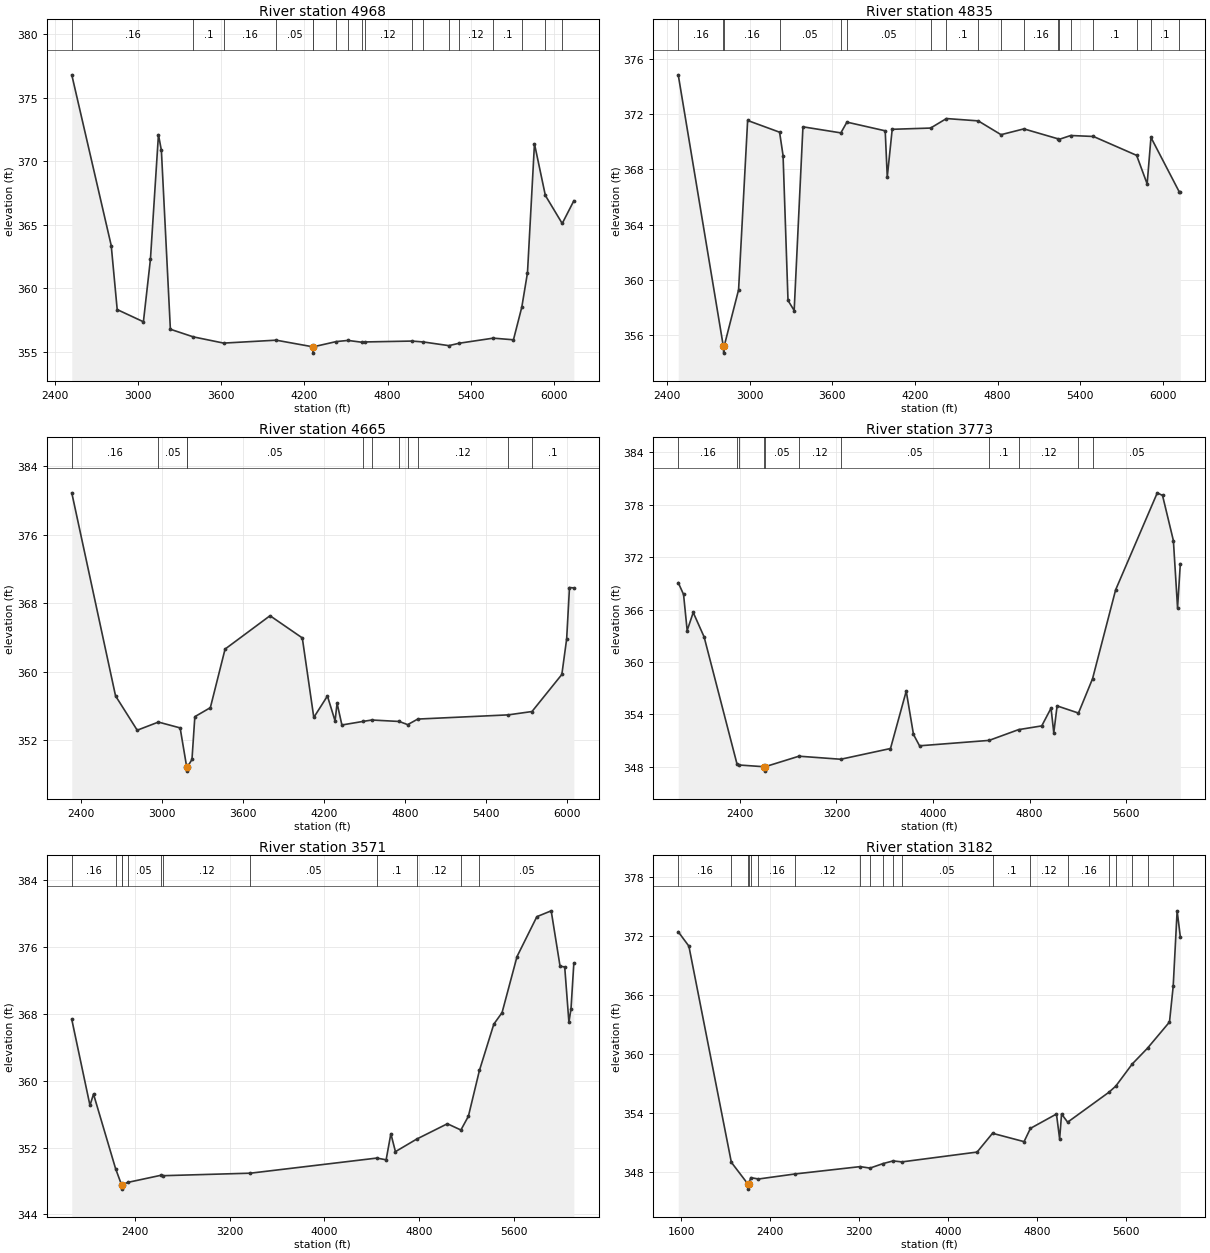
Type RM Length L Ch R = 1,4968,133,133,133
BEGIN DESCRIPTION:
OWENS CREEK 4.0
END DESCRIPTION:
XS GIS Cut Line= 4
      3516745.48     10465972.52      3515396.53     10465083.64
      3514452.09     10466434.34      3514101.35     10466486.43
#Sta/Elev= 30
  2524.2  376.81  2808.6  363.36  2851.6  358.32  3040.5  357.36  3091.1  362.28
  3148.9  372.10  3170.0  370.86  3234.8  356.77  3400.2  356.17  3618.6  355.68
  3997.1  355.91  4260.1  355.39  4262.9  354.89  4266.1  355.39  4430.5  355.80
  4514.4  355.89  4613.4  355.75  4634.1  355.77  4975.4  355.84  5057.6  355.77
  5241.6  355.48  5316.4  355.67  5561.6  356.07  5707.2  355.94  5767.3  358.51
  5808.3  361.22  5858.6  371.38  5937.1  367.31  6058.6  365.10  6142.4  366.89
#Mann=18,-1,0
  2524.2    0.16       0  3400.2     0.1       0  3618.6    0.16       0
  3997.1    0.05       0  4260.1    0.07       0  4266.1    0.05       0
  4430.5     0.1       0  4514.4    0.16       0  4613.4    0.05       0
  4634.1    0.12       0  4975.4    0.16       0  5057.6    0.12       0
  5241.6    0.16       0  5316.4    0.12       0  5561.6     0.1       0
  5767.3    0.16       0  5937.1     0.1       0  6058.6    0.05       0
Bank Sta=4260.1,4266.1
Exp/Cntr=0.3,0.1

Type RM Length L Ch R = 1,4835,170,170,170
BEGIN DESCRIPTION:
Mapping XS a2ea7c7c
END DESCRIPTION:
XS GIS Cut Line= 4
      3516689.08     10465833.65      3515354.87     10464920.45
      3514371.36     10466376.18      3514107.55     10466436.72
#Sta/Elev= 30
  2482.0  374.86  2809.3  355.18  2812.1  354.68  2815.3  355.18  2920.0  359.27
  2985.7  371.55  3217.6  370.70  3242.9  369.01  3278.8  358.50  3323.5  357.77
  3387.2  371.09  3662.4  370.65  3706.4  371.43  3984.3  370.80  3999.2  367.45
  4035.1  370.91  4313.6  371.00  4428.9  371.69  4659.6  371.52  4825.0  370.52
  4991.0  370.94  5235.2  370.23  5243.7  370.17  5330.8  370.46  5495.8  370.39
  5809.3  369.02  5885.6  366.95  5913.3  370.32  6120.3  366.34  6126.3  366.37
#Mann=18,-1,0
  2482.0    0.16       0  2809.3    0.07       0  2815.3    0.16       0
  3217.6    0.05       0  3662.4    0.16       0  3706.4    0.05       0
  4313.6    0.16       0  4428.9     0.1       0  4659.6    0.05       0
  4825.0    0.12       0  4991.0    0.16       0  5235.2    0.12       0
  5243.7    0.16       0  5330.8    0.12       0  5495.8     0.1       0
  5809.3    0.16       0  5913.3     0.1       0  6120.3    0.05       0
Bank Sta=2809.3,2815.3
Exp/Cntr=0.3,0.1

Type RM Length L Ch R = 1,4665,892,892,892
BEGIN DESCRIPTION:
Mapping XS 48af6aaa
END DESCRIPTION:
XS GIS Cut Line= 3
      3516792.39     10465750.32      3515292.80     10464787.42
      3514176.33     10466370.02
#Sta/Elev= 30
  2332.0  380.87  2656.3  357.19  2816.8  353.19  2973.6  354.14  3134.6  353.46
  3183.1  348.92  3185.9  348.42  3189.1  348.92  3222.4  349.78  3243.6  354.77
  3358.5  355.82  3467.5  362.65  3800.5  366.54  4039.6  363.95  4124.7  354.68
  4225.7  357.18  4282.3  354.27  4297.1  356.35  4332.8  353.80  4487.1  354.21
  4554.2  354.38  4757.9  354.21  4820.0  353.84  4894.8  354.49  5565.4  354.98
  5740.9  355.37  5962.0  359.69  5997.7  363.84  6018.6  369.83  6050.9  369.78
#Mann=11,-1,0
  2332.0    0.16       0  2973.6    0.05       0  3183.1    0.07       0
  3189.1    0.05       0  4487.1     0.1       0  4554.2    0.05       0
  4757.9    0.12       0  4820.0    0.05       0  4894.8    0.12       0
  5565.4    0.16       0  5740.9     0.1       0
Bank Sta=3183.1,3189.1
Exp/Cntr=0.3,0.1

Type RM Length L Ch R = 1,3773,202,202,202
BEGIN DESCRIPTION:
Mapping XS 8fb0aae0
END DESCRIPTION:
XS GIS Cut Line= 4
      3517235.96     10464887.46      3514610.22     10464709.80
      3514158.83     10465300.08      3513772.56     10465981.47
#Sta/Elev= 30
  1890.1  369.08  1934.1  367.74  1964.1  363.60  2014.2  365.67  2104.4  362.87
  2377.3  348.29  2396.0  348.20  2602.6  348.00  2605.3  347.50  2608.6  348.00
  2890.1  349.21  3236.0  348.86  3648.0  350.09  3778.3  356.66  3838.4  351.70
  3888.5  350.40  4464.8  351.02  4708.2  352.25  4900.6  352.68  4977.6  354.71
  5000.3  351.89  5027.7  354.97  5204.8  354.15  5321.3  358.08  5512.8  368.27
  5857.6  379.37  5900.9  379.07  5990.9  373.90  6025.4  366.19  6048.2  371.25
#Mann=11,-1,0
  1890.1    0.16       0  2377.3     0.1       0  2396.0    0.05       0
  2602.6    0.07       0  2608.6    0.05       0  2890.1    0.12       0
  3236.0    0.05       0  4464.8     0.1       0  4708.2    0.12       0
  5204.8    0.16       0  5321.3    0.05       0
Bank Sta=2602.6,2608.6
Exp/Cntr=0.3,0.1

Type RM Length L Ch R = 1,3571,389,389,389
BEGIN DESCRIPTION:
Mapping XS 33ec061d
END DESCRIPTION:
XS GIS Cut Line= 4
      3517205.67     10464783.58      3514458.31     10464636.01
      3513976.54     10465295.74      3513698.78     10465912.01
#Sta/Elev= 30
  1865.2  367.35  2019.0  357.05  2049.0  358.40  2235.2  349.49  2286.4  347.52
  2289.1  347.02  2292.4  347.52  2336.6  347.82  2616.4  348.67  2640.4  348.63
  3375.7  348.93  4444.4  350.74  4522.6  350.53  4562.6  353.66  4601.2  351.51
  4780.6  353.01  5040.4  354.85  5154.6  354.10  5218.0  355.75  5311.2  361.23
  5432.9  366.78  5502.6  368.16  5629.3  374.88  5796.7  379.65  5917.9  380.35
  5992.8  373.72  6032.2  373.63  6067.7  367.01  6085.4  368.62  6109.4  374.10
#Mann=12,-1,0
  1865.2    0.16       0  2235.2     0.1       0  2286.4    0.07       0
  2292.4     0.1       0  2336.6    0.05       0  2616.4    0.16       0
  2640.4    0.12       0  3375.7    0.05       0  4444.4     0.1       0
  4780.6    0.12       0  5154.6    0.16       0  5311.2    0.05       0
Bank Sta=2286.4,2292.4
Exp/Cntr=0.3,0.1

Type RM Length L Ch R = 1,3182,0,0,0
BEGIN DESCRIPTION:
OWENS CREEK 1.0
END DESCRIPTION:
XS GIS Cut Line= 4
      3517392.30     10464640.35      3514358.48     10464523.17
      3513720.87     10464820.02      3513395.36     10465523.11
#Sta/Elev= 30
  1572.6  372.46  1668.3  371.00  2050.1  349.01  2200.3  346.78  2203.0  346.28
  2206.3  346.78  2224.7  347.45  2294.2  347.31  2620.8  347.82  3208.5  348.57
  3296.8  348.42  3414.5  348.88  3504.9  349.15  3583.5  349.05  4259.7  350.05
  4398.3  351.96  4681.9  351.11  4739.2  352.46  4973.3  353.92  5001.8  351.38
  5019.0  353.92  5073.8  353.09  5446.8  356.15  5506.6  356.76  5654.6  359.01
  5792.0  360.62  5989.5  363.28  6022.8  366.91  6058.2  374.59  6086.8  371.96
#Mann=20,-1,0
  1572.6    0.16       0  2050.1     0.1       0  2200.3    0.07       0
  2206.3     0.1       0  2224.7    0.05       0  2294.2    0.16       0
  2620.8    0.12       0  3208.5    0.05       0  3296.8    0.12       0
  3414.5    0.05       0  3504.9    0.12       0  3583.5    0.05       0
  4398.3     0.1       0  4739.2    0.12       0  5073.8    0.16       0
  5446.8    0.05       0  5506.6    0.16       0  5654.6     0.1       0
  5792.0    0.05       0  6022.8     0.1       0
Bank Sta=2200.3,2206.3
Exp/Cntr=0.3,0.1

Chan Stop Cuts=-1