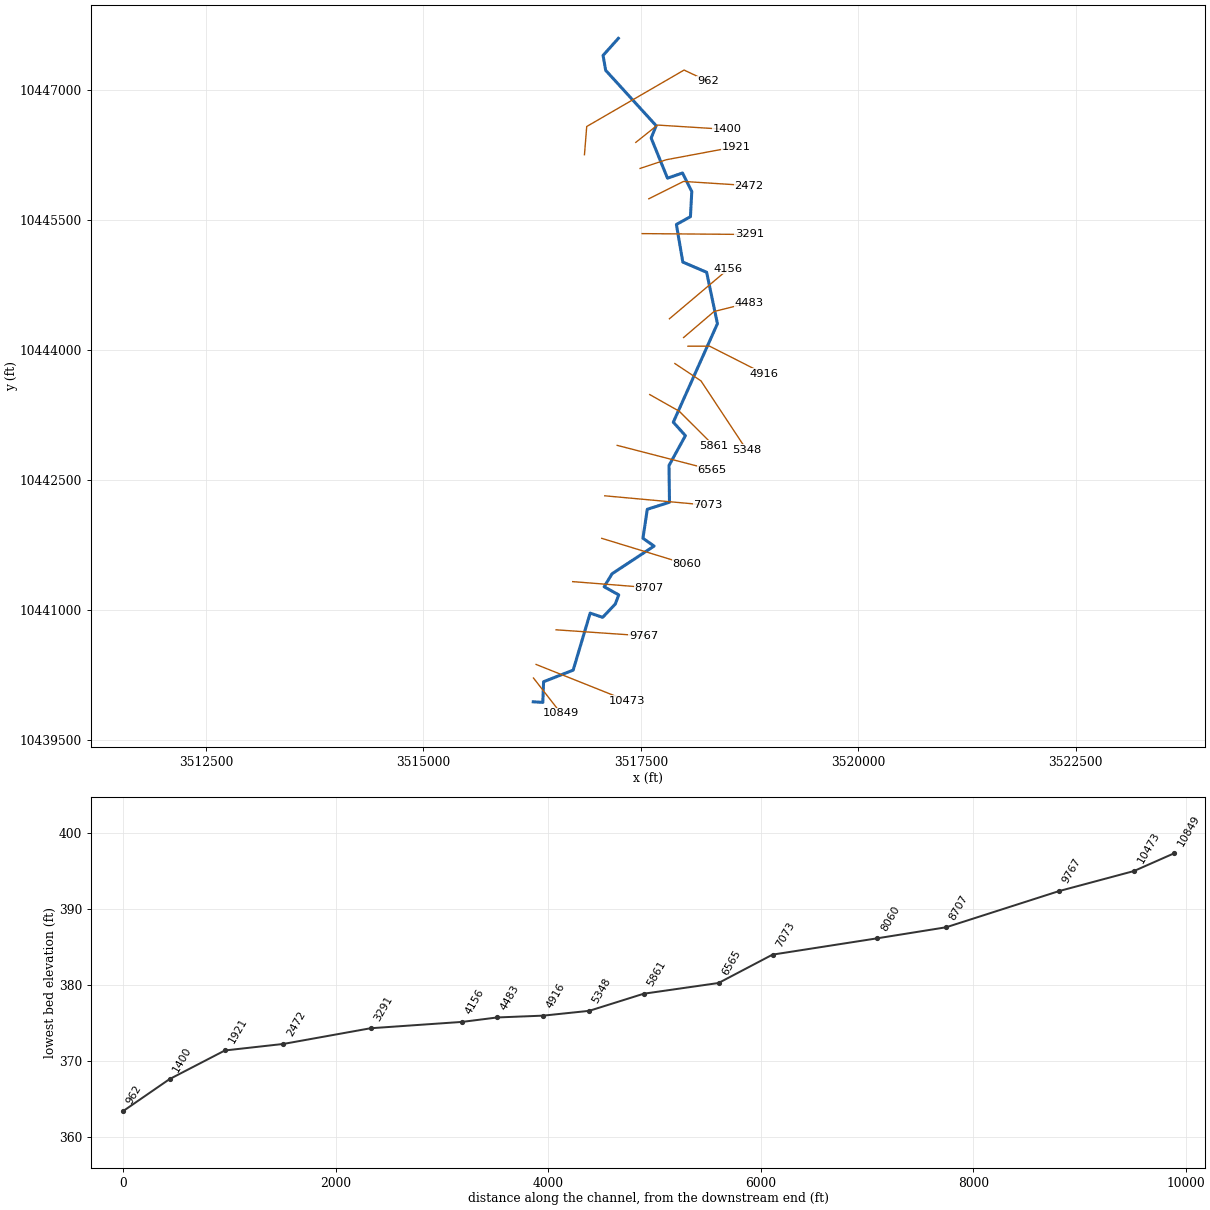
--- PIN OAK CREEK NORTH.prj (project) ---

Proj Title=PIN OAK CREEK NORTH Base Level Engineering
Current Plan=p01
Default Exp/Contr=0.3,0.1
English Units
Geom File=g01
Flow File=f01
Plan File=p01
Y Axis Title=Elevation
X Axis Title(PF)=Main Channel Distance
X Axis Title(XS)=Station
BEGIN DESCRIPTION:
PIN OAK CREEK NORTH
END DESCRIPTION:
DSS Export Rating Curves= 0
DSS Export Rating Curve Sorted= 0
DSS Export Volume Flow Curves= 0
DXF OffsetX= 0
DXF OffsetY= 0
DXF ScaleX= 1
DXF ScaleY= 10

--- PIN OAK CREEK NORTH.p01 (plan) ---

Plan Title=Multiple Run
Short Identifier=Multiple
Geom File=g01
Flow File=f01
Subcritical Flow
K Sum by GR= 0
Std Step Tol= 0.01
Critical Tol= 0.01
Num of Std Step Trials= 20
Max Error Tol= 0.3
Flow Tol Ratio= 0.001
Split Flow NTrial= 30
Split Flow Tol= 0.02
Split Flow Ratio= 0.02
Log Output Level= 0
Friction Slope Method= 1
Unsteady Friction Slope Method= 2
Unsteady Bridges Friction Slope Method= 1
Parabolic Critical Depth
Global Vel Dist=  1 , 1 , 1
Global Log Level= 0
CheckData=True
Encroach Param= -1, 0, 0, 0
BEGIN DESCRIPTION:
Multiple Run
END DESCRIPTION:

--- PIN OAK CREEK NORTH.f01 (steady flow) ---

Flow Title=Multiple
Program Version=4.10
Number of Profiles= 7
Profile Names=10-year,25-year,50-year,1pct_min,100-year,1pct_plu,500-year
River Rch & RM=PIN OAK CREEK NO,Reach-1         ,10849
     821    1115    1355    1201    1624    2197    2328
River Rch & RM=PIN OAK CREEK NO,Reach-1         ,5861
    1026    1408    1721    1534    2074    2805    3006
Boundary for River Rch & Prof#=PIN OAK CREEK NO,Reach-1         , 1
Up Type= 0
Dn Type= 3
Dn Slope=0.005
Boundary for River Rch & Prof#=PIN OAK CREEK NO,Reach-1         , 2
Up Type= 0
Dn Type= 3
Dn Slope=0.005
Boundary for River Rch & Prof#=PIN OAK CREEK NO,Reach-1         , 3
Up Type= 0
Dn Type= 3
Dn Slope=0.005
Boundary for River Rch & Prof#=PIN OAK CREEK NO,Reach-1         , 4
Up Type= 0
Dn Type= 3
Dn Slope=0.005
Boundary for River Rch & Prof#=PIN OAK CREEK NO,Reach-1         , 5
Up Type= 0
Dn Type= 3
Dn Slope=0.005
Boundary for River Rch & Prof#=PIN OAK CREEK NO,Reach-1         , 6
Up Type= 0
Dn Type= 3
Dn Slope=0.005
Boundary for River Rch & Prof#=PIN OAK CREEK NO,Reach-1         , 7
Up Type= 0
Dn Type= 3
Dn Slope=0.005
DSS Import GetInterval= 0
DSS Import GetPeak= 0
DSS Import FillOption= 0

--- PIN OAK CREEK NORTH.g01 (geometry) ---

Geom Title=Existing Conditions
Program Version=4.10

River Reach=PIN OAK CREEK NO,Reach-1
Reach XY= 30
      3516263.25     10439941.46      3516373.09     10439934.64
      3516381.81     10440172.93      3516722.14      10440306.5
      3516917.49     10440963.83      3517061.02     10440915.06
      3517206.73     10441068.83      3517246.26      10441174.5
       3517078.6     10441267.71      3517169.66     10441418.09
      3517652.72     10441737.08      3517524.65     10441826.89
      3517574.45     10442161.14      3517829.84     10442242.71
      3517824.19      10442665.9      3518012.88     10443010.02
       3517873.7     10443165.46      3518381.24     10444301.64
      3518256.97     10444894.14      3517983.01     10445011.89
      3517909.27     10445445.08      3518070.63     10445535.16
      3518086.25     10445825.52      3517979.48     10446039.06
      3517806.73     10445979.24      3517619.07      10446441.5
      3517676.56      10446584.2      3517095.74     10447223.15
      3517066.19     10447394.66      3517242.11     10447591.64

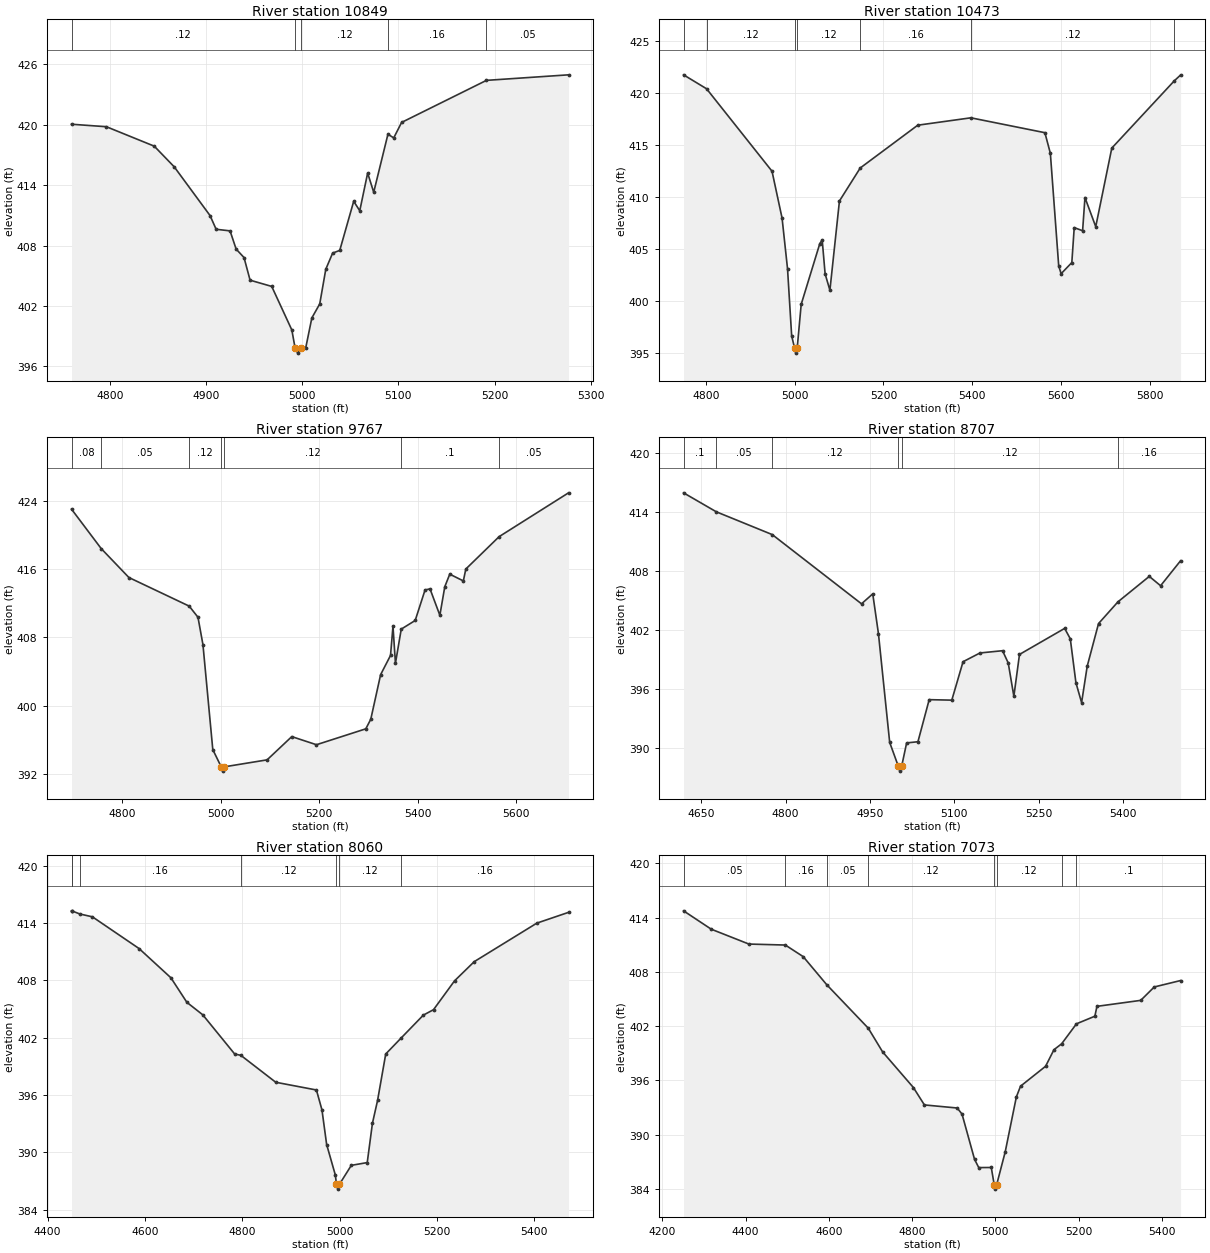
Type RM Length L Ch R = 1 ,10849   ,376,376,376
BEGIN DESCRIPTION:
PIN OAK CREEK NORTH 22.0
END DESCRIPTION:
XS GIS Cut Line= 2
      3516265.43       10440216.      3516582.29     10439807.98
#Sta/Elev= 30
  4760.3  420.06  4796.6  419.81  4846.3  417.88  4867.1  415.82  4904.3  410.98
  4910.6  409.62  4925.1  409.46  4931.4  407.65  4939.6  406.81  4945.9  404.56
  4968.4  403.94  4989.3  399.61  4992.7  397.81  4995.4  397.31  4998.7  397.81
  5003.8  397.86  5010.1  400.81  5018.3   402.2  5024.6  405.65  5031.7  407.25
  5039.1  407.52  5053.6   412.4  5059.9  411.46  5068.1  415.21  5074.4   413.3
  5089.2  419.07  5095.2   418.7  5103.4  420.24  5191.6  424.42  5276.9  424.97
#Mann= 5 ,-1 , 0
  4760.3     .12       0  4992.7     .07       0  4998.7     .12       0
  5089.2     .16       0  5191.6     .05       0
Bank Sta=4992.7,4998.7
XS Rating Curve= 0 ,0
Exp/Cntr=0.3,0.1

Type RM Length L Ch R = 1 ,10473   ,706,706,706
BEGIN DESCRIPTION:
PIN OAK CREEK NORTH 21.0
END DESCRIPTION:
XS GIS Cut Line= 2
      3516295.85     10440372.24      3517336.02     10439956.17
#Sta/Elev= 30
  4749.4  421.73  4801.3  420.39  4948.8  412.47  4971.5  407.96  4983.8  403.09
  4993.1  396.65  4999.6  395.49  5002.4  394.99  5005.6  395.49  5014.6  399.68
  5056.5  405.51  5061.9  405.87  5068.5  402.61  5079.3  401.03  5100.8  409.61
  5147.7  412.78  5277.3  416.89  5397.1   417.6  5563.9  416.17  5576.2  414.19
    5595  403.39  5600.4  402.62  5624.6  403.69    5630  407.05  5648.9  406.75
  5654.2  409.94  5678.5  407.14  5714.7  414.69  5855.7  421.16  5869.7  421.71
#Mann= 7 ,-1 , 0
  4749.4     .16       0  4801.3     .12       0  4999.6     .07       0
  5005.6     .12       0  5147.7     .16       0  5397.1     .12       0
  5855.7     .05       0
Bank Sta=4999.6,5005.6
XS Rating Curve= 0 ,0
Exp/Cntr=0.3,0.1

Type RM Length L Ch R = 1 ,9767    ,1060,1060,1060
BEGIN DESCRIPTION:
PIN OAK CREEK NORTH 20.0
END DESCRIPTION:
XS GIS Cut Line= 2
      3516525.87     10440771.56      3517532.78     10440702.12
#Sta/Elev= 30
  4696.8  423.01    4757   418.4  4813.3  415.01  4935.8  411.66  4953.6  410.36
  4963.7  407.15  4983.7  394.87  5000.8  392.85  5003.5  392.35  5006.8  392.85
    5094  393.67  5144.1  396.39  5194.2  395.44  5294.4   397.3  5304.5  398.42
  5324.5  403.64  5344.6  405.89  5349.6  409.31  5354.6  404.97  5366.4  408.97
  5394.7  409.98  5414.7  413.55  5424.8  413.68  5444.8  410.59  5454.8  413.93
  5464.9   415.4  5492.5  414.61  5497.5     416  5565.1  419.79  5706.1  424.92
#Mann= 7 ,-1 , 0
  4696.8     .08       0    4757     .05       0  4935.8     .12       0
  5000.8     .07       0  5006.8     .12       0  5366.4      .1       0
  5565.1     .05       0
Bank Sta=5000.8,5006.8
XS Rating Curve= 0 ,0
Exp/Cntr=0.3,0.1

Type RM Length L Ch R = 1 ,8707    ,647,647,647
BEGIN DESCRIPTION:
PIN OAK CREEK NORTH 18.0
END DESCRIPTION:
XS GIS Cut Line= 2
      3516716.82     10441327.12      3517597.49     10441257.71
#Sta/Elev= 30
  4618.7  415.91  4676.9  413.98  4776.4  411.66    4935  404.62    4955  405.63
  4965.1  401.59  4985.1  390.52  5000.4   388.1  5003.1   387.6  5006.4   388.1
  5015.2  390.47  5035.3  390.59  5055.3  394.87  5095.5  394.82  5115.5  398.73
  5145.6  399.62  5185.7  399.85  5195.8   398.6  5205.8  395.21  5215.8  399.47
  5296.1  402.12  5306.1  401.06  5316.1   396.6  5326.2  394.57  5336.2  398.28
  5356.3  402.61  5390.8  404.82  5446.5  407.41  5466.6  406.46  5502.1     409
#Mann= 6 ,-1 , 0
  4618.7      .1       0  4676.9     .05       0  4776.4     .12       0
  5000.4     .07       0  5006.4     .12       0  5390.8     .16       0
Bank Sta=5000.4,5006.4
XS Rating Curve= 0 ,0
Exp/Cntr=0.3,0.1

Type RM Length L Ch R = 1 ,8060    ,987,987,987
BEGIN DESCRIPTION:
PIN OAK CREEK NORTH 17.0
END DESCRIPTION:
XS GIS Cut Line= 2
      3517050.97     10441826.26       3518027.3     10441526.86
#Sta/Elev= 30
  4449.3  415.29  4449.7  415.29  4466.4  414.96  4492.3  414.66  4588.1  411.34
  4653.5  408.28  4686.3  405.71    4719   404.4  4784.5   400.3  4797.2  400.16
  4868.9  397.34  4952.5  396.53  4963.9  394.44  4973.5  390.82  4991.4  387.62
  4993.7  386.65  4996.4  386.15  4999.7  386.65  5024.2  388.64  5056.9  388.93
  5067.6  393.05  5078.1  395.43  5094.9   400.3  5126.5  401.97  5172.2  404.37
  5193.1  404.94  5236.3  407.96  5276.8  409.97  5405.3     414  5470.5  415.13
#Mann= 7 ,-1 , 0
  4449.3      .1       0  4449.7     .05       0  4466.4     .16       0
  4797.2     .12       0  4993.7     .07       0  4999.7     .12       0
  5126.5     .16       0
Bank Sta=4993.7,4999.7
XS Rating Curve= 0 ,0
Exp/Cntr=0.3,0.1

Type RM Length L Ch R = 1 ,7073    ,508,508,508
BEGIN DESCRIPTION:
PIN OAK CREEK NORTH 15.0
END DESCRIPTION:
XS GIS Cut Line= 2
      3517085.76      10442316.7      3518275.02     10442208.19
#Sta/Elev= 30
  4250.9  414.74  4317.5  412.71  4407.9  411.07  4495.5  410.96  4538.4  409.68
  4595.1  406.57  4694.7  401.78  4729.2  399.16  4803.2  395.22  4829.6   393.3
  4908.4  392.96    4920  392.29  4950.1  387.29  4960.2  386.38  4990.3  386.39
  4997.3   384.5  5000.1     384  5003.3   384.5  5023.7   388.1  5050.6  394.19
  5060.6  395.37  5120.8  397.57  5140.9   399.4  5159.3  400.05    5195  402.26
  5239.2   403.1  5244.2  404.19  5349.4  404.85  5381.9  406.33  5445.1  407.04
#Mann= 8 ,-1 , 0
  4250.9     .05       0  4495.5     .16       0  4595.1     .05       0
  4694.7     .12       0  4997.3     .07       0  5003.3     .12       0
  5159.3     .16       0    5195      .1       0
Bank Sta=4997.3,5003.3
XS Rating Curve= 0 ,0
Exp/Cntr=0.3,0.1

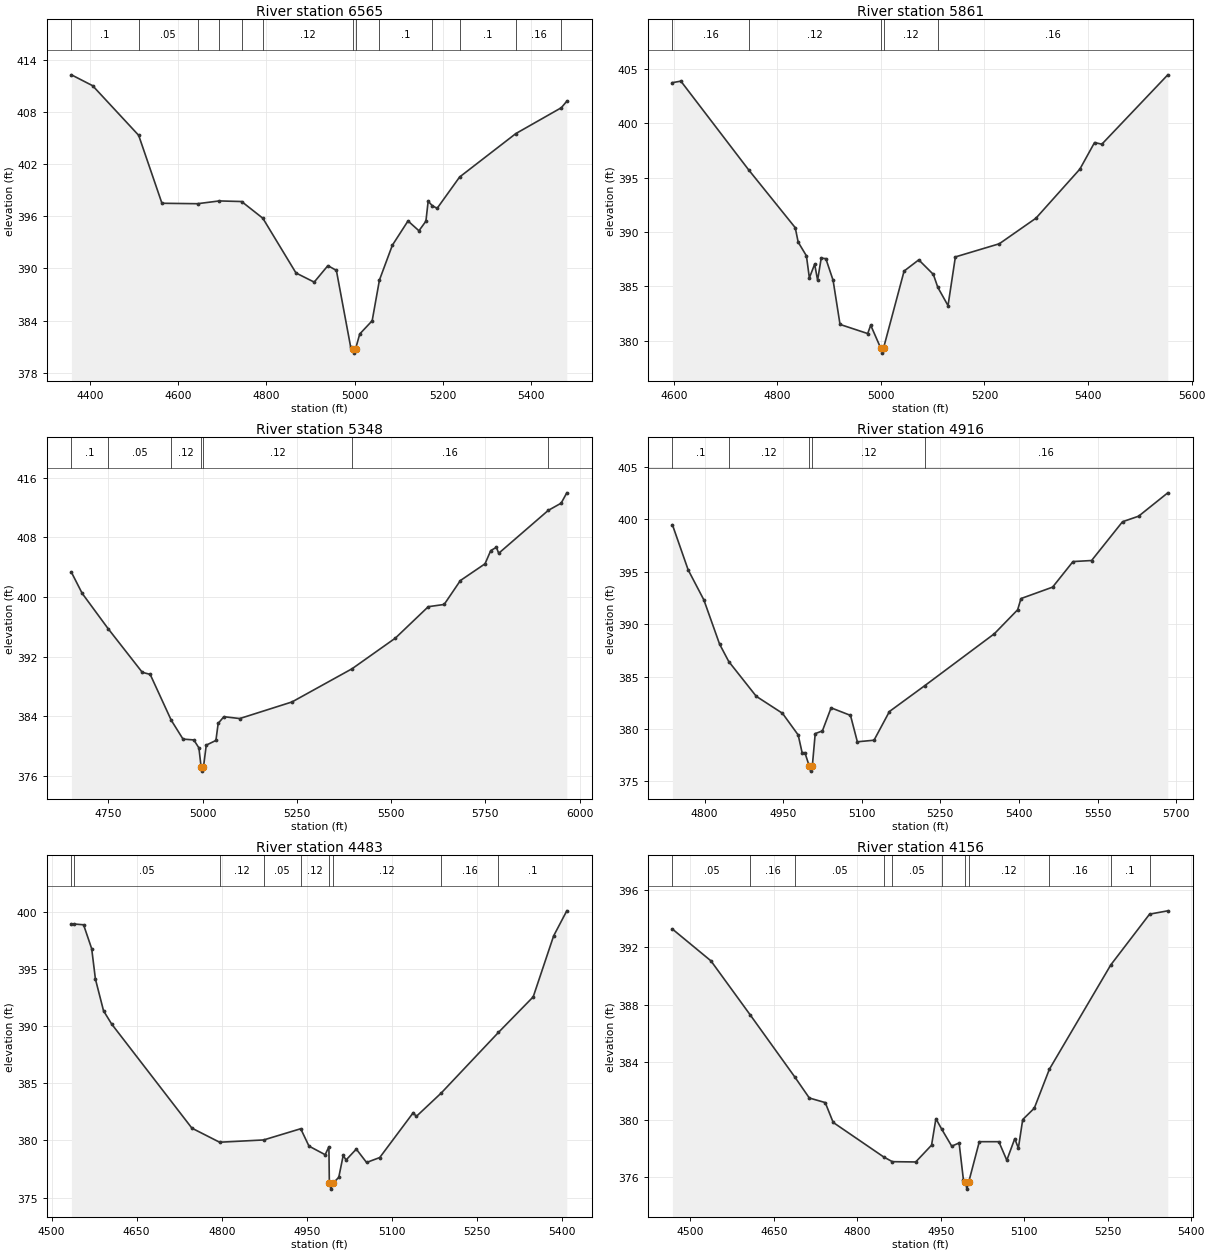
Type RM Length L Ch R = 1 ,6565    ,704,704,704
BEGIN DESCRIPTION:
PIN OAK CREEK NORTH 13.0
END DESCRIPTION:
XS GIS Cut Line= 2
      3517229.01     10442898.29      3518316.82     10442616.58
#Sta/Elev= 30
  4357.7  412.25  4405.8     411  4510.2   405.3    4563  397.49  4643.7  397.44
  4693.2  397.76  4743.8  397.69  4791.9  395.77  4867.1  389.48  4908.4  388.43
  4939.4  390.32  4958.7  389.78    4991  381.01  4996.3  380.77  4999.1  380.27
  5002.3  380.77  5011.7  382.47  5039.9  383.99  5056.4  388.67  5085.7  392.67
  5121.2  395.46    5146  394.33  5161.8  395.43  5166.9  397.72  5176.6   397.2
  5187.3  396.91  5238.3  400.51  5365.8   405.5    5469  408.47  5481.4  409.22
#Mann= 13 ,-1 , 0
  4357.7      .1       0  4510.2     .05       0  4643.7     .12       0
  4693.2     .05       0  4743.8     .16       0  4791.9     .12       0
  4996.3     .07       0  5002.3     .12       0  5056.4      .1       0
  5176.6     .12       0  5238.3      .1       0  5365.8     .16       0
    5469     .05       0
Bank Sta=4996.3,5002.3
XS Rating Curve= 0 ,0
Exp/Cntr=0.3,0.1

Type RM Length L Ch R = 1 ,5861    ,513,513,513
BEGIN DESCRIPTION:
PIN OAK CREEK NORTH 12.0
END DESCRIPTION:
XS GIS Cut Line= 3
      3517602.19     10443484.26      3517942.11     10443291.64
      3518342.12     10442891.63
#Sta/Elev= 30
  4597.5  403.74  4613.8  403.88  4744.5  395.73  4834.6   390.4  4840.3  389.07
  4856.2  387.81  4861.9  385.78  4872.1  387.04  4877.8  385.57  4884.8   387.6
  4893.7  387.55  4907.7  385.56  4921.1   381.5  4974.5  380.66  4980.3  381.43
  4999.3  379.36  5002.1  378.86  5005.3  379.36  5044.8  386.41  5073.1  387.44
  5101.3   386.1  5109.9  384.91  5129.6  383.23  5143.8  387.71  5228.6  388.92
  5299.3  391.27  5384.2  395.79  5412.5  398.23  5426.6  398.08  5553.9  404.46
#Mann= 5 ,-1 , 0
  4597.5     .16       0  4744.5     .12       0  4999.3     .07       0
  5005.3     .12       0  5109.9     .16       0
Bank Sta=4999.3,5005.3
XS Rating Curve= 0 ,0
Exp/Cntr=0.3,0.1

Type RM Length L Ch R = 1 ,5348    ,432,432,432
BEGIN DESCRIPTION:
PIN OAK CREEK NORTH 11.0
END DESCRIPTION:
XS GIS Cut Line= 3
      3517892.13     10443841.62      3518192.11     10443641.64
      3518716.67     10442846.02
#Sta/Elev= 30
  4652.3  403.31  4680.8  400.48  4749.3  395.76  4840.1  389.88  4861.1   389.6
    4917  383.44  4948.2  380.91  4976.8   380.8  4990.3  379.73  4996.3  377.11
    4999  376.61  5002.3  377.11  5009.8   380.1  5035.4  380.73  5041.4  383.02
  5056.5  383.92  5098.6  383.67  5237.2   385.9  5396.5  390.36  5511.2  394.47
  5598.5  398.69  5640.6  398.99  5683.6   402.2    5749  404.45  5764.1  406.22
  5779.2  406.67  5785.2  405.86  5916.6  411.62  5950.8  412.59  5965.8  413.98
#Mann= 7 ,-1 , 0
  4652.3      .1       0  4749.3     .05       0    4917     .12       0
  4996.3     .07       0  5002.3     .12       0  5396.5     .16       0
  5916.6     .05       0
Bank Sta=4996.3,5002.3
XS Rating Curve= 0 ,0
Exp/Cntr=0.3,0.1

Type RM Length L Ch R = 1 ,4916    ,433,433,433
BEGIN DESCRIPTION:
PIN OAK CREEK NORTH 10.0
END DESCRIPTION:
XS GIS Cut Line= 3
      3518042.06     10444041.64      3518292.11     10444041.64
      3518911.73     10443726.28
#Sta/Elev= 30
  4738.7  399.49  4768.7  395.19  4798.7  392.32  4828.7   388.1  4846.2  386.44
  4898.7  383.12  4948.7   381.5  4978.7  379.43  4986.2  377.74  4991.5  377.74
  4999.7  376.48  5002.4  375.98  5005.7  376.48  5011.2  379.56  5024.9  379.82
  5041.5  382.02  5078.5   381.3  5091.6  378.78  5123.4  378.93  5152.8  381.67
  5219.8  384.12    5353  389.09  5397.5  391.38  5403.9  392.45  5464.2  393.54
  5503.1  395.98  5538.6  396.08  5597.6  399.78  5628.3  400.31    5684  402.54
#Mann= 5 ,-1 , 0
  4738.7      .1       0  4846.2     .12       0  4999.7     .07       0
  5005.7     .12       0  5219.8     .16       0
Bank Sta=4999.7,5005.7
XS Rating Curve= 0 ,0
Exp/Cntr=0.3,0.1

Type RM Length L Ch R = 1 ,4483    ,327,327,327
BEGIN DESCRIPTION:
PIN OAK CREEK NORTH 9.0
END DESCRIPTION:
XS GIS Cut Line= 3
      3517992.08     10444141.62      3518342.11     10444441.64
      3518742.08     10444541.64
#Sta/Elev= 30
  4535.1  398.91  4539.1  398.92  4556.5  398.85  4570.8  396.76  4577.4   394.1
  4591.7  391.33  4605.9  390.18  4747.5  381.07  4796.3  379.84    4874  380.04
  4939.3  381.02  4953.9   379.5  4982.4  378.75    4989  379.44  4989.8  376.24
  4992.6  375.74  4995.8  376.24  5006.4  376.77  5014.2  378.68  5019.3  378.29
  5037.3  379.24  5055.4  378.07  5078.6   378.5  5137.8  382.43    5143  382.09
    5187  384.14  5287.9  389.44  5349.2  392.55  5385.2  397.88  5408.4  400.07
#Mann= 9 ,-1 , 0
  4535.1      .1       0  4539.1     .05       0  4796.3     .12       0
    4874     .05       0  4939.3     .12       0  4989.8     .07       0
  4995.8     .12       0    5187     .16       0  5287.9      .1       0
Bank Sta=4989.8,4995.8
XS Rating Curve= 0 ,0
Exp/Cntr=0.3,0.1

Type RM Length L Ch R = 1 ,4156    ,865,865,865
BEGIN DESCRIPTION:
PIN OAK CREEK NORTH 8.0
END DESCRIPTION:
XS GIS Cut Line= 2
      3517829.11     10444357.82      3518508.41     10444933.15
#Sta/Elev= 30
  4467.9  393.25  4537.1  391.04  4607.7  387.28  4688.2  382.94  4713.9   381.5
  4742.5  381.18  4756.8   379.8  4847.5   377.4  4863.1  377.07  4905.1  377.05
  4933.6  378.22  4941.4  380.06  4951.7  379.34  4969.8  378.15  4983.1  378.37
  4990.8  375.82  4994.4  375.66  4997.1  375.16  5000.4  375.66  5019.4  378.46
  5054.5  378.46  5068.8  377.17  5083.1  378.67  5089.6  378.01  5097.4     380
  5118.2  380.79  5145.3   383.5  5255.7  390.76  5325.4  394.29  5358.1  394.52
#Mann= 11 ,-1 , 0
  4467.9     .05       0  4607.7     .16       0  4688.2     .05       0
  4847.5     .12       0  4863.1     .05       0  4951.7     .12       0
  4994.4     .07       0  5000.4     .12       0  5145.3     .16       0
  5255.7      .1       0  5325.4     .16       0
Bank Sta=4994.4,5000.4
XS Rating Curve= 0 ,0
Exp/Cntr=0.3,0.1

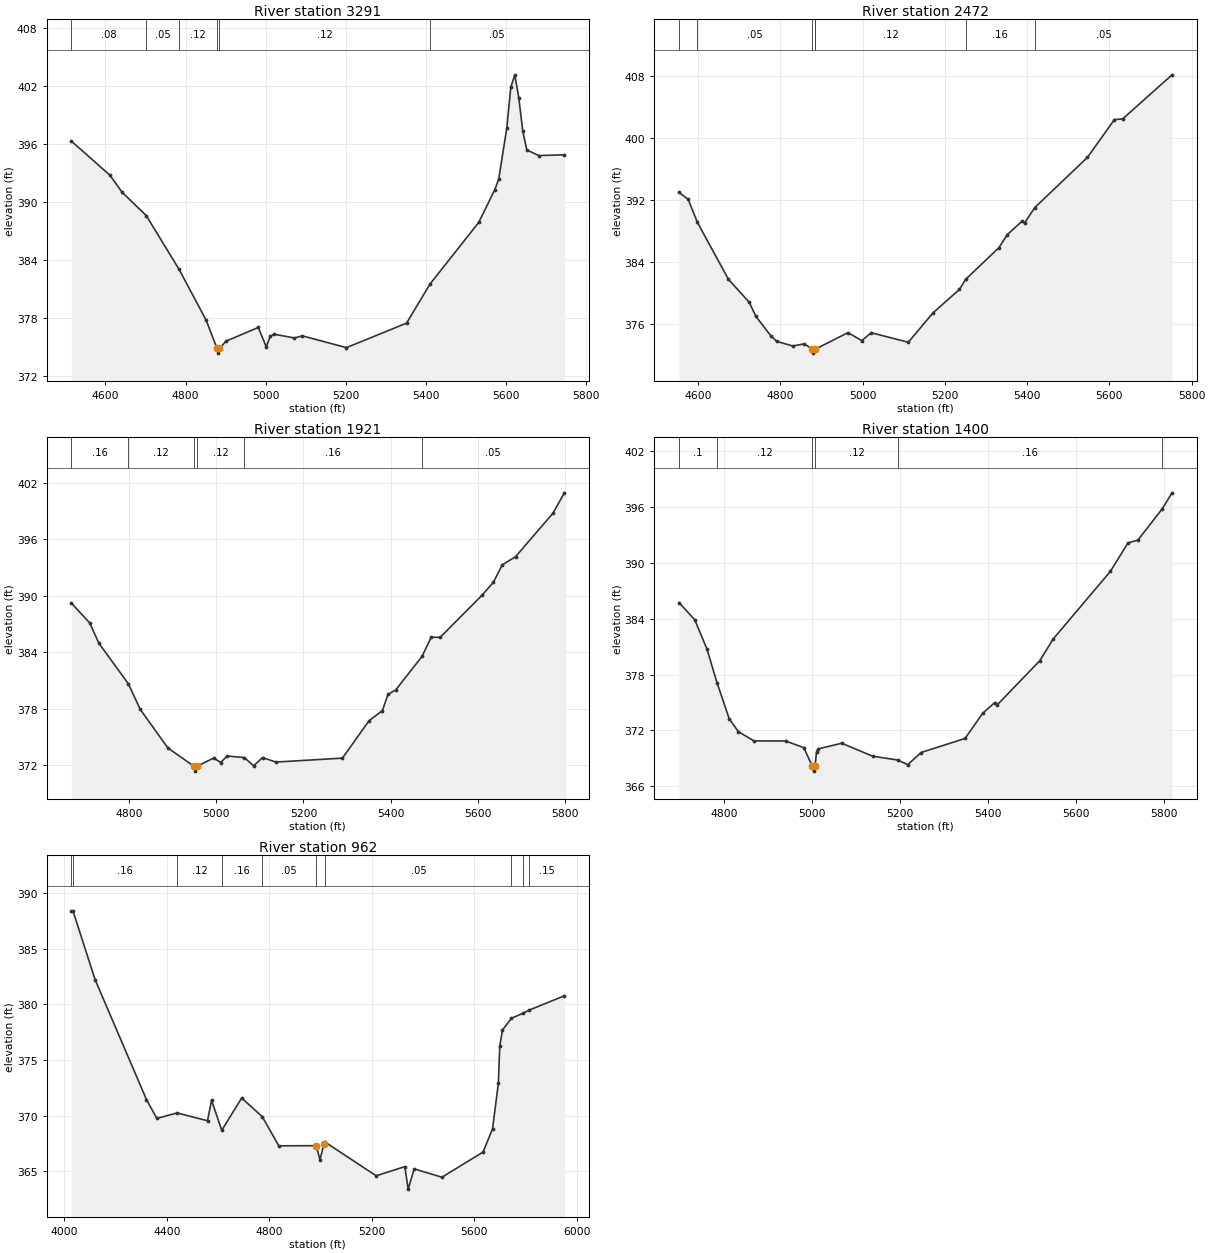
Type RM Length L Ch R = 1 ,3291    ,819,819,819
BEGIN DESCRIPTION:
PIN OAK CREEK NORTH 6.0
END DESCRIPTION:
XS GIS Cut Line= 2
      3517515.72     10445340.05      3518745.78     10445330.07
#Sta/Elev= 30
    4515   396.3  4611.4  392.76  4641.4  391.01  4702.1  388.57    4784  382.99
  4851.4  377.73  4878.4  374.82  4881.1  374.32  4884.4  374.82  4901.4  375.57
  4981.4  376.98  5001.4  374.96  5011.4  376.09  5021.4  376.28  5071.4  375.89
  5091.4  376.11  5201.4  374.89  5351.4  377.43    5410  381.49  5531.4  387.87
  5571.4  391.25  5581.4  392.38  5601.4  397.64  5611.4  401.88  5621.4  403.17
  5631.4  400.78  5641.4  397.31  5651.4  395.38  5681.4   394.8  5745.1  394.88
#Mann= 6 ,-1 , 0
    4515     .08       0  4702.1     .05       0    4784     .12       0
  4878.4     .07       0  4884.4     .12       0    5410     .05       0
Bank Sta=4878.4,4884.4
XS Rating Curve= 0 ,0
Exp/Cntr=0.3,0.1

Type RM Length L Ch R = 1 ,2472    ,551,551,551
BEGIN DESCRIPTION:
PIN OAK CREEK NORTH 5.0
END DESCRIPTION:
XS GIS Cut Line= 3
      3517592.13     10445741.66      3517992.11     10445941.64
      3518741.87     10445893.44
#Sta/Elev= 30
  4553.8  392.97  4576.1  392.08  4598.5  389.12    4674  381.77  4724.3  378.83
    4741  376.98  4777.4  374.47  4791.4  373.77  4830.5  373.18  4858.4  373.46
  4877.8  372.76  4880.5  372.26  4883.8  372.76  4885.4  372.77  4964.6   374.9
  4998.2  373.87    5021  374.89  5111.2  373.66  5171.3  377.45  5235.6  380.47
  5250.5  381.76  5331.7  385.86  5351.7  387.52  5388.7  389.31  5393.7  389.02
  5418.6  391.01  5546.8  397.49  5612.2  402.35  5632.3  402.44  5752.3  408.12
#Mann= 7 ,-1 , 0
  4553.8      .1       0  4598.5     .05       0  4877.8     .07       0
  4883.8     .05       0  4885.4     .12       0  5250.5     .16       0
  5418.6     .05       0
Bank Sta=4877.8,4883.8
XS Rating Curve= 0 ,0
Exp/Cntr=0.3,0.1

Type RM Length L Ch R = 1 ,1921    ,521,521,521
BEGIN DESCRIPTION:
PIN OAK CREEK NORTH 4.0
END DESCRIPTION:
XS GIS Cut Line= 3
      3517492.14     10446091.65      3517792.11     10446191.64
      3518592.07     10446341.64
#Sta/Elev= 30
    4668  389.22  4710.1  387.12  4731.2  384.96  4798.5  380.68  4826.1  377.94
  4889.3  373.86  4949.6   371.9  4952.3   371.4  4955.6   371.9  4994.4  372.79
  5010.5  372.31  5024.9     373  5064.6  372.84  5085.9  371.96  5106.3  372.84
  5136.8  372.36  5289.4  372.78  5350.5  376.75    5381  377.82  5393.7  379.53
  5411.5  380.01  5471.9  383.57  5492.9  385.61  5513.3  385.58  5609.1  390.04
  5635.3  391.42  5655.7  393.27  5686.2  394.14  5771.9  398.75  5798.1  400.91
#Mann= 6 ,-1 , 0
    4668     .16       0  4798.5     .12       0  4949.6     .07       0
  4955.6     .12       0  5064.6     .16       0  5471.9     .05       0
Bank Sta=4949.6,4955.6
XS Rating Curve= 0 ,0
Exp/Cntr=0.3,0.1

Type RM Length L Ch R = 1 ,1400    ,438,438,438
BEGIN DESCRIPTION:
PIN OAK CREEK NORTH 3.0
END DESCRIPTION:
XS GIS Cut Line= 3
      3517442.14     10446391.67      3517692.11     10446591.64
      3518492.14     10446541.64
#Sta/Elev= 30
  4697.6  385.75  4733.6  383.89  4761.6  380.71  4784.1  377.13    4812  373.25
  4832.8  371.87    4868  370.88  4940.1  370.87  4981.7  370.15  5001.1  368.13
  5003.9  367.63  5007.1  368.13  5010.5  369.69  5014.5  370.02  5067.8  370.63
  5137.9  369.24  5195.4  368.82  5218.1  368.32  5248.2  369.63  5348.4  371.14
  5388.4  373.84    5416     375    5421  374.72  5518.7  379.51  5548.7  381.82
    5679   389.1  5719.1  392.16  5741.6  392.46  5797.2  395.83  5819.3  397.54
#Mann= 6 ,-1 , 0
  4697.6      .1       0  4784.1     .12       0  5001.1     .07       0
  5007.1     .12       0  5195.4     .16       0  5797.2     .05       0
Bank Sta=5001.1,5007.1
XS Rating Curve= 0 ,0
Exp/Cntr=0.3,0.1

Type RM Length L Ch R = 1 ,962     ,0,0,0
BEGIN DESCRIPTION:
PIN OAK CREEK NORTH 1.0
END DESCRIPTION:
XS GIS Cut Line= 4
      3516851.97     10446249.37      3516878.01     10446574.86
       3517997.8      10447225.9      3518270.26     10447096.16
#Sta/Elev= 30
  4027.8  388.34  4034.2   388.4  4120.4  382.23    4321  371.45  4361.4  369.76
  4440.2  370.25  4559.2  369.55  4574.9  371.39  4614.7  368.69  4692.4  371.59
  4772.7  369.92  4837.2   367.3  4983.7  367.31  4997.8  366.03  5013.5  367.48
  5019.3  367.61  5217.1  364.61  5328.9  365.43    5342  363.41  5365.4  365.23
  5473.7  364.48  5634.2  366.74  5671.1  368.82  5693.8   372.9  5699.3  376.26
  5709.8  377.69  5744.7  378.75    5790   379.2  5812.3  379.47  5951.4  380.77
#Mann= 10 ,-1 , 0
  4027.8      .1       0  4034.2     .16       0  4440.2     .12       0
  4614.7     .16       0  4772.7     .05       0  4983.7     .03       0
  5019.3     .05       0  5744.7     .15       0    5790     .08       0
  5812.3     .15       0
Bank Sta=4983.7,5013.5
XS Rating Curve= 0 ,0
Exp/Cntr=0.3,0.1

Chan Stop Cuts=-1
Use User Specified Reach Order=0
Composite Channel Slope=5