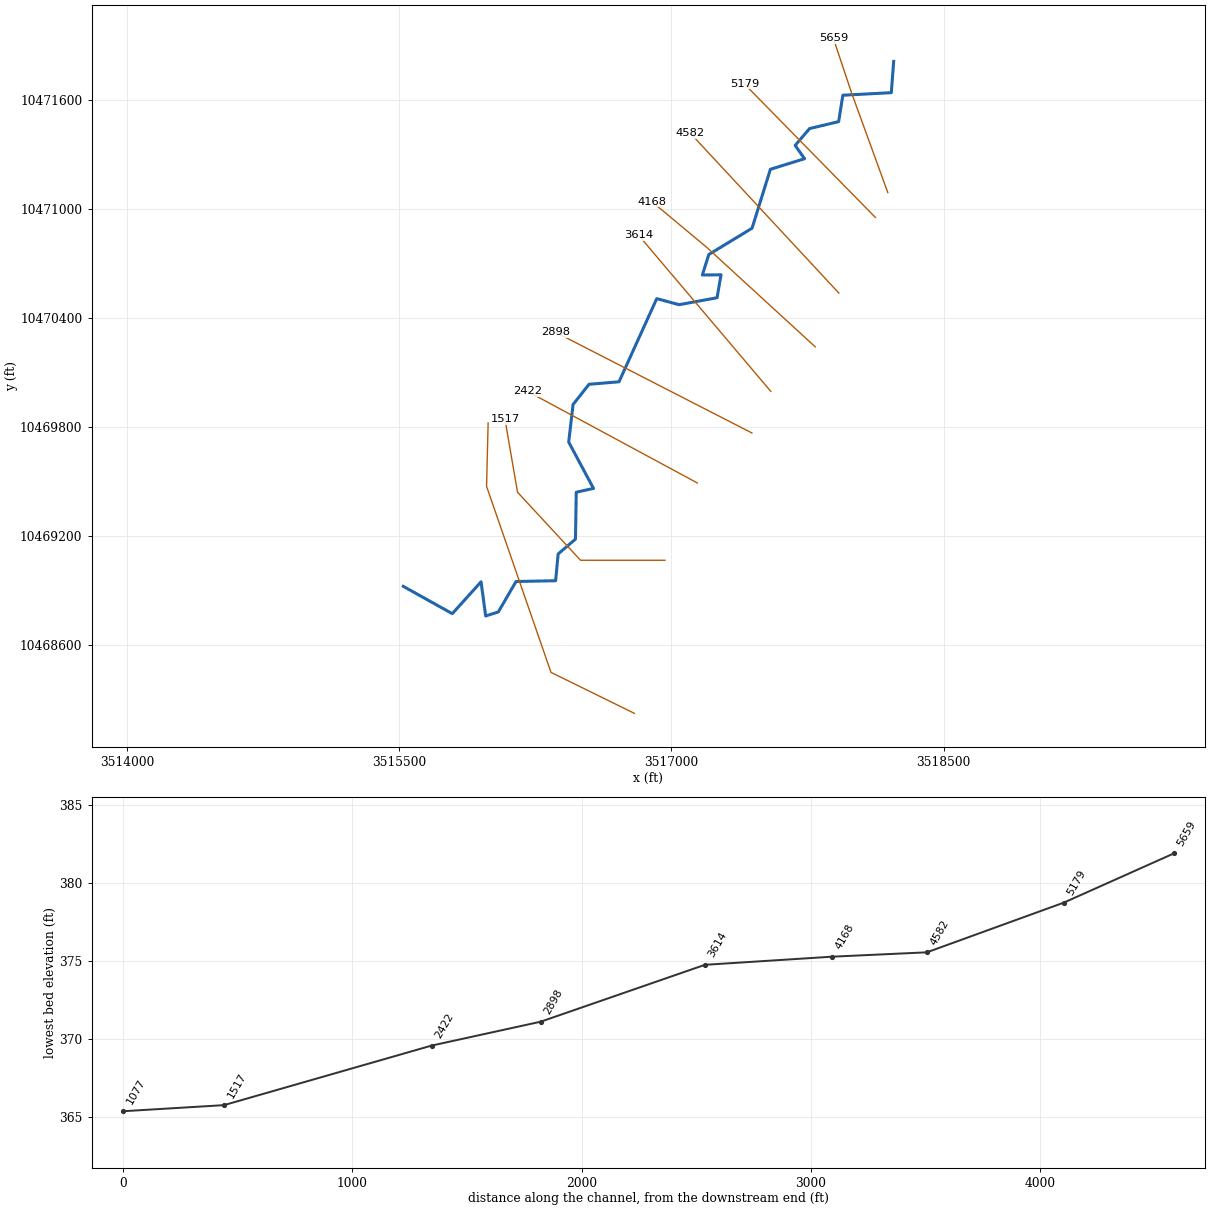
--- POLE CAT CREEK.prj (project) ---

Proj Title=POLE CAT CREEK Base Level Engineering
Current Plan=p01
Default Exp/Contr=0.3,0.1
English Units
Geom File=g01
Flow File=f01
Plan File=p01
BEGIN DESCRIPTION:
POLE CAT CREEK
END DESCRIPTION:

--- POLE CAT CREEK.p01 (plan) ---

Plan Title=Multiple Run
Short Identifier=Multiple
Geom File=g01
Flow File=f01
Subcritical Flow
K Sum by GR= 0
Std Step Tol= 0.01
Critical Tol= 0.01
Num of Std Step Trials= 20
Max Error Tol= 0.3
Flow Tol Ratio= 0.001
Split Flow NTrial= 30
Split Flow Tol= 0.02
Split Flow Ratio= 0.02
Log Output Level= 0
Friction Slope Method= 1
Unsteady Friction Slope Method= 2
Unsteady Bridges Friction Slope Method= 1
Parabolic Critical Depth
Global Vel Dist=  1 , 1 , 1
Global Log Level= 0
CheckData=True
Encroach Param= -1, 0, 0, 0
BEGIN DESCRIPTION:
Multiple Run
END DESCRIPTION:

--- POLE CAT CREEK.f01 (steady flow) ---

Flow Title=Multiple
Number of Profiles=7
Profile Names=10-year,25-year,50-year,1pct_min,100-year,1pct_plu,500-year
River Rch & RM= POLE CAT CREEK,Reach-1,5659
     948    1296    1580    1406    1901    2571    2744
Boundary for River Rch & Prof#=POLE CAT CREEK,Reach-1,1
Up Type=0
Dn Type=3
Dn Slope=0.005
Boundary for River Rch & Prof#=POLE CAT CREEK,Reach-1,2
Up Type=0
Dn Type=3
Dn Slope=0.005
Boundary for River Rch & Prof#=POLE CAT CREEK,Reach-1,3
Up Type=0
Dn Type=3
Dn Slope=0.005
Boundary for River Rch & Prof#=POLE CAT CREEK,Reach-1,4
Up Type=0
Dn Type=3
Dn Slope=0.005
Boundary for River Rch & Prof#=POLE CAT CREEK,Reach-1,5
Up Type=0
Dn Type=3
Dn Slope=0.005
Boundary for River Rch & Prof#=POLE CAT CREEK,Reach-1,6
Up Type=0
Dn Type=3
Dn Slope=0.005
Boundary for River Rch & Prof#=POLE CAT CREEK,Reach-1,7
Up Type=0
Dn Type=3
Dn Slope=0.005

--- POLE CAT CREEK.g01 (geometry) ---

Geom Title=Existing Conditions

River Reach=POLE CAT CREEK,Reach-1
Reach XY= 30
      3518224.39     10471814.35      3518211.37     10471642.19
      3517944.37     10471628.05      3517921.22     10471482.54
      3517760.93     10471444.36      3517681.60     10471351.46
      3517733.31     10471278.32      3517544.98     10471219.87
      3517444.02     10470895.18      3517205.73     10470750.44
      3517170.03     10470637.35      3517272.89     10470638.51
      3517251.27     10470512.14      3517041.66     10470473.75
      3516918.85     10470507.21      3516710.77     10470048.83
      3516545.72     10470035.29      3516457.80     10469923.84
      3516433.51     10469716.93      3516570.19     10469461.36
      3516475.29     10469440.37      3516470.93     10469181.84
      3516375.48     10469100.28      3516361.55     10468952.62
      3516143.37     10468948.36      3516045.63     10468780.57
      3515975.95     10468758.41      3515950.73     10468946.80
      3515792.11     10468771.23      3515522.11     10468921.64

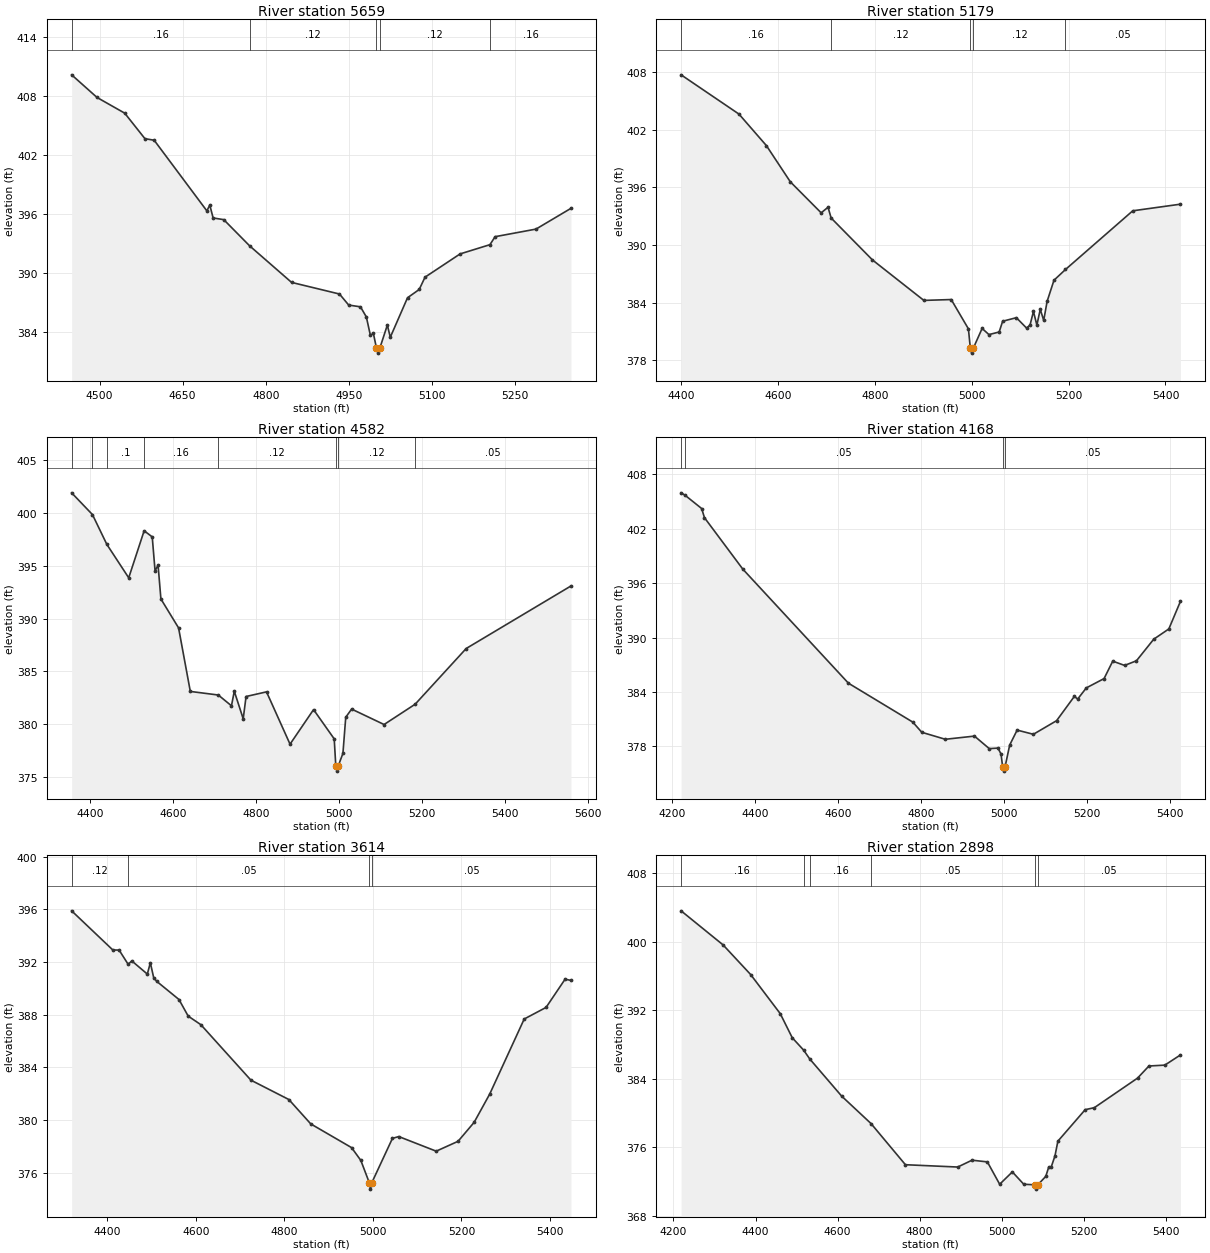
Type RM Length L Ch R = 1,5659,480,480,480
BEGIN DESCRIPTION:
POLE CAT CREEK 9.0
END DESCRIPTION:
XS GIS Cut Line= 3
      3518192.10     10471091.66      3517992.11     10471641.64
      3517892.12     10471941.60
#Sta/Elev= 30
  4449.7  410.14  4495.6  407.84  4545.5  406.25  4582.0  403.66  4598.7  403.50
  4693.8  396.33  4699.1  396.92  4705.1  395.61  4724.3  395.44  4771.0  392.78
  4846.7  389.07  4933.2  387.89  4949.8  386.77  4971.1  386.59  4981.7  385.56
  4989.0  383.69  4994.4  383.89  5000.0  382.39  5002.7  381.89  5006.0  382.39
  5019.6  384.74  5024.9  383.50  5056.0  387.51  5077.1  388.35  5087.6  389.60
  5150.9  391.96  5204.8  392.90  5214.1  393.71  5287.9  394.48  5351.1  396.59
#Mann=5,-1,0
  4449.7    0.16       0  4771.0    0.12       0  5000.0    0.07       0
  5006.0    0.12       0  5204.8    0.16       0
Bank Sta=5000,5006
Exp/Cntr=0.3,0.1

Type RM Length L Ch R = 1,5179,597,597,597
BEGIN DESCRIPTION:
POLE CAT CREEK 8.0
END DESCRIPTION:
XS GIS Cut Line= 2
      3518123.86     10470954.32      3517401.60     10471690.47
#Sta/Elev= 30
  4399.7  407.72  4519.3  403.63  4575.9  400.35  4625.3  396.58  4689.0  393.35
  4703.2  393.93  4709.6  392.81  4795.0  388.44  4901.1  384.23  4957.6  384.32
  4993.1  381.27  4997.1  379.24  4999.8  378.74  5003.1  379.24  5021.4  381.31
  5035.5  380.67  5056.6  380.94  5063.8  382.06  5092.1  382.43  5113.2  381.35
  5120.4  381.67  5127.4  383.08  5134.5  381.66  5141.5  383.30  5148.6  382.15
  5155.7  384.14  5169.8  386.33  5193.6  387.45  5332.5  393.56  5431.0  394.25
#Mann=5,-1,0
  4399.7    0.16       0  4709.6    0.12       0  4997.1    0.07       0
  5003.1    0.12       0  5193.6    0.05       0
Bank Sta=4997.1,5003.1
Exp/Cntr=0.3,0.1

Type RM Length L Ch R = 1,4582,414,414,414
BEGIN DESCRIPTION:
POLE CAT CREEK 7.0
END DESCRIPTION:
XS GIS Cut Line= 2
      3517922.44     10470537.69      3517103.05     10471419.58
#Sta/Elev= 30
  4354.8  401.89  4405.0  399.83  4439.7  397.01  4492.4  393.85  4529.6  398.30
  4549.1  397.72  4555.9  394.51  4563.2  395.04  4570.0  391.85  4612.6  389.11
  4640.9  383.10  4708.4  382.76  4740.1  381.74  4746.9  383.12  4768.4  380.51
  4775.3  382.62  4824.6  383.06  4881.3  378.11  4938.0  381.38  4987.8  378.61
  4991.6  376.06  4994.4  375.56  4997.6  376.06  5008.8  377.24  5015.6  380.66
  5029.8  381.43  5108.0  379.97  5182.9  381.89  5305.9  387.16  5558.6  393.08
#Mann=8,-1,0
  4354.8     0.1       0  4405.0    0.05       0  4439.7     0.1       0
  4529.6    0.16       0  4708.4    0.12       0  4991.6    0.07       0
  4997.6    0.12       0  5182.9    0.05       0
Bank Sta=4991.6,4997.6
Exp/Cntr=0.3,0.1

Type RM Length L Ch R = 1,4168,554,554,554
BEGIN DESCRIPTION:
POLE CAT CREEK 6.0
END DESCRIPTION:
XS GIS Cut Line= 3
      3517792.09     10470241.66      3517192.11     10470791.64
      3516892.13     10471041.62
#Sta/Elev= 30
  4221.0  405.95  4230.4  405.69  4270.6  404.22  4277.4  403.21  4369.9  397.54
  4624.6  384.97  4779.9  380.68  4801.5  379.56  4858.3  378.79  4928.6  379.14
  4964.3  377.76  4985.3  377.82  4992.7  377.16  4996.5  375.78  4999.2  375.28
  5002.5  375.78  5013.6  378.16  5031.5  379.80  5070.7  379.34  5126.7  380.84
  5169.6  383.52  5177.5  383.22  5198.3  384.45  5241.2  385.48  5262.1  387.40
  5290.7  386.93  5319.3  387.44  5361.0  389.82  5397.4  390.95  5425.4  393.99
#Mann=4,-1,0
  4221.0    0.16       0  4230.4    0.05       0  4996.5   0.035       0
  5002.5    0.05       0
Bank Sta=4996.5,5002.5
Exp/Cntr=0.3,0.1

Type RM Length L Ch R = 1,3614,716,716,716
BEGIN DESCRIPTION:
POLE CAT CREEK 5.0
END DESCRIPTION:
XS GIS Cut Line= 2
      3517547.48     10469995.98      3516818.48     10470856.89
#Sta/Elev= 30
  4319.3  395.88  4412.3  392.91  4426.6  392.90  4447.0  391.82  4455.2  392.08
  4490.3  391.08  4497.1  391.94  4504.6  390.82  4511.1  390.54  4561.8  389.15
  4582.6  387.89  4611.2  387.24  4724.3  383.03  4810.0  381.56  4859.5  379.71
  4951.7  377.91  4972.6  376.94  4991.6  375.26  4994.4  374.76  4997.6  375.26
  5044.0  378.61  5058.3  378.75  5142.9  377.64  5192.3  378.39  5228.6  379.83
  5263.7  381.97  5341.7  387.67  5391.1  388.55  5434.0  390.69  5447.4  390.60
#Mann=4,-1,0
  4319.3    0.12       0  4447.0    0.05       0  4991.6    0.03       0
  4997.6    0.05       0
Bank Sta=4991.6,4997.6
Exp/Cntr=0.3,0.1

Type RM Length L Ch R = 1,2898,476,476,476
BEGIN DESCRIPTION:
POLE CAT CREEK 4.0
END DESCRIPTION:
XS GIS Cut Line= 2
      3517443.26     10469766.84      3516360.00     10470322.36
#Sta/Elev= 30
  4218.5  403.62  4320.9  399.64  4388.1  396.18  4460.3  391.61  4489.5  388.80
  4517.3  387.35  4532.2  386.32  4610.0  381.98  4681.5  378.78  4765.4  373.97
  4892.9  373.70  4927.8  374.50  4965.2  374.30  4995.2  371.69  5026.1  373.13
  5053.9  371.69  5082.1  371.62  5084.9  371.12  5088.1  371.62  5107.6  372.61
  5114.9  373.71  5120.5  373.65  5130.1  375.02  5137.1  376.72  5203.7  380.40
  5225.9  380.63  5331.2  384.08  5359.1  385.50  5397.8  385.60  5435.9  386.79
#Mann=6,-1,0
  4218.5    0.16       0  4517.3    0.12       0  4532.2    0.16       0
  4681.5    0.05       0  5082.1    0.03       0  5088.1    0.05       0
Bank Sta=5082.1,5088.1
Exp/Cntr=0.3,0.1

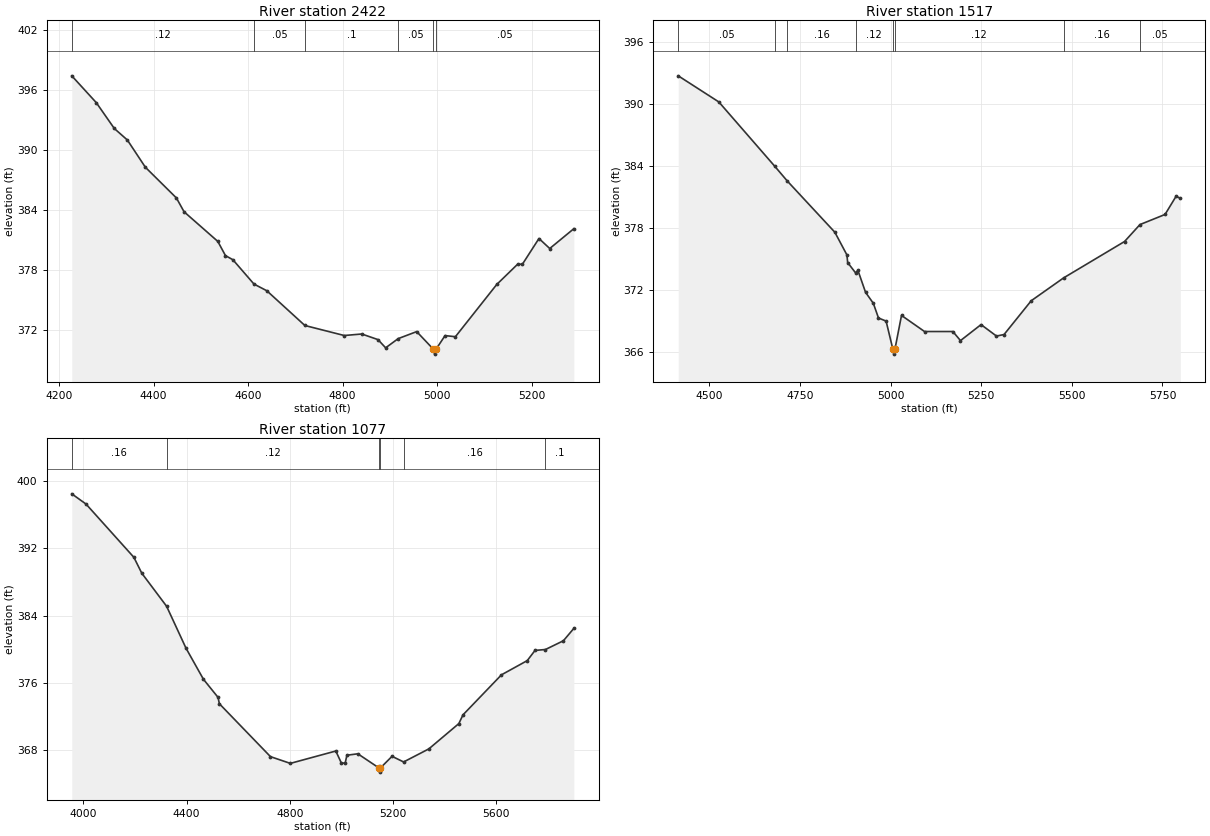
Type RM Length L Ch R = 1,2422,905,905,905
BEGIN DESCRIPTION:
POLE CAT CREEK 3.0
END DESCRIPTION:
XS GIS Cut Line= 2
      3517142.12     10469491.63      3516207.19     10469995.99
#Sta/Elev= 30
  4227.0  397.39  4278.9  394.71  4317.0  392.13  4344.6  390.98  4382.7  388.26
  4448.4  385.19  4464.6  383.81  4536.0  380.85  4552.2  379.43  4567.9  379.02
  4612.5  376.59  4639.7  375.92  4720.2  372.45  4803.5  371.45  4840.6  371.60
  4874.9  371.04  4891.1  370.22  4917.7  371.14  4956.8  371.84  4991.9  370.09
  4994.6  369.59  4997.9  370.09  5016.8  371.44  5038.7  371.33  5126.2  376.55
  5170.1  378.56  5180.6  378.58  5215.5  381.14  5238.3  380.14  5289.3  382.12
#Mann=6,-1,0
  4227.0    0.12       0  4612.5    0.05       0  4720.2     0.1       0
  4917.7    0.05       0  4991.9    0.03       0  4997.9    0.05       0
Bank Sta=4991.9,4997.9
Exp/Cntr=0.3,0.1

Type RM Length L Ch R = 1,1517,440,440,440
BEGIN DESCRIPTION:
POLE CAT CREEK 2.0
END DESCRIPTION:
XS GIS Cut Line= 4
      3516964.11     10469065.43      3516498.86     10469065.43
      3516151.63     10469440.43      3516082.20     10469843.17
#Sta/Elev= 30
  4414.3  392.74  4526.3  390.21  4680.3  383.99  4715.4  382.54  4846.3  377.59
  4879.6  375.39  4881.7  374.65  4903.3  373.66  4910.0  373.89  4931.0  371.77
  4952.5  370.70  4966.7  369.28  4987.7  368.98  5006.2  366.28  5009.0  365.78
  5012.2  366.28  5030.2  369.53  5093.7  367.97  5171.9  367.97  5192.9  367.09
  5249.6  368.64  5292.2  367.53  5313.1  367.68  5388.0  370.95  5477.6  373.17
  5645.5  376.69  5688.0  378.33  5757.2  379.31  5787.6  381.07  5799.3  380.88
#Mann=8,-1,0
  4414.3    0.05       0  4680.3     0.1       0  4715.4    0.16       0
  4903.3    0.12       0  5006.2    0.07       0  5012.2    0.12       0
  5477.6    0.16       0  5688.0    0.05       0
Bank Sta=5006.2,5012.2
Exp/Cntr=0.3,0.1

Type RM Length L Ch R = 1,1077,0,0,0
BEGIN DESCRIPTION:
POLE CAT CREEK 1.0
END DESCRIPTION:
XS GIS Cut Line= 4
      3516795.74     10468221.68      3516336.01     10468447.73
      3515980.99     10469472.40      3515989.63     10469822.17
#Sta/Elev= 30
  3954.6  398.48  4010.0  397.26  4195.4  390.93  4226.1  389.04  4322.3  385.11
  4397.6  380.12  4465.1  376.43  4521.7  374.28  4526.9  373.52  4725.0  367.23
  4802.0  366.43  4978.3  367.90  5000.2  366.45  5014.7  366.48  5021.4  367.40
  5063.7  367.57  5145.4  365.89  5148.1  365.39  5151.4  365.89  5196.3  367.27
  5241.2  366.60  5338.9  368.15  5455.3  371.16  5471.4  372.20  5620.6  376.96
  5720.6  378.65  5750.6  379.86  5791.2  379.97  5860.7  381.01  5901.2  382.48
#Mann=6,-1,0
  3954.6    0.16       0  4322.3    0.12       0  5145.4    0.07       0
  5151.4    0.12       0  5241.2    0.16       0  5791.2     0.1       0
Bank Sta=5145.4,5151.4
Exp/Cntr=0.3,0.1

Chan Stop Cuts=-1