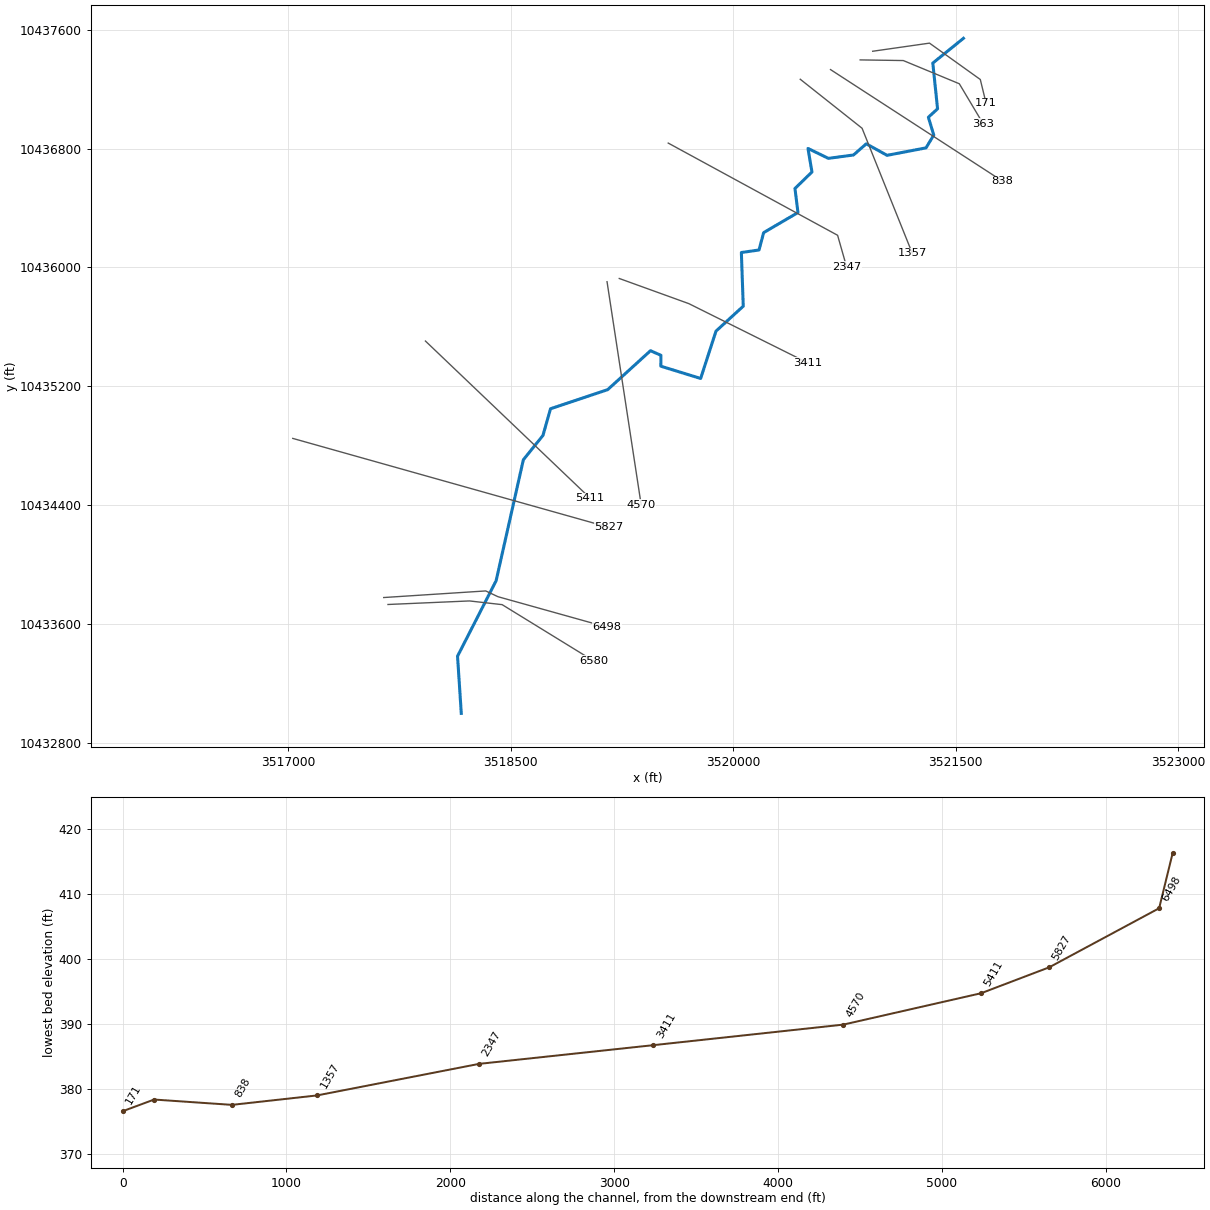
--- SCHOOLHOUSE BRANCH TRIB 1.prj (project) ---

Proj Title=SCHOOLHOUSE BRANCH TRIB 1 Base Level Engineering
Current Plan=p01
Default Exp/Contr=0.3,0.1
English Units
Geom File=g01
Flow File=f01
Plan File=p01
Y Axis Title=Elevation
X Axis Title(PF)=Main Channel Distance
X Axis Title(XS)=Station
BEGIN DESCRIPTION:
SCHOOLHOUSE BRANCH TRIB 1
END DESCRIPTION:
DSS Export Rating Curves= 0
DSS Export Rating Curve Sorted= 0
DSS Export Volume Flow Curves= 0
DXF OffsetX= 0
DXF OffsetY= 0
DXF ScaleX= 1
DXF ScaleY= 10

--- SCHOOLHOUSE BRANCH TRIB 1.p01 (plan) ---

Plan Title=Multiple Run
Short Identifier=Multiple
Geom File=g01
Flow File=f01
Subcritical Flow
K Sum by GR= 0
Std Step Tol= 0.01
Critical Tol= 0.01
Num of Std Step Trials= 20
Max Error Tol= 0.3
Flow Tol Ratio= 0.001
Split Flow NTrial= 30
Split Flow Tol= 0.02
Split Flow Ratio= 0.02
Log Output Level= 0
Friction Slope Method= 1
Unsteady Friction Slope Method= 2
Unsteady Bridges Friction Slope Method= 1
Parabolic Critical Depth
Global Vel Dist=  1 , 1 , 1
Global Log Level= 0
CheckData=True
Encroach Param= -1, 0, 0, 0
BEGIN DESCRIPTION:
Multiple Run
END DESCRIPTION:

--- SCHOOLHOUSE BRANCH TRIB 1.f01 (steady flow) ---

Flow Title=Multiple
Program Version=4.10
Number of Profiles= 7
Profile Names=10-year,25-year,50-year,1pct_min,100-year,1pct_plu,500-year
River Rch & RM=SCHOOLHOUSE BRAN,Reach-1         ,6580
     912    1256    1541    1380    1866    2524    2730
Boundary for River Rch & Prof#=SCHOOLHOUSE BRAN,Reach-1         , 1
Up Type= 0
Dn Type= 3
Dn Slope=0.005
Boundary for River Rch & Prof#=SCHOOLHOUSE BRAN,Reach-1         , 2
Up Type= 0
Dn Type= 3
Dn Slope=0.005
Boundary for River Rch & Prof#=SCHOOLHOUSE BRAN,Reach-1         , 3
Up Type= 0
Dn Type= 3
Dn Slope=0.005
Boundary for River Rch & Prof#=SCHOOLHOUSE BRAN,Reach-1         , 4
Up Type= 0
Dn Type= 3
Dn Slope=0.005
Boundary for River Rch & Prof#=SCHOOLHOUSE BRAN,Reach-1         , 5
Up Type= 0
Dn Type= 3
Dn Slope=0.005
Boundary for River Rch & Prof#=SCHOOLHOUSE BRAN,Reach-1         , 6
Up Type= 0
Dn Type= 3
Dn Slope=0.005
Boundary for River Rch & Prof#=SCHOOLHOUSE BRAN,Reach-1         , 7
Up Type= 0
Dn Type= 3
Dn Slope=0.005
DSS Import GetInterval= 0
DSS Import GetPeak= 0
DSS Import FillOption= 0

--- SCHOOLHOUSE BRANCH TRIB 1.g01 (geometry) ---

Geom Title=Existing Conditions
Program Version=4.10

River Reach=SCHOOLHOUSE BRAN,Reach-1
Reach XY= 30
      3518167.98     10432997.75       3518142.7     10433382.54
      3518402.76     10433890.61      3518586.24     10434704.64
      3518718.35     10434868.48      3518769.43     10435048.24
      3519154.69      10435176.9      3519443.25     10435439.04
      3519513.64      10435407.8      3519512.83     10435334.71
      3519781.16     10435252.16      3519884.55     10435570.75
      3520068.23     10435738.49      3520055.63     10436099.94
      3520174.68     10436117.03      3520205.87      10436233.9
      3520437.02     10436368.96       3520416.8     10436530.78
      3520531.36     10436642.07      3520504.44     10436800.46
      3520642.04     10436733.76      3520811.11     10436756.37
      3520897.39     10436831.72      3521037.46     10436754.07
      3521300.28     10436804.37      3521352.25     10436890.48
      3521315.91      10437010.4      3521377.82     10437067.25
      3521345.79     10437375.06      3521552.11     10437541.64

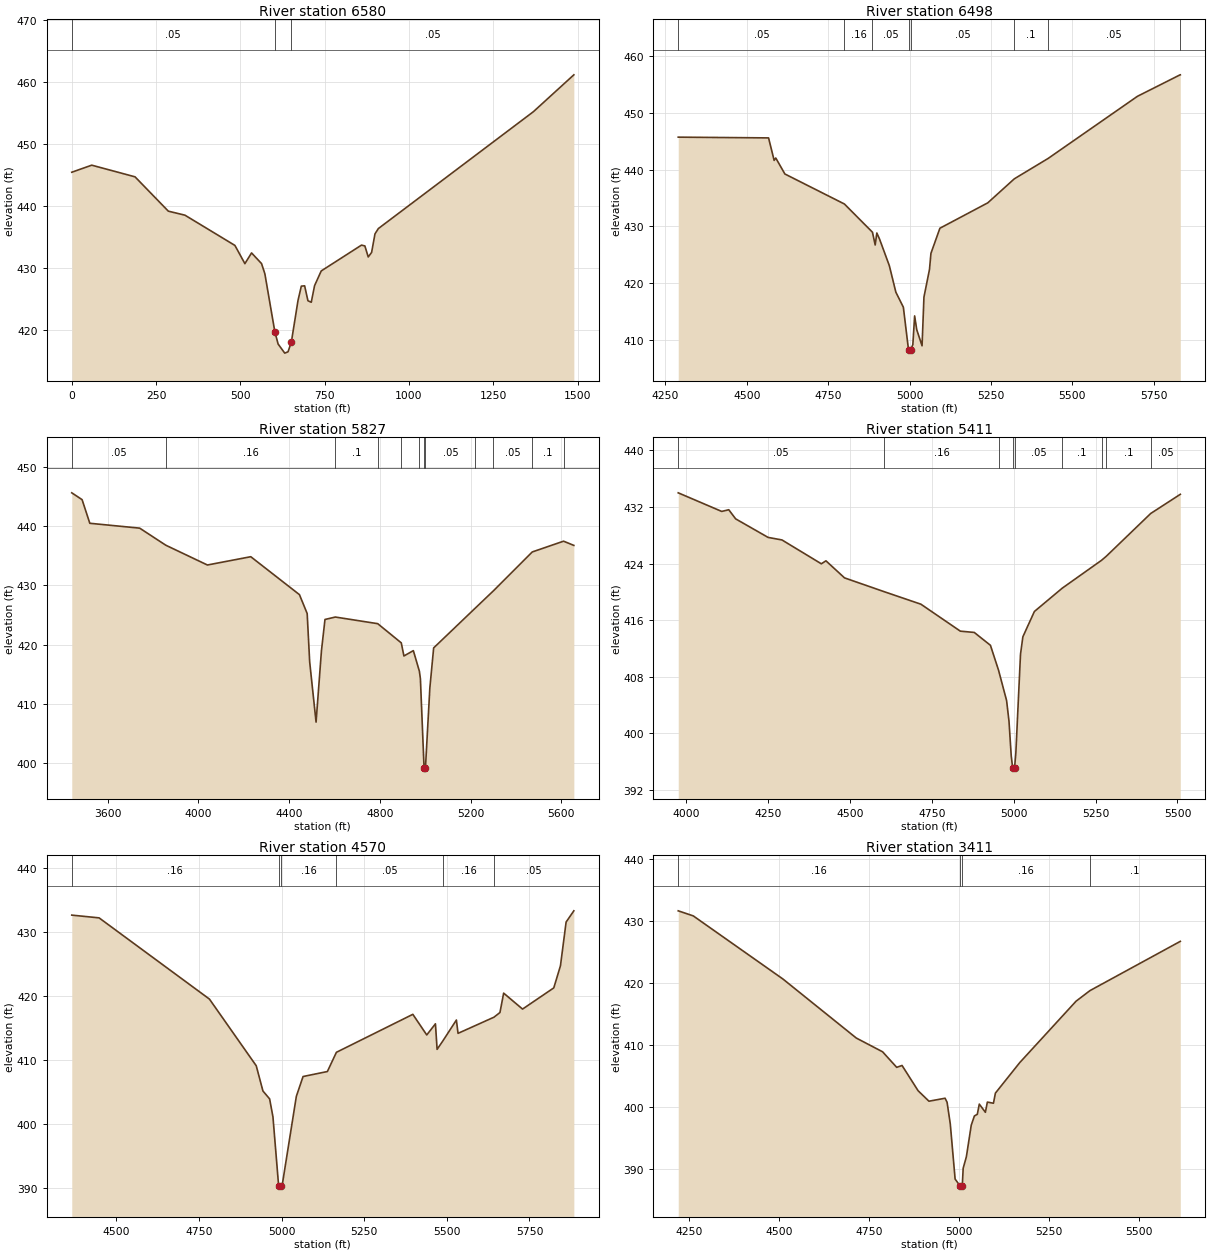
Type RM Length L Ch R = 1 ,6580    ,82,82,82
XS GIS Cut Line= 4
     3517674.025     10433730.71      3518223.07    10433754.581
     3518443.339    10433729.625     3519059.659    10433350.935
#Sta/Elev= 30
       0  445.38   59.24  446.52  187.58  444.64   286.3   439.1  335.67  438.45
  483.76  433.57  513.37  430.63  533.12  432.36   562.7  430.64  572.53  429.01
  602.02  419.68  611.85  417.66  631.51  416.19  641.35  416.41  651.18  417.99
  670.84  424.68  680.67     427   690.5  427.05  700.33  424.64  710.16   424.4
     720  427.08  739.66  429.45   859.1  433.62   869.1  433.49  879.09  431.71
  889.09  432.44  899.08  435.43  909.08  436.29 1368.83  455.15 1488.76   461.1
#Mann= 3 , 0 , 0
       0     .05       0  602.02     .03       0  651.18     .05       0
Bank Sta=602.02,651.18
XS Rating Curve= 0 ,0
Exp/Cntr=0.3,0.1

Type RM Length L Ch R = 1 ,6498    ,671,671,671
BEGIN DESCRIPTION:
Mapping XS ac4fe020
END DESCRIPTION:
XS GIS Cut Line= 4
      3517645.28     10433777.51      3518332.75     10433821.96
      3518415.39     10433783.07      3519148.81     10433578.32
#Sta/Elev= 30
  4289.7  445.69  4567.1  445.56  4584.2  441.61  4589.2  442.03  4617.2  439.22
  4799.9  433.95  4886.1  428.99  4894.5  426.75  4899.5  428.85  4907.8   427.8
  4937.9  423.12  4957.9  418.47    4981  415.81    4997  408.25  4999.7  407.75
    5003  408.25  5010.1  409.24  5015.6  414.29  5022.1  411.86  5038.4  409.04
  5044.2  417.59  5061.2  422.44  5065.7  425.28  5093.2  429.69  5240.2  434.15
  5321.7  438.37  5425.5  441.95  5699.9  452.87  5830.4  456.63  5831.4  456.64
#Mann= 8 ,-1 , 0
  4289.7     .05       0  4799.9     .16       0  4886.1     .05       0
    4997     .03       0    5003     .05       0  5321.7      .1       0
  5425.5     .05       0  5830.4      .1       0
Bank Sta=4997,5003
XS Rating Curve= 0 ,0
Exp/Cntr=0.3,0.1

Type RM Length L Ch R = 1 ,5827    ,416,416,416
BEGIN DESCRIPTION:
SCHOOLHOUSE BRANCH TRIB 1 12.0
END DESCRIPTION:
XS GIS Cut Line= 2
      3517032.31      10434848.7      3519163.34     10434249.75
#Sta/Elev= 30
  3441.9  445.62  3487.4  444.47  3521.5  440.48  3741.4  439.66  3856.5  436.78
  4039.9  433.44  4231.1  434.84  4445.7  428.44  4479.8  425.25  4490.8   417.1
    4519  406.93  4542.8  419.01  4558.3  424.25  4604.1  424.66  4790.9  423.54
  4894.7   420.3  4906.3  418.09  4947.9  418.99  4974.5  415.52    4979  414.25
  4995.2  399.16  4997.9  398.66  5001.2  399.16  5020.6  412.67  5037.4  419.45
  5221.8   426.2  5300.8  429.08    5472  435.64  5610.2  437.46  5655.5  436.75
#Mann= 12 ,-1 , 0
  3441.9     .05       0  3856.5     .16       0  4604.1      .1       0
  4790.9     .05       0  4894.7      .1       0  4974.5     .05       0
  4995.2     .03       0  5001.2     .05       0  5221.8      .1       0
  5300.8     .05       0    5472      .1       0  5610.2     .05       0
Bank Sta=4995.2,5001.2
XS Rating Curve= 0 ,0
Exp/Cntr=0.3,0.1

Type RM Length L Ch R = 1 ,5411    ,841,841,841
BEGIN DESCRIPTION:
SCHOOLHOUSE BRANCH TRIB 1 11.0
END DESCRIPTION:
XS GIS Cut Line= 2
      3517926.38     10435504.08      3519036.43     10434446.06
#Sta/Elev= 30
  3975.2     434  4108.1  431.37  4129.5  431.61  4150.6  430.32  4249.7   427.7
  4292.1  427.34  4412.3  423.97  4426.4  424.39  4483.1  421.98  4604.8  420.02
  4716.4  418.26  4836.9  414.45  4879.4  414.27  4928.8  412.45  4953.6  408.92
  4978.1  404.65  4985.4  401.75  4992.3  396.82  4996.5  395.17  4999.3  394.67
  5002.5  395.17  5006.4  397.25  5020.6  411.18  5027.8  413.65    5063  417.23
  5148.2  420.53  5268.3  424.47  5282.7  425.04  5418.3  431.08  5508.7  433.79
#Mann= 9 ,-1 , 0
  3975.2     .05       0  4604.8     .16       0  4953.6     .05       0
  4996.5     .03       0  5002.5     .05       0  5148.2      .1       0
  5268.3     .16       0  5282.7      .1       0  5418.3     .05       0
Bank Sta=4996.5,5002.5
XS Rating Curve= 0 ,0
Exp/Cntr=0.3,0.1

Type RM Length L Ch R = 1 ,4570    ,1159,1159,1159
BEGIN DESCRIPTION:
SCHOOLHOUSE BRANCH TRIB 1 9.0
END DESCRIPTION:
XS GIS Cut Line= 2
      3519150.32     10435903.43      3519380.36     10434401.65
#Sta/Elev= 30
    4365  432.62  4447.7  432.19  4781.6  419.51  4923.2   409.1  4943.5  405.16
  4963.7  403.93  4973.8  401.12    4991  390.34  4993.8  389.84    4997  390.34
  5001.6   390.4  5044.6  404.33  5064.9  407.42  5138.5   408.2  5165.8   411.2
  5397.1  417.13  5439.2  413.91  5465.5  415.65  5470.5  411.66  5487.8  412.97
  5528.9  416.24  5533.9  414.16  5642.5  416.68  5660.7  417.41  5671.9  420.44
  5729.1  417.95  5823.6  421.26  5843.8  424.71  5860.9  431.54  5884.3  433.29
#Mann= 6 ,-1 , 0
    4365     .16       0    4991     .07       0    4997     .16       0
  5165.8     .05       0  5487.8     .16       0  5642.5     .05       0
Bank Sta=4991,4997
XS Rating Curve= 0 ,0
Exp/Cntr=0.3,0.1

Type RM Length L Ch R = 1 ,3411    ,1064,1064,1064
BEGIN DESCRIPTION:
SCHOOLHOUSE BRANCH TRIB 1 7.0
END DESCRIPTION:
XS GIS Cut Line= 3
      3519232.78      10435925.1      3519701.54     10435755.83
      3520504.36     10435356.59
#Sta/Elev= 30
  4218.9  431.63  4260.7  430.81  4509.7  420.62  4713.7  411.08  4786.7  408.86
  4825.9  406.35  4840.8  406.65  4885.4  402.57  4915.5  400.88  4960.3  401.36
  4965.9  400.71  4974.8   397.2  4988.2  388.31  5002.1  387.18  5004.8  386.68
  5008.1  387.18  5010.6  390.05  5019.5  391.91    5033     397  5041.8   398.5
  5049.9  398.77  5055.4  400.41  5072.3  399.09  5077.8  400.74  5094.7  400.55
  5100.2  402.19  5167.4  407.09  5324.2  417.03  5362.8  418.74  5613.9   426.7
#Mann= 4 ,-1 , 0
  4218.9     .16       0  5002.1     .07       0  5008.1     .16       0
  5362.8      .1       0
Bank Sta=5002.1,5008.1
XS Rating Curve= 0 ,0
Exp/Cntr=0.3,0.1

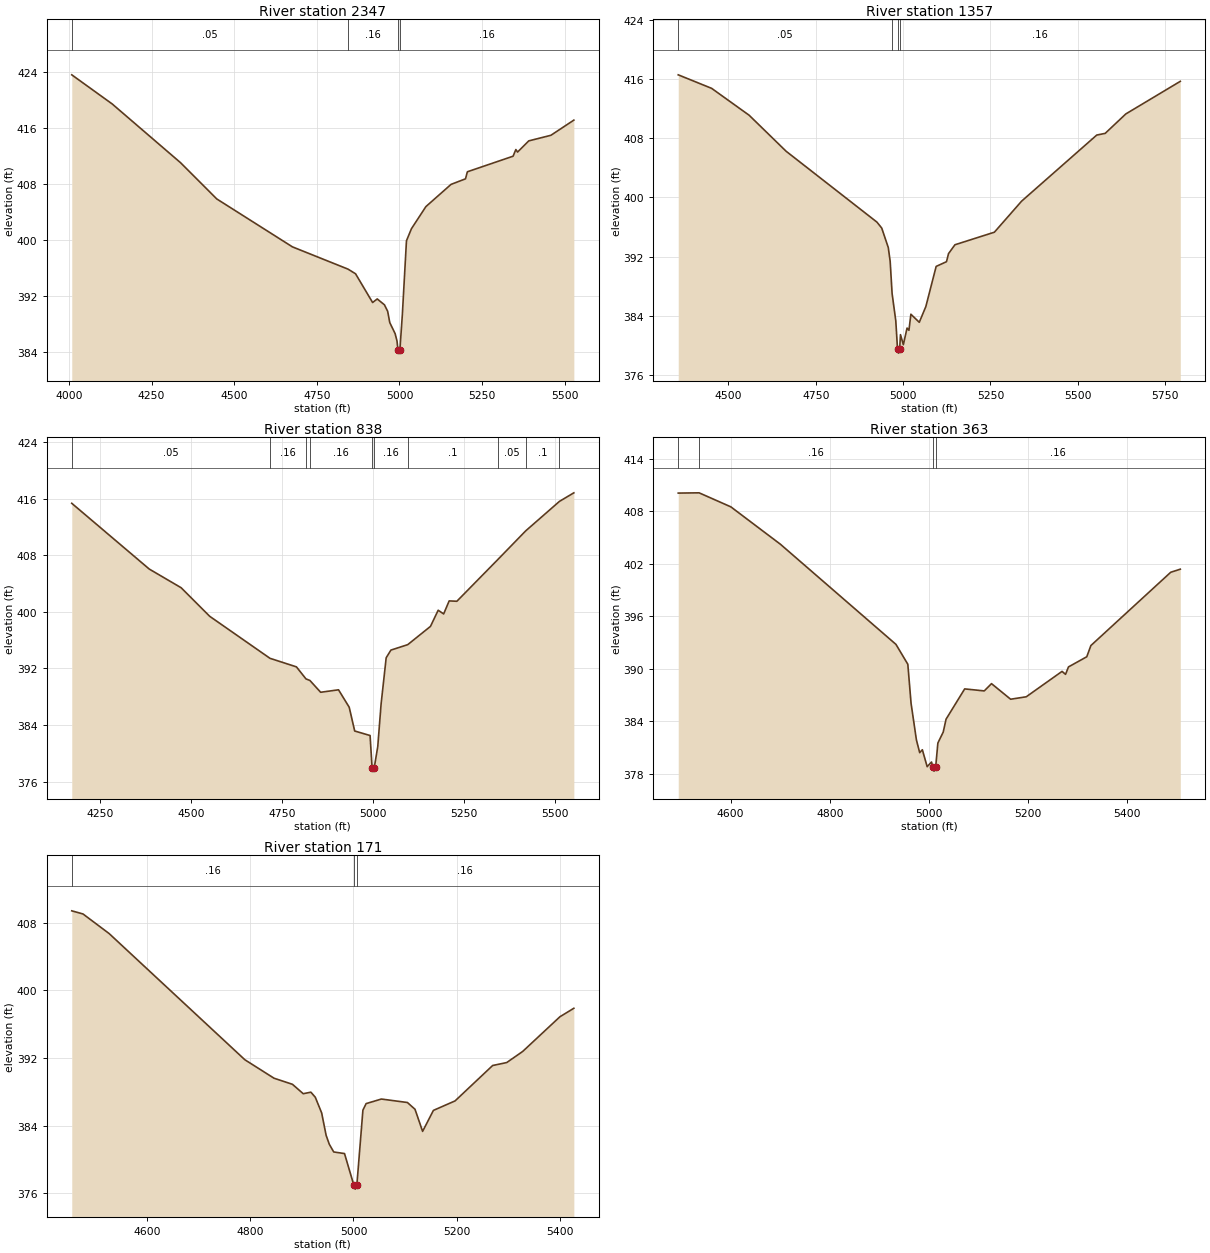
Type RM Length L Ch R = 1 ,2347    ,990,990,990
BEGIN DESCRIPTION:
SCHOOLHOUSE BRANCH TRIB 1 5.0
END DESCRIPTION:
XS GIS Cut Line= 3
      3519562.67     10436836.55      3520704.15      10436215.9
      3520764.42     10436004.94
#Sta/Elev= 30
  4008.7  423.61  4130.8  419.45    4338  411.03  4447.2  405.86  4676.2     399
  4844.5  395.81  4867.1  395.15  4918.7  391.04  4932.7  391.55  4954.5  390.71
  4964.2  389.79  4970.7  388.16  4986.8  386.59  4992.5  385.53  4995.3   384.3
  4998.1   383.8  5001.3   384.3  5008.7  389.33  5021.1  399.87  5036.2   401.6
  5079.9  404.76    5156  407.94  5199.7  408.73  5205.3  409.74  5343.6  411.97
    5352  412.92  5357.2  412.56    5391  414.16    5458  414.96  5527.4  417.13
#Mann= 4 ,-1 , 0
  4008.7     .05       0  4844.5     .16       0  4995.3     .07       0
  5001.3     .16       0
Bank Sta=4995.3,5001.3
XS Rating Curve= 0 ,0
Exp/Cntr=0.3,0.1

Type RM Length L Ch R = 1 ,1357    ,519,519,519
BEGIN DESCRIPTION:
SCHOOLHOUSE BRANCH TRIB 1 3.0
END DESCRIPTION:
XS GIS Cut Line= 3
      3520452.43     10437266.23      3520869.08     10436936.38
       3521206.9     10436096.16
#Sta/Elev= 30
  4356.6  416.59  4452.2  414.76  4559.6  411.12  4665.4  406.25  4925.4  396.66
    4939  395.86  4957.8  393.22  4963.2  391.35  4968.7  387.01  4979.3   383.3
  4984.3  379.44  4987.1  378.94  4990.3  379.44  4992.7  381.44  5000.9  380.08
  5011.5  382.33  5016.9  382.03  5022.5   384.2  5046.5  383.11  5065.3  385.24
  5094.8  390.67  5124.4  391.31  5130.2   392.4  5148.6   393.6  5261.5   395.3
  5339.4   399.5  5554.4  408.44  5578.6  408.67  5637.7   411.3  5793.6  415.71
#Mann= 4 ,-1 , 0
  4356.6     .05       0  4968.7     .16       0  4984.3     .07       0
  4990.3     .16       0
Bank Sta=4984.3,4990.3
XS Rating Curve= 0 ,0
Exp/Cntr=0.3,0.1

Type RM Length L Ch R = 1 ,838     ,475,475,475
BEGIN DESCRIPTION:
SCHOOLHOUSE BRANCH TRIB 1 2.0
END DESCRIPTION:
XS GIS Cut Line= 2
      3520656.44     10437331.32      3521815.26     10436580.48
#Sta/Elev= 30
  4172.4  415.33  4385.5  406.04  4473.2   403.4  4551.6  399.37  4717.5  393.43
  4790.3  392.22  4816.5  390.52  4827.3   390.3  4856.9  388.63    4906  388.98
  4935.4  386.52  4950.5  383.16  4992.8  382.52  4998.3  377.99  5001.1  377.49
  5004.3  377.99  5013.9  380.94  5023.1  386.97  5037.1  393.51  5050.1  394.59
  5096.4  395.36  5158.9  397.94  5180.1  400.22  5195.2   399.7  5210.3  401.54
  5231.5  401.49  5343.5  407.35  5420.9  411.44  5513.6   415.6  5553.2  416.81
#Mann= 10 ,-1 , 0
  4172.4     .05       0  4717.5     .16       0  4816.5     .05       0
  4827.3     .16       0  4998.3     .07       0  5004.3     .16       0
  5096.4      .1       0  5343.5     .05       0  5420.9      .1       0
  5513.6     .05       0
Bank Sta=4998.3,5004.3
XS Rating Curve= 0 ,0
Exp/Cntr=0.3,0.1

Type RM Length L Ch R = 1 ,363     ,192,192,192
BEGIN DESCRIPTION:
SCHOOLHOUSE BRANCH TRIB 1 1.1
END DESCRIPTION:
XS GIS Cut Line= 4
      3520856.02     10437396.45      3521146.85     10437392.11
      3521524.46     10437235.86      3521685.05     10436966.76
#Sta/Elev= 30
  4494.2  410.06  4536.3  410.09  4600.3  408.49  4700.3  404.22  4933.5  392.78
  4957.4  390.51  4963.9  386.06  4974.7  381.88  4981.3  380.42  4986.7  380.75
  4996.4  378.82  5005.2  379.35  5007.6  378.81  5010.3  378.31  5013.6  378.81
    5018  381.52  5028.8  382.77  5034.5  384.24  5072.1   387.7  5111.6  387.47
  5126.2   388.3  5164.8  386.52  5196.3   386.8  5268.5   389.7  5275.6  389.36
  5281.5  390.21  5318.4  391.37  5326.7  392.65  5487.8  401.02  5507.1  401.37
#Mann= 4 ,-1 , 0
  4494.2     .05       0  4536.3     .16       0  5007.6     .07       0
  5013.6     .16       0
Bank Sta=5007.6,5013.6
XS Rating Curve= 0 ,0
Exp/Cntr=0.3,0.1

Type RM Length L Ch R = 1 ,171     ,0,0,0
BEGIN DESCRIPTION:
SCHOOLHOUSE BRANCH TRIB 1 1.0
END DESCRIPTION:
XS GIS Cut Line= 4
       3520940.6     10437454.69      3521323.43     10437509.38
      3521665.87     10437264.58      3521704.67      10437105.5
#Sta/Elev= 30
    4455  409.38  4476.7  409.01  4527.2   406.7  4789.9  391.79  4846.3  389.61
    4882  388.89  4902.8  387.78  4917.6  387.96  4926.1  387.37  4938.5  385.51
  4947.1  382.87  4953.2  381.82  4961.8   380.9  4982.7  380.71  5000.6  377.01
  5003.4  376.51  5006.6  377.01  5018.3  385.84  5024.5  386.61    5054  387.15
  5104.4  386.74  5119.1  385.94  5133.8  383.33  5154.7  385.81  5196.6  386.93
  5269.3  391.11  5296.6  391.46  5327.4  392.77  5399.5  396.87  5426.4  397.87
#Mann= 3 ,-1 , 0
    4455     .16       0  5000.6     .07       0  5006.6     .16       0
Bank Sta=5000.6,5006.6
XS Rating Curve= 0 ,0
Exp/Cntr=0.3,0.1

Chan Stop Cuts=-1
Use User Specified Reach Order=0
Composite Channel Slope=5