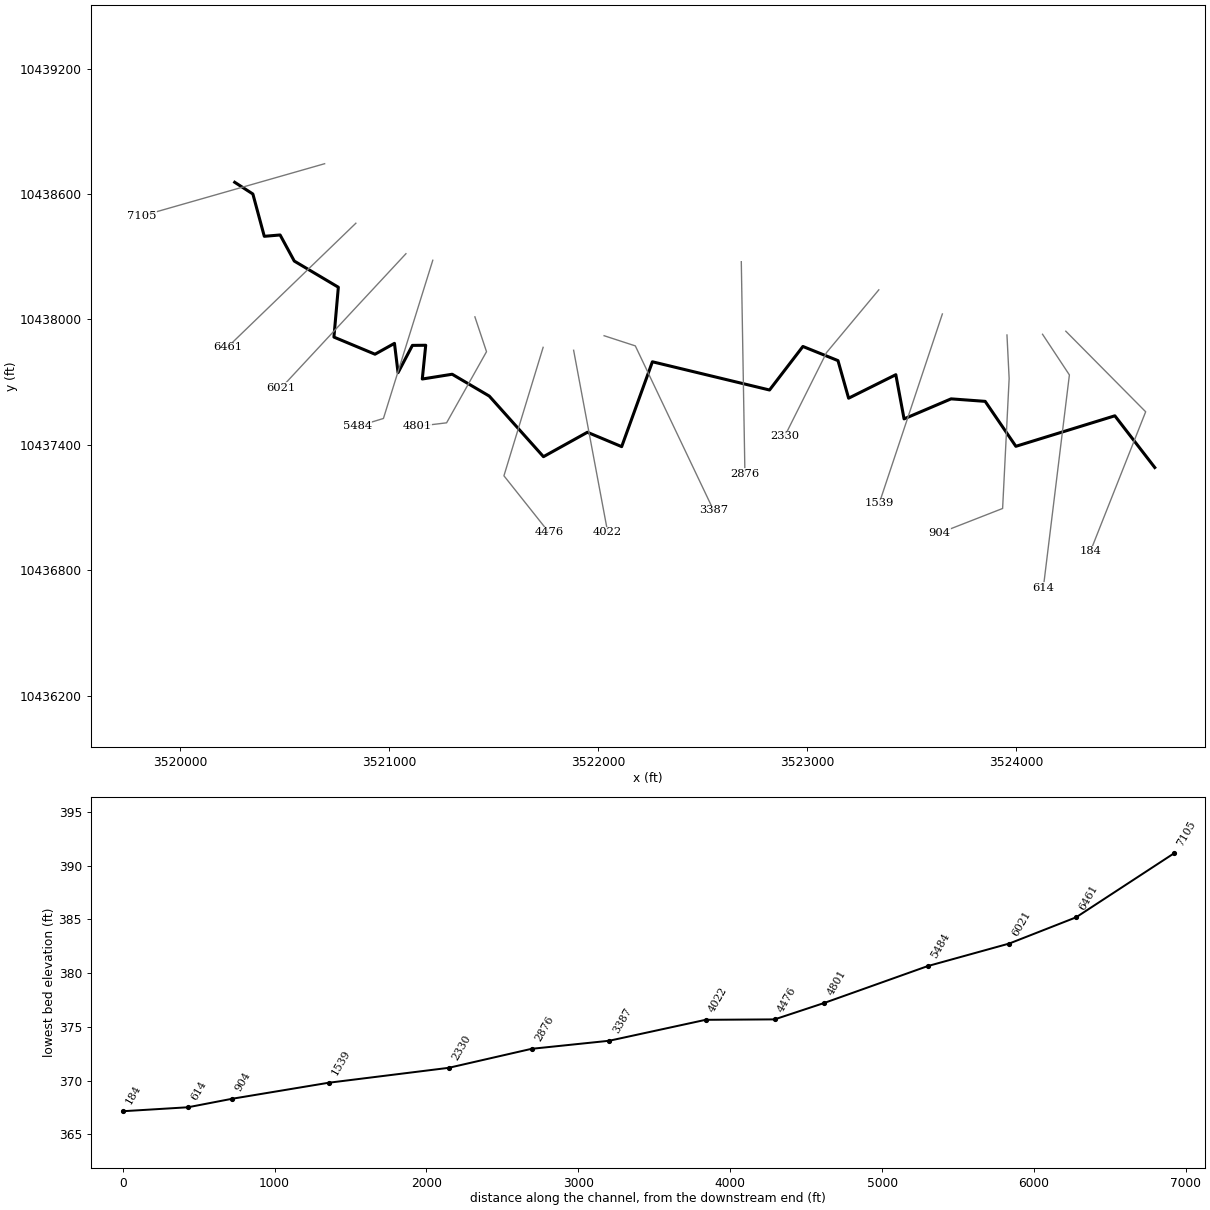
--- SCHOOLHOUSE BRANCH.prj (project) ---

Proj Title=SCHOOLHOUSE BRANCH Base Level Engineering
Current Plan=p01
Default Exp/Contr=0.3,0.1
English Units
Geom File=g01
Flow File=f01
Plan File=p01
Y Axis Title=Elevation
X Axis Title(PF)=Main Channel Distance
X Axis Title(XS)=Station
BEGIN DESCRIPTION:
SCHOOLHOUSE BRANCH
END DESCRIPTION:
DSS Export Rating Curves= 0
DSS Export Rating Curve Sorted= 0
DSS Export Volume Flow Curves= 0
DXF OffsetX= 0
DXF OffsetY= 0
DXF ScaleX= 1
DXF ScaleY= 10

--- SCHOOLHOUSE BRANCH.p01 (plan) ---

Plan Title=Multiple Run
Short Identifier=Multiple
Geom File=g01
Flow File=f01
Subcritical Flow
K Sum by GR= 0
Std Step Tol= 0.01
Critical Tol= 0.01
Num of Std Step Trials= 20
Max Error Tol= 0.3
Flow Tol Ratio= 0.001
Split Flow NTrial= 30
Split Flow Tol= 0.02
Split Flow Ratio= 0.02
Log Output Level= 0
Friction Slope Method= 1
Unsteady Friction Slope Method= 2
Unsteady Bridges Friction Slope Method= 1
Parabolic Critical Depth
Global Vel Dist=  1 , 1 , 1
Global Log Level= 0
CheckData=True
Encroach Param= -1, 0, 0, 0
BEGIN DESCRIPTION:
Multiple Run
END DESCRIPTION:

--- SCHOOLHOUSE BRANCH.f01 (steady flow) ---

Flow Title=Multiple
Number of Profiles=7
Profile Names=10-year,25-year,50-year,1pct_min,100-year,1pct_plu,500-year
River Rch & RM= SCHOOLHOUSE BRAN,Reach-1,7105
     424     557     662     577     780    1055    1077
River Rch & RM= SCHOOLHOUSE BRAN,Reach-1,4476
    1233    1719    2126    1916    2591    3504    3842
Boundary for River Rch & Prof#=SCHOOLHOUSE BRAN,Reach-1,1
Up Type=0
Dn Type=3
Dn Slope=0.005
Boundary for River Rch & Prof#=SCHOOLHOUSE BRAN,Reach-1,2
Up Type=0
Dn Type=3
Dn Slope=0.005
Boundary for River Rch & Prof#=SCHOOLHOUSE BRAN,Reach-1,3
Up Type=0
Dn Type=3
Dn Slope=0.005
Boundary for River Rch & Prof#=SCHOOLHOUSE BRAN,Reach-1,4
Up Type=0
Dn Type=3
Dn Slope=0.005
Boundary for River Rch & Prof#=SCHOOLHOUSE BRAN,Reach-1,5
Up Type=0
Dn Type=3
Dn Slope=0.005
Boundary for River Rch & Prof#=SCHOOLHOUSE BRAN,Reach-1,6
Up Type=0
Dn Type=3
Dn Slope=0.005
Boundary for River Rch & Prof#=SCHOOLHOUSE BRAN,Reach-1,7
Up Type=0
Dn Type=3
Dn Slope=0.005

--- SCHOOLHOUSE BRANCH.g01 (geometry) ---

Geom Title=Existing Conditions
Program Version=4.10

River Reach=SCHOOLHOUSE BRAN,Reach-1
Reach XY= 30
      3520261.08     10438656.24      3520347.94     10438600.13
      3520402.59     10438397.73      3520478.24     10438404.12
      3520546.09     10438279.28      3520756.76     10438154.12
      3520735.69     10437915.56      3520932.18     10437833.66
      3521025.26     10437885.62      3521042.38     10437745.38
      3521111.07     10437875.91      3521174.73     10437876.52
      3521158.33     10437715.08      3521301.32     10437737.86
      3521478.76      10437633.4      3521737.94     10437343.49
      3521948.05     10437460.28      3522112.07     10437391.54
      3522259.08     10437797.52      3522819.34     10437662.47
        3522979.     10437870.76      3523146.78     10437803.05
      3523197.62     10437623.21      3523423.47      10437735.7
       3523462.9      10437524.3      3523687.82      10437620.1
      3523850.87     10437608.14      3523997.67      10437393.1
      3524471.16     10437539.06      3524662.11     10437291.64

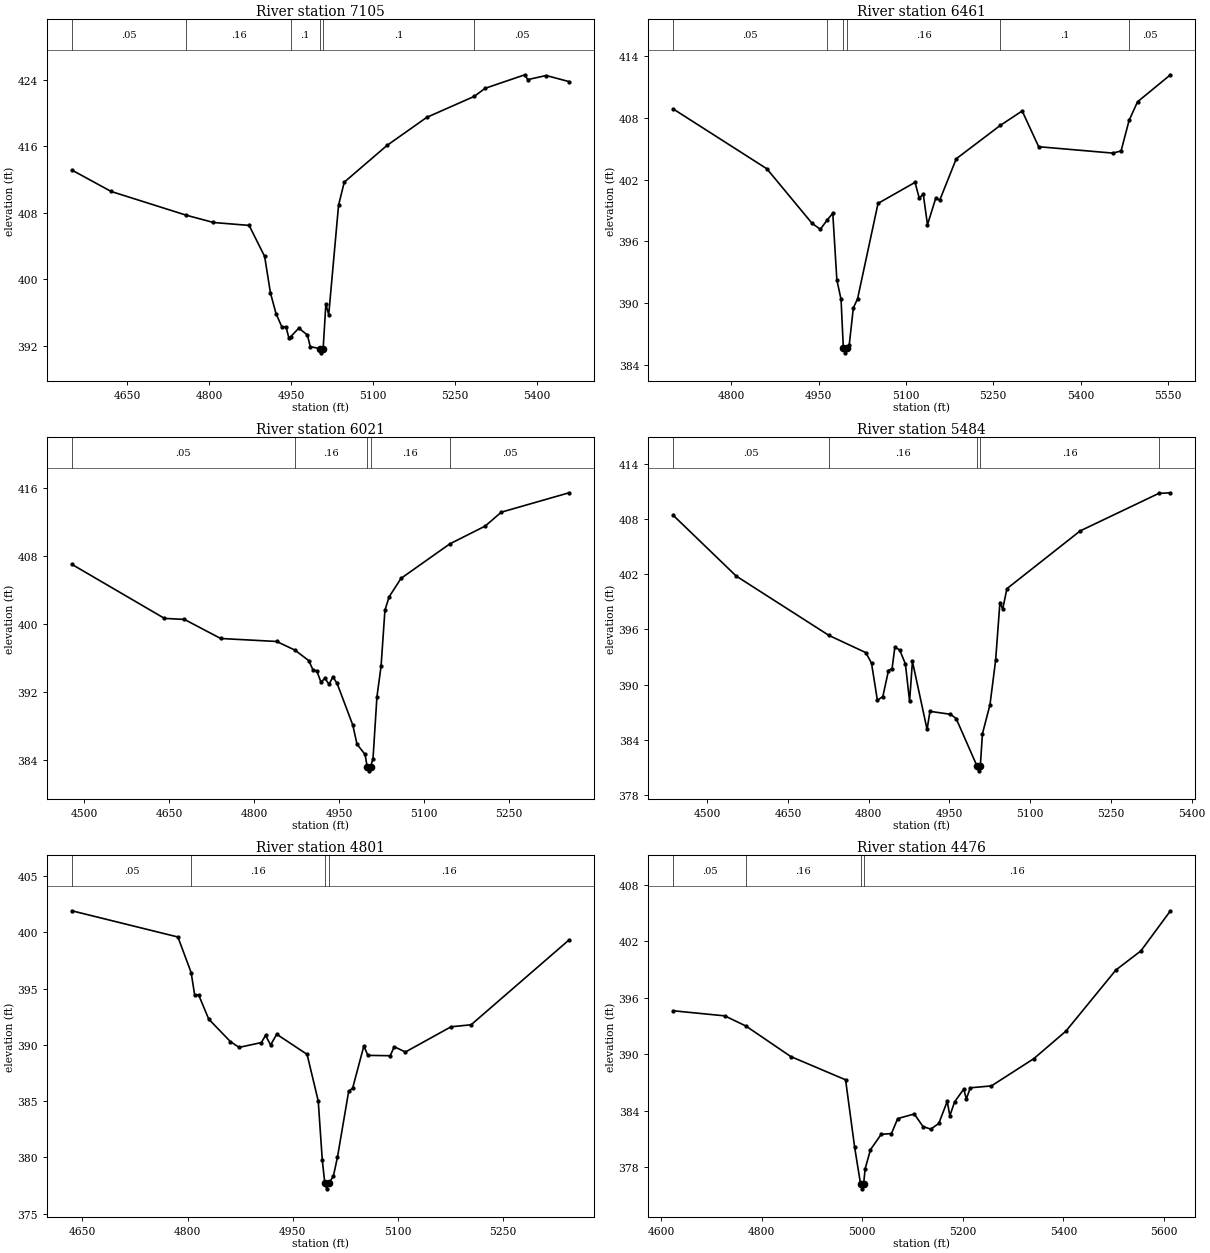
Type RM Length L Ch R = 1 ,7105    ,644,644,644
BEGIN DESCRIPTION:
SCHOOLHOUSE BRANCH 14.0
END DESCRIPTION:
XS GIS Cut Line= 2
      3520691.21     10438745.05      3519816.71     10438495.19
#Sta/Elev= 30
  4548.6  413.13  4620.6  410.55  4758.3  407.69  4807.7  406.82  4872.9  406.47
  4901.3  402.73  4911.9  398.35  4922.1  395.86  4932.5   394.3  4940.5  394.23
  4945.7  392.91    4949  393.08  4963.7  394.11  4979.5  393.29  4984.7  391.89
  5002.3  391.64    5005  391.14  5008.3  391.64  5013.3  397.02  5018.5  395.73
  5036.5   408.9  5046.9  411.67  5125.1  416.09  5197.9  419.47  5284.7  421.99
  5304.5  422.96  5377.3  424.59  5382.5  424.01  5416.3   424.5  5458.1  423.77
#Mann= 6 ,-1 , 0
  4548.6     .05       0  4758.3     .16       0    4949      .1       0
  5002.3     .07       0  5008.3      .1       0  5284.7     .05       0
Bank Sta=5002.3,5008.3
XS Rating Curve= 0 ,0
Exp/Cntr=0.3,0.1

Type RM Length L Ch R = 1 ,6461    ,440,440,440
BEGIN DESCRIPTION:
SCHOOLHOUSE BRANCH 13.0
END DESCRIPTION:
XS GIS Cut Line= 2
      3520840.57     10438460.37      3520226.59      10437867.2
#Sta/Elev= 30
  4700.5  408.85  4861.2  403.05  4938.9  397.75  4953.1  397.18    4965   398.1
  4974.4  398.73  4981.4  392.27  4988.6  390.38  4992.5  385.69  4995.3  385.19
  4998.5  385.69  5002.7  385.98  5009.7  389.55  5016.9  390.42  5052.1  399.69
  5115.6  401.73  5122.8  400.22  5129.8  400.57    5137  397.62  5151.1  400.18
  5158.1  400.01  5186.4  404.02  5262.1  407.26  5299.6  408.66  5327.9  405.19
  5455.2  404.57  5469.4  404.78  5483.2  407.75  5497.7  409.55  5554.2  412.17
#Mann= 6 ,-1 , 0
  4700.5     .05       0    4965     .16       0  4992.5     .07       0
  4998.5     .16       0  5262.1      .1       0  5483.2     .05       0
Bank Sta=4992.5,4998.5
XS Rating Curve= 0 ,0
Exp/Cntr=0.3,0.1

Type RM Length L Ch R = 1 ,6021    ,537,537,537
BEGIN DESCRIPTION:
SCHOOLHOUSE BRANCH 12.0
END DESCRIPTION:
XS GIS Cut Line= 2
       3521080.1     10438314.48      3520482.88     10437672.12
#Sta/Elev= 30
  4478.4     407  4641.8  400.65    4677  400.53    4741  398.29  4839.7  397.94
  4871.8  396.93  4896.4  395.69  4903.7  394.61  4910.5  394.49  4917.9  393.15
  4924.7  393.62  4932.1  392.92  4938.9  393.77  4946.2  393.04  4974.1  388.11
  4981.4  385.88  4995.6  384.68  4999.4  383.25  5002.1  382.75  5005.4  383.25
  5009.7  384.18  5016.6  391.43  5023.9  395.04  5030.7   401.6  5038.1  403.18
  5059.1  405.35  5145.2   409.4  5207.6  411.49  5235.9  413.12  5355.5   415.4
#Mann= 5 ,-1 , 0
  4478.4     .05       0  4871.8     .16       0  4999.4     .07       0
  5005.4     .16       0  5145.2     .05       0
Bank Sta=4999.4,5005.4
XS Rating Curve= 0 ,0
Exp/Cntr=0.3,0.1

Type RM Length L Ch R = 1 ,5484    ,683,683,683
BEGIN DESCRIPTION:
SCHOOLHOUSE BRANCH 11.0
END DESCRIPTION:
XS GIS Cut Line= 3
       3521208.6     10438283.28      3520972.48     10437526.31
      3520847.53     10437488.13
#Sta/Elev= 30
  4436.9  408.39  4553.8   401.8  4726.2  395.35  4794.8  393.48  4805.2  392.33
  4816.1  388.31  4826.2  388.72  4836.7  391.54  4843.4  391.76  4848.6  394.09
  4857.6  393.76  4868.1  392.26  4875.9  388.19  4881.2  392.53  4908.4  385.14
  4913.7  387.11  4951.9  386.79  4962.4  386.33  5001.3  381.15    5004  380.65
  5007.3  381.15  5011.2  384.67  5025.2  387.82  5035.7  392.64  5043.7  398.92
  5048.9  398.22  5056.7  400.43  5192.8   406.7  5338.7  410.77  5360.5  410.84
#Mann= 5 ,-1 , 0
  4436.9     .05       0  4726.2     .16       0  5001.3     .07       0
  5007.3     .16       0  5338.7     .05       0
Bank Sta=5001.3,5007.3
XS Rating Curve= 0 ,0
Exp/Cntr=0.3,0.1

Type RM Length L Ch R = 1 ,4801    ,325,325,325
BEGIN DESCRIPTION:
SCHOOLHOUSE BRANCH 10.0
END DESCRIPTION:
XS GIS Cut Line= 4
      3521409.98     10438012.42      3521465.54     10437845.75
      3521274.57     10437505.48       3521132.2     10437488.11
#Sta/Elev= 30
    4635  401.92  4786.3  399.59  4805.2  396.43  4810.2  394.44  4815.9  394.44
  4830.3  392.29  4861.3  390.29  4873.6  389.78  4905.5  390.21  4911.3  390.85
  4918.6  389.99  4927.2  390.95  4970.6  389.16  4986.5  385.02  4992.3  379.75
  4995.9  377.71  4998.6  377.21  5001.9  377.71  5008.2  378.37  5013.9  380.01
  5029.9  385.87  5035.6  386.16  5051.6  389.91  5057.3  389.07  5089.2  389.04
  5094.9  389.84  5110.9  389.37  5175.9  391.61  5204.6  391.79  5344.3  399.33
#Mann= 4 ,-1 , 0
    4635     .05       0  4805.2     .16       0  4995.9     .07       0
  5001.9     .16       0
Bank Sta=4995.9,5001.9
XS Rating Curve= 0 ,0
Exp/Cntr=0.3,0.1

Type RM Length L Ch R = 1 ,4476    ,454,454,454
BEGIN DESCRIPTION:
SCHOOLHOUSE BRANCH 9.0
END DESCRIPTION:
XS GIS Cut Line= 3
      3521736.37     10437866.58      3521548.87       10437252.
      3521764.14     10436981.18
#Sta/Elev= 30
  4624.4   394.6  4726.8  394.06  4768.9  392.98    4858  389.74    4967  387.27
    4985  380.11  4996.8  376.19  4999.5  375.69  5002.8  376.19  5005.9  377.82
  5016.4  379.84  5037.8  381.48  5058.2  381.56  5070.6  383.15  5103.5  383.64
  5120.9  382.31  5136.3  382.03  5152.3  382.63  5169.1  384.98  5174.3  383.45
  5183.7  384.92  5201.9  386.28  5207.1  385.24    5215  386.42  5256.9  386.62
  5341.1  389.51  5405.1  392.44  5504.4  398.93  5554.1  400.96  5612.9  405.22
#Mann= 4 ,-1 , 0
  4624.4     .05       0  4768.9     .16       0  4996.8     .07       0
  5002.8     .16       0
Bank Sta=4996.8,5002.8
XS Rating Curve= 0 ,0
Exp/Cntr=0.3,0.1

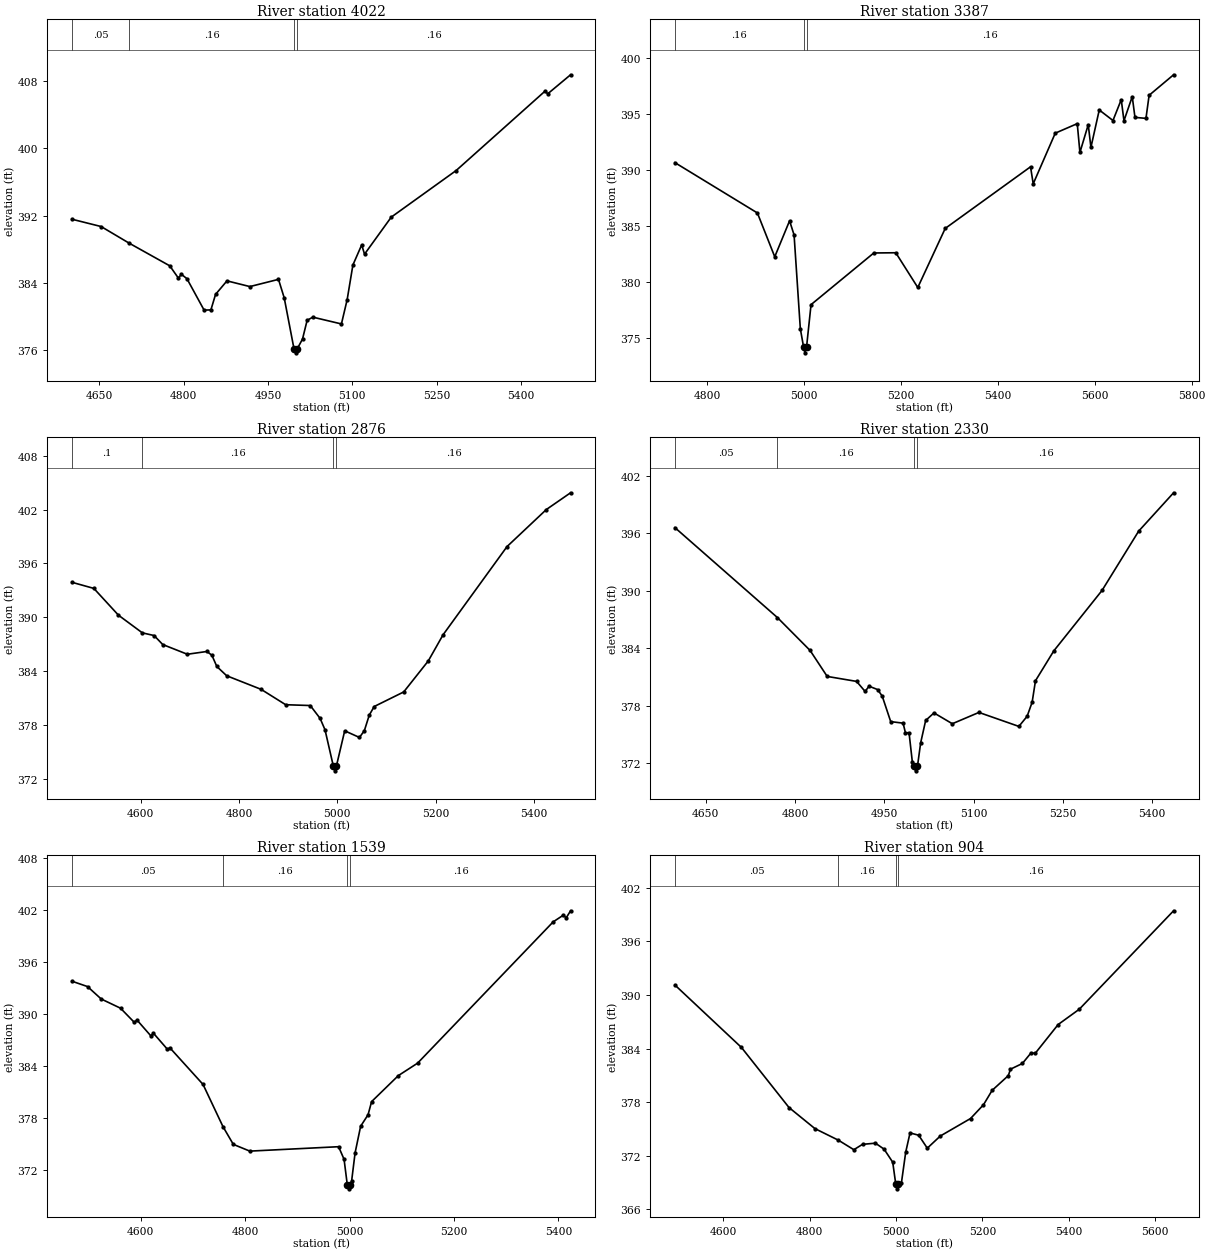
Type RM Length L Ch R = 1 ,4022    ,635,635,635
BEGIN DESCRIPTION:
SCHOOLHOUSE BRANCH 8.0
END DESCRIPTION:
XS GIS Cut Line= 2
      3521882.21     10437852.66      3522045.39      10436981.2
#Sta/Elev= 30
  4601.4  391.56  4653.3  390.69  4702.9  388.72  4775.4  386.01  4790.8  384.54
  4795.9  385.01  4805.9  384.48  4836.4  380.74  4848.5  380.76  4856.8  382.61
  4877.1  384.22  4917.8  383.54  4968.7   384.4  4978.9  382.19  4996.2  376.15
    4999  375.65  5002.2  376.15  5011.4  377.29  5019.6  379.52  5029.7   379.9
  5080.6  379.09  5090.8  381.99    5101  386.11  5116.6   388.5  5121.7   387.4
  5169.2  391.81  5284.6  397.36  5442.4   406.8  5447.5   406.5    5488  408.76
#Mann= 4 ,-1 , 0
  4601.4     .05       0  4702.9     .16       0  4996.2     .07       0
  5002.2     .16       0
Bank Sta=4996.2,5002.2
XS Rating Curve= 0 ,0
Exp/Cntr=0.3,0.1

Type RM Length L Ch R = 1 ,3387    ,511,511,511
BEGIN DESCRIPTION:
SCHOOLHOUSE BRANCH 7.0
END DESCRIPTION:
XS GIS Cut Line= 3
      3522028.04     10437922.14      3522177.34     10437873.53
      3522552.01     10437086.03
#Sta/Elev= 30
  4733.6  390.67  4903.8  386.18  4939.6  382.27  4970.2  385.48  4979.5  384.22
  4992.4  375.85  4999.2   374.2  5001.9   373.7  5005.2   374.2  5014.5     378
    5144  382.61  5189.4  382.63  5234.8  379.53  5291.4   384.8  5467.5   390.3
    5473  388.78  5518.5   393.3  5563.9  394.15  5569.4  391.58  5586.6  394.06
  5592.1  392.03  5609.3  395.37  5637.6  394.43  5654.7  396.29  5660.3  394.41
  5677.4  396.56    5683  394.71  5705.7  394.62  5712.2  396.68  5762.7  398.51
#Mann= 3 ,-1 , 0
  4733.6     .16       0  4999.2     .07       0  5005.2     .16       0
Bank Sta=4999.2,5005.2
XS Rating Curve= 0 ,0
Exp/Cntr=0.3,0.1

Type RM Length L Ch R = 1 ,2876    ,546,546,546
BEGIN DESCRIPTION:
SCHOOLHOUSE BRANCH 6.0
END DESCRIPTION:
XS GIS Cut Line= 2
      3522684.29     10438276.28      3522701.65     10437262.43
#Sta/Elev= 30
  4460.3  393.91  4504.9  393.23    4555  390.25  4603.5  388.29  4627.4  387.99
    4645  386.99    4695  385.91    4735  386.22    4745  385.79    4755  384.55
    4775  383.52    4845  382.01    4895   380.3    4945  380.21    4965  378.78
    4975  377.51    4992  373.45  4994.8  372.95    4998  373.45    5015   377.4
    5045  376.66    5055  377.42    5065  379.15    5075   380.1    5135  381.72
    5185  385.17    5215  388.07  5345.1  397.88  5425.1     402  5474.3  403.86
#Mann= 4 ,-1 , 0
  4460.3      .1       0  4603.5     .16       0    4992     .07       0
    4998     .16       0
Bank Sta=4992,4998
XS Rating Curve= 0 ,0
Exp/Cntr=0.3,0.1

Type RM Length L Ch R = 1 ,2330    ,791,791,791
BEGIN DESCRIPTION:
SCHOOLHOUSE BRANCH 5.0
END DESCRIPTION:
XS GIS Cut Line= 3
      3523342.09     10438141.62      3523092.11     10437841.64
       3522892.1     10437441.64
#Sta/Elev= 30
  4598.4  396.58  4770.7  387.18  4825.5  383.75  4854.2  381.04  4903.6  380.52
  4917.9  379.47  4924.5  380.02  4938.8  379.67  4946.6  378.99  4960.9  376.32
  4981.7  376.16  4985.6  375.16  4991.7  375.16  4997.3  372.07  4999.9  371.68
  5002.6  371.18  5005.9  371.68  5011.2   374.1  5019.6  376.44  5033.6  377.23
  5064.4   376.1  5109.1  377.28  5176.2  375.82  5190.1  376.88  5198.5  378.35
  5204.1  380.59  5234.9  383.71  5315.9  390.02  5377.4  396.21  5436.1  400.22
#Mann= 4 ,-1 , 0
  4598.4     .05       0  4770.7     .16       0  4999.9     .07       0
  5005.9     .16       0
Bank Sta=4999.9,5005.9
XS Rating Curve= 0 ,0
Exp/Cntr=0.3,0.1

Type RM Length L Ch R = 1 ,1539    ,635,635,635
BEGIN DESCRIPTION:
SCHOOLHOUSE BRANCH 3.0
END DESCRIPTION:
XS GIS Cut Line= 2
      3523646.09     10438026.31        3523344.     10437120.04
#Sta/Elev= 30
  4468.1  393.79    4498  393.17  4524.3  391.73  4561.2  390.67  4587.5  389.04
  4592.8   389.3  4619.2  387.48  4624.4  387.77  4650.8  385.94  4656.1  386.07
  4719.3  381.86  4757.5  376.98  4777.3  374.93  4808.9  374.15    4979  374.66
  4989.5   373.2  4995.6  370.29  4998.4  369.79  5001.6  370.29  5003.9  370.66
  5010.6  373.95  5021.2  377.02  5035.5  378.36  5042.2  379.87  5093.5  382.88
  5130.4  384.32  5390.1  400.65  5409.7  401.43    5415  401.11  5423.4  401.93
#Mann= 4 ,-1 , 0
  4468.1     .05       0  4757.5     .16       0  4995.6     .07       0
  5001.6     .16       0
Bank Sta=4995.6,5001.6
XS Rating Curve= 0 ,0
Exp/Cntr=0.3,0.1

Type RM Length L Ch R = 1 ,904     ,290,290,290
BEGIN DESCRIPTION:
SCHOOLHOUSE BRANCH 2.0
END DESCRIPTION:
XS GIS Cut Line= 4
      3523955.12     10437925.65      3523965.54     10437717.28
      3523934.29     10437095.75      3523632.18     10436977.69
#Sta/Elev= 30
  4487.5  391.11  4641.7  384.12  4751.8   377.4  4811.9  375.04  4866.4  373.74
    4902  372.68  4922.1  373.28  4952.1  373.41  4972.1  372.74  4992.1  371.28
  4999.2   368.8  5001.9   368.3  5005.2   368.8  5012.2  368.95  5022.2  372.41
  5032.2  374.56  5052.2   374.3  5072.2  372.85  5102.3  374.21  5172.4  376.17
  5202.4  377.71  5222.4  379.32  5259.9  380.97  5264.9  381.69  5292.5  382.33
  5312.5  383.51  5322.3  383.47  5375.4  386.69  5424.3   388.4  5642.8  399.42
#Mann= 4 ,-1 , 0
  4487.5     .05       0  4866.4     .16       0  4999.2     .07       0
  5005.2     .16       0
Bank Sta=4999.2,5005.2
XS Rating Curve= 0 ,0
Exp/Cntr=0.3,0.1

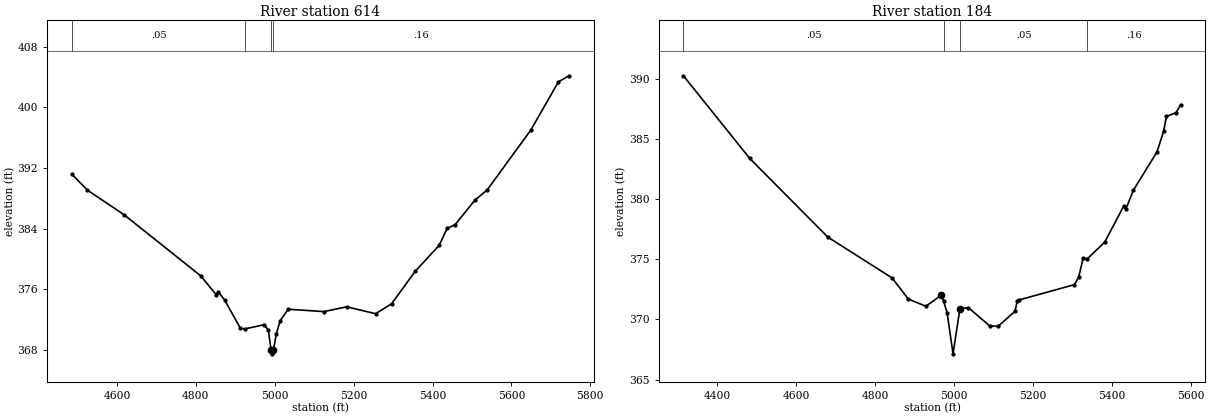
Type RM Length L Ch R = 1 ,614     ,430,430,430
BEGIN DESCRIPTION:
SCHOOLHOUSE BRANCH 1.1
END DESCRIPTION:
XS GIS Cut Line= 3
      3524125.24     10437929.12      3524253.73     10437734.64
      3524128.91     10436715.25
#Sta/Elev= 30
  4485.7   391.2    4525   389.1  4618.3  385.84  4812.5  377.79  4851.7   375.3
  4856.7  375.69  4872.9  374.61  4913.2  370.86  4925.1   370.8  4973.7  371.36
  4983.8  370.62  4990.8  368.01  4993.6  367.51  4996.8  368.01  5003.9  370.14
    5014  371.88  5034.1  373.39  5124.8  373.08  5182.5  373.71  5255.8   372.8
  5296.1  374.11  5356.5  378.41    5417  381.83  5437.1  384.06  5457.3  384.54
  5507.6  387.79  5537.9  389.08  5648.7  396.98  5719.2  403.37  5745.8  404.17
#Mann= 4 ,-1 , 0
  4485.7     .05       0  4925.1     .16       0  4990.8     .07       0
  4996.8     .16       0
Bank Sta=4990.8,4996.8
XS Rating Curve= 0 ,0
Exp/Cntr=0.3,0.1

Type RM Length L Ch R = 1 ,184     ,0,0,0
BEGIN DESCRIPTION:
SCHOOLHOUSE BRANCH 1.0
END DESCRIPTION:
XS GIS Cut Line= 3
      3524236.59     10437943.75      3524618.55     10437558.32
      3524354.67     10436891.67
#Sta/Elev= 30
  4314.8  390.28  4482.8   383.4  4680.8  376.85  4843.4  373.46  4884.6   371.7
  4929.1   371.1  4968.4  372.03  4973.8  371.56  4982.9  370.55  4997.9  367.14
  5015.2  370.87  5036.7  370.99  5090.5  369.47    5112  369.43  5154.9  370.68
  5160.3   371.5  5165.7  371.63  5305.6   372.9  5316.3  373.53  5327.8  375.13
  5337.8  375.04  5381.9  376.42  5430.6  379.45    5436   379.2  5454.9  380.76
  5514.4  383.93  5531.4  385.65  5538.7   386.9    5563  387.21  5574.4  387.87
#Mann= 4 ,-1 , 0
  4314.8     .05       0  4973.8     .03       0  5015.2     .05       0
  5337.8     .16       0
Bank Sta=4968.4,5015.2
XS Rating Curve= 0 ,0
Exp/Cntr=0.3,0.1

Chan Stop Cuts=-1
Use User Specified Reach Order=0
Composite Channel Slope=5