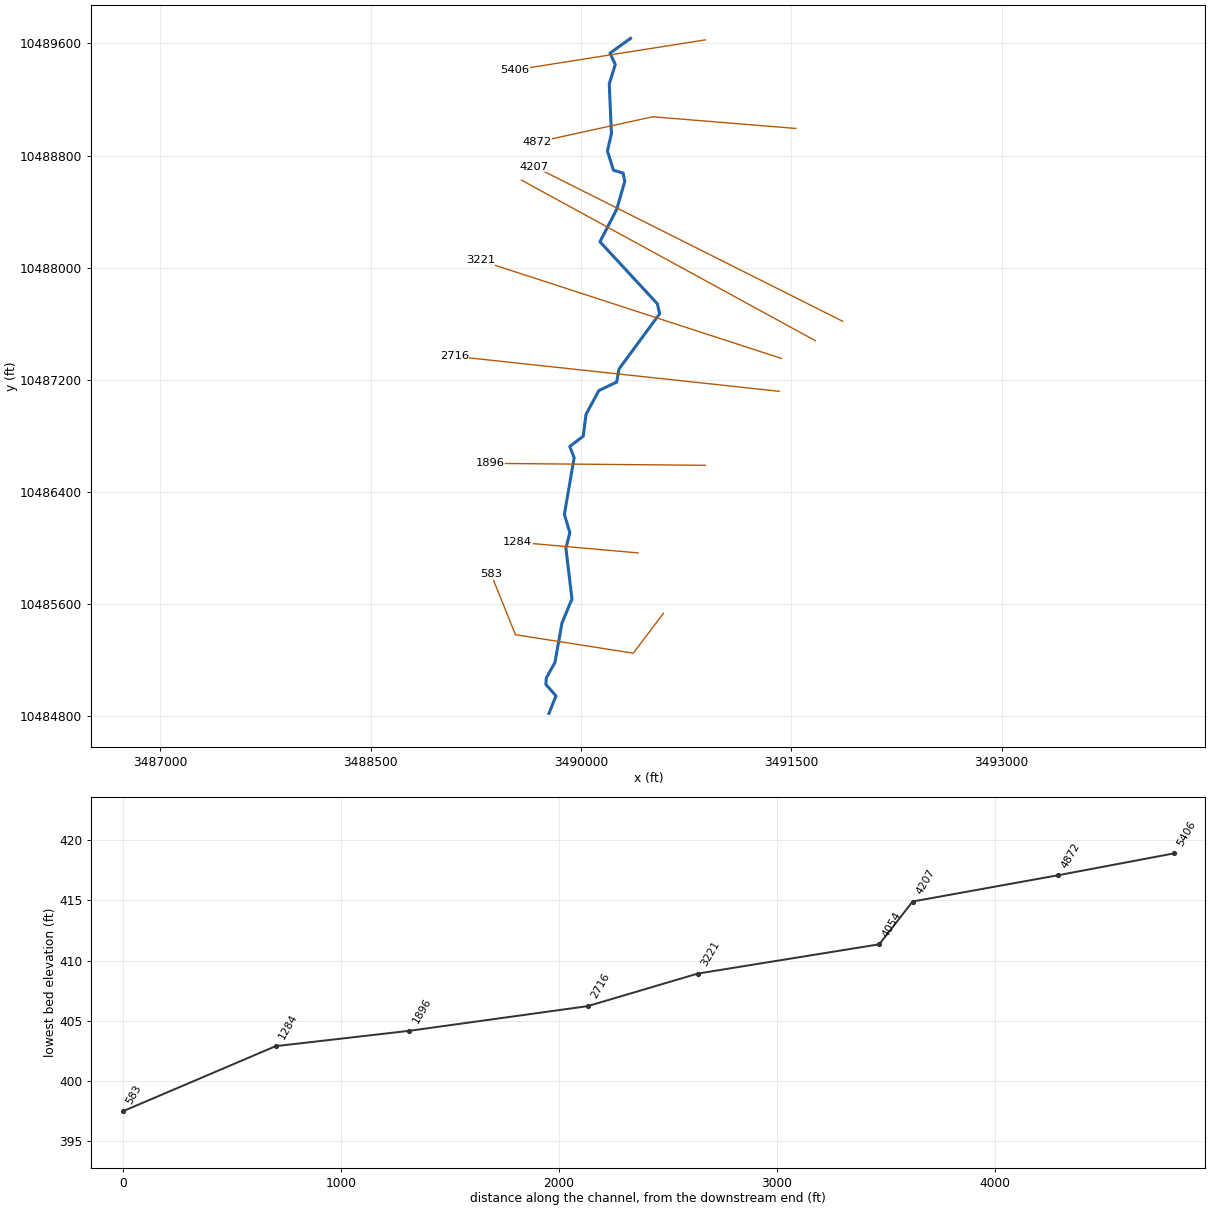
--- SCOTT BRANCH.prj (project) ---

Proj Title=SCOTT BRANCH Base Level Engineering
Current Plan=p01
Default Exp/Contr=0.3,0.1
English Units
Geom File=g01
Flow File=f01
Plan File=p01
Y Axis Title=Elevation
X Axis Title(PF)=Main Channel Distance
X Axis Title(XS)=Station
BEGIN DESCRIPTION:
SCOTT BRANCH
END DESCRIPTION:
DSS Export Rating Curves= 0
DSS Export Rating Curve Sorted= 0
DSS Export Volume Flow Curves= 0
DXF OffsetX= 0
DXF OffsetY= 0
DXF ScaleX= 1
DXF ScaleY= 10

--- SCOTT BRANCH.p01 (plan) ---

Plan Title=Multiple Run
Short Identifier=Multiple
Geom File=g01
Flow File=f01
Subcritical Flow
K Sum by GR= 0
Std Step Tol= 0.01
Critical Tol= 0.01
Num of Std Step Trials= 20
Max Error Tol= 0.3
Flow Tol Ratio= 0.001
Split Flow NTrial= 30
Split Flow Tol= 0.02
Split Flow Ratio= 0.02
Log Output Level= 0
Friction Slope Method= 1
Unsteady Friction Slope Method= 2
Unsteady Bridges Friction Slope Method= 1
Parabolic Critical Depth
Global Vel Dist=  1 , 1 , 1
Global Log Level= 0
CheckData=True
Encroach Param= -1, 0, 0, 0
BEGIN DESCRIPTION:
Multiple Run
END DESCRIPTION:

--- SCOTT BRANCH.f01 (steady flow) ---

Flow Title=Multiple
Number of Profiles=7
Profile Names=10-year,25-year,50-year,1pct_min,100-year,1pct_plu,500-year
River Rch & RM= SCOTT BRANCH,Reach-1,5406
    1231    1720    2130    1923    2601    3517    3870
Boundary for River Rch & Prof#=SCOTT BRANCH,Reach-1,1
Up Type=0
Dn Type=3
Dn Slope=0.005
Boundary for River Rch & Prof#=SCOTT BRANCH,Reach-1,2
Up Type=0
Dn Type=3
Dn Slope=0.005
Boundary for River Rch & Prof#=SCOTT BRANCH,Reach-1,3
Up Type=0
Dn Type=3
Dn Slope=0.005
Boundary for River Rch & Prof#=SCOTT BRANCH,Reach-1,4
Up Type=0
Dn Type=3
Dn Slope=0.005
Boundary for River Rch & Prof#=SCOTT BRANCH,Reach-1,5
Up Type=0
Dn Type=3
Dn Slope=0.005
Boundary for River Rch & Prof#=SCOTT BRANCH,Reach-1,6
Up Type=0
Dn Type=3
Dn Slope=0.005
Boundary for River Rch & Prof#=SCOTT BRANCH,Reach-1,7
Up Type=0
Dn Type=3
Dn Slope=0.005

--- SCOTT BRANCH.g01 (geometry) ---

Geom Title=Existing Conditions
Program Version=4.10

River Reach=SCOTT BRANCH    ,Reach-1
Reach XY= 30
      3490354.25     10489636.78      3490207.11     10489530.88
      3490244.87     10489450.15      3490201.91     10489312.13
      3490217.53     10488956.66      3490188.89     10488832.96
      3490231.85     10488696.24      3490300.86     10488675.41
      3490312.58     10488615.51       3490254.9     10488416.76
      3490135.59     10488185.56      3490545.01      10487743.3
      3490561.46      10487672.1      3490271.54     10487278.29
       3490254.9     10487184.96       3490127.7     10487124.09
       3490036.2     10486954.66      3490016.56     10486799.06
        3489920.     10486725.25       3489951.6     10486645.82
      3489881.89     10486241.62      3489920.73      10486111.3
      3489892.77     10485999.58      3489935.98     10485637.74
      3489864.46     10485465.67      3489814.42     10485184.25
      3489753.43     10485075.61      3489749.61     10485028.72
      3489821.81     10484946.63      3489772.11     10484821.64

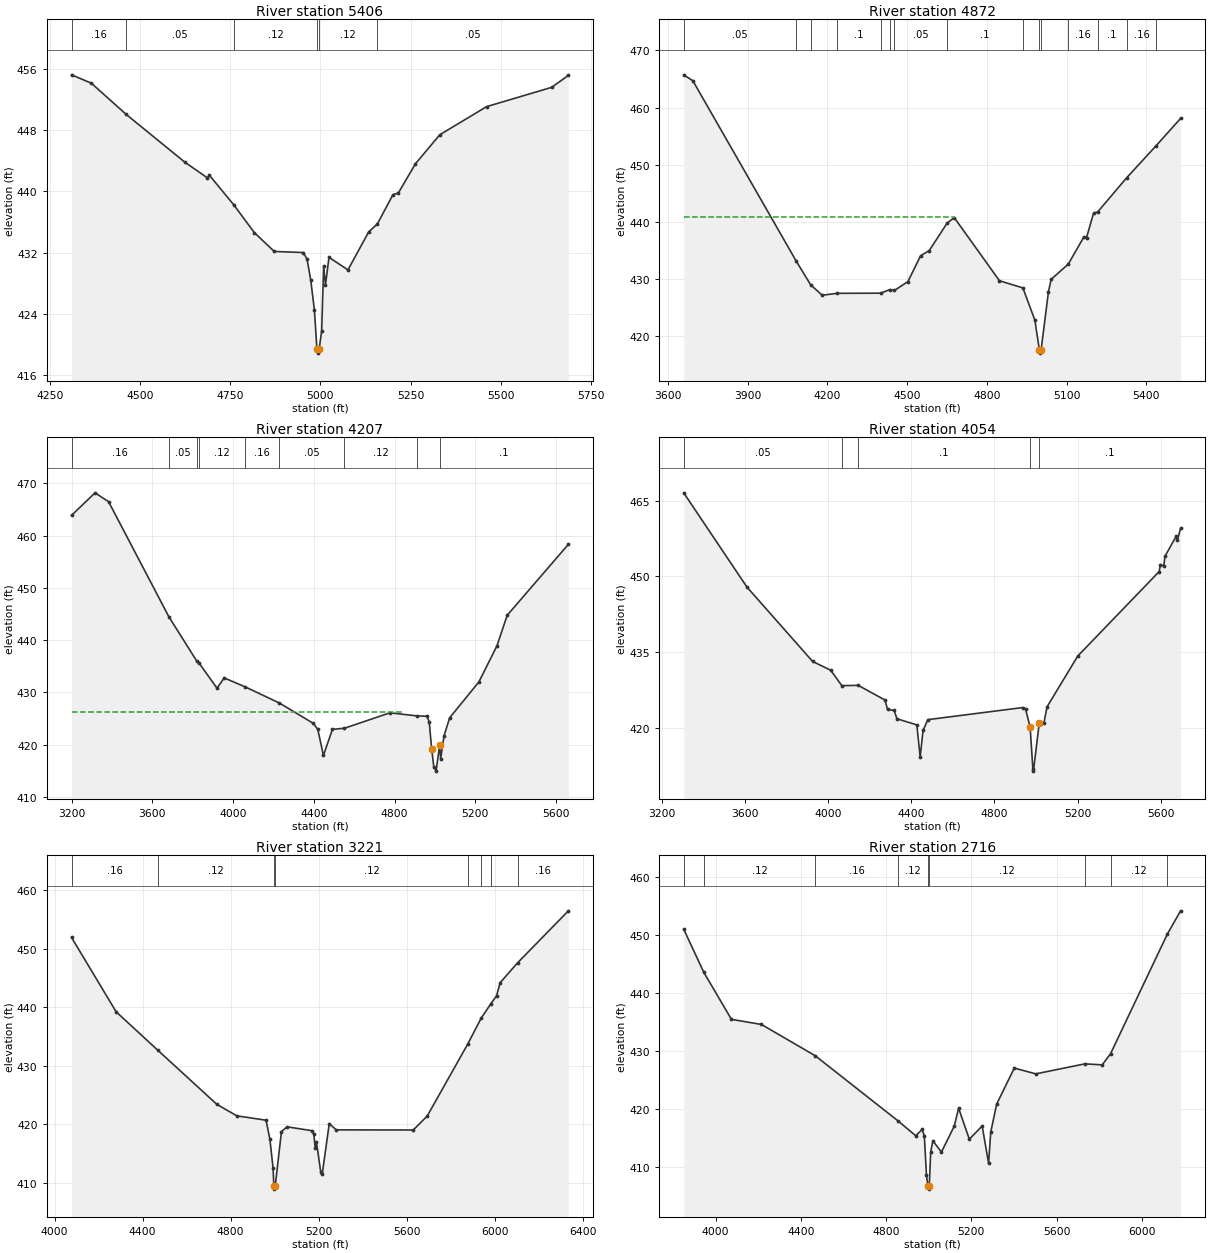
Type RM Length L Ch R = 1 ,5406    ,534,534,534
BEGIN DESCRIPTION:
SCOTT BRANCH 8.0
END DESCRIPTION:
XS GIS Cut Line= 2
      3490887.14      10489625.9      3489526.55     10489410.71
#Sta/Elev= 30
    4310  455.21    4365  454.12  4461.7  450.04  4624.6   443.8    4687  441.76
    4692  442.13  4760.1  438.23  4816.8  434.63  4871.9  432.17  4952.9  432.02
  4963.1  431.14  4973.2  428.44  4983.3  424.57  4990.4   419.4  4993.2   418.9
  4996.4   419.4  5003.5  421.75    5009   430.3  5014.1  427.79  5023.8   431.4
  5076.4  429.76  5133.8  434.71    5158  435.76  5201.2  439.58  5216.2   439.8
  5263.6  443.61    5331  447.39  5460.8  451.06  5641.4  453.58  5687.5  455.14
#Mann= 6 ,-1 , 0
    4310     .16       0  4461.7     .05       0  4760.1     .12       0
  4990.4     .07       0  4996.4     .12       0    5158     .05       0
Bank Sta=4990.4,4996.4
XS Rating Curve= 0 ,0
Exp/Cntr=0.3,0.1

Type RM Length L Ch R = 1 ,4872    ,665,665,665
BEGIN DESCRIPTION:
SCOTT BRANCH 7.0
END DESCRIPTION:
XS GIS Cut Line= 3
      3491532.95     10488993.95      3490512.12     10489077.29
      3489686.42     10488896.88
#Sta/Elev= 30
  3659.1  465.72  3693.6  464.68  4082.8  433.13  4137.1     429  4180.2   427.2
  4236.6  427.53  4400.1  427.56  4435.6  428.19  4451.9  428.03  4502.7  429.58
  4550.2  434.08    4583  435.01  4650.2   439.8  4676.9  440.77  4847.1  429.73
  4935.2  428.48  4980.2  422.86  4997.6  417.58  5000.4  417.08  5003.6  417.58
  5031.4   427.8  5041.6  429.98  5106.1  432.64  5164.4  437.36  5174.7  437.27
    5201  441.51  5216.6  441.76  5326.1  447.75  5436.9  453.35  5528.5   458.1
#Mann= 15 ,-1 , 0
  3659.1     .05       0  4082.8     .16       0  4137.1     .05       0
  4236.6      .1       0  4400.1     .05       0  4435.6      .1       0
  4451.9     .05       0  4650.2      .1       0  4935.2     .12       0
  4997.6     .07       0  5003.6     .12       0  5106.1     .16       0
  5216.6      .1       0  5326.1     .16       0  5436.9     .05       0
#XS Ineff= 2 , 0
         4677.56  440.86
Permanent Ineff=
       F       F
Bank Sta=4997.6,5003.6
XS Rating Curve= 0 ,0
Exp/Cntr=0.3,0.1

Type RM Length L Ch R = 1 ,4207    ,153,153,153
BEGIN DESCRIPTION:
SCOTT BRANCH 6.0
END DESCRIPTION:
XS GIS Cut Line= 2
      3491866.29     10487618.95      3489666.04     10488722.54
#Sta/Elev= 30
  3199.5  463.86  3316.1  468.18  3383.2  466.48  3682.2  444.43  3820.3  435.96
  3831.5   435.6  3920.2  430.78    3956  432.75  4059.6  431.04  4229.2  427.95
  4397.2  424.06  4419.6   422.9  4447.5  417.92  4492.2  422.91  4551.4  423.12
    4777  426.07  4911.8  425.48  4961.3  425.42  4971.8  424.25  4983.6  419.21
  4994.2  415.74  5005.7  414.91  5023.3  419.91  5028.3  417.26  5045.1  421.69
    5073  425.12  5217.9     432  5307.4  438.91  5357.8  444.74    5661  458.32
#Mann= 9 ,-1 , 0
  3199.5     .16       0  3682.2     .05       0  3820.3     .16       0
  3831.5     .12       0  4059.6     .16       0  4229.2     .05       0
  4551.4     .12       0  4911.8     .05       0  5023.3      .1       0
#XS Ineff= 2 , 0
         4837.21  426.23
Permanent Ineff=
       F       F
Bank Sta=4983.6,5023.3
XS Rating Curve= 0 ,0
Exp/Cntr=0.3,0.1

Type RM Length L Ch R = 1 ,4054    ,833,833,833
BEGIN DESCRIPTION:
Mapping XS 16874b23
END DESCRIPTION:
XS GIS Cut Line= 2
      3491671.81     10487480.08      3489575.84     10488625.23
#Sta/Elev= 30
  3306.2  466.57  3609.9  447.89  3925.8  433.12  4013.1  431.37  4066.1  428.32
  4145.2  428.37    4274  425.46  4285.9  423.59  4317.7  423.41  4331.4  421.75
  4426.8  420.53  4442.9  414.17  4456.8  419.42  4479.6  421.57  4935.4  423.97
  4949.6  423.63  4971.4  420.11  4984.5  411.86  4987.3  411.36  5015.1  420.86
  5037.9  420.96    5053  424.13  5200.1  434.18  5591.9  450.96  5597.6  452.35
  5613.8  452.05  5619.5  453.97  5673.5  457.96  5679.2  457.18  5694.6   459.5
#Mann= 5 ,-1 , 0
  3306.2     .05       0  4066.1     .16       0  4145.2      .1       0
  4971.4     .05       0  5015.1      .1       0
Bank Sta=4971.4,5015.1
XS Rating Curve= 0 ,0
Exp/Cntr=0.3,0.1

Type RM Length L Ch R = 1 ,3221    ,505,505,505
BEGIN DESCRIPTION:
Mapping XS aee17f99
END DESCRIPTION:
XS GIS Cut Line= 2
      3491429.91     10487353.63      3489281.49     10488052.41
#Sta/Elev= 30
  4076.5  451.95  4279.7  439.23  4470.1  432.63  4737.4  423.42    4828  421.46
    4961  420.71  4978.5  417.46  4992.9  412.57  4996.6  409.43  4999.3  408.93
  5002.6  409.43  5031.1  418.76  5056.8  419.58  5167.8  418.93  5178.3  418.32
  5184.5  415.94  5189.8  417.07  5209.9  411.81  5216.5  411.54  5248.4  420.11
  5280.4  419.06  5630.5  419.04  5693.6  421.41  5877.6  433.69  5939.2  438.15
  5982.9   440.6  6009.1  441.97  6025.5  444.22  6105.2  447.63  6335.7   456.5
#Mann= 8 ,-1 , 0
  4076.5     .16       0  4470.1     .12       0  4996.6     .07       0
  5002.6     .12       0  5877.6     .05       0  5939.2     .16       0
  5982.9     .05       0  6105.2     .16       0
Bank Sta=4996.6,5002.6
XS Rating Curve= 0 ,0
Exp/Cntr=0.3,0.1

Type RM Length L Ch R = 1 ,2716    ,820,820,820
BEGIN DESCRIPTION:
SCOTT BRANCH 5.0
END DESCRIPTION:
XS GIS Cut Line= 2
      3491414.87     10487118.95       3489096.3     10487368.86
#Sta/Elev= 30
    3850  450.95    3944  443.55  4074.1  435.44  4214.9  434.56  4467.7  429.17
  4854.8     418    4939  415.42  4969.2  416.49  4979.3  415.39  4989.3   408.7
  4996.4  406.73  4999.1  406.23  5002.4  406.73  5009.4  412.68  5019.5  414.54
  5059.7  412.61  5120.1  417.09  5140.2  420.17  5190.5  414.82  5250.8  417.09
    5281  410.67  5291.1  416.04  5318.8  420.85  5401.7  427.06  5502.3  426.06
  5732.8  427.78  5814.1  427.61  5853.3  429.52  6119.7  450.09    6182  454.11
#Mann= 9 ,-1 , 0
    3850     .16       0    3944     .12       0  4467.7     .16       0
  4854.8     .12       0  4996.4     .07       0  5002.4     .12       0
  5732.8     .16       0  5853.3     .12       0  6119.7     .16       0
Bank Sta=4996.4,5002.4
XS Rating Curve= 0 ,0
Exp/Cntr=0.3,0.1

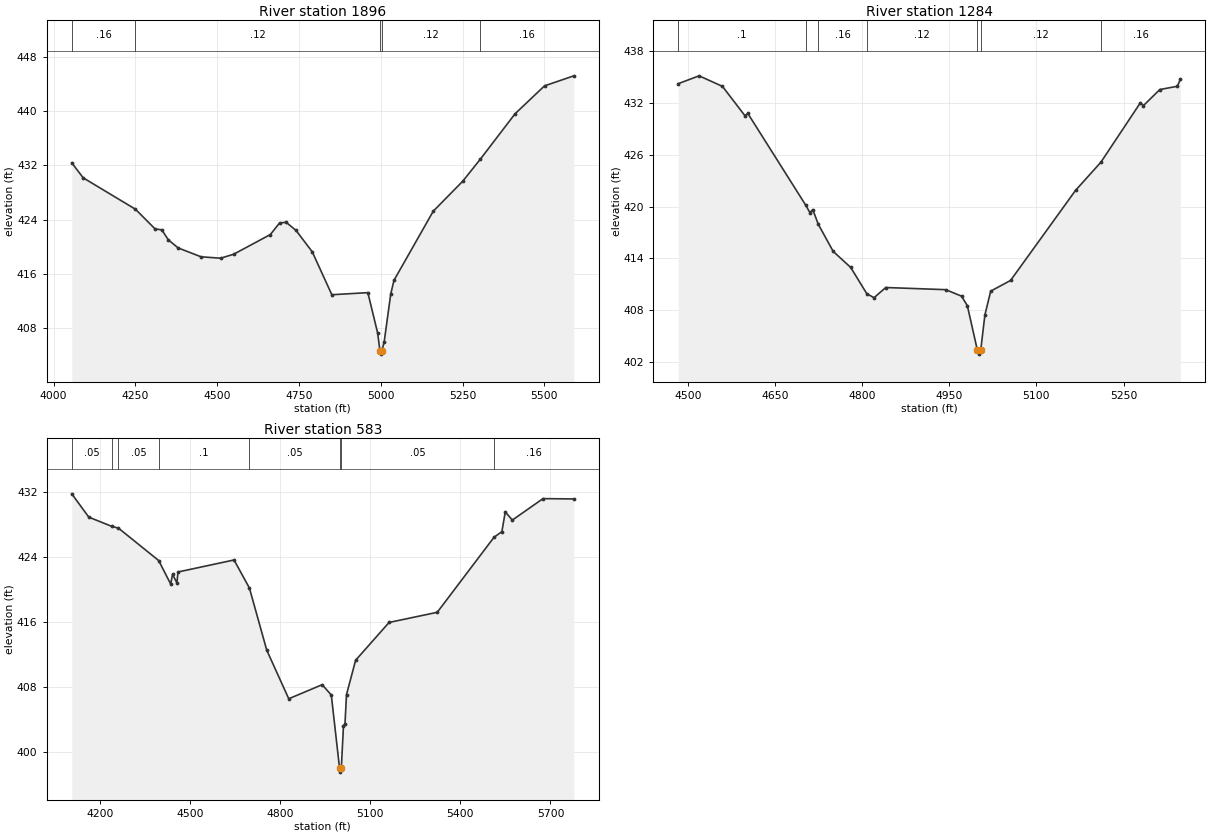
Type RM Length L Ch R = 1 ,1896    ,612,612,612
BEGIN DESCRIPTION:
SCOTT BRANCH 4.0
END DESCRIPTION:
XS GIS Cut Line= 2
      3490887.08     10486591.17      3489352.44     10486605.06
#Sta/Elev= 30
  4055.6  432.36  4090.6  430.15  4250.2  425.53  4310.6  422.61  4330.6   422.5
  4350.6  421.03  4380.6  419.83  4450.6  418.52  4510.6  418.31  4550.6   418.9
  4662.7   421.8  4690.6  423.49  4710.6  423.61  4740.6  422.43  4790.6  419.26
  4850.6  412.93  4960.6  413.24  4990.6  407.29  4997.6  404.68  5000.4  404.18
  5003.6  404.68  5010.6  406.01  5030.6  413.04  5040.6  415.06  5160.6  425.24
  5250.6  429.65  5304.8  432.92  5410.6  439.59  5500.6   443.7  5590.3  445.18
#Mann= 5 ,-1 , 0
  4055.6     .16       0  4250.2     .12       0  4997.6     .07       0
  5003.6     .12       0  5304.8     .16       0
Bank Sta=4997.6,5003.6
XS Rating Curve= 0 ,0
Exp/Cntr=0.3,0.1

Type RM Length L Ch R = 1 ,1284    ,701,701,701
BEGIN DESCRIPTION:
SCOTT BRANCH 3.0
END DESCRIPTION:
XS GIS Cut Line= 2
       3490407.9     10485966.18      3489546.98     10486042.55
#Sta/Elev= 30
  4483.5  434.25  4519.4  435.16  4559.6  433.94  4598.3  430.54  4603.3   430.8
  4702.6  420.21  4710.1  419.32  4715.1  419.66  4724.5  417.97  4750.3  414.81
  4780.5  412.95  4808.1  409.91  4820.6  409.45  4840.7  410.63  4943.8  410.38
  4971.2  409.63  4981.2  408.52  4998.3  403.41  5001.1  402.91  5004.3  403.41
  5011.4  407.45  5021.4  410.21  5055.6  411.45  5167.4  421.88  5211.2  425.16
  5279.2  432.05  5284.2   431.7  5312.5  433.57  5342.7  433.95  5347.8  434.74
#Mann= 7 ,-1 , 0
  4483.5      .1       0  4702.6     .05       0  4724.5     .16       0
  4808.1     .12       0  4998.3     .07       0  5004.3     .12       0
  5211.2     .16       0
Bank Sta=4998.3,5004.3
XS Rating Curve= 0 ,0
Exp/Cntr=0.3,0.1

Type RM Length L Ch R = 1 ,583     ,0,0,0
BEGIN DESCRIPTION:
SCOTT BRANCH 1.0
END DESCRIPTION:
XS GIS Cut Line= 4
      3490588.51     10485535.62      3490373.23      10485250.9
      3489532.95     10485382.84      3489359.33     10485813.43
#Sta/Elev= 30
  4106.1  431.76  4162.8  428.89  4239.7  427.75  4261.5  427.54  4395.5  423.55
  4435.4  420.66  4441.7  421.85  4456.2   420.8  4459.8  422.14  4646.4  423.62
  4697.6  420.17  4755.3  412.52  4828.6  406.54  4939.9  408.27  4970.3     407
  4997.7  398.01  5000.4  397.51  5003.7  398.01  5010.8   403.2  5015.8  403.43
  5020.9  407.06  5051.3  411.28  5162.6  415.93  5323.1  417.18    5512  426.41
  5538.3  427.11  5549.5  429.53  5573.2  428.53  5675.2  431.17  5777.9  431.13
#Mann= 8 ,-1 , 0
  4106.1     .05       0  4239.7      .1       0  4261.5     .05       0
  4395.5      .1       0  4697.6     .05       0  4997.7    .035       0
  5003.7     .05       0    5512     .16       0
Bank Sta=4997.7,5003.7
XS Rating Curve= 0 ,0
Exp/Cntr=0.3,0.1

Chan Stop Cuts=-1
Use User Specified Reach Order=0
Composite Channel Slope=5