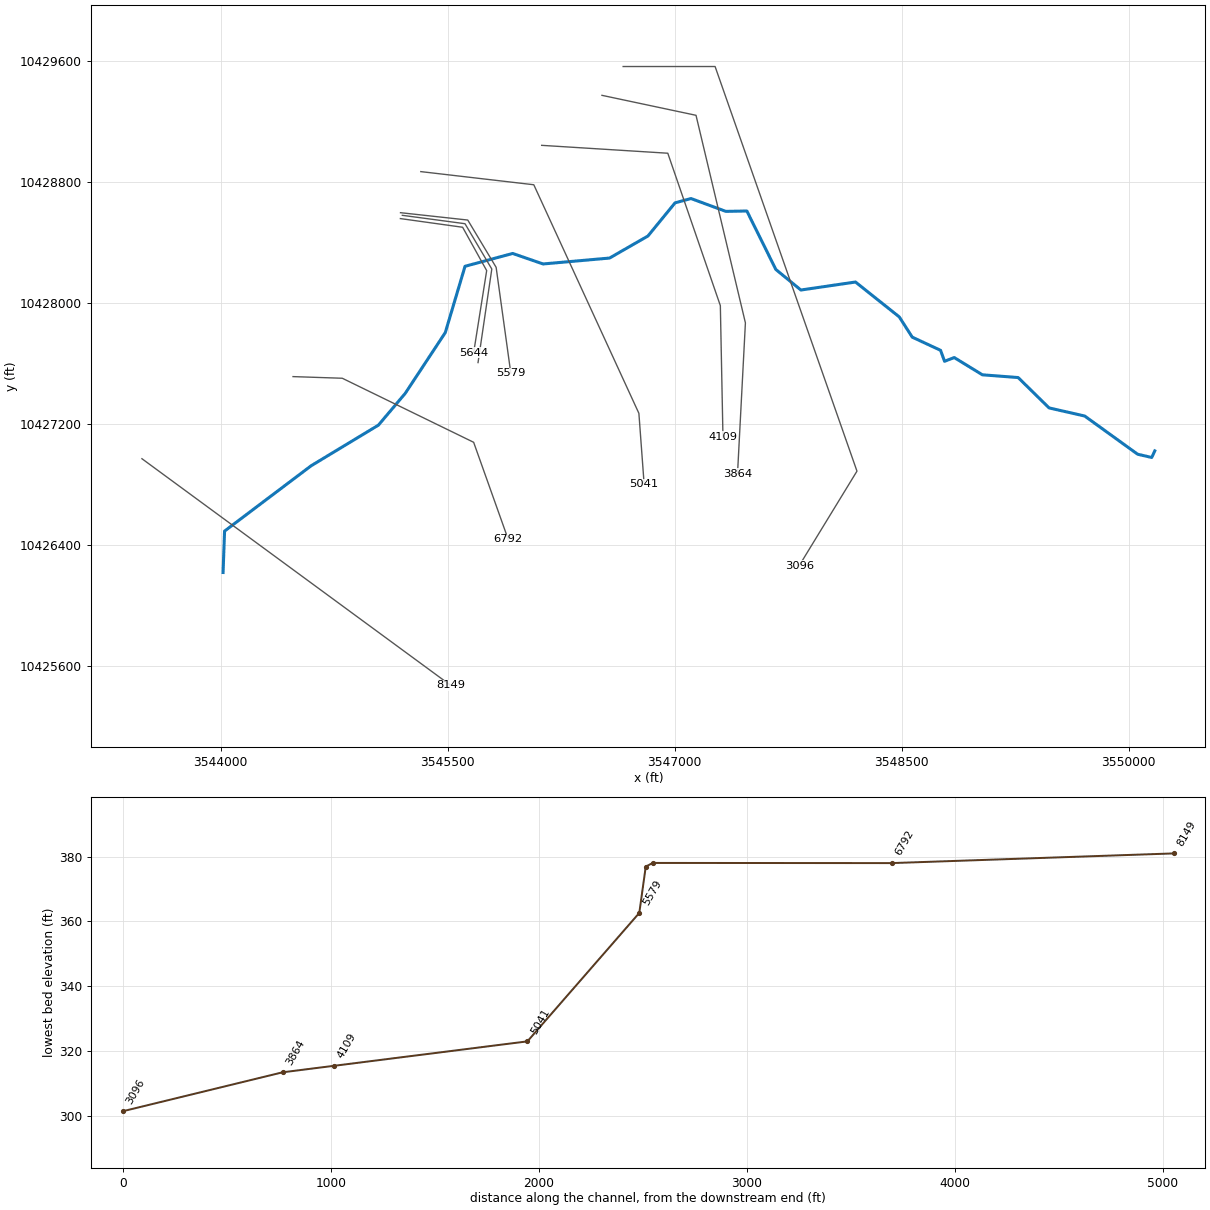
--- SHOP BRANCH.prj (project) ---

Proj Title=SHOP BRANCH Base Level Engineering
Current Plan=p01
Default Exp/Contr=0.3,0.1
English Units
Geom File=g01
Flow File=f01
Plan File=p01
Y Axis Title=Elevation
X Axis Title(PF)=Main Channel Distance
X Axis Title(XS)=Station
BEGIN DESCRIPTION:
SHOP BRANCH
END DESCRIPTION:
DSS Export Rating Curves= 0
DSS Export Rating Curve Sorted= 0
DSS Export Volume Flow Curves= 0
DXF OffsetX= 0
DXF OffsetY= 0
DXF ScaleX= 1
DXF ScaleY= 10

--- SHOP BRANCH.p01 (plan) ---

Plan Title=Multiple Run
Short Identifier=Multiple
Geom File=g01
Flow File=f01
Subcritical Flow
K Sum by GR= 0
Std Step Tol= 0.01
Critical Tol= 0.01
Num of Std Step Trials= 20
Max Error Tol= 0.3
Flow Tol Ratio= 0.001
Split Flow NTrial= 30
Split Flow Tol= 0.02
Split Flow Ratio= 0.02
Log Output Level= 0
Friction Slope Method= 1
Unsteady Friction Slope Method= 2
Unsteady Bridges Friction Slope Method= 1
Parabolic Critical Depth
Global Vel Dist=  1 , 1 , 1
Global Log Level= 0
CheckData=True
Encroach Param= -1, 0, 0, 0
BEGIN DESCRIPTION:
Multiple Run
END DESCRIPTION:

--- SHOP BRANCH.f01 (steady flow) ---

Flow Title=Multiple
Number of Profiles=7
Profile Names=10-year,25-year,50-year,1pct_min,100-year,1pct_plu,500-year
River Rch & RM= SHOP BRANCH,Reach-1,8149
    1068    1486    1835    1656    2239    3028    3322
Boundary for River Rch & Prof#=SHOP BRANCH,Reach-1,1
Up Type=0
Dn Type=3
Dn Slope=0.005
Boundary for River Rch & Prof#=SHOP BRANCH,Reach-1,2
Up Type=0
Dn Type=3
Dn Slope=0.005
Boundary for River Rch & Prof#=SHOP BRANCH,Reach-1,3
Up Type=0
Dn Type=3
Dn Slope=0.005
Boundary for River Rch & Prof#=SHOP BRANCH,Reach-1,4
Up Type=0
Dn Type=3
Dn Slope=0.005
Boundary for River Rch & Prof#=SHOP BRANCH,Reach-1,5
Up Type=0
Dn Type=3
Dn Slope=0.005
Boundary for River Rch & Prof#=SHOP BRANCH,Reach-1,6
Up Type=0
Dn Type=3
Dn Slope=0.005
Boundary for River Rch & Prof#=SHOP BRANCH,Reach-1,7
Up Type=0
Dn Type=3
Dn Slope=0.005

--- SHOP BRANCH.g01 (geometry) ---

Geom Title=Existing Conditions
Program Version=4.10

River Reach=SHOP BRANCH     ,Reach-1
Reach XY= 30
      3544015.74     10426218.01      3544025.65     10426491.63
      3544597.92      10426923.4      3545042.11     10427191.64
      3545219.24     10427401.42      3545483.98     10427803.02
      3545614.55     10428241.26      3545929.42     10428326.11
      3546130.16     10428256.66      3546569.61     10428295.73
      3546822.98     10428441.25      3547002.41     10428660.59
      3547107.51     10428689.02      3547337.65     10428604.25
      3547476.78     10428606.59      3547668.15     10428220.45
      3547833.58     10428084.53      3548194.51     10428137.35
      3548483.79     10427906.92      3548569.54     10427773.07
      3548756.62     10427686.08      3548783.05     10427613.59
      3548847.01     10427638.24      3549033.16     10427524.22
      3549269.27     10427506.16      3549473.62      10427305.5
      3549708.94     10427252.02      3550058.78     10426999.49
      3550152.04     10426978.01      3550172.11     10427021.64

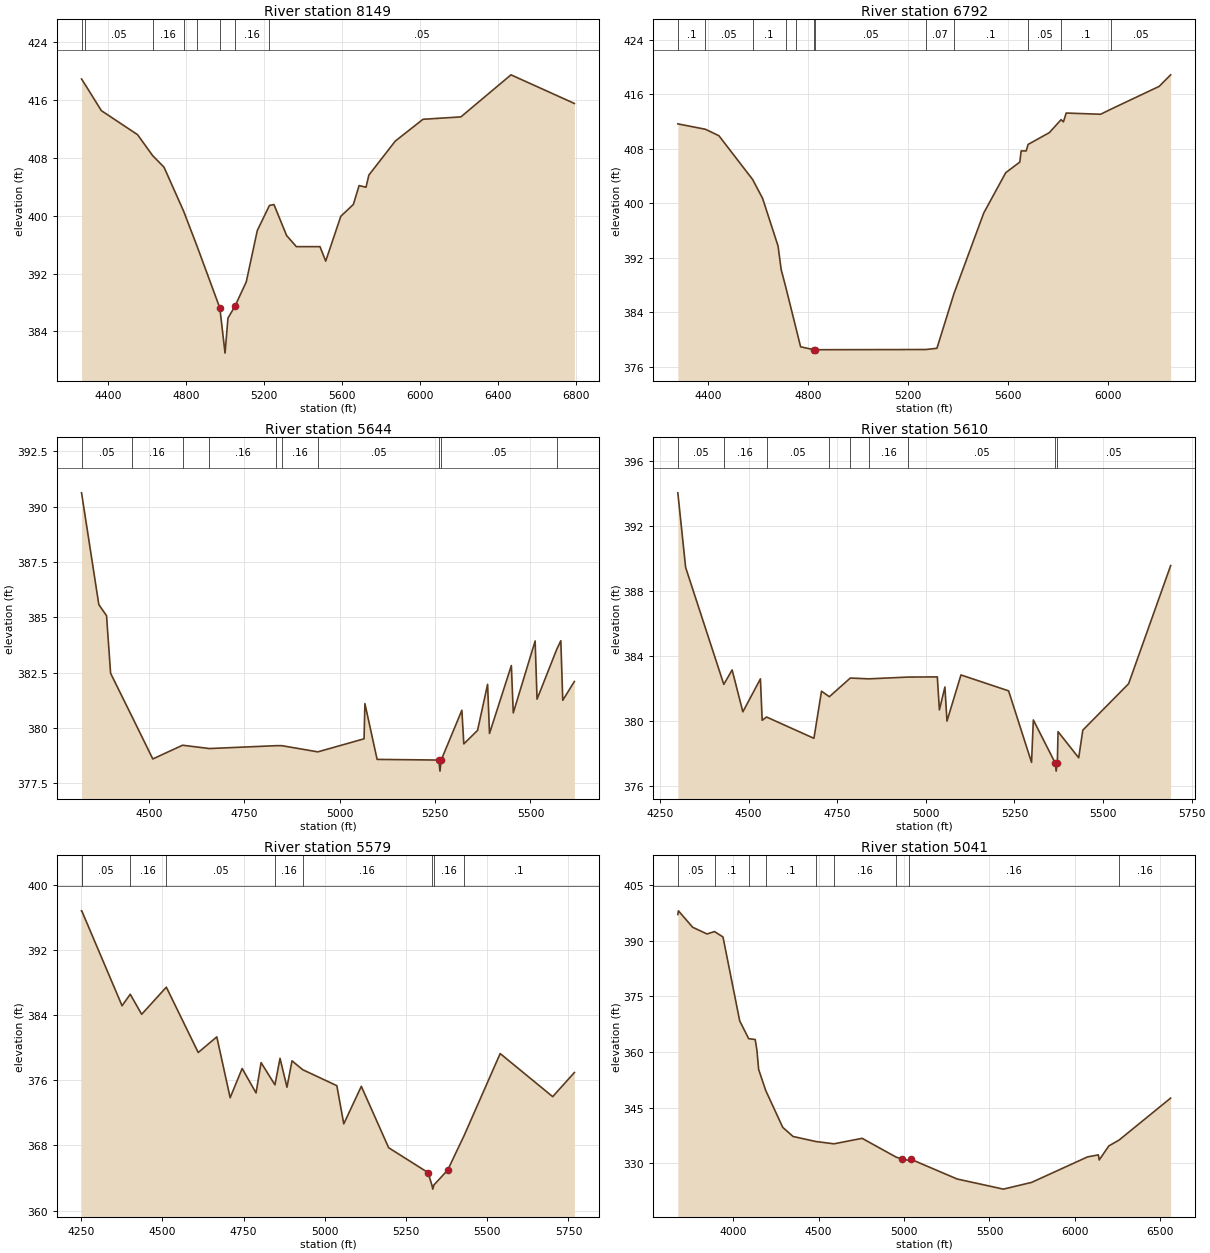
Type RM Length L Ch R = 1 ,8149    ,1357,1357,1357
BEGIN DESCRIPTION:
SHOP BRANCH 16.0
END DESCRIPTION:
XS GIS Cut Line= 2
       3543479.6     10426969.85      3545518.31     10425473.35
#Sta/Elev= 30
  4264.2  418.91    4284  418.08  4365.7  414.54  4551.7  411.21  4628.9  408.32
  4687.5  406.71  4787.8  400.64  4858.8  395.65  4973.8  387.24  5000.6  380.99
  5015.5  385.84    5051  387.45  5109.6  390.86    5166  397.95  5228.4  401.42
  5251.6  401.54  5316.5  397.26  5366.6  395.72  5487.8  395.72  5517.1  393.72
  5594.6  399.92  5659.1  401.56  5688.4  404.17  5723.9  403.94  5738.6  405.62
  5874.4  410.33  6016.4  413.34  6210.9  413.67  6467.9  419.49  6793.2  415.53
#Mann= 8 ,-1 , 0
  4264.2     .16       0    4284     .05       0  4628.9     .16       0
  4787.8     .07       0  4858.8     .16       0  4973.8     .05       0
    5051     .16       0  5228.4     .05       0
Bank Sta=4973.8,5051
XS Rating Curve= 0 ,0
Exp/Cntr=0.3,0.1

Type RM Length L Ch R = 1 ,6792    ,1148,1148,1148
BEGIN DESCRIPTION:
SHOP BRANCH 13.0
END DESCRIPTION:
XS GIS Cut Line= 4
      3544477.91     10427512.36      3544803.41     10427501.51
      3545671.46     10427078.34      3545899.32     10426438.17
#Sta/Elev= 30
    4280  411.66  4390.1  410.87  4444.3  409.92  4579.2  403.49  4618.9  400.73
  4680.9  393.72  4693.2  390.28  4711.5  387.72  4754.2  381.42    4771  378.93
  4824.2   378.5    4827     378  4830.2   378.5  5272.1  378.53  5316.2  378.71
  5384.2  386.73  5503.3  398.56  5591.3  404.49  5647.7  406.05    5653  407.69
  5673.2  407.68  5680.8  408.64  5765.7  410.37  5812.8  412.28  5822.1  411.95
  5833.2  413.25  5970.9  413.07  6012.3  413.82  6204.8  417.16  6250.9  418.86
#Mann= 12 ,-1 , 0
    4280      .1       0  4390.1     .05       0  4579.2      .1       0
  4711.5     .16       0  4754.2     .05       0  4824.2    .033       0
  4830.2     .05       0  5272.1     .07       0  5384.2      .1       0
  5680.8     .05       0  5812.8      .1       0  6012.3     .05       0
Bank Sta=4824.2,4830.2
XS Rating Curve= 0 ,0
Exp/Cntr=0.3,0.1

Type RM Length L Ch R = 1 ,5644    ,34,34,34
BEGIN DESCRIPTION:
SHOP BRANCH 12.0
END DESCRIPTION:
XS GIS Cut Line= 4
      3545187.23     10428556.51      3545598.69     10428499.22
      3545757.55     10428212.76      3545671.61     10427671.12
#Sta/Elev= 30
  4323.7  390.62    4369  385.57  4389.2  385.07  4399.8  382.47  4456.3   380.5
  4510.4   378.6  4588.4  379.22  4658.8  379.07  4834.3   379.2  4848.5   379.2
  4942.9  378.92    5064  379.51  5066.2   381.1  5098.2  378.58  5260.1  378.55
  5262.9  378.05  5266.1  378.55  5320.3   380.8  5325.4  379.28  5361.4  379.89
  5387.7  381.97  5392.7  379.75    5450  382.82    5455  380.68  5512.3  383.93
  5517.3   381.3  5568.9  383.55  5579.6  383.94  5584.7  381.25  5615.1   382.1
#Mann= 10 ,-1 , 0
  4323.7     .05       0  4456.3     .16       0  4588.4     .05       0
  4658.8     .16       0  4834.3     .05       0  4848.5     .16       0
  4942.9     .05       0  5260.1    .033       0  5266.1     .05       0
  5568.9      .1       0
Bank Sta=5260.1,5266.1
XS Rating Curve= 0 ,0
Exp/Cntr=0.3,0.1

Type RM Length L Ch R = 1 ,5610    ,31,31,31
BEGIN DESCRIPTION:
SHOP BRANCH 11.0
END DESCRIPTION:
XS GIS Cut Line= 4
      3545200.25     10428578.12      3545614.32     10428522.65
       3545791.4     10428223.18      3545700.49       10427605.
#Sta/Elev= 30
  4300.2  394.06  4322.2  389.47  4429.9  382.27  4453.4  383.16  4483.7  380.58
  4533.2  382.61  4538.2  380.06  4550.6  380.26  4684.2  378.95  4705.6  381.85
  4727.7  381.51  4786.8  382.66  4839.1  382.61  4950.6  382.72  5032.4  382.73
  5038.2   380.7  5053.8  382.11  5059.6  380.01  5099.1  382.85  5233.5  381.87
  5298.2  377.47  5303.3  380.08    5365  377.43  5367.7  376.93    5371  377.43
    5373  379.36  5431.3  377.75  5442.8  379.45  5572.1  382.31  5690.7  389.58
#Mann= 9 ,-1 , 0
  4300.2     .05       0  4429.9     .16       0  4550.6     .05       0
  4727.7     .16       0  4786.8     .05       0  4839.1     .16       0
  4950.6     .05       0    5365     .04       0    5371     .05       0
Bank Sta=5365,5371
XS Rating Curve= 0 ,0
Exp/Cntr=0.3,0.1

Type RM Length L Ch R = 1 ,5579    ,538,538,538
BEGIN DESCRIPTION:
SHOP BRANCH 10.0
END DESCRIPTION:
XS GIS Cut Line= 4
      3545188.13     10428595.48      3545632.55     10428546.87
      3545820.05     10428234.37      3545916.94     10427535.36
#Sta/Elev= 30
    4251  396.79  4251.6  396.79  4375.7  385.14  4400.9  386.55  4436.1  384.09
    4512  387.42  4610.2   379.4  4667.4  381.32  4708.5  373.85  4745.4  377.44
  4788.2  374.44  4803.7  378.16  4846.4  375.43    4862  378.69  4883.4  375.14
  4898.9  378.38  4931.8  377.29  5036.9  375.33  5058.3  370.64  5112.3  375.25
  5196.5  367.71  5317.7  364.66  5329.6  363.13  5332.4  362.63  5335.6  363.13
  5378.2  364.97  5428.7   369.2  5539.8  379.27  5701.5  373.98  5768.2  376.94
#Mann= 9 ,-1 , 0
    4251      .1       0  4251.6     .05       0  4400.9     .16       0
    4512     .05       0  4846.4     .16       0  4931.8     .16       0
  5329.6     .12       0  5335.6     .16       0  5428.7      .1       0
Bank Sta=5317.7,5378.2
XS Rating Curve= 0 ,0
Exp/Cntr=0.3,0.1

Type RM Length L Ch R = 1 ,5041    ,932,932,932
BEGIN DESCRIPTION:
SHOP BRANCH 9.0
END DESCRIPTION:
XS GIS Cut Line= 4
      3545322.32      10428866.9      3546068.89     10428780.09
      3546763.33     10427269.67      3546798.06     10426800.87
#Sta/Elev= 30
  3676.1  397.06  3679.6  398.04  3763.2   393.6  3846.8   391.8  3890.8  392.45
  3940.4  390.99  4038.3  368.35  4090.7  363.56  4128.9  363.34    4139  360.43
  4149.1  355.26  4190.6  349.58    4290  339.65  4350.4  337.19  4483.7  335.83
  4590.3  335.21  4754.6  336.69  4954.9  331.59  4987.3  331.18  5031.3  330.69
  5041.3  331.02  5310.6  325.72  5581.4  322.99  5746.8  324.81  6073.3  331.67
  6137.2  332.23  6142.2  330.85  6198.4  334.64  6258.6  336.23  6560.2  347.54
#Mann= 9 ,-1 , 0
  3676.1     .05       0  3890.8      .1       0  4090.7     .05       0
  4190.6      .1       0  4483.7     .05       0  4590.3     .16       0
  4954.9    .012       0  5031.3     .16       0  6258.6     .16       0
#Block Obstruct= 2 , 0
                         5067.92          330.17
Bank Sta=4987.3,5041.3
XS Rating Curve= 0 ,0
Exp/Cntr=0.3,0.1

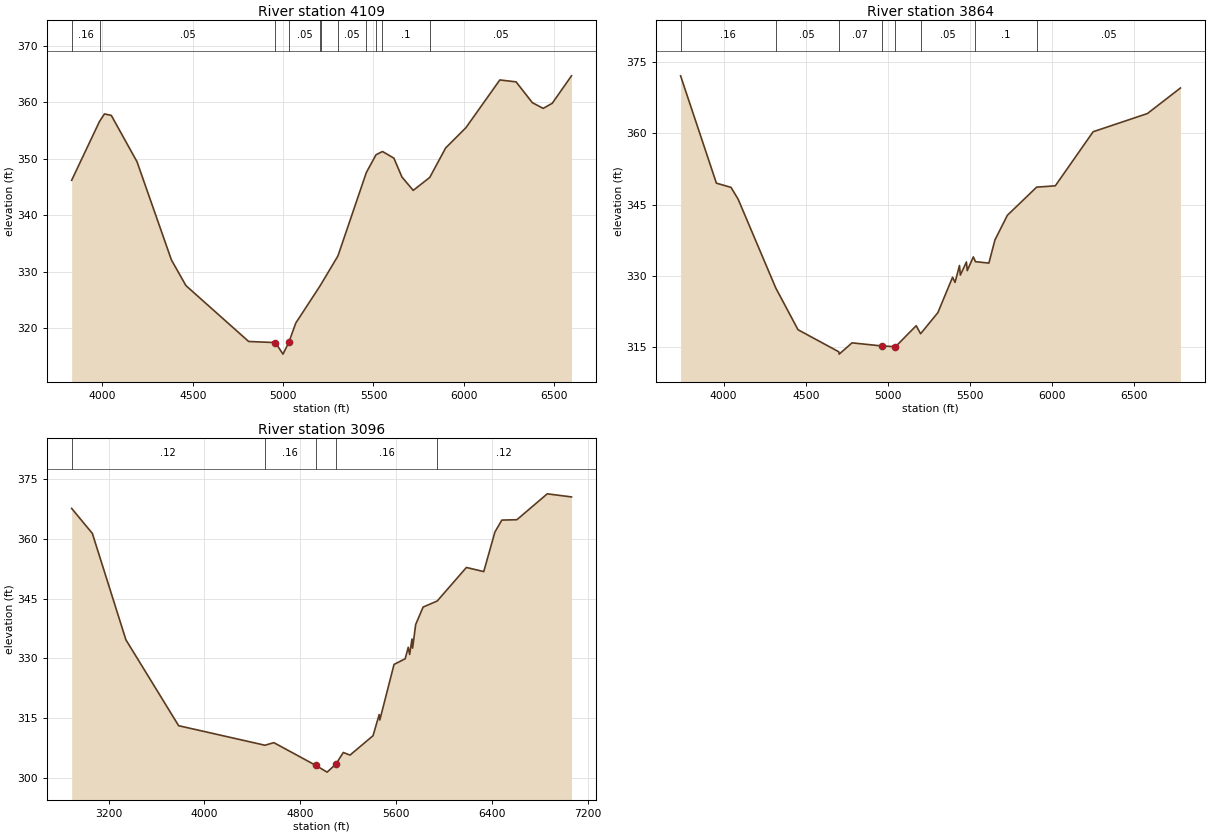
Type RM Length L Ch R = 1 ,4109    ,245,245,245
BEGIN DESCRIPTION:
SHOP BRANCH 6.0
END DESCRIPTION:
XS GIS Cut Line= 4
      3546120.94     10429040.51      3546954.31     10428988.42
      3547301.53     10427981.48      3547318.86     10427115.07
#Sta/Elev= 30
  3829.3  346.19  3983.5   356.6  4010.8  357.93  4048.7  357.67  4191.2  349.46
  4381.5   332.1  4461.7  327.56    4809  317.67  4957.1  317.47  4999.1  315.43
  5031.1  317.49  5069.9  320.93  5206.6  327.62  5207.4  327.67  5303.2   332.8
  5460.4  347.56  5513.9   350.7  5549.8  351.28  5612.9  350.11  5657.5  346.77
  5719.9   344.4  5811.6   346.7  5899.3   351.9  6011.3  355.48  6199.3  363.94
  6289.4   363.6  6379.4  359.92  6439.4  358.91  6489.4  359.81    6596  364.67
#Mann= 11 ,-1 , 0
  3829.3     .16       0  3983.5     .05       0  4957.1    .035       0
  5031.1     .05       0  5206.6     .05       0  5207.4     .12       0
  5303.2     .05       0  5460.4      .1       0  5513.9     .05       0
  5549.8      .1       0  5811.6     .05       0
Bank Sta=4957.1,5031.1
XS Rating Curve= 0 ,0
Exp/Cntr=0.3,0.1

Type RM Length L Ch R = 1 ,3864    ,768,768,768
BEGIN DESCRIPTION:
Mapping XS 621ccb42
END DESCRIPTION:
XS GIS Cut Line= 4
      3546519.21     10429370.93      3547140.77     10429238.98
      3547467.16     10427867.45      3547415.07     10426870.94
#Sta/Elev= 30
  3738.1  372.17  3956.1  349.52  4045.1  348.63  4088.6  346.13  4317.2  327.43
    4453  318.59    4701  313.94  4703.8  313.44  4781.9  315.82  4962.1  315.17
  5046.4     315  5172.5  319.44  5199.3  317.74  5304.5   322.2    5394  329.67
    5409  328.58  5436.1  332.14  5441.3  330.11  5478.3  332.89  5483.4  331.07
  5520.4  333.96  5533.5  332.95    5615  332.65    5652  337.54  5727.6  342.74
  5905.9  348.68  6019.5  348.96  6249.8  360.37  6580.2  364.21  6781.2   369.6
#Mann= 8 ,-1 , 0
  3738.1     .16       0  4317.2     .05       0    4701     .07       0
  4962.1     .05       0  5046.4     .12       0  5199.3     .05       0
  5533.5      .1       0  5905.9     .05       0
#Block Obstruct= 2 , 0
         4950.29  314.31
Bank Sta=4962.1,5046.4
XS Rating Curve= 0 ,0
Exp/Cntr=0.3,0.1

Type RM Length L Ch R = 1 ,3096    ,0,0,0
BEGIN DESCRIPTION:
SHOP BRANCH 1.0
END DESCRIPTION:
XS GIS Cut Line= 4
      3546659.17     10429561.34      3547266.81     10429561.34
      3548204.31     10426887.73      3547822.37     10426262.74
#Sta/Elev= 30
  2891.2  367.62  3064.1  361.34  3344.1  334.65  3784.6  313.08  4505.3  308.18
  4579.4  308.83  4929.1  303.13  5024.2  301.43  5097.4  303.44  5159.4  306.36
  5215.2   305.7  5407.5  310.57  5458.9  315.88  5464.2  314.52  5582.9  328.46
  5675.9  329.88  5701.6  332.77  5713.3  330.97  5732.6  334.84  5737.9  332.56
  5763.6  338.48  5825.7  342.86  5943.4  344.38  6187.1   352.8    6332  351.76
  6424.8  361.67  6482.9  364.69  6608.6  364.78  6862.2  371.28  7064.5   370.5
#Mann= 5 ,-1 , 0
  2891.2     .12       0  4505.3     .16       0  4929.1     .12       0
  5097.4     .16       0  5943.4     .12       0
Bank Sta=4929.1,5097.4
XS Rating Curve= 0 ,0
Exp/Cntr=0.3,0.1

Chan Stop Cuts=-1
Use User Specified Reach Order=0
Composite Channel Slope=5