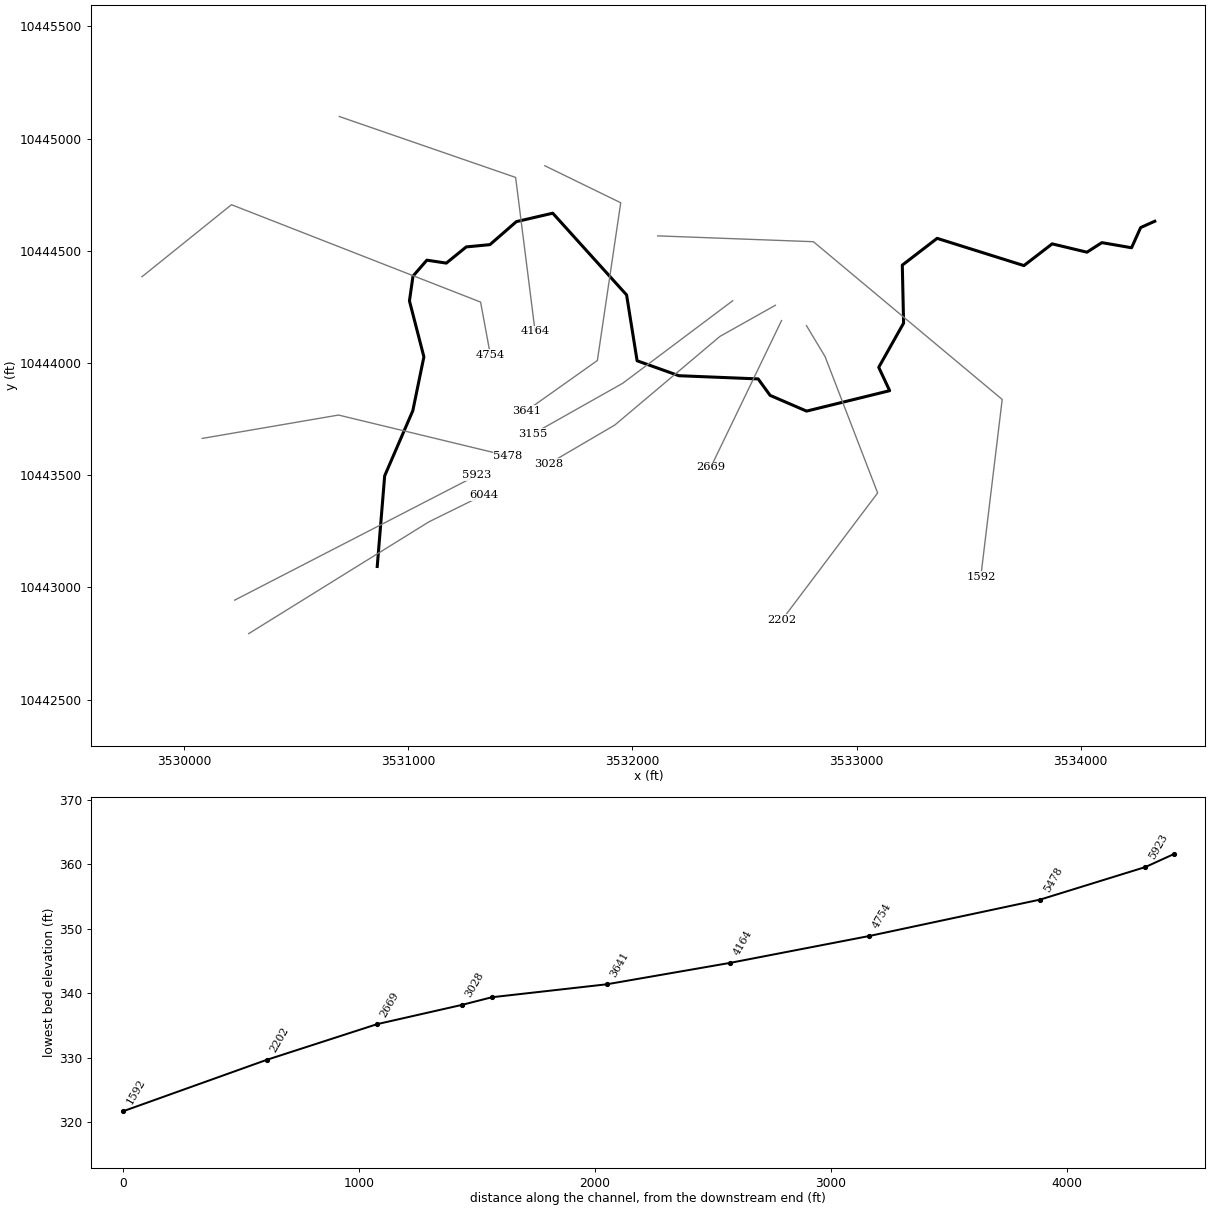
--- STEELE CREEK TRIB 11.prj (project) ---

Proj Title=STEELE CREEK TRIB 11 Base Level Engineering
Current Plan=p01
Default Exp/Contr=0.3,0.1
English Units
Geom File=g01
Flow File=f01
Plan File=p01
BEGIN DESCRIPTION:
STEELE CREEK TRIB 11
END DESCRIPTION:

--- STEELE CREEK TRIB 11.p01 (plan) ---

Plan Title=Multiple Run
Short Identifier=Multiple
Geom File=g01
Flow File=f01
Subcritical Flow
K Sum by GR= 0
Std Step Tol= 0.01
Critical Tol= 0.01
Num of Std Step Trials= 20
Max Error Tol= 0.3
Flow Tol Ratio= 0.001
Split Flow NTrial= 30
Split Flow Tol= 0.02
Split Flow Ratio= 0.02
Log Output Level= 0
Friction Slope Method= 1
Unsteady Friction Slope Method= 2
Unsteady Bridges Friction Slope Method= 1
Parabolic Critical Depth
Global Vel Dist=  1 , 1 , 1
Global Log Level= 0
CheckData=True
Encroach Param= -1, 0, 0, 0
BEGIN DESCRIPTION:
Multiple Run
END DESCRIPTION:

--- STEELE CREEK TRIB 11.f01 (steady flow) ---

Flow Title=Multiple
Number of Profiles=7
Profile Names=10-year,25-year,50-year,1pct_min,100-year,1pct_plu,500-year
River Rch & RM= STEELE CREEK TRI,Reach-1,6044
     702     948    1147    1016    1373    1857    1960
Boundary for River Rch & Prof#=STEELE CREEK TRI,Reach-1,1
Up Type=0
Dn Type=3
Dn Slope=0.005
Boundary for River Rch & Prof#=STEELE CREEK TRI,Reach-1,2
Up Type=0
Dn Type=3
Dn Slope=0.005
Boundary for River Rch & Prof#=STEELE CREEK TRI,Reach-1,3
Up Type=0
Dn Type=3
Dn Slope=0.005
Boundary for River Rch & Prof#=STEELE CREEK TRI,Reach-1,4
Up Type=0
Dn Type=3
Dn Slope=0.005
Boundary for River Rch & Prof#=STEELE CREEK TRI,Reach-1,5
Up Type=0
Dn Type=3
Dn Slope=0.005
Boundary for River Rch & Prof#=STEELE CREEK TRI,Reach-1,6
Up Type=0
Dn Type=3
Dn Slope=0.005
Boundary for River Rch & Prof#=STEELE CREEK TRI,Reach-1,7
Up Type=0
Dn Type=3
Dn Slope=0.005

--- STEELE CREEK TRIB 11.g01 (geometry) ---

Geom Title=Existing Conditions

River Reach=STEELE CREEK TRI,Reach-1
Reach XY= 30
      3530862.26     10443092.85      3530895.42     10443496.86
      3531020.95     10443787.12      3531070.38     10444027.44
      3531005.96     10444276.60      3531021.69     10444386.89
      3531083.55     10444458.16      3531170.40     10444445.04
      3531259.22     10444517.23      3531364.81     10444527.28
      3531482.79     10444629.87      3531645.05     10444667.54
      3531974.41     10444303.12      3532021.28     10444009.72
      3532207.72     10443943.17      3532561.18     10443928.92
      3532614.45     10443855.58      3532777.08     10443785.40
      3533147.64     10443876.46      3533098.94     10443980.59
      3533209.85     10444177.43      3533204.08     10444436.02
      3533359.43     10444555.41      3533746.54     10444433.95
      3533872.43     10444530.83      3534027.60     10444493.71
      3534093.98     10444536.30      3534226.56     10444513.47
      3534267.19     10444603.52      3534330.11     10444631.65

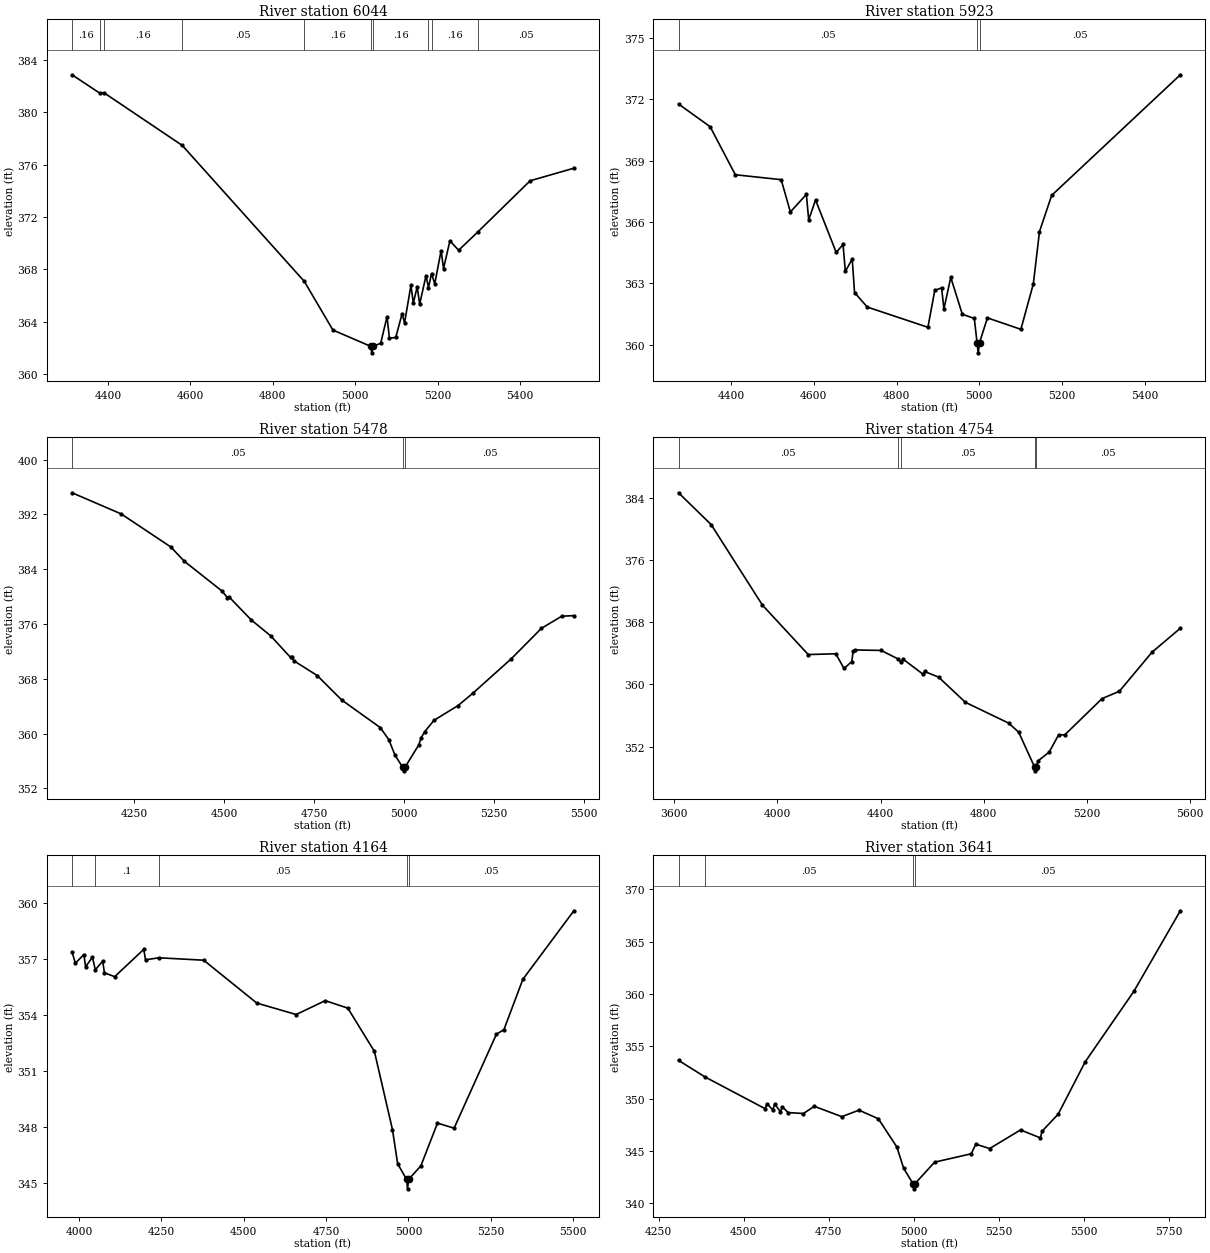
Type RM Length L Ch R = 1,6044,121,121,121
BEGIN DESCRIPTION:
STEELE CREEK TRIB 11 13.0
END DESCRIPTION:
XS GIS Cut Line= 4
      3530289.06     10442793.63      3530737.01     10443071.43
      3531092.91     10443291.91      3531335.94     10443411.69
#Sta/Elev= 30
  4313.2  382.87  4381.5  381.44  4390.3  381.50  4580.4  377.47  4876.3  367.08
  4945.7  363.36  5037.2  362.12  5040.0  361.62  5043.2  362.12  5061.5  362.35
  5076.9  364.38  5082.7  362.73  5098.1  362.80  5113.5  364.62  5119.4  363.90
  5134.8  366.78  5140.6  365.42  5150.1  366.67  5156.0  365.33  5171.4  367.52
  5177.4  366.61  5184.8  367.67  5192.6  366.90  5208.0  369.43  5213.9  368.06
  5229.3  370.18  5250.5  369.46  5296.4  370.84  5423.9  374.77  5529.9  375.73
#Mann=10,-1,0
  4313.2    0.16       0  4381.5    0.05       0  4390.3    0.16       0
  4580.4    0.05       0  4876.3    0.16       0  5037.2    0.07       0
  5043.2    0.16       0  5177.4    0.05       0  5184.8    0.16       0
  5296.4    0.05       0
Bank Sta=5037.2,5043.2
Exp/Cntr=0.3,0.1

Type RM Length L Ch R = 1,5923,445,445,445
BEGIN DESCRIPTION:
Mapping XS 6491454c
END DESCRIPTION:
XS GIS Cut Line= 2
      3530226.63     10442942.97      3531304.71     10443498.51
#Sta/Elev= 30
  4273.0  371.77  4349.4  370.66  4410.3  368.31  4521.1  368.07  4543.3  366.49
  4582.0  367.35  4587.6  366.10  4604.1  367.08  4654.1  364.51  4670.6  364.90
  4676.2  363.58  4692.8  364.19  4698.4  362.55  4729.1  361.84  4875.7  360.85
  4892.3  362.65  4908.8  362.78  4914.4  361.75  4931.0  363.29  4958.8  361.49
  4987.9  361.28  4994.5  360.10  4997.2  359.60  5000.5  360.10  5019.6  361.31
  5100.4  360.75  5130.5  362.97  5145.4  365.53  5174.8  367.30  5485.8  373.20
#Mann=3,-1,0
  4273.0    0.05       0  4994.5    0.04       0  5000.5    0.05       0
Bank Sta=4994.5,5000.5
Exp/Cntr=0.3,0.1

Type RM Length L Ch R = 1,5478,724,724,724
BEGIN DESCRIPTION:
STEELE CREEK TRIB 11 12.0
END DESCRIPTION:
XS GIS Cut Line= 3
      3530081.91     10443663.68      3530689.56     10443767.85
      3531444.76     10443585.56
#Sta/Elev= 30
  4077.6  395.15  4214.1  392.06  4351.7  387.24  4389.1  385.16  4493.8  380.81
  4509.2  379.83  4514.3  379.90  4574.9  376.60  4629.3  374.25  4684.2  371.11
  4689.3  371.15  4692.9  370.64  4758.5  368.46  4826.2  364.90  4933.3  360.87
  4957.0  359.12  4974.5  356.82  4995.9  355.05  4998.6  354.55  5001.9  355.05
  5040.8  358.38  5046.5  359.34  5056.8  360.27  5082.7  361.93  5149.4  364.08
  5190.5  365.88  5297.2  370.91  5381.0  375.36  5437.4  377.13  5471.0  377.21
#Mann=3,-1,0
  4077.6    0.05       0  4995.9    0.03       0  5001.9    0.05       0
Bank Sta=4995.9,5001.9
Exp/Cntr=0.3,0.1

Type RM Length L Ch R = 1,4754,590,590,590
BEGIN DESCRIPTION:
STEELE CREEK TRIB 11 10.0
END DESCRIPTION:
XS GIS Cut Line= 4
      3529812.82     10444384.16      3530212.13     10444705.35
      3531323.24     10444271.32      3531366.64     10444036.94
#Sta/Elev= 30
  3617.5  384.66  3743.8  380.57  3942.2  370.22  4119.8  363.85  4226.6  363.95
  4258.6  362.06  4288.5  362.93  4293.8  364.25  4301.7  364.44  4402.5  364.38
  4468.0  363.28  4479.8  362.87  4486.6  363.27  4565.4  361.30  4570.8  361.67
  4625.1  360.94  4728.4  357.71  4896.7  355.02  4935.1  353.86  4996.5  349.39
  4999.3  348.89  5002.5  349.39  5010.8  350.19  5053.2  351.30  5089.6  353.51
  5114.0  353.53  5257.9  358.18  5325.2  359.13  5451.8  364.16  5561.2  367.23
#Mann=5,-1,0
  3617.5    0.05       0  4468.0    0.07       0  4479.8    0.05       0
  4996.5    0.03       0  5002.5    0.05       0
Bank Sta=4996.5,5002.5
Exp/Cntr=0.3,0.1

Type RM Length L Ch R = 1,4164,523,523,523
BEGIN DESCRIPTION:
STEELE CREEK TRIB 11 9.0
END DESCRIPTION:
XS GIS Cut Line= 3
      3530693.32     10445098.33      3531479.49     10444826.88
      3531566.30     10444141.06
#Sta/Elev= 30
  3978.9  357.36  3988.8  356.76  4014.7  357.22  4020.0  356.57  4040.6  357.08
  4049.5  356.41  4071.8  356.87  4077.1  356.25  4108.2  356.04  4196.5  357.50
  4201.8  356.94  4242.3  357.05  4378.4  356.92  4539.6  354.63  4659.1  354.02
  4747.3  354.76  4815.9  354.36  4896.5  352.05  4951.4  347.87  4967.1  346.05
  4994.3  345.21  4997.1  344.71  5000.3  345.21  5037.6  345.94  5088.0  348.22
  5138.4  347.95  5266.9  352.97  5289.6  353.21  5347.1  355.90  5501.9  359.56
#Mann=5,-1,0
  3978.9    0.05       0  4049.5     0.1       0  4242.3    0.05       0
  4994.3    0.03       0  5000.3    0.05       0
Bank Sta=4994.3,5000.3
Exp/Cntr=0.3,0.1

Type RM Length L Ch R = 1,3641,486,486,486
BEGIN DESCRIPTION:
STEELE CREEK TRIB 11 7.0
END DESCRIPTION:
XS GIS Cut Line= 4
      3531609.71     10444878.96      3531948.24     10444714.03
      3531844.07     10444010.91      3531527.26     10443786.50
#Sta/Elev= 30
  4308.8  353.66  4385.9  352.09  4563.5  349.04  4569.1  349.52  4586.0  348.92
  4591.6  349.48  4608.6  348.75  4614.1  349.22  4631.1  348.67  4676.2  348.58
  4708.0  349.27  4788.9  348.28  4839.4  348.90  4896.4  348.08  4950.6  345.39
  4971.0  343.33  4998.2  341.88  5000.9  341.38  5004.2  341.88  5061.8  343.93
  5169.4  344.73  5183.1  345.65  5223.6  345.23  5314.5  347.01  5372.8  346.25
  5377.9  346.89  5425.0  348.51  5505.0  353.54  5647.8  360.26  5784.4  367.96
#Mann=4,-1,0
  4308.8    0.08       0  4385.9    0.05       0  4998.2    0.03       0
  5004.2    0.05       0
Bank Sta=4998.2,5004.2
Exp/Cntr=0.3,0.1

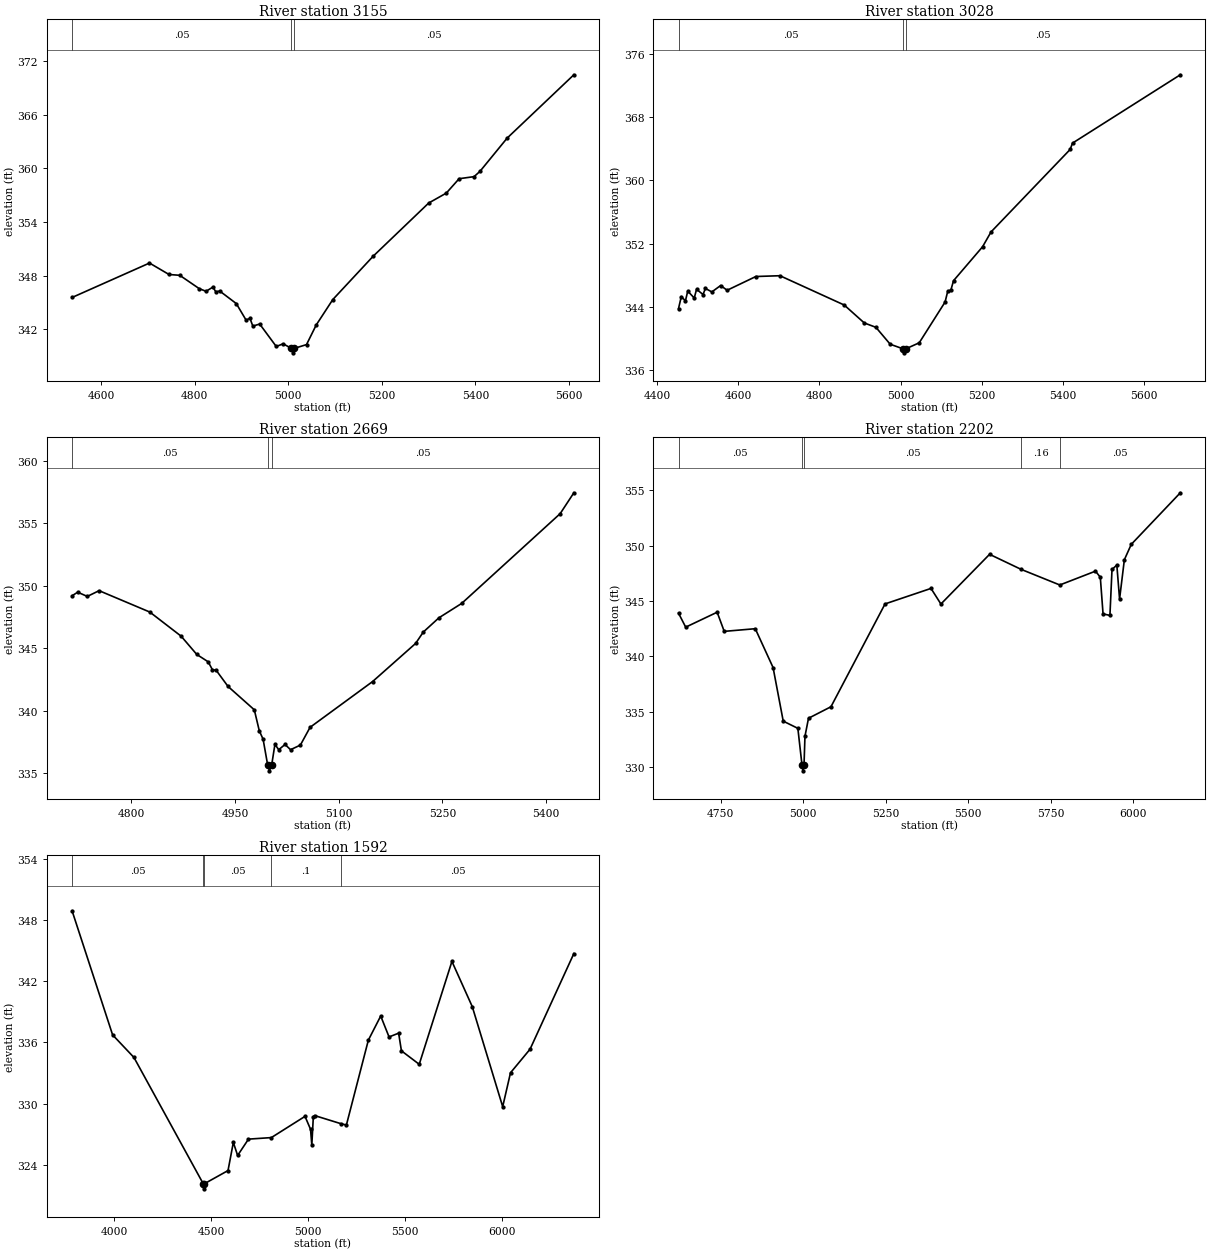
Type RM Length L Ch R = 1,3155,127,127,127
BEGIN DESCRIPTION:
Mapping XS 02f28737
END DESCRIPTION:
XS GIS Cut Line= 3
      3532447.54     10444277.27      3531957.08     10443909.43
      3531557.30     10443684.27
#Sta/Elev= 30
  4538.3  345.56  4703.7  349.41  4745.4  348.13  4768.3  348.04  4809.9  346.55
  4824.5  346.25  4839.1  346.72  4845.4  346.19  4853.7  346.28  4889.1  344.88
  4909.9  343.04  4918.3  343.22  4924.5  342.36  4939.1  342.59  4974.5  340.08
  4989.1  340.38  5006.9  339.87  5009.7  339.37  5012.9  339.87  5039.1  340.29
  5059.9  342.49  5095.3  345.33  5181.6  350.18  5300.1  356.12  5337.7  357.23
  5365.1  358.84  5397.0  359.07  5409.6  359.66  5467.7  363.38  5610.2  370.46
#Mann=3,-1,0
  4538.3    0.05       0  5006.9   0.035       0  5012.9    0.05       0
Bank Sta=5006.9,5012.9
Exp/Cntr=0.3,0.1

Type RM Length L Ch R = 1,3028,359,359,359
BEGIN DESCRIPTION:
STEELE CREEK TRIB 11 6.0
END DESCRIPTION:
XS GIS Cut Line= 4
      3532638.02     10444257.17      3532390.65     10444118.30
      3531921.90     10443723.34      3531628.92     10443551.89
#Sta/Elev= 30
  4453.2  343.79  4460.0  345.30  4470.2  344.76  4475.9  345.99  4491.9  345.12
  4497.6  346.22  4513.6  345.56  4519.3  346.33  4535.3  345.89  4556.9  346.70
  4572.9  346.10  4643.7  347.84  4703.0  347.94  4861.4  344.23  4910.8  341.96
  4939.4  341.41  4974.6  339.27  5006.7  338.68  5009.5  338.18  5012.7  338.68
  5046.1  339.45  5109.8  344.61  5116.3  345.97  5124.1  346.12  5130.6  347.31
  5202.1  351.60  5223.0  353.48  5417.9  363.92  5423.7  364.72  5689.3  373.37
#Mann=3,-1,0
  4453.2    0.05       0  5006.7    0.03       0  5012.7    0.05       0
Bank Sta=5006.7,5012.7
Exp/Cntr=0.3,0.1

Type RM Length L Ch R = 1,2669,467,467,467
BEGIN DESCRIPTION:
Mapping XS b13cf568
END DESCRIPTION:
XS GIS Cut Line= 2
      3532665.51     10444188.91      3532350.10     10443535.56
#Sta/Elev= 30
  4714.5  349.19  4722.6  349.48  4736.5  349.14  4753.6  349.60  4826.9  347.89
  4872.2  345.96  4894.8  344.50  4911.3  343.91  4917.4  343.28  4922.9  343.23
  4940.0  341.94  4978.0  340.07  4985.2  338.39  4990.7  337.72  4997.2  335.69
  4999.9  335.19  5003.2  335.69  5007.8  337.31  5013.3  336.88  5022.4  337.30
  5030.4  336.88  5044.6  337.25  5058.6  338.67  5149.0  342.33  5211.2  345.38
  5222.3  346.29  5244.9  347.43  5277.8  348.58  5420.2  355.76  5440.0  357.43
#Mann=3,-1,0
  4714.5    0.05       0  4997.2    0.03       0  5003.2    0.05       0
Bank Sta=4997.2,5003.2
Exp/Cntr=0.3,0.1

Type RM Length L Ch R = 1,2202,610,610,610
BEGIN DESCRIPTION:
STEELE CREEK TRIB 11 4.0
END DESCRIPTION:
XS GIS Cut Line= 4
      3532776.61     10444166.41      3532859.70     10444028.27
      3533094.07     10443420.63      3532668.83     10442856.53
#Sta/Elev= 30
  4622.9  343.89  4644.6  342.63  4739.8  343.98  4761.2  342.25  4855.2  342.49
  4909.1  338.98  4939.8  334.14  4984.1  333.49  4996.7  330.15  4999.5  329.65
  5002.7  330.15  5005.6  332.77  5016.3  334.40  5084.3  335.44  5248.0  344.73
  5387.1  346.13  5417.1  344.72  5564.4  349.21  5660.0  347.85  5777.0  346.44
  5885.0  347.69  5899.6  347.14  5907.9  343.83  5928.7  343.69  5935.0  347.84
  5949.6  348.24  5957.9  345.17  5972.4  348.72  5993.3  350.11  6141.8  354.77
#Mann=5,-1,0
  4622.9    0.05       0  4996.7    0.03       0  5002.7    0.05       0
  5660.0    0.16       0  5777.0    0.05       0
Bank Sta=4996.7,5002.7
Exp/Cntr=0.3,0.1

Type RM Length L Ch R = 1,1592,0,0,0
BEGIN DESCRIPTION:
STEELE CREEK TRIB 11 1.0
END DESCRIPTION:
XS GIS Cut Line= 4
      3532113.19     10444566.46      3532807.61     10444540.42
      3533649.63     10443837.29      3533554.14     10443047.34
#Sta/Elev= 30
  3781.7  348.88  3990.8  336.72  4100.8  334.51  4458.1  322.14  4460.8  321.64
  4464.1  322.14  4585.9  323.43  4613.3  326.19  4635.4  324.91  4691.4  326.51
  4809.3  326.66  4982.9  328.74  5011.5  327.47  5018.0  325.92  5025.8  328.70
  5032.4  328.82  5168.5  328.02  5196.3  327.89  5309.6  336.21  5373.3  338.57
  5416.3  336.52  5465.7  336.89  5480.1  335.16  5571.9  333.84  5740.5  343.92
  5845.4  339.49  6002.3  329.69  6042.6  333.01  6143.4  335.32  6369.3  344.69
#Mann=5,-1,0
  3781.7    0.05       0  4458.1    0.07       0  4464.1    0.05       0
  4809.3     0.1       0  5168.5    0.05       0
Bank Sta=4458.1,4464.1
Exp/Cntr=0.3,0.1

Chan Stop Cuts=-1