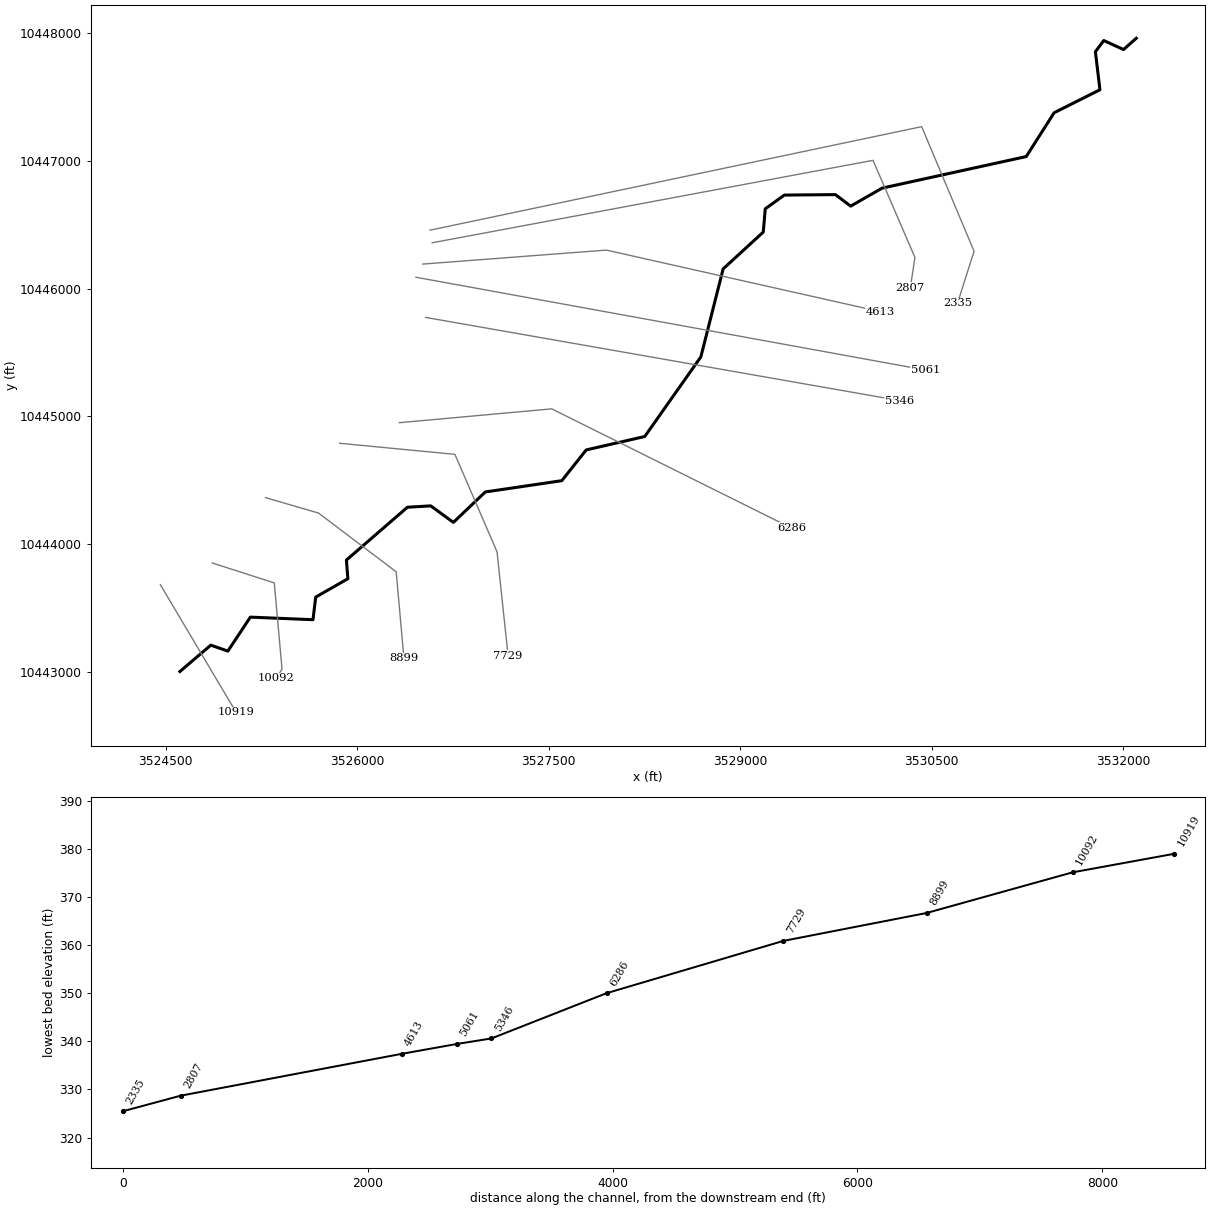
--- STEELE CREEK TRIB 12.prj (project) ---

Proj Title=STEELE CREEK TRIB 12 Base Level Engineering
Current Plan=p01
Default Exp/Contr=0.3,0.1
English Units
Geom File=g01
Flow File=f01
Plan File=p01
Y Axis Title=Elevation
X Axis Title(PF)=Main Channel Distance
X Axis Title(XS)=Station
BEGIN DESCRIPTION:
STEELE CREEK TRIB 12
END DESCRIPTION:
DSS Export Rating Curves= 0
DSS Export Rating Curve Sorted= 0
DSS Export Volume Flow Curves= 0
DXF OffsetX= 0
DXF OffsetY= 0
DXF ScaleX= 1
DXF ScaleY= 10

--- STEELE CREEK TRIB 12.p01 (plan) ---

Plan Title=Multiple Run
Short Identifier=Multiple
Geom File=g01
Flow File=f01
Subcritical Flow
K Sum by GR= 0
Std Step Tol= 0.01
Critical Tol= 0.01
Num of Std Step Trials= 20
Max Error Tol= 0.3
Flow Tol Ratio= 0.001
Split Flow NTrial= 30
Split Flow Tol= 0.02
Split Flow Ratio= 0.02
Log Output Level= 0
Friction Slope Method= 1
Unsteady Friction Slope Method= 2
Unsteady Bridges Friction Slope Method= 1
Parabolic Critical Depth
Global Vel Dist=  1 , 1 , 1
Global Log Level= 0
CheckData=True
Encroach Param= -1, 0, 0, 0
BEGIN DESCRIPTION:
Multiple Run
END DESCRIPTION:

--- STEELE CREEK TRIB 12.f01 (steady flow) ---

Flow Title=Multiple
Number of Profiles=7
Profile Names=10-year,25-year,50-year,1pct_min,100-year,1pct_plu,500-year
River Rch & RM= STEELE CREEK TRI,Reach-1,10919
     937    1292    1587    1422    1924    2602    2819
River Rch & RM= STEELE CREEK TRI,Reach-1,5061
    1124    1561    1925    1732    2342    3168    3459
Boundary for River Rch & Prof#=STEELE CREEK TRI,Reach-1,1
Up Type=0
Dn Type=3
Dn Slope=0.005
Boundary for River Rch & Prof#=STEELE CREEK TRI,Reach-1,2
Up Type=0
Dn Type=3
Dn Slope=0.005
Boundary for River Rch & Prof#=STEELE CREEK TRI,Reach-1,3
Up Type=0
Dn Type=3
Dn Slope=0.005
Boundary for River Rch & Prof#=STEELE CREEK TRI,Reach-1,4
Up Type=0
Dn Type=3
Dn Slope=0.005
Boundary for River Rch & Prof#=STEELE CREEK TRI,Reach-1,5
Up Type=0
Dn Type=3
Dn Slope=0.005
Boundary for River Rch & Prof#=STEELE CREEK TRI,Reach-1,6
Up Type=0
Dn Type=3
Dn Slope=0.005
Boundary for River Rch & Prof#=STEELE CREEK TRI,Reach-1,7
Up Type=0
Dn Type=3
Dn Slope=0.005

--- STEELE CREEK TRIB 12.g01 (geometry) ---

Geom Title=Existing Conditions
Program Version=4.10

River Reach=STEELE CREEK TRI,Reach-1
Reach XY= 30
       3524611.8     10443001.89      3524853.89     10443208.45
      3524987.32     10443161.75       3525163.6     10443427.89
      3525654.04     10443407.69      3525675.62     10443584.85
      3525927.26     10443728.72      3525915.98     10443874.82
       3526393.5     10444288.45      3526576.42     10444299.35
      3526753.81     10444169.72      3527003.52     10444408.21
      3527602.74     10444496.53      3527794.12     10444737.58
      3528252.45      10444842.5      3528692.02     10445466.36
      3528866.65      10446155.6      3529180.88     10446443.79
      3529196.51     10446626.08      3529346.05     10446733.56
      3529746.28      10446737.2       3529865.2     10446646.92
      3530111.73     10446787.98      3531240.61     10447035.31
       3531458.7      10447378.2      3531817.79     10447558.62
      3531782.13     10447856.35      3531847.62     10447944.11
      3532002.47     10447873.55      3532102.11     10447961.64

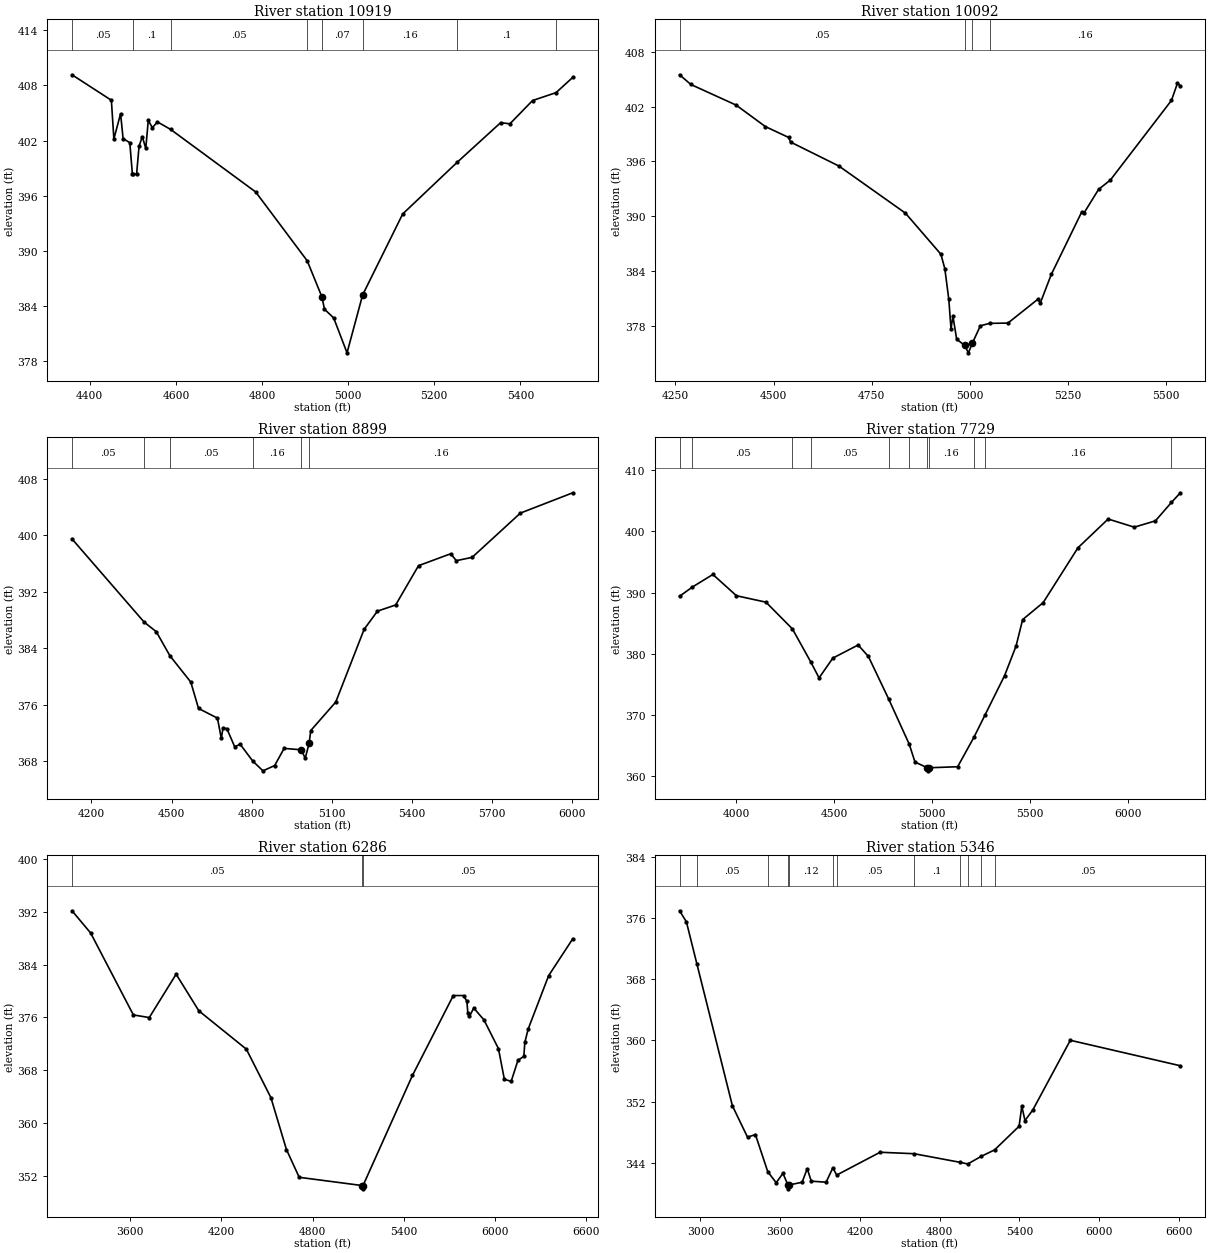
Type RM Length L Ch R = 1 ,10919   ,827,827,827
BEGIN DESCRIPTION:
STEELE CREEK TRIB 12 18.0
END DESCRIPTION:
XS GIS Cut Line= 2
      3524458.52     10443681.99      3525052.27     10442681.98
#Sta/Elev= 30
  4358.8  409.15  4450.2  406.38    4456  402.18  4471.6  404.92  4477.4  402.22
    4493  401.77  4498.9  398.42  4501.4   398.4  4508.7  398.33  4514.5  401.38
    4522  402.43  4530.1  401.15  4535.9   404.2  4545.3   403.4  4557.3  404.03
  4587.9  403.21  4785.3  396.42    4905  388.94  4939.3     385  4945.1  383.68
  4966.5  382.73  4997.5  378.94  5033.7  385.23  5126.8  394.03  5253.7  399.66
  5354.3  403.95  5375.7  403.82  5428.3  406.35  5482.9  407.21  5521.8  408.87
#Mann= 8 ,-1 , 0
  4358.8     .05       0  4501.4      .1       0  4587.9     .05       0
    4905     .16       0  4939.3     .07       0  5033.7     .16       0
  5253.7      .1       0  5482.9     .05       0
Bank Sta=4939.3,5033.7
XS Rating Curve= 0 ,0
Exp/Cntr=0.3,0.1

Type RM Length L Ch R = 1 ,10092   ,1193,1193,1193
BEGIN DESCRIPTION:
STEELE CREEK TRIB 12 16.0
END DESCRIPTION:
XS GIS Cut Line= 4
      3524864.75     10443852.15      3525350.87     10443695.89
      3525411.64     10443020.54      3525364.75     10442947.61
#Sta/Elev= 30
  4260.6  405.47  4289.3  404.41  4404.5  402.16  4479.2  399.81  4538.1  398.63
  4543.3  398.12  4666.5   395.5  4835.7  390.36  4926.1  385.87  4936.1  384.29
  4946.2  380.95  4951.8  377.74  4956.8  379.09  4966.3  376.58  4986.3  375.93
  4996.1   375.1  5006.4  376.17  5026.5  378.05    5050  378.32  5096.8  378.35
  5173.8  380.98  5178.8  380.49  5207.2  383.66  5284.8  390.49  5289.9  390.33
  5327.7  392.95  5357.8  393.98  5513.3  402.67  5528.5  404.54    5536  404.26
#Mann= 4 ,-1 , 0
  4260.6     .05       0  4986.3    .035       0  5006.4     .05       0
    5050     .16       0
Bank Sta=4986.3,5006.4
XS Rating Curve= 0 ,0
Exp/Cntr=0.3,0.1

Type RM Length L Ch R = 1 ,8899    ,1170,1170,1170
BEGIN DESCRIPTION:
STEELE CREEK TRIB 12 13.0
END DESCRIPTION:
XS GIS Cut Line= 4
      3525281.45     10444364.29      3525698.09     10444242.77
      3526305.73      10443782.7      3526366.45     10443106.18
#Sta/Elev= 30
  4127.1  399.51  4397.3  387.72  4442.8  386.36  4493.6  382.96  4571.8  379.23
  4600.9  375.49  4671.7  374.12  4686.2  371.24  4692.5  372.74  4707.1  372.62
  4736.2  370.07    4757  370.41  4803.6  368.05  4842.1  366.65    4886   367.4
  4921.4  369.83  4985.9  369.63  5000.4  368.42    5015  370.55  5021.2  372.36
  5114.8   376.4    5221   386.7  5270.9  389.28    5339  390.15  5424.7  395.72
  5545.2  397.41  5566.3  396.43  5625.5   396.9  5806.2  403.17  6002.5  406.05
#Mann= 6 ,-1 , 0
  4127.1     .05       0  4397.3      .1       0  4493.6     .05       0
  4803.6     .16       0  4985.9     .07       0    5015     .16       0
Bank Sta=4985.9,5015
XS Rating Curve= 0 ,0
Exp/Cntr=0.3,0.1

Type RM Length L Ch R = 1 ,7729    ,1443,1443,1443
BEGIN DESCRIPTION:
STEELE CREEK TRIB 12 11.0
END DESCRIPTION:
XS GIS Cut Line= 4
      3525863.02     10444789.64       3526765.8     10444702.84
      3527095.66     10443938.95      3527182.27     10443124.85
#Sta/Elev= 30
  3710.1  389.39  3775.9   390.9    3880  392.95  4000.5  389.47  4151.2  388.42
  4286.3  384.05  4380.1  378.64  4422.5  376.04  4492.8  379.28  4622.1  381.42
  4674.5  379.54  4777.8   372.6  4882.9  365.21  4912.4  362.29  4975.4  361.35
  4978.1  360.85  4981.4  361.35  5130.3  361.52  5215.1  366.44  5271.1  370.05
  5369.9  376.41  5428.7  381.26  5462.1  385.57  5567.1  388.35  5744.7  397.31
  5898.9  402.01  6032.3  400.68  6140.3  401.71  6222.3  404.73  6267.8   406.3
#Mann= 11 ,-1 , 0
  3710.1      .1       0  3775.9     .05       0  4286.3      .1       0
  4380.1     .05       0  4777.8      .1       0  4882.9     .16       0
  4975.4     .07       0  4981.4     .16       0  5215.1     .05       0
  5271.1     .16       0  6222.3     .05       0
Bank Sta=4975.4,4981.4
XS Rating Curve= 0 ,0
Exp/Cntr=0.3,0.1

Type RM Length L Ch R = 1 ,6286    ,940,940,940
BEGIN DESCRIPTION:
STEELE CREEK TRIB 12 9.0
END DESCRIPTION:
XS GIS Cut Line= 3
      3526330.14     10444950.73      3527523.76     10445059.24
      3529400.34     10444126.38
#Sta/Elev= 30
  3217.1  392.17  3339.6   388.8  3620.7  376.37  3725.2  375.97  3901.9  382.55
  4051.5  376.99  4363.8  371.18  4525.5  363.82  4627.6  355.95  4711.6  351.74
  5125.5  350.49  5128.3  349.99  5131.5  350.49  5456.4  367.19  5725.2  379.31
  5792.4  379.31  5814.8  378.43  5820.9  376.59  5831.6  376.14  5859.6  377.42
  5926.8  375.62    6022  371.27  6061.2   366.6    6106   366.3  6150.8   369.5
  6189.4  370.09  6195.6   372.2    6218  374.25  6352.4  382.33  6511.3  387.93
#Mann= 3 ,-1 , 0
  3217.1     .05       0  5125.5     .03       0  5131.5     .05       0
Bank Sta=5125.5,5131.5
XS Rating Curve= 0 ,0
Exp/Cntr=0.3,0.1

Type RM Length L Ch R = 1 ,5346    ,285,285,285
BEGIN DESCRIPTION:
STEELE CREEK TRIB 12 8.0
END DESCRIPTION:
XS GIS Cut Line= 2
      3526536.33     10445775.39      3530247.16     10445124.37
#Sta/Elev= 30
    2843  376.92  2894.1  375.48  2972.9  369.99  3240.3  351.44    3354  347.34
  3413.4  347.68  3506.3  342.83  3569.7  341.39  3620.5  342.61  3658.1  341.09
  3660.8  340.59  3664.1  341.09  3764.7  341.45  3803.2  343.22  3833.7  341.59
  3945.4  341.46    3996  343.34  4024.8  342.39  4351.5  345.37  4606.6  345.18
  4951.8  344.06  5010.8  343.84  5111.9  344.83  5212.9  345.68  5397.2  348.77
  5417.5  351.39  5441.4  349.51  5500.8  350.91  5782.5     360  6610.5  356.67
#Mann= 12 ,-1 , 0
    2843      .1       0  2972.9     .05       0  3506.3     .12       0
  3658.1     .03       0  3664.1     .12       0    3996     .08       0
  4024.8     .05       0  4606.6      .1       0  4951.8     .05       0
  5010.8      .1       0  5111.9     .08       0  5212.9     .05       0
Bank Sta=3658.1,3664.1
XS Rating Curve= 0 ,0
Exp/Cntr=0.3,0.1

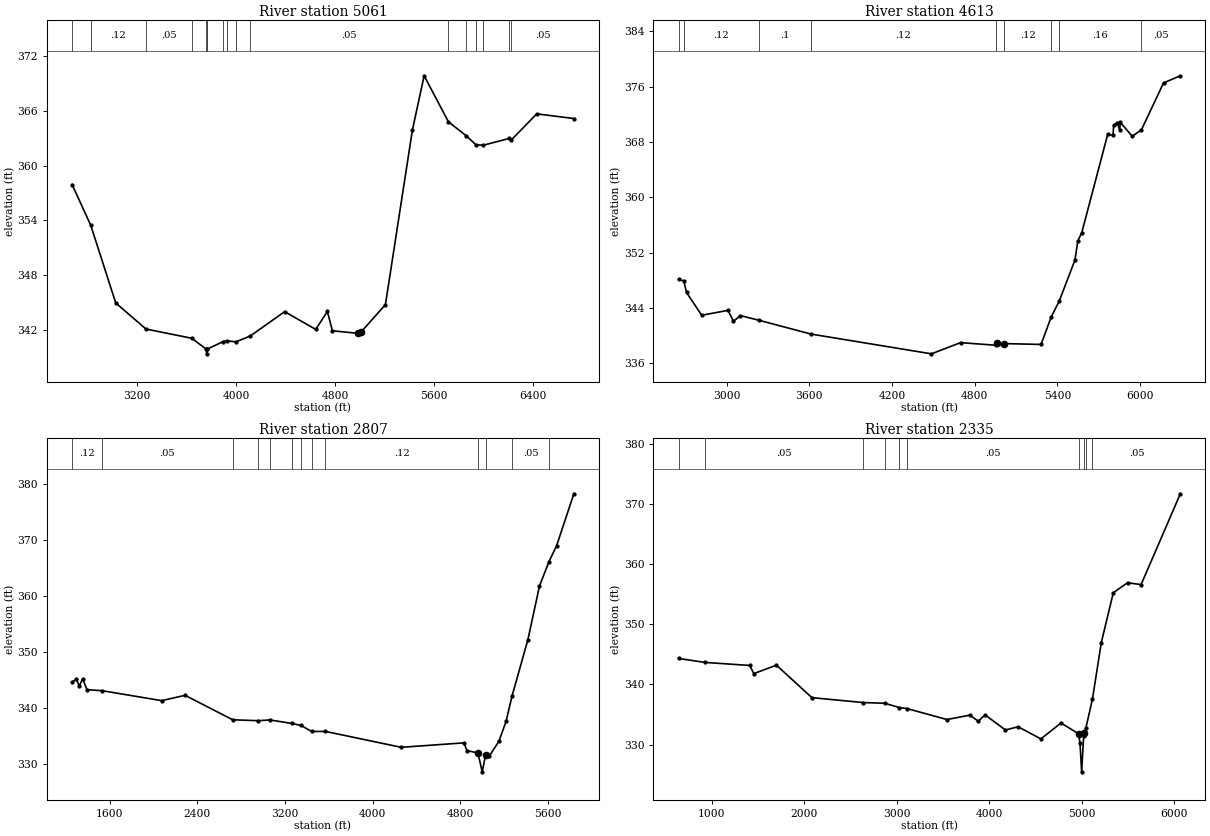
Type RM Length L Ch R = 1 ,5061    ,448,448,448
BEGIN DESCRIPTION:
STEELE CREEK TRIB 12 7.0
END DESCRIPTION:
XS GIS Cut Line= 2
      3526460.44     10446090.05      3530453.49     10445363.06
#Sta/Elev= 30
  2673.9  357.93  2824.3   353.5  3027.1  344.99  3271.8  342.14  3642.3  341.13
  3760.2  339.93  3762.9  339.43  3766.2  339.93  3767.9  339.95  3893.9  340.76
  3928.2  340.85    3999  340.74  4115.4  341.38  4393.4  344.04  4644.7   342.1
    4739  344.06  4779.6  341.95  4984.9  341.67  5013.4  341.85  5208.4   344.8
  5426.8  363.89  5521.6  369.81  5718.1  364.78  5861.6  363.26  5940.2  362.28
  5999.2  362.22  6208.4  362.96  6225.3  362.78  6432.4  365.65  6732.6  365.14
#Mann= 17 ,-1 , 0
  2673.9     .05       0  2824.3     .12       0  3271.8     .05       0
  3642.3     .12       0  3760.2     .03       0  3766.2     .12       0
  3767.9     .05       0  3893.9     .12       0  3928.2     .08       0
    3999     .12       0  4115.4     .05       0  5718.1     .16       0
  5861.6     .05       0  5940.2     .16       0  5999.2     .05       0
  6208.4     .16       0  6225.3     .05       0
Bank Sta=4984.9,5013.4
XS Rating Curve= 0 ,0
Exp/Cntr=0.3,0.1

Type RM Length L Ch R = 1 ,4613    ,1806,1806,1806
BEGIN DESCRIPTION:
Mapping XS 73a27331
END DESCRIPTION:
XS GIS Cut Line= 3
      3526514.49     10446193.24      3527952.03     10446302.62
      3530097.92     10445820.37
#Sta/Elev= 30
  2651.4  348.15  2689.2  347.94  2709.2  346.26  2819.5  342.97    3010  343.67
  3050.2  342.09  3100.3  342.92  3235.7  342.24  3611.8  340.25  4486.2  337.39
  4697.9  339.01  4954.1  338.63  4964.4   338.9  5015.6  338.87  5282.1  338.75
  5355.4  342.71  5413.6     345  5528.1  350.96  5548.6  353.72    5577  354.88
  5765.6  369.12  5803.8  368.96  5808.9  370.42  5835.6   370.8  5852.2  369.72
  5857.3  370.85  5943.9  368.83  6010.6  369.78  6170.7  376.55  6292.5  377.58
#Mann= 9 ,-1 , 0
  2651.4     .05       0  2689.2     .12       0  3235.7      .1       0
  3611.8     .12       0  4954.1     .07       0  5015.6     .12       0
  5355.4     .05       0  5413.6     .16       0  6010.6     .05       0
Bank Sta=4964.4,5015.6
XS Rating Curve= 0 ,0
Exp/Cntr=0.3,0.1

Type RM Length L Ch R = 1 ,2807    ,472,472,472
BEGIN DESCRIPTION:
Mapping XS 7ec304f3
END DESCRIPTION:
XS GIS Cut Line= 4
      3526587.43     10446359.91      3530040.57     10447005.74
      3530368.69     10446245.33       3530332.3     10446006.19
#Sta/Elev= 30
  1255.8  344.67  1294.3  345.18  1321.6     344  1352.1  345.25  1392.8  343.31
  1525.5  343.16  2074.4  341.37  2288.1  342.32  2723.2  337.96  2958.5   337.8
  3062.6  337.94  3262.9  337.31  3348.2  336.95  3443.3  335.88  3569.9  335.89
  4261.7  333.06  4834.5  333.85  4863.4  332.47  4962.9  332.06  5001.7  328.69
  5033.5  331.76  5067.9  331.53  5154.5  334.15  5219.8  337.67  5274.3   342.2
  5418.8  352.21  5524.8  361.77  5609.8  366.06  5681.7  368.99  5838.9  378.22
#Mann= 13 ,-1 , 0
  1255.8     .12       0  1525.5     .05       0  2723.2     .12       0
  2958.5     .05       0  3062.6      .1       0  3262.9     .05       0
  3348.2      .1       0  3443.3     .05       0  3569.9     .12       0
  4962.9     .07       0  5033.5     .12       0  5274.3     .05       0
  5609.8     .16       0
Bank Sta=4962.9,5033.5
XS Rating Curve= 0 ,0
Exp/Cntr=0.3,0.1

Type RM Length L Ch R = 1 ,2335    ,0,0,0
BEGIN DESCRIPTION:
STEELE CREEK TRIB 12 1.0
END DESCRIPTION:
XS GIS Cut Line= 4
      3526571.81     10446458.87      3530421.51      10447269.5
      3530831.91     10446293.29      3530701.93     10445886.02
#Sta/Elev= 30
     643  344.33   925.5  343.67  1411.8  343.16  1456.5   341.8  1700.4  343.21
  2083.6   337.8  2640.3  336.98    2870  336.87  3029.9  336.15  3109.4  335.99
  3542.3  334.16  3791.4  334.89  3880.8  333.87  3954.4  334.93  4174.5  332.42
    4312  332.95  4557.3  330.93  4773.8  333.58  4965.3  331.78  4980.1  330.17
  4997.6  325.45  5019.6  331.45  5027.6  331.85  5043.9  332.79  5114.5  337.57
  5210.1  346.98  5339.7  355.27  5493.1  356.93  5639.6  356.62  6063.6  371.74
#Mann= 10 ,-1 , 0
     643     .12       0   925.5     .05       0  2640.3      .1       0
    2870     .05       0  3029.9     .12       0  3109.4     .05       0
  4965.3     .03       0  5027.6     .05       0  5043.9     .16       0
  5114.5     .05       0
Bank Sta=4965.3,5027.6
XS Rating Curve= 0 ,0
Exp/Cntr=0.3,0.1

Chan Stop Cuts=-1
Use User Specified Reach Order=0
Composite Channel Slope=5