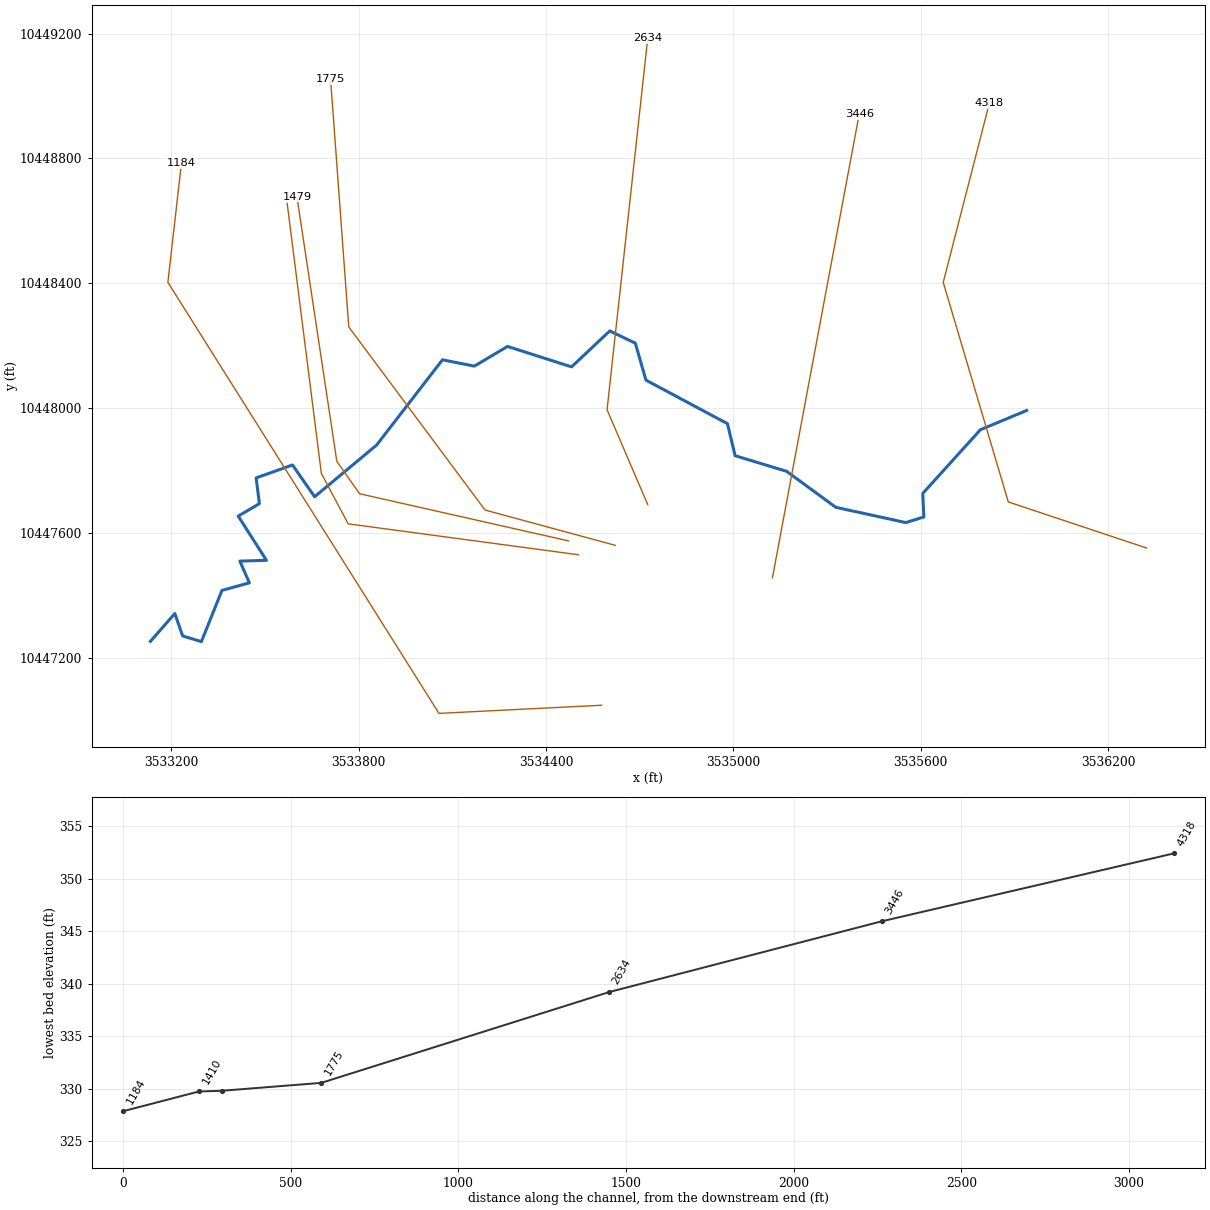
--- STEELE CREEK TRIB 13.prj (project) ---

Proj Title=STEELE CREEK TRIB 13 Base Level Engineering
Current Plan=p01
Default Exp/Contr=0.3,0.1
English Units
Geom File=g01
Flow File=f01
Plan File=p01
BEGIN DESCRIPTION:
STEELE CREEK TRIB 13
END DESCRIPTION:

--- STEELE CREEK TRIB 13.p01 (plan) ---

Plan Title=Multiple Run
Short Identifier=Multiple
Geom File=g01
Flow File=f01
Subcritical Flow
K Sum by GR= 0
Std Step Tol= 0.01
Critical Tol= 0.01
Num of Std Step Trials= 20
Max Error Tol= 0.3
Flow Tol Ratio= 0.001
Split Flow NTrial= 30
Split Flow Tol= 0.02
Split Flow Ratio= 0.02
Log Output Level= 0
Friction Slope Method= 1
Unsteady Friction Slope Method= 2
Unsteady Bridges Friction Slope Method= 1
Parabolic Critical Depth
Global Vel Dist=  1 , 1 , 1
Global Log Level= 0
CheckData=True
Encroach Param= -1, 0, 0, 0
BEGIN DESCRIPTION:
Multiple Run
END DESCRIPTION:

--- STEELE CREEK TRIB 13.f01 (steady flow) ---

Flow Title=Multiple
Number of Profiles=7
Profile Names=10-year,25-year,50-year,1pct_min,100-year,1pct_plu,500-year
River Rch & RM= STEELE CREEK TRI,Reach-1,4318
     661     888    1070     943    1276    1725    1806
Boundary for River Rch & Prof#=STEELE CREEK TRI,Reach-1,1
Up Type=0
Dn Type=3
Dn Slope=0.005
Boundary for River Rch & Prof#=STEELE CREEK TRI,Reach-1,2
Up Type=0
Dn Type=3
Dn Slope=0.005
Boundary for River Rch & Prof#=STEELE CREEK TRI,Reach-1,3
Up Type=0
Dn Type=3
Dn Slope=0.005
Boundary for River Rch & Prof#=STEELE CREEK TRI,Reach-1,4
Up Type=0
Dn Type=3
Dn Slope=0.005
Boundary for River Rch & Prof#=STEELE CREEK TRI,Reach-1,5
Up Type=0
Dn Type=3
Dn Slope=0.005
Boundary for River Rch & Prof#=STEELE CREEK TRI,Reach-1,6
Up Type=0
Dn Type=3
Dn Slope=0.005
Boundary for River Rch & Prof#=STEELE CREEK TRI,Reach-1,7
Up Type=0
Dn Type=3
Dn Slope=0.005

--- STEELE CREEK TRIB 13.g01 (geometry) ---

Geom Title=Existing Conditions

River Reach=STEELE CREEK TRI,Reach-1
Reach XY= 30
      3535939.33     10447992.91      3535791.32     10447931.34
      3535606.77     10447727.40      3535610.24     10447651.98
      3535552.52     10447634.01      3535328.23     10447682.86
      3535170.68     10447798.19      3535005.76     10447848.13
      3534981.26     10447950.68      3534720.33     10448090.13
      3534686.31     10448208.35      3534604.50     10448247.71
      3534482.13     10448132.53      3534277.08     10448198.07
      3534170.96     10448134.93      3534068.84     10448155.23
      3533857.99     10447882.36      3533659.34     10447716.65
      3533588.59     10447818.40      3533472.13     10447777.09
      3533482.55     10447694.63      3533414.84     10447654.70
      3533505.12     10447513.20      3533420.05     10447510.60
      3533450.43     10447441.15      3533362.76     10447416.85
      3533296.79     10447252.79      3533236.89     10447271.01
      3533211.72     10447342.72      3533133.59     10447253.65

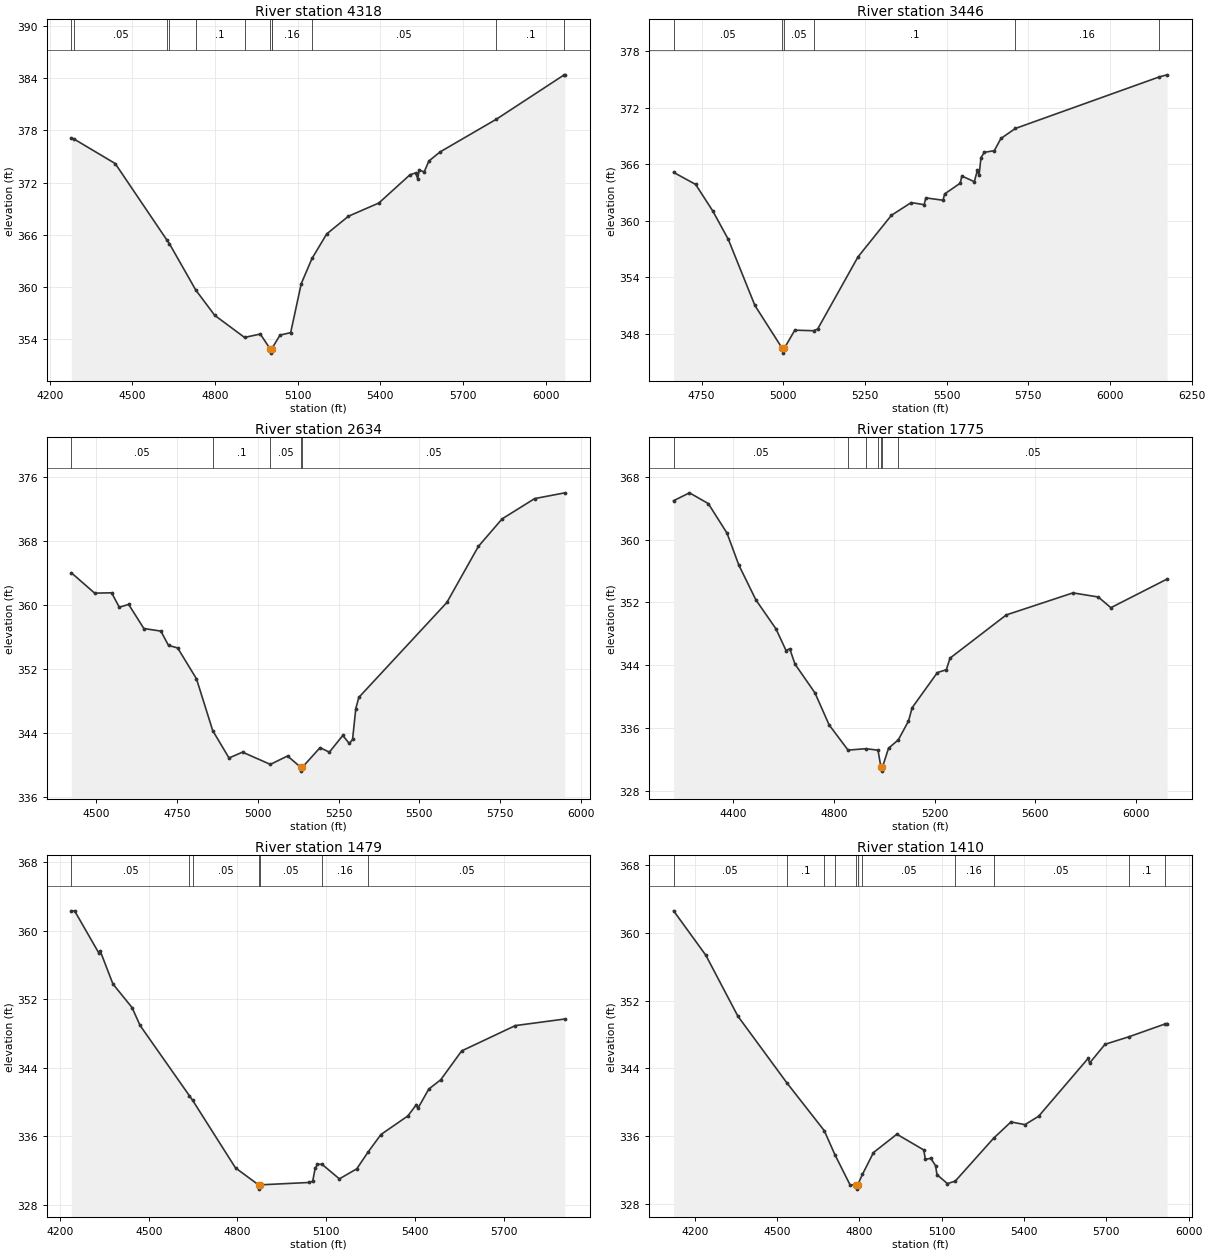
Type RM Length L Ch R = 1,4318,872,872,872
BEGIN DESCRIPTION:
STEELE CREEK TRIB 13 8.0
END DESCRIPTION:
XS GIS Cut Line= 4
      3536323.26     10447552.56      3535880.53     10447700.14
      3535672.20     10448403.27      3535819.76     10448976.15
#Sta/Elev= 30
  4278.5  377.10  4287.9  377.00  4437.8  374.18  4626.1  365.37  4634.8  364.97
  4730.0  359.68  4798.9  356.77  4907.3  354.23  4964.5  354.62  5000.0  352.93
  5002.7  352.43  5006.0  352.93  5008.5  353.06  5036.2  354.50  5074.7  354.78
  5113.1  360.40  5152.3  363.30  5205.7  366.11  5284.6  368.14  5394.7  369.65
  5507.8  372.89  5528.5  373.11  5536.0  372.42  5541.1  373.42  5559.5  373.23
  5576.7  374.48  5617.4  375.52  5821.6  379.27  6067.8  384.36  6070.1  384.36
#Mann=12,-1,0
  4278.5     0.1       0  4287.9    0.05       0  4626.1     0.1       0
  4634.8    0.05       0  4730.0     0.1       0  4907.3    0.05       0
  5000.0   0.035       0  5006.0    0.05       0  5008.5    0.16       0
  5152.3    0.05       0  5821.6     0.1       0  6067.8    0.05       0
Bank Sta=5000,5006
Exp/Cntr=0.3,0.1

Type RM Length L Ch R = 1,3446,812,812,812
BEGIN DESCRIPTION:
STEELE CREEK TRIB 13 7.0
END DESCRIPTION:
XS GIS Cut Line= 2
      3535125.32     10447457.08      3535403.11     10448941.51
#Sta/Elev= 30
  4664.5  365.16  4731.9  363.88  4784.5  361.05  4831.9  358.04  4913.3  351.02
  4997.1  346.46  4999.8  345.96  5003.1  346.46  5035.4  348.40  5092.6  348.34
  5105.3  348.52  5228.7  356.18  5331.0  360.60  5391.5  361.95  5431.2  361.73
  5436.3  362.45  5488.9  362.20  5494.0  362.87  5541.5  364.01  5546.6  364.77
  5584.8  364.17  5594.1  365.39  5599.2  364.85  5605.1  366.72  5615.3  367.29
  5645.8  367.46  5666.2  368.76  5710.1  369.82  6150.7  375.30  6174.7  375.52
#Mann=6,-1,0
  4664.5    0.05       0  4997.1    0.03       0  5003.1    0.05       0
  5092.6     0.1       0  5710.1    0.16       0  6150.7    0.05       0
Bank Sta=4997.1,5003.1
Exp/Cntr=0.3,0.1

Type RM Length L Ch R = 1,2634,859,859,859
BEGIN DESCRIPTION:
STEELE CREEK TRIB 13 5.0
END DESCRIPTION:
XS GIS Cut Line= 3
      3534726.01     10447691.48      3534595.81     10447995.28
      3534726.02     10449184.55
#Sta/Elev= 30
  4423.2  363.99  4495.3  361.45  4547.9  361.49  4571.5  359.69  4600.5  360.04
  4647.6  357.03  4700.2  356.71  4723.8  354.92  4752.1  354.61  4810.4  350.75
  4860.6  344.29  4911.0  340.87  4952.8  341.60  5039.0  340.07  5092.1  341.12
  5132.3  339.73  5135.0  339.23  5138.3  339.73  5192.7  342.16  5221.4  341.60
  5263.1  343.68  5283.2  342.68  5293.3  343.19  5303.3  347.04  5312.6  348.43
  5585.0  360.28  5682.5  367.28  5756.0  370.72  5856.6  373.25  5950.1  373.97
#Mann=5,-1,0
  4423.2    0.05       0  4860.6     0.1       0  5039.0    0.05       0
  5132.3    0.07       0  5138.3    0.05       0
Bank Sta=5132.3,5138.3
Exp/Cntr=0.3,0.1

Type RM Length L Ch R = 1,1775,296,296,296
BEGIN DESCRIPTION:
STEELE CREEK TRIB 13 2.0
END DESCRIPTION:
XS GIS Cut Line= 4
      3534621.89     10447561.24      3534205.18     10447674.10
      3533768.74     10448260.36      3533710.39     10449054.33
#Sta/Elev= 30
  4164.2  364.93  4227.2  365.93  4301.7  364.57  4376.2  360.81  4423.0  356.76
  4490.6  352.34  4570.3  348.66  4610.5  345.90  4625.1  346.13  4645.9  344.18
  4725.2  340.52  4781.5  336.45  4856.6  333.25  4927.4  333.43  4975.4  333.24
  4987.1  331.08  4989.8  330.58  4993.1  331.08  5017.2  333.49  5056.0  334.55
  5096.4  336.94  5111.0  338.64  5211.1  343.10  5246.6  343.46  5261.2  344.93
  5484.5  350.42  5749.2  353.22  5849.5  352.70  5899.7  351.34  6122.9  354.98
#Mann=7,-1,0
  4164.2    0.05       0  4856.6    0.16       0  4927.4    0.05       0
  4975.4    0.16       0  4987.1    0.07       0  4993.1    0.16       0
  5056.0    0.05       0
Bank Sta=4987.1,4993.1
Exp/Cntr=0.3,0.1

Type RM Length L Ch R = 1,1479,69,69,69
BEGIN DESCRIPTION:
Mapping XS ccfc175f
END DESCRIPTION:
XS GIS Cut Line= 4
      3534472.59     10447575.29      3533803.33     10447726.33
      3533730.41     10447830.49      3533602.82     10448676.78
#Sta/Elev= 30
  4238.1  362.35  4249.1  362.35  4330.4  357.46  4335.5  357.68  4378.8  353.80
  4443.6  351.04  4470.3  348.97  4637.7  340.73  4647.9  340.23  4793.3  332.31
  4871.2  330.33  4873.9  329.83  4877.2  330.33  5043.2  330.61  5054.5  330.76
  5062.6  332.25  5070.6  332.72  5085.6  332.74  5144.6  331.03  5203.4  332.20
  5241.0  334.13  5285.1  336.21  5376.1  338.38  5405.2  339.71  5410.2  339.27
  5446.9  341.52  5487.4  342.61  5558.2  345.98  5739.7  348.94  5907.2  349.71
#Mann=7,-1,0
  4238.1    0.05       0  4637.7     0.1       0  4647.9    0.05       0
  4871.2    0.03       0  4877.2    0.05       0  5085.6    0.16       0
  5241.0    0.05       0
Bank Sta=4871.2,4877.2
Exp/Cntr=0.3,0.1

Type RM Length L Ch R = 1,1410,226,226,226
BEGIN DESCRIPTION:
Mapping XS 16997939
END DESCRIPTION:
XS GIS Cut Line= 4
      3534503.84     10447531.02      3533766.87     10447629.97
      3533680.93     10447791.43      3533571.55     10448656.05
#Sta/Elev= 30
  4123.2  362.60  4240.8  357.35  4357.0  350.19  4534.9  342.34  4672.1  336.66
  4710.8  333.83  4766.1  330.26  4787.9  330.26  4790.6  329.76  4793.9  330.26
  4811.0  331.49  4851.4  334.08  4936.6  336.24  5034.7  334.38  5040.4  333.27
  5060.0  333.40  5077.6  332.53  5082.7  331.47  5120.5  330.42  5148.9  330.69
  5288.8  335.76  5352.3  337.69  5403.3  337.37  5453.1  338.36  5633.7  345.20
  5638.8  344.64  5695.0  346.85  5782.1  347.74  5914.6  349.26  5921.2  349.30
#Mann=11,-1,0
  4123.2    0.05       0  4534.9     0.1       0  4672.1    0.05       0
  4710.8     0.1       0  4787.9    0.03       0  4793.9     0.1       0
  4811.0    0.05       0  5148.9    0.16       0  5288.8    0.05       0
  5782.1     0.1       0  5914.6    0.05       0
Bank Sta=4787.9,4793.9
Exp/Cntr=0.3,0.1

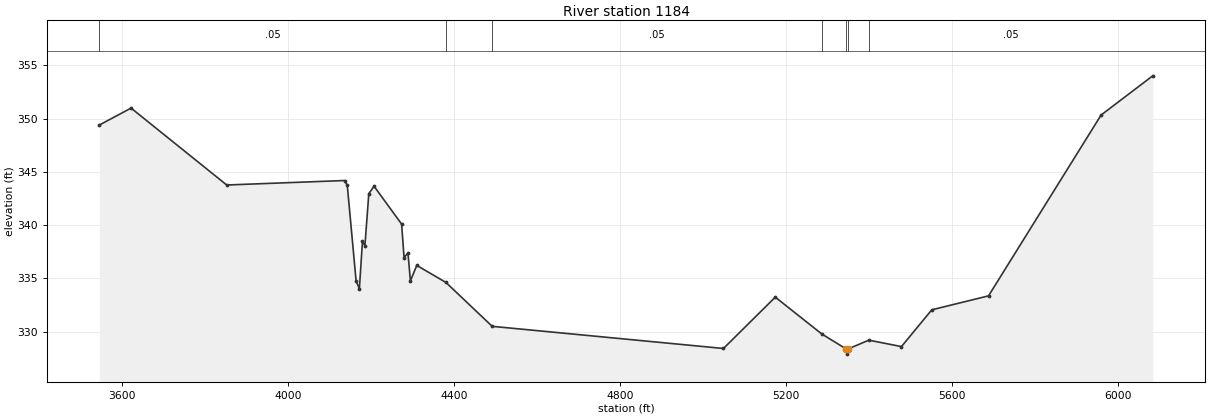
Type RM Length L Ch R = 1,1184,0,0,0
BEGIN DESCRIPTION:
STEELE CREEK TRIB 13 1.0
END DESCRIPTION:
XS GIS Cut Line= 4
      3534578.40     10447049.10      3534057.61     10447023.06
      3533189.56     10448403.27      3533232.96     10448785.18
#Sta/Elev= 30
  3546.4  349.39  3622.8  350.98  3853.1  343.76  4137.0  344.18  4143.4  343.72
  4164.6  334.76  4172.5  334.01  4179.9  338.46  4185.9  338.07  4195.2  342.95
  4207.9  343.64  4274.2  340.09  4280.1  336.95  4289.5  337.37  4295.4  334.76
  4310.7  336.21  4380.9  334.61  4492.3  330.49  5049.1  328.41  5173.9  333.23
  5285.9  329.77  5344.0  328.38  5346.7  327.88  5350.0  328.38  5399.1  329.19
  5477.7  328.59  5550.7  332.04  5687.3  333.35  5958.4  350.33  6082.7  354.01
#Mann=7,-1,0
  3546.4    0.05       0  4380.9     0.1       0  4492.3    0.05       0
  5285.9     0.1       0  5344.0    0.03       0  5350.0     0.1       0
  5399.1    0.05       0
Bank Sta=5344,5350
Exp/Cntr=0.3,0.1

Chan Stop Cuts=-1