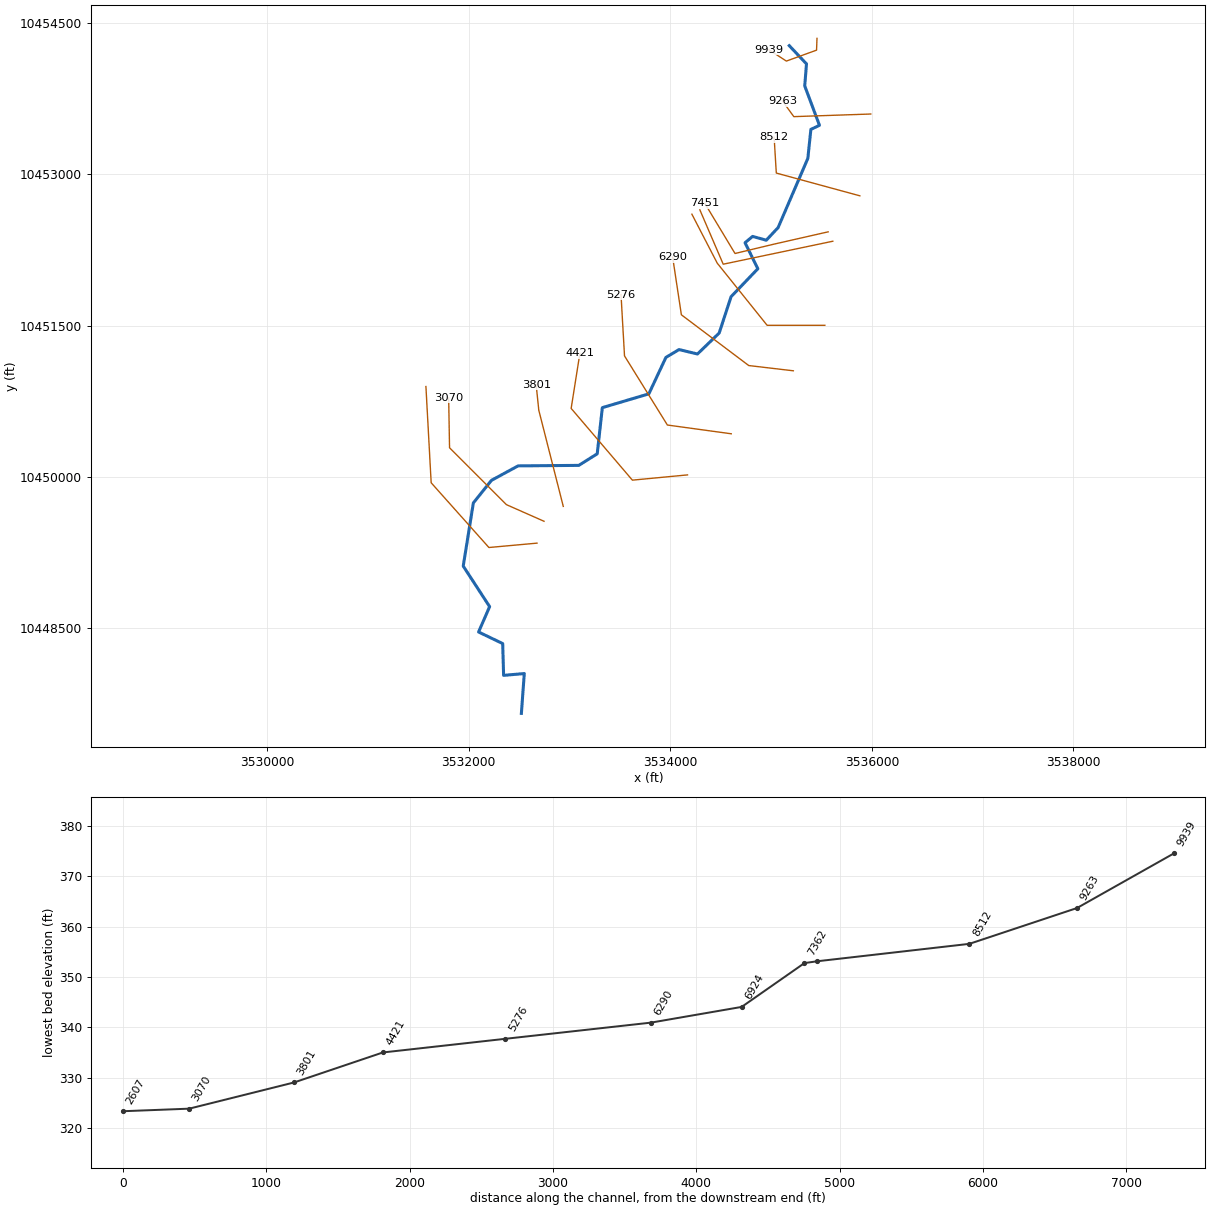
--- STEELE CREEK TRIB 14 3.prj (project) ---

Proj Title=STEELE CREEK TRIB 14 3 Base Level Engineering
Current Plan=p01
Default Exp/Contr=0.3,0.1
English Units
Geom File=g01
Flow File=f01
Plan File=p01
Y Axis Title=Elevation
X Axis Title(PF)=Main Channel Distance
X Axis Title(XS)=Station
BEGIN DESCRIPTION:
STEELE CREEK TRIB 14 3
END DESCRIPTION:
DSS Export Rating Curves= 0
DSS Export Rating Curve Sorted= 0
DSS Export Volume Flow Curves= 0
DXF OffsetX= 0
DXF OffsetY= 0
DXF ScaleX= 1
DXF ScaleY= 10

--- STEELE CREEK TRIB 14 3.p01 (plan) ---

Plan Title=Multiple Run
Short Identifier=Multiple
Geom File=g01
Flow File=f01
Subcritical Flow
K Sum by GR= 0
Std Step Tol= 0.01
Critical Tol= 0.01
Num of Std Step Trials= 20
Max Error Tol= 0.3
Flow Tol Ratio= 0.001
Split Flow NTrial= 30
Split Flow Tol= 0.02
Split Flow Ratio= 0.02
Log Output Level= 0
Friction Slope Method= 1
Unsteady Friction Slope Method= 2
Unsteady Bridges Friction Slope Method= 1
Parabolic Critical Depth
Global Vel Dist=  1 , 1 , 1
Global Log Level= 0
CheckData=True
Encroach Param= -1, 0, 0, 0
BEGIN DESCRIPTION:
Multiple Run
END DESCRIPTION:

--- STEELE CREEK TRIB 14 3.f01 (steady flow) ---

Flow Title=Multiple
Program Version=4.10
Number of Profiles= 7
Profile Names=10-year,25-year,50-year,1pct_min,100-year,1pct_plu,500-year
River Rch & RM=STEELE CREEK TRI,Reach-1         ,9939
     914    1248    1521    1353    1830    2475    2640
Boundary for River Rch & Prof#=STEELE CREEK TRI,Reach-1         , 1
Up Type= 0
Dn Type= 3
Dn Slope=0.0012
Boundary for River Rch & Prof#=STEELE CREEK TRI,Reach-1         , 2
Up Type= 0
Dn Type= 3
Dn Slope=0.0012
Boundary for River Rch & Prof#=STEELE CREEK TRI,Reach-1         , 3
Up Type= 0
Dn Type= 3
Dn Slope=0.0012
Boundary for River Rch & Prof#=STEELE CREEK TRI,Reach-1         , 4
Up Type= 0
Dn Type= 3
Dn Slope=0.0012
Boundary for River Rch & Prof#=STEELE CREEK TRI,Reach-1         , 5
Up Type= 0
Dn Type= 3
Dn Slope=0.0012
Boundary for River Rch & Prof#=STEELE CREEK TRI,Reach-1         , 6
Up Type= 0
Dn Type= 3
Dn Slope=0.0012
Boundary for River Rch & Prof#=STEELE CREEK TRI,Reach-1         , 7
Up Type= 0
Dn Type= 3
Dn Slope=0.0012
DSS Import GetInterval= 0
DSS Import GetPeak= 0
DSS Import FillOption= 0

--- STEELE CREEK TRIB 14 3.g01 (geometry) ---

Geom Title=Existing Conditions
Program Version=4.10

River Reach=STEELE CREEK TRI,Reach-1
Reach XY= 30
      3535180.01      10454276.8       3535350.8     10454096.13
      3535333.61     10453877.33      3535479.63     10453486.46
      3535394.45     10453445.78       3535364.5     10453158.68
      3535069.21     10452471.36      3534952.02     10452346.36
       3534816.6     10452384.13      3534741.42     10452321.57
      3534868.27     10452063.26      3534602.75     10451786.06
      3534484.53     10451425.14      3534269.14     10451217.41
      3534086.33     10451261.43      3533956.19     10451183.44
      3533786.82      10450821.9       3533325.4     10450685.14
      3533274.64     10450227.19      3533091.79     10450112.25
      3532489.41     10450107.36      3532225.34     10449963.71
      3532045.81     10449740.11      3531945.09     10449112.81
      3532207.11      10448710.6      3532097.29       10448459.
      3532336.77     10448344.18      3532345.77     10448028.86
      3532551.02     10448046.77      3532522.11     10447651.64

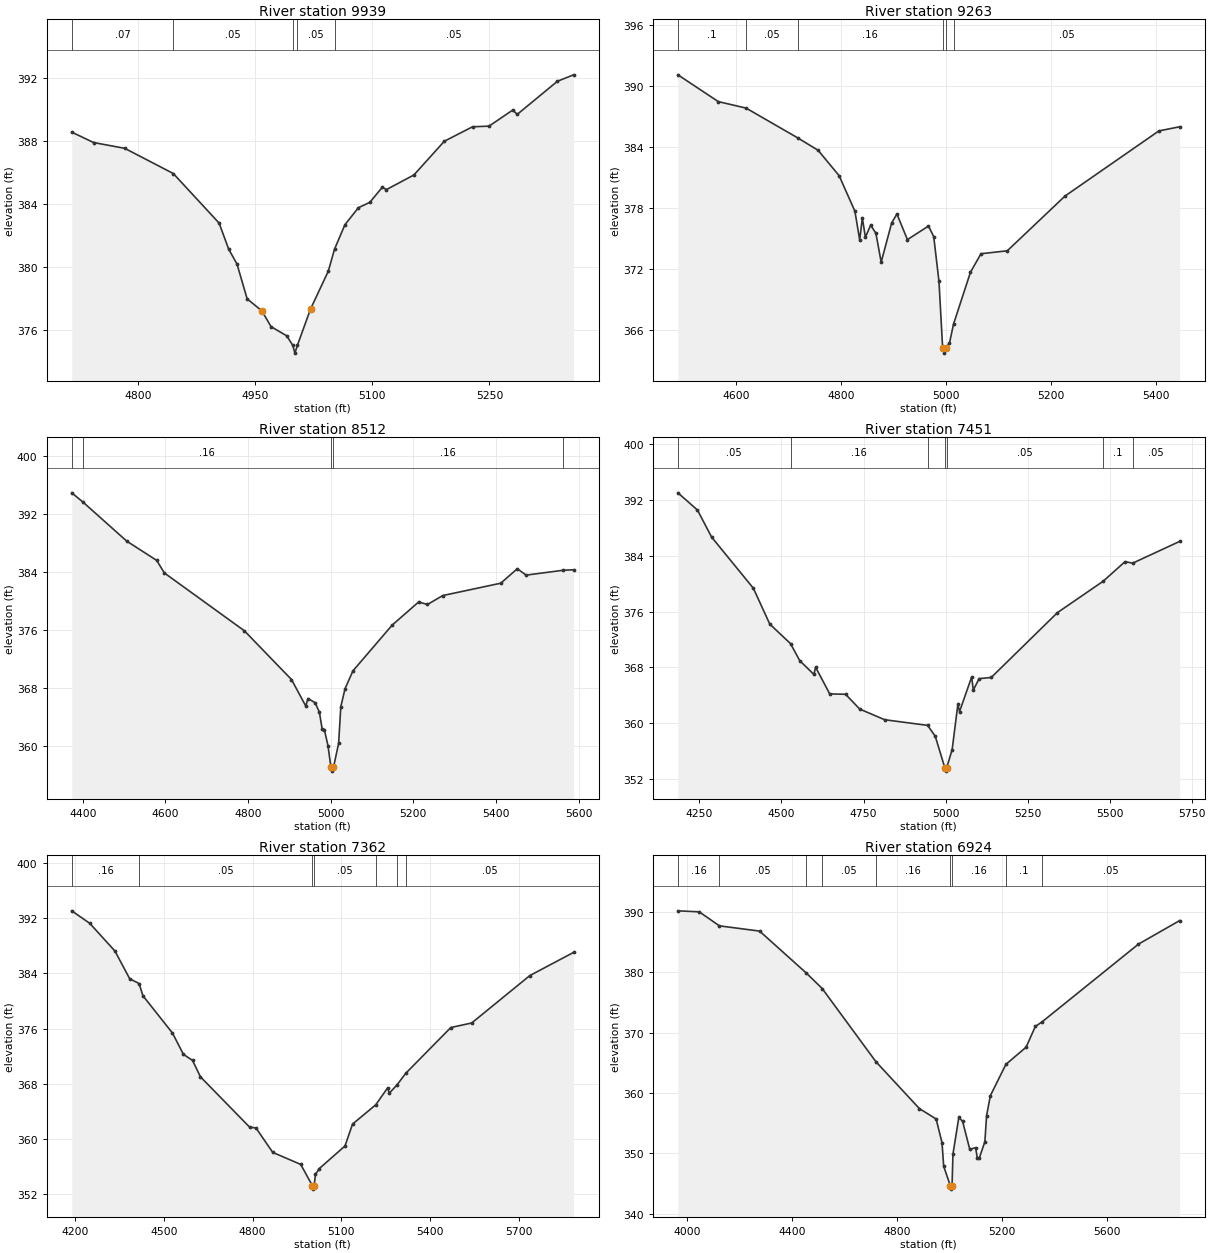
Type RM Length L Ch R = 1 ,9939    ,676,676,676
BEGIN DESCRIPTION:
STEELE CREEK TRIB 14.3 17.0
END DESCRIPTION:
XS GIS Cut Line= 4
      3535455.18     10454349.48      3535450.84     10454232.26
      3535151.36     10454123.75      3534977.75      10454236.6
#Sta/Elev= 30
  4714.9  388.55  4742.8  387.89  4782.8  387.52    4845  385.92  4903.7  382.77
  4915.9  381.12  4926.6  380.17  4939.6  377.96  4958.5  377.19  4970.3  376.19
  4990.3  375.61    4998  375.01  5000.8  374.51    5004  375.01  5020.9  377.32
  5043.6  379.72  5051.6  381.12  5064.9  382.67  5082.2  383.75  5096.8  384.09
  5112.8  385.05  5118.1   384.9  5153.3  385.83  5192.2  387.97  5228.4  388.89
  5249.5  388.93  5279.8  389.95  5285.7  389.68  5337.1  391.78  5357.8  392.19
#Mann= 5 ,-1 , 0
  4714.9     .07       0    4845     .05       0    4998     .03       0
    5004     .05       0  5051.6     .05       0
Bank Sta=4958.5,5020.9
XS Rating Curve= 0 ,0
Exp/Cntr=0.3,0.1

Type RM Length L Ch R = 1 ,9263    ,751,751,751
BEGIN DESCRIPTION:
STEELE CREEK TRIB 14.3 16.0
END DESCRIPTION:
XS GIS Cut Line= 3
      3535988.99     10453598.58      3535225.15     10453572.54
      3535113.08     10453727.71
#Sta/Elev= 30
  4489.3  391.12  4566.2  388.48  4619.1  387.84  4717.9  384.89  4756.3  383.68
  4796.4  381.17  4826.4  377.67  4835.5  374.84  4840.5  377.01  4846.4  375.11
  4856.4   376.3  4866.4  375.49  4876.4  372.65  4896.4  376.52  4906.4   377.4
  4926.4  374.87  4966.5  376.21  4976.5  375.17  4986.5  370.75  4993.5  364.18
  4996.2  363.68  4999.5  364.18  5006.5  364.67  5014.2  366.54  5046.5  371.66
  5066.5  373.48  5116.6  373.77  5226.6  379.17  5405.3  385.59    5445     386
#Mann= 6 ,-1 , 0
  4489.3      .1       0  4619.1     .05       0  4717.9     .16       0
  4993.5     .07       0  4999.5     .16       0  5014.2     .05       0
Bank Sta=4993.5,4999.5
XS Rating Curve= 0 ,0
Exp/Cntr=0.3,0.1

Type RM Length L Ch R = 1 ,8512    ,1061,1061,1061
BEGIN DESCRIPTION:
STEELE CREEK TRIB 14.3 15.0
END DESCRIPTION:
XS GIS Cut Line= 3
      3535880.49     10452786.96      3535051.54     10453012.64
       3535029.9     10453367.55
#Sta/Elev= 30
  4373.2  394.89  4400.5  393.61  4506.3  388.24  4578.8  385.59  4597.4  383.86
    4791   375.9  4905.1  369.19  4939.7  365.54  4944.9  366.57  4962.3     366
  4972.6   364.7  4979.5  362.33  4984.6   362.3  4993.4   360.1  5000.7  357.08
  5003.5  356.58  5006.7  357.08  5019.2  360.41  5024.5  365.46  5034.8  367.93
  5053.8  370.38  5148.8  376.68  5212.8  379.86  5234.3  379.52  5271.4  380.75
  5411.7  382.45  5451.7  384.44  5473.1  383.56  5562.4  384.23  5587.9   384.3
#Mann= 5 ,-1 , 0
  4373.2     .05       0  4400.5     .16       0  5000.7     .07       0
  5006.7     .16       0  5562.4     .05       0
Bank Sta=5000.7,5006.7
XS Rating Curve= 0 ,0
Exp/Cntr=0.3,0.1

Type RM Length L Ch R = 1 ,7451    ,89,89,89
BEGIN DESCRIPTION:
STEELE CREEK TRIB 14.3 13.1
END DESCRIPTION:
XS GIS Cut Line= 4
      3535566.34     10452429.57      3535021.69     10452305.88
      3534641.91     10452214.73      3534342.44     10452711.69
#Sta/Elev= 30
  4184.4  393.03    4244  390.56    4287  386.69  4414.3  379.35  4464.5   374.2
  4527.6  371.41  4555.8  368.96  4598.9  366.99    4604  368.03  4647.1   364.2
  4695.3  364.15  4738.4  362.03  4814.5   360.5  4945.4  359.69  4968.7  358.13
  4997.7  353.63  5000.5  353.13  5003.7  353.63  5020.2  356.23  5037.6  362.72
  5042.7  361.67  5079.6  366.62  5084.7  364.76  5102.4  366.39  5139.3  366.56
  5341.2  375.86  5480.8  380.37    5547  383.16  5570.5  382.95  5713.7  386.07
#Mann= 7 ,-1 , 0
  4184.4     .05       0  4527.6     .16       0  4945.4     .05       0
  4997.7    .035       0  5003.7     .05       0  5480.8      .1       0
  5570.5     .05       0
Bank Sta=4997.7,5003.7
XS Rating Curve= 0 ,0
Exp/Cntr=0.3,0.1

Type RM Length L Ch R = 1 ,7362    ,438,438,438
BEGIN DESCRIPTION:
STEELE CREEK TRIB 14.3 13.0
END DESCRIPTION:
XS GIS Cut Line= 3
      3535611.98     10452336.26      3534524.72      10452108.4
      3534292.96     10452647.73
#Sta/Elev= 30
  4187.8  393.07    4249  391.25    4334  387.24  4383.9  383.23  4415.6  382.54
  4428.7  380.77  4528.6  375.37  4565.7  372.28  4596.4  371.41  4623.3  369.03
  4790.5  361.71  4810.9  361.64  4867.8  358.09  4962.5  356.35    5002  353.27
  5004.8  352.77    5008  353.27  5012.4  354.91  5025.5  355.75  5112.3  359.02
  5137.9  362.19  5216.4  364.98  5256.9  367.45    5262  366.65  5289.1   367.9
  5317.8  369.54  5470.4  376.17  5541.1  376.83  5737.6  383.69  5885.7  387.05
#Mann= 7 ,-1 , 0
  4187.8     .16       0  4415.6     .05       0    5002     .04       0
    5008     .05       0  5216.4     .16       0  5289.1      .1       0
  5317.8     .05       0
Bank Sta=5002,5008
XS Rating Curve= 0 ,0
Exp/Cntr=0.3,0.1

Type RM Length L Ch R = 1 ,6924    ,634,634,634
BEGIN DESCRIPTION:
STEELE CREEK TRIB 14.3 11.0
END DESCRIPTION:
XS GIS Cut Line= 4
      3535533.32     10451502.22      3534960.39     10451502.22
       3534465.6     10452118.54      3534213.87     10452604.64
#Sta/Elev= 30
  3965.2  390.18  4046.4  390.01  4123.4  387.69  4276.4  386.82  4454.2  379.87
  4514.5  377.31  4719.1  365.19  4884.4  357.43  4948.4   355.7  4970.8  351.77
  4977.2  347.86    5003  344.58  5005.8  344.08    5009  344.58  5012.4  349.87
  5034.8  355.96  5049.2  355.31  5076.5  350.67  5098.8  350.95  5105.2  349.21
  5113.2  349.29    5134  351.94  5140.5  356.24  5154.9  359.56  5213.9  364.74
  5290.9  367.59  5326.1  371.02  5351.8  371.79  5718.6  384.66  5875.9  388.57
#Mann= 9 ,-1 , 0
  3965.2     .16       0  4123.4     .05       0  4454.2     .16       0
  4514.5     .05       0  4719.1     .16       0    5003     .07       0
    5009     .16       0  5213.9      .1       0  5351.8     .05       0
Bank Sta=5003,5009
XS Rating Curve= 0 ,0
Exp/Cntr=0.3,0.1

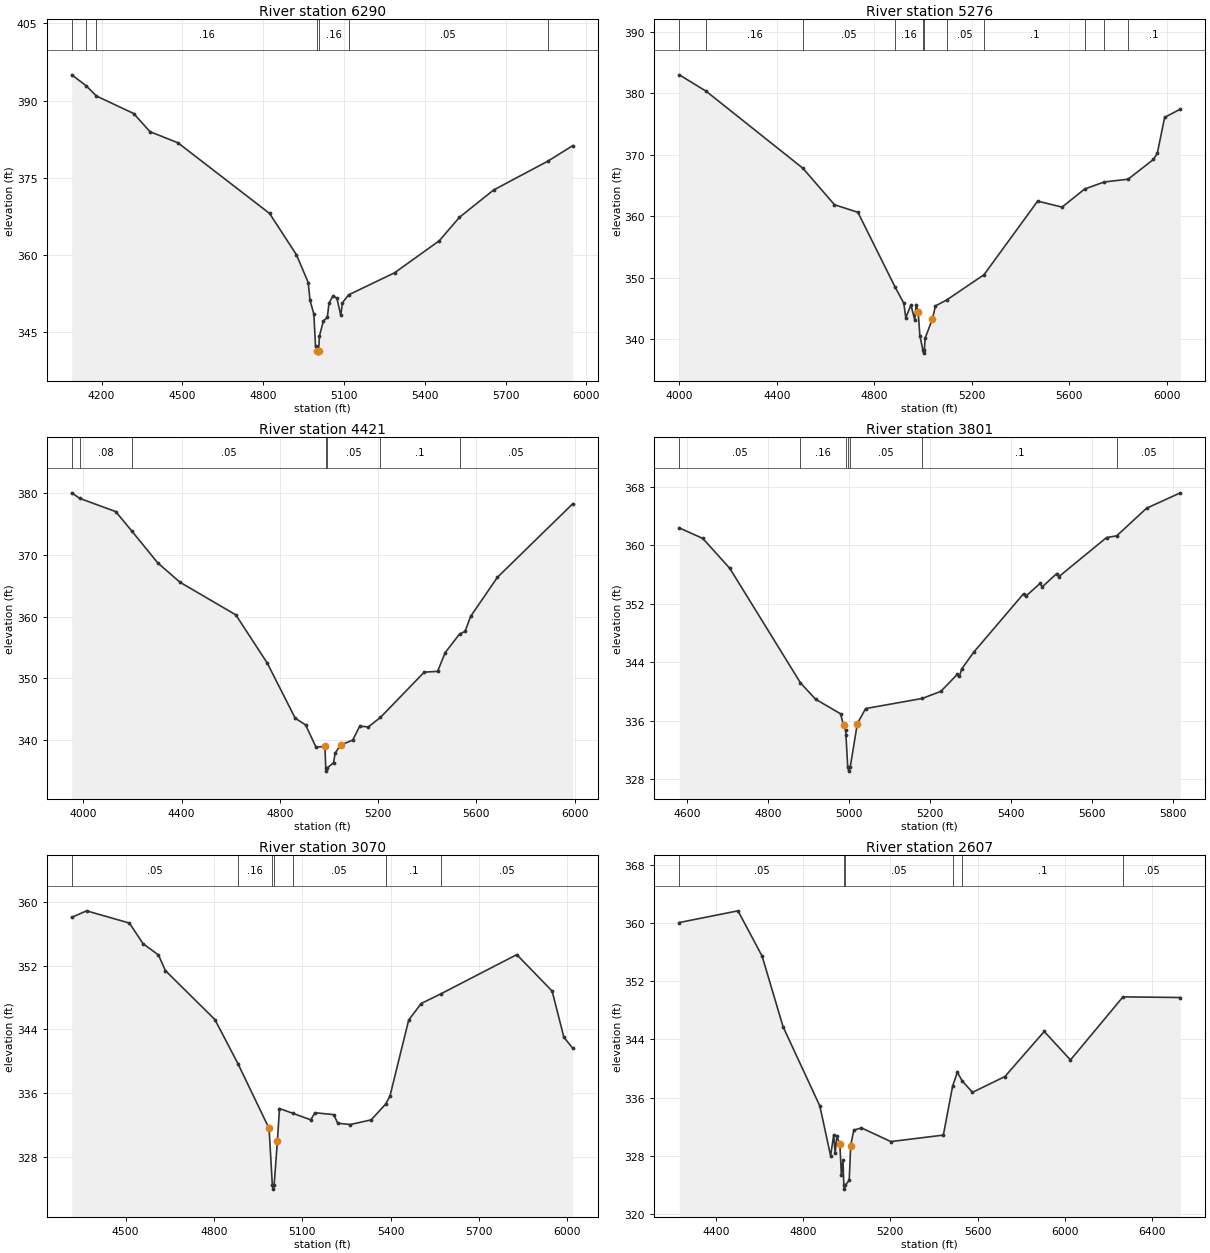
Type RM Length L Ch R = 1 ,6290    ,1014,1014,1014
BEGIN DESCRIPTION:
STEELE CREEK TRIB 14.3 10.0
END DESCRIPTION:
XS GIS Cut Line= 4
      3535220.78     10451050.84       3534778.1     10451102.92
       3534109.7     10451606.39       3534023.1     10452177.93
#Sta/Elev= 30
  4089.1  394.99  4142.8  392.87  4180.8  390.88  4319.4  387.47  4379.8  383.95
  4483.3   381.8  4823.8  368.08  4923.7  360.05  4967.5  354.65  4973.7  351.28
  4988.3  348.52  4994.5   342.3  4999.9  341.46  5002.6  340.96  5005.9  341.46
  5009.1  344.31  5023.7  347.21  5038.3   347.9  5044.5  350.67  5059.1  352.08
  5073.7  351.64  5088.2  348.32  5094.5  350.75  5117.2  352.27  5288.1  356.56
  5454.3  362.79  5528.7  367.32  5655.5  372.62  5857.5  378.24  5949.7  381.24
#Mann= 7 ,-1 , 0
  4089.1     .05       0  4142.8      .1       0  4180.8     .16       0
  4999.9     .07       0  5005.9     .16       0  5117.2     .05       0
  5857.5      .1       0
Bank Sta=4999.9,5005.9
XS Rating Curve= 0 ,0
Exp/Cntr=0.3,0.1

Type RM Length L Ch R = 1 ,5276    ,855,855,855
BEGIN DESCRIPTION:
STEELE CREEK TRIB 14.3 8.0
END DESCRIPTION:
XS GIS Cut Line= 4
      3534604.46     10450425.84      3533970.81     10450512.64
      3533545.46     10451198.41      3533510.74     10451806.08
#Sta/Elev= 30
  4000.5  383.03  4110.6  380.36  4507.5  367.83  4636.9   361.9    4733  360.67
  4885.4  348.52  4921.3  345.88  4929.4  343.53  4950.7  345.58  4966.1  343.16
  4971.9  345.66  4980.1  344.49  4987.3  340.58  4999.7  338.26  5002.4  337.76
  5005.7  338.26  5008.6  340.17    5039  343.37  5051.1  345.45  5096.7  346.39
  5250.4  350.52  5470.3  362.49  5570.5  361.51  5662.9  364.45    5743   365.6
  5841.1  366.05  5945.1  369.26  5961.1  370.26  5991.2  376.11  6055.7  377.45
#Mann= 11 ,-1 , 0
  4000.5     .05       0  4110.6     .16       0  4507.5     .05       0
  4885.4     .16       0  4999.7     .07       0  5005.7     .16       0
  5096.7     .05       0  5250.4      .1       0  5662.9     .05       0
    5743     .08       0  5841.1      .1       0
Bank Sta=4980.1,5039
XS Rating Curve= 0 ,0
Exp/Cntr=0.3,0.1

Type RM Length L Ch R = 1 ,4421    ,620,620,620
BEGIN DESCRIPTION:
STEELE CREEK TRIB 14.3 6.0
END DESCRIPTION:
XS GIS Cut Line= 4
       3534170.5     10450017.85      3533623.59     10449965.77
      3533015.95     10450677.57      3533102.75     10451224.44
#Sta/Elev= 30
    3953  379.96  3985.3  379.07  4132.2  376.93  4198.7  373.74    4303  368.66
  4393.4  365.54    4621  360.26  4748.4  352.51  4862.6  343.59  4904.6  342.52
  4947.1  338.93  4983.4  339.04  4986.9  335.55  4989.7  335.05  4992.9  335.55
  5018.5  336.42  5025.1  337.96    5047  339.26  5096.4  340.05    5125   342.3
  5160.1  342.19  5209.5  343.72  5387.4  351.02    5442  351.15  5472.8  354.17
  5531.1  357.17  5553.8   357.6  5576.2  360.01  5685.4  366.33    5992   378.2
#Mann= 7 ,-1 , 0
    3953     .05       0  3985.3     .08       0  4198.7     .05       0
  4986.9     .03       0  4992.9     .05       0  5209.5      .1       0
  5531.1     .05       0
Bank Sta=4983.4,5047
XS Rating Curve= 0 ,0
Exp/Cntr=0.3,0.1

Type RM Length L Ch R = 1 ,3801    ,731,731,731
BEGIN DESCRIPTION:
STEELE CREEK TRIB 14.3 4.0
END DESCRIPTION:
XS GIS Cut Line= 3
      3532937.83     10449705.33      3532694.77     10450660.21
      3532668.73     10450911.94
#Sta/Elev= 30
  4580.8  362.37  4638.9  360.93  4705.7  356.83  4880.2  341.18  4917.5  338.94
  4979.4  336.94  4986.8  335.35    4992  334.71  4992.6  334.11  4997.1   329.6
  4999.8   329.1  5003.1   329.6  5020.7  335.59  5041.3  337.66    5181  339.04
  5227.1  340.01    5268  342.34  5273.2   342.1  5278.7  343.08  5308.9   345.4
  5431.7  353.37  5436.8  353.01  5472.6  354.78  5477.7   354.3  5513.5  356.12
  5518.6  355.69  5636.7  361.05  5661.9  361.29  5735.6  365.06  5819.2  367.17
#Mann= 7 ,-1 , 0
  4580.8     .05       0  4880.2     .16       0  4992.6     .05       0
  4997.1     .03       0  5003.1     .05       0    5181      .1       0
  5661.9     .05       0
Bank Sta=4986.8,5020.7
XS Rating Curve= 0 ,0
Exp/Cntr=0.3,0.1

Type RM Length L Ch R = 1 ,3070    ,463,463,463
BEGIN DESCRIPTION:
STEELE CREEK TRIB 14.3 2.0
END DESCRIPTION:
XS GIS Cut Line= 4
      3532746.84     10449557.78      3532373.59     10449722.71
      3531809.35     10450286.95      3531800.67     10450781.75
#Sta/Elev= 30
    4317   358.1  4367.5  358.92  4512.8  357.38  4559.4  354.78  4611.5  353.37
  4634.8  351.41  4803.1  345.24  4881.2   339.7    4987  331.54  4998.1  324.41
  5000.9  323.91  5004.1  324.41  5015.3  329.99  5022.3  334.05  5067.6  333.45
  5128.4  332.63  5142.6  333.52  5206.2  333.28  5220.3   332.2  5262.8  332.04
  5333.5  332.62  5382.4   334.6  5397.1  335.58  5460.8  345.17  5503.2  347.26
  5571.4   348.5  5827.8  353.41  5947.8  348.83  5987.8  343.01  6017.9  341.64
#Mann= 7 ,-1 , 0
    4317     .05       0  4881.2     .16       0  4998.1     .07       0
  5004.1     .16       0  5067.6     .05       0  5382.4      .1       0
  5571.4     .05       0
Bank Sta=4987,5015.3
XS Rating Curve= 0 ,0
Exp/Cntr=0.3,0.1

Type RM Length L Ch R = 1 ,2607    ,0,0,0
BEGIN DESCRIPTION:
STEELE CREEK TRIB 14.3 1.0
END DESCRIPTION:
XS GIS Cut Line= 4
      3532677.36     10449340.76      3532199.97     10449297.36
      3531627.06     10449939.72      3531574.97     10450894.62
#Sta/Elev= 30
    4233  360.06  4501.9  361.67  4612.3  355.45  4708.8  345.71  4877.1  334.83
  4926.4  327.98  4940.6  330.86  4947.3  328.37  4954.8  330.69    4969  329.56
  4975.7  325.38  4983.2  327.42  4986.9   323.9  4989.7   323.4  4992.9   323.9
  5011.7  324.62  5018.4  329.38  5032.6  331.51  5067.7  331.82  5202.3  329.94
  5443.1  330.83  5485.7  337.59  5507.4  339.47  5529.5  338.28  5576.6  336.71
  5725.2  338.88  5905.5  345.08  6025.7  341.16  6266.5  349.84  6529.4  349.75
#Mann= 6 ,-1 , 0
    4233     .05       0  4986.9     .03       0  4992.9     .05       0
  5485.7     .12       0  5529.5      .1       0  6266.5     .05       0
Bank Sta=4969,5018.4
XS Rating Curve= 0 ,0
Exp/Cntr=0.3,0.1

Chan Stop Cuts=-1
Use User Specified Reach Order=0
Composite Channel Slope=5