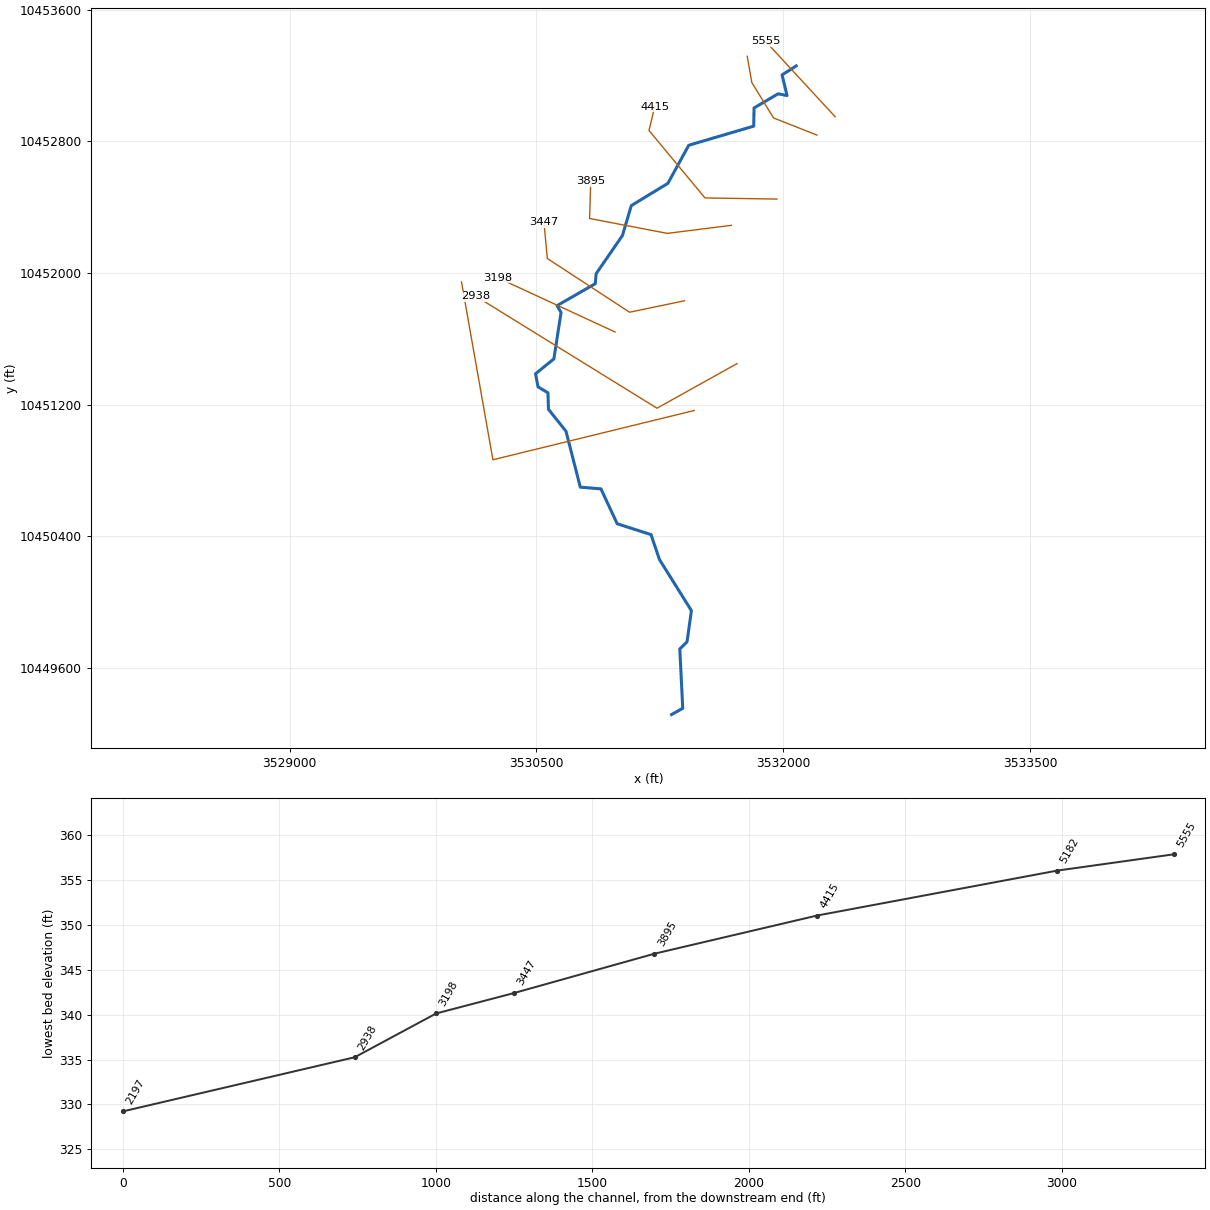
--- STEELE CREEK TRIB 15.prj (project) ---

Proj Title=STEELE CREEK TRIB 15 Base Level Engineering
Current Plan=p01
Default Exp/Contr=0.3,0.1
English Units
Geom File=g01
Flow File=f01
Plan File=p01
Y Axis Title=Elevation
X Axis Title(PF)=Main Channel Distance
X Axis Title(XS)=Station
BEGIN DESCRIPTION:
STEELE CREEK TRIB 15
END DESCRIPTION:
DSS Export Rating Curves= 0
DSS Export Rating Curve Sorted= 0
DSS Export Volume Flow Curves= 0
DXF OffsetX= 0
DXF OffsetY= 0
DXF ScaleX= 1
DXF ScaleY= 10

--- STEELE CREEK TRIB 15.p01 (plan) ---

Plan Title=Multiple Run
Short Identifier=Multiple
Geom File=g01
Flow File=f01
Subcritical Flow
K Sum by GR= 0
Std Step Tol= 0.01
Critical Tol= 0.01
Num of Std Step Trials= 20
Max Error Tol= 0.3
Flow Tol Ratio= 0.001
Split Flow NTrial= 30
Split Flow Tol= 0.02
Split Flow Ratio= 0.02
Log Output Level= 0
Friction Slope Method= 1
Unsteady Friction Slope Method= 2
Unsteady Bridges Friction Slope Method= 1
Parabolic Critical Depth
Global Vel Dist=  1 , 1 , 1
Global Log Level= 0
CheckData=True
Encroach Param= -1, 0, 0, 0
BEGIN DESCRIPTION:
Multiple Run
END DESCRIPTION:

--- STEELE CREEK TRIB 15.f01 (steady flow) ---

Flow Title=Multiple
Number of Profiles=7
Profile Names=10-year,25-year,50-year,1pct_min,100-year,1pct_plu,500-year
River Rch & RM= STEELE CREEK TRI,Reach-1,5555
     414     540     638     553     748    1011    1021
Boundary for River Rch & Prof#=STEELE CREEK TRI,Reach-1,1
Up Type=0
Dn Type=3
Dn Slope=0.005
Boundary for River Rch & Prof#=STEELE CREEK TRI,Reach-1,2
Up Type=0
Dn Type=3
Dn Slope=0.005
Boundary for River Rch & Prof#=STEELE CREEK TRI,Reach-1,3
Up Type=0
Dn Type=3
Dn Slope=0.005
Boundary for River Rch & Prof#=STEELE CREEK TRI,Reach-1,4
Up Type=0
Dn Type=3
Dn Slope=0.005
Boundary for River Rch & Prof#=STEELE CREEK TRI,Reach-1,5
Up Type=0
Dn Type=3
Dn Slope=0.005
Boundary for River Rch & Prof#=STEELE CREEK TRI,Reach-1,6
Up Type=0
Dn Type=3
Dn Slope=0.005
Boundary for River Rch & Prof#=STEELE CREEK TRI,Reach-1,7
Up Type=0
Dn Type=3
Dn Slope=0.005

--- STEELE CREEK TRIB 15.g01 (geometry) ---

Geom Title=Existing Conditions
Program Version=4.10

River Reach=STEELE CREEK TRI,Reach-1
Reach XY= 30
      3532079.29     10453257.76      3531993.13     10453203.07
      3532023.51     10453077.64      3531969.69     10453088.49
      3531822.99     10453002.34      3531820.82     10452891.64
        3531426.     10452775.54      3531299.22     10452544.18
      3531076.84     10452408.98      3531022.74       10452227.
      3530862.92     10451994.96      3530857.93     10451934.42
      3530625.51     10451801.17       3530649.6     10451758.85
      3530606.12     10451477.56      3530494.82     10451387.06
      3530509.66     10451307.64      3530570.08     10451271.44
       3530573.2     10451171.18      3530679.84     10451037.55
      3530766.64     10450698.05      3530892.29     10450687.61
      3530990.86     10450475.75      3531196.59      10450409.6
      3531247.72     10450258.47      3531442.11     10449948.05
      3531415.54     10449758.32      3531371.52     10449714.72
      3531389.49     10449354.04      3531321.64     10449316.45

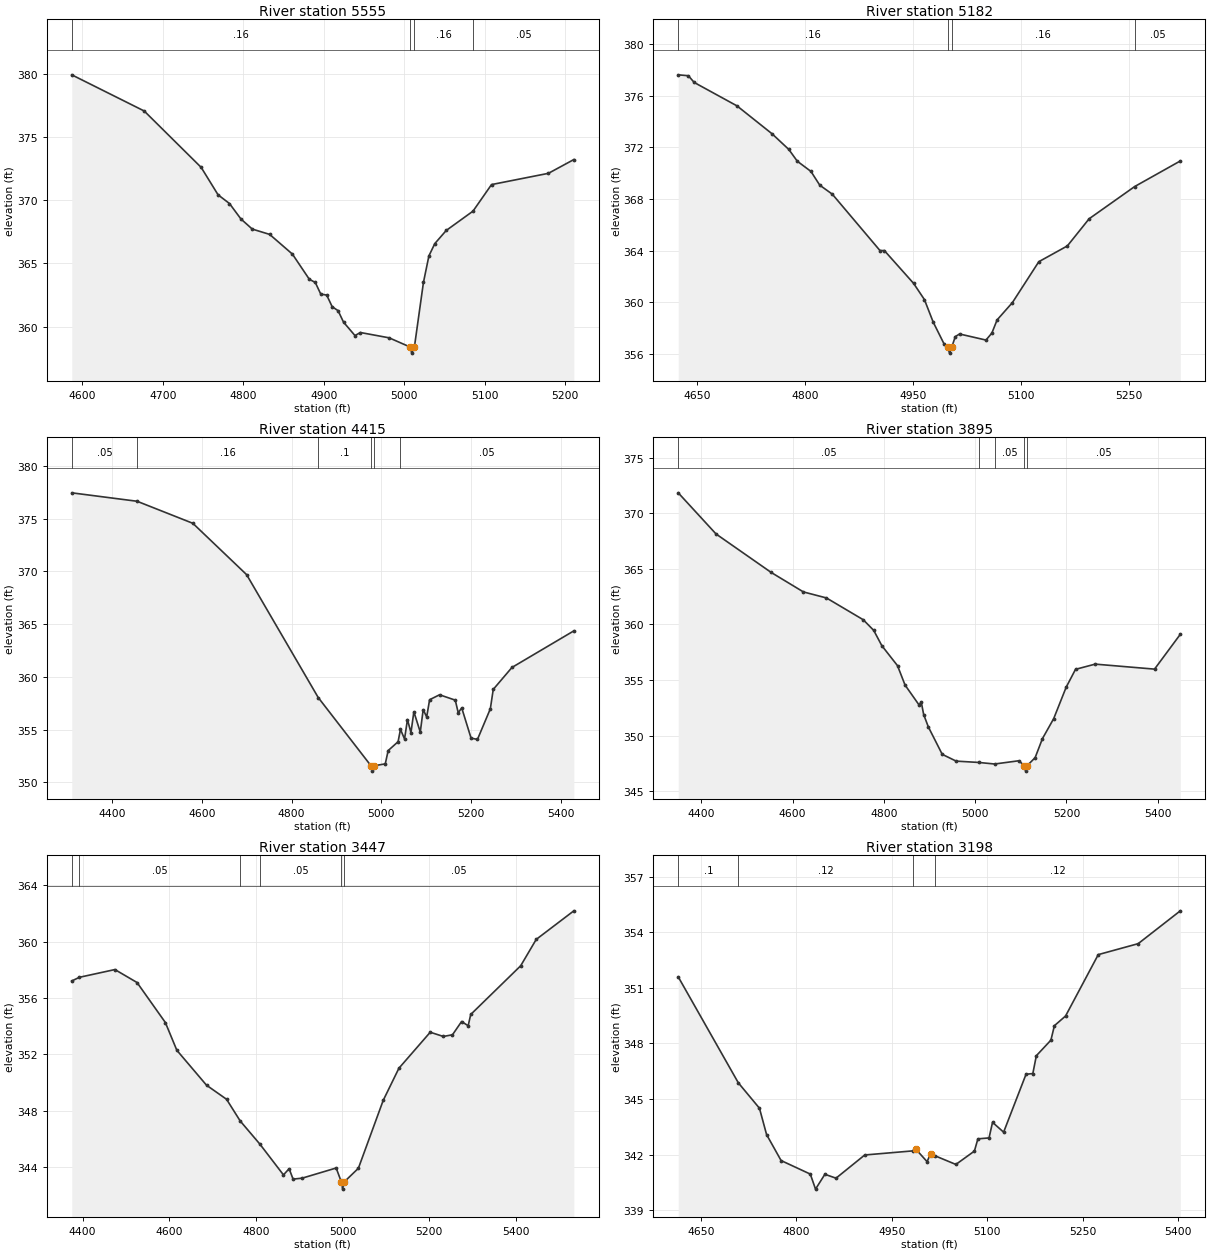
Type RM Length L Ch R = 1 ,5555    ,373,373,373
BEGIN DESCRIPTION:
STEELE CREEK TRIB 15 8.0
END DESCRIPTION:
XS GIS Cut Line= 2
       3532316.3     10452948.57      3531892.83     10453406.74
#Sta/Elev= 30
    4587  379.91    4677  377.05  4747.8  372.59  4768.8  370.42    4783  369.73
  4797.2  368.51  4811.3  367.71  4832.9  367.29  4861.2  365.73  4882.2  363.74
  4889.6  363.49  4896.4  362.57  4903.8  362.49  4910.6  361.57  4917.9  361.26
  4924.7  360.35  4938.9  359.29  4945.7  359.53  4981.4  359.11  5006.8   358.4
  5009.5   357.9  5012.8   358.4    5024  363.49  5030.8  365.59  5038.1  366.56
  5052.3   367.6  5085.6  369.13  5108.6  371.23  5179.3  372.12  5210.9  373.21
#Mann= 4 ,-1 , 0
    4587     .16       0  5006.8     .07       0  5012.8     .16       0
  5085.6     .05       0
Bank Sta=5006.8,5012.8
XS Rating Curve= 0 ,0
Exp/Cntr=0.3,0.1

Type RM Length L Ch R = 1 ,5182    ,767,767,767
BEGIN DESCRIPTION:
STEELE CREEK TRIB 15 7.0
END DESCRIPTION:
XS GIS Cut Line= 4
       3532205.2     10452837.45      3531941.29     10452941.62
      3531809.35      10453156.9      3531781.58     10453316.59
#Sta/Elev= 30
  4623.5   377.6  4637.6  377.53  4645.7  377.01  4705.2   375.2    4754  373.04
  4777.3  371.83  4789.1  370.92  4808.1  370.13  4820.3  369.07  4837.8  368.37
  4904.1  364.01  4910.2  364.01  4950.9  361.47  4965.9  360.22  4978.1  358.48
  4993.5  356.76  4998.1  356.58  5000.8  356.08  5004.1  356.58  5008.9  357.36
  5014.8  357.56  5051.5  357.09  5059.7  357.63    5067  358.65  5088.3  359.99
    5125  363.15  5164.7  364.37    5195  366.47  5258.3  368.96  5321.8  370.94
#Mann= 4 ,-1 , 0
  4623.5     .16       0  4998.1     .07       0  5004.1     .16       0
  5258.3     .05       0
Bank Sta=4998.1,5004.1
XS Rating Curve= 0 ,0
Exp/Cntr=0.3,0.1

Type RM Length L Ch R = 1 ,4415    ,520,520,520
BEGIN DESCRIPTION:
STEELE CREEK TRIB 15 6.0
END DESCRIPTION:
XS GIS Cut Line= 4
      3531962.14     10452448.57      3531524.63     10452455.51
      3531184.35     10452865.23      3531219.08     10453011.09
#Sta/Elev= 30
  4309.4  377.46  4455.1  376.66  4579.5  374.57  4699.5   369.7  4859.2  358.05
  4977.1  351.57  4979.9  351.07  4983.1  351.57  5008.8  351.76  5015.3  353.02
  5037.4  353.86  5042.7  355.03  5051.8  354.12  5058.3  355.96  5066.1  354.72
  5072.6   356.7  5086.9  354.77  5093.4   356.9  5101.2  356.21  5107.7  357.84
  5129.9  358.31    5165   357.8  5171.5  356.61  5179.4  357.06  5200.2   354.2
  5214.5  354.08  5243.2  356.98  5249.7  358.82  5291.4   360.9  5429.5  364.37
#Mann= 6 ,-1 , 0
  4309.4     .05       0  4455.1     .16       0  4859.2      .1       0
  4977.1     .07       0  4983.1      .1       0  5042.7     .05       0
Bank Sta=4977.1,4983.1
XS Rating Curve= 0 ,0
Exp/Cntr=0.3,0.1

Type RM Length L Ch R = 1 ,3895    ,448,448,448
BEGIN DESCRIPTION:
STEELE CREEK TRIB 15 5.0
END DESCRIPTION:
XS GIS Cut Line= 4
      3531684.35     10452288.85      3531295.46     10452240.23
      3530823.24     10452330.51      3530830.14     10452558.11
#Sta/Elev= 30
  4349.3  371.83  4432.2  368.13  4553.1  364.67  4623.7  362.92  4674.1  362.38
  4754.8  360.42  4777.8  359.46  4795.5  358.09  4829.9  356.29  4846.4  354.55
  4876.9  352.77    4882  353.01  4887.2   351.9  4897.4  350.79  4927.9  348.32
  4958.4  347.71  5007.9  347.59  5042.8  347.45  5095.4  347.74  5108.2  347.31
  5110.9  346.81  5114.2  347.31  5131.5  348.02  5147.5  349.73  5172.2  351.53
  5199.5  354.35    5220  355.96  5263.1  356.43  5393.2  355.98  5449.7  359.11
#Mann= 5 ,-1 , 0
  4349.3     .05       0  5007.9      .1       0  5042.8     .05       0
  5108.2     .03       0  5114.2     .05       0
Bank Sta=5108.2,5114.2
XS Rating Curve= 0 ,0
Exp/Cntr=0.3,0.1

Type RM Length L Ch R = 1 ,3447    ,249,249,249
BEGIN DESCRIPTION:
STEELE CREEK TRIB 15 4.0
END DESCRIPTION:
XS GIS Cut Line= 4
      3531399.62     10451830.51      3531066.29     10451761.07
      3530566.29     10452087.46       3530545.6      10452308.2
#Sta/Elev= 30
  4374.9  357.21  4392.5  357.47  4474.5  358.02  4525.6   357.1    4591  354.26
  4617.5  352.29    4686  349.81  4732.3  348.81  4763.8  347.27  4809.4  345.62
  4863.7  343.44  4876.8  343.88  4885.9  343.14    4907  343.21  4985.4  343.93
  4997.5  342.93  5000.3  342.43  5003.5  342.93  5036.7  343.91    5094  348.73
  5130.2  351.01  5202.6  353.57  5232.9  353.27    5254  353.39    5275  354.33
  5290.2  354.03  5296.1  354.83  5411.5  358.29  5447.3  360.16  5534.2  362.19
#Mann= 6 ,-1 , 0
  4374.9      .1       0  4392.5     .05       0  4763.8      .1       0
  4809.4     .05       0  4997.5     .03       0  5003.5     .05       0
Bank Sta=4997.5,5003.5
XS Rating Curve= 0 ,0
Exp/Cntr=0.3,0.1

Type RM Length L Ch R = 1 ,3198    ,260,260,260
BEGIN DESCRIPTION:
Mapping XS 110b1514
END DESCRIPTION:
XS GIS Cut Line= 2
      3530978.15     10451640.89      3530262.03     10451971.61
#Sta/Elev= 30
  4614.4  351.59  4708.8  345.88    4742  344.51  4753.2  343.09    4776  341.69
  4821.9  340.96  4830.1  340.15  4844.8  340.95  4862.3  340.74  4907.4  341.99
  4982.5  342.21    4988  342.29  5005.4  341.63  5010.9  342.07  5017.6  341.95
  5050.6  341.48  5079.7   342.2  5085.2  342.86  5102.7  342.91  5108.2  343.75
  5125.6  343.22  5160.8  346.34  5171.5  346.38    5177  347.34  5199.9  348.18
  5205.4  348.96  5222.9  349.48  5274.3  352.79    5337  353.38  5403.2  355.15
#Mann= 4 ,-1 , 0
  4614.4      .1       0  4708.8     .12       0  4982.5     .07       0
  5017.6     .12       0
Bank Sta=4988,5010.9
XS Rating Curve= 0 ,0
Exp/Cntr=0.3,0.1

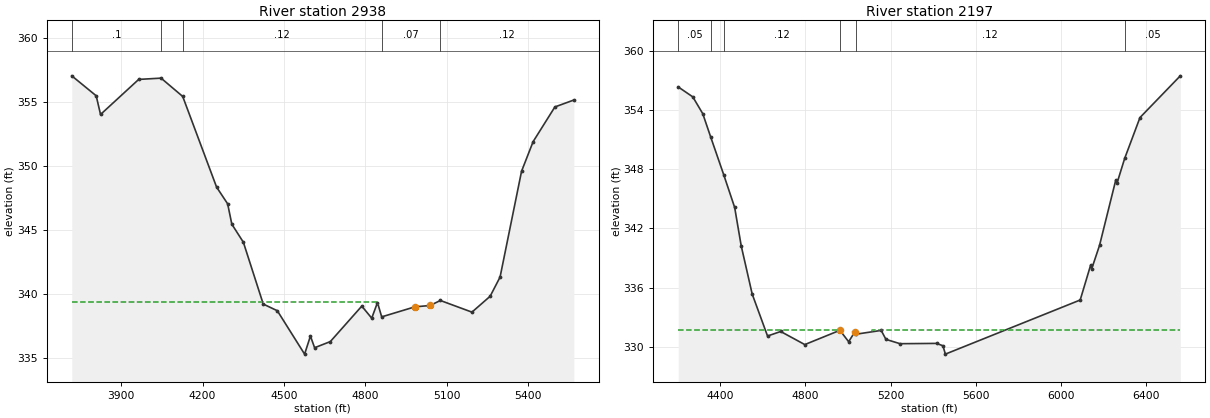
Type RM Length L Ch R = 1 ,2938    ,741,741,741
BEGIN DESCRIPTION:
STEELE CREEK TRIB 15 1.1
END DESCRIPTION:
XS GIS Cut Line= 3
      3531719.09     10451448.58      3531232.96     10451177.73
      3530132.71     10451857.51
#Sta/Elev= 30
  3718.3  357.01  3808.3  355.45  3824.3  353.99  3964.9  356.73  4047.3  356.83
    4127   355.4  4251.8  348.32  4292.6  347.01    4308  345.42  4350.5  344.01
  4423.8  339.18  4475.6  338.66  4576.1  335.27  4597.6  336.68    4613  335.77
  4670.9  336.25  4786.8  339.02  4823.4  338.08  4844.7   339.3  4860.1  338.18
  4981.8  338.96 5038.35  339.07  5076.4  339.46  5192.7  338.55  5259.7  339.79
  5296.3  341.29  5375.5  349.56  5418.1  351.87  5498.3  354.58  5568.1  355.12
#Mann= 5 ,-1 , 0
  3718.3      .1       0  4047.3     .05       0    4127     .12       0
  4860.1     .07       0  5076.4     .12       0
#XS Ineff= 2 , 0
       0 4847.77  339.32               0
Permanent Ineff=
       T       F
Bank Sta=4981.8,5038.35
XS Rating Curve= 0 ,0
Exp/Cntr=0.3,0.1

Type RM Length L Ch R = 1 ,2197    ,0,0,0
BEGIN DESCRIPTION:
STEELE CREEK TRIB 15 1.0
END DESCRIPTION:
XS GIS Cut Line= 3
      3531459.41     10451163.92      3530235.49     10450864.45
      3530044.52     10451945.17
#Sta/Elev= 30
  4202.7  356.38  4271.1  355.37  4317.9  353.66  4355.3  351.28  4416.1  347.47
  4467.6  344.14  4498.5  340.22    4550  335.33    4622  331.07  4683.8  331.53
    4797   330.2  4961.8  331.65  5002.9  330.49  5030.7  331.45  5035.9  331.25
  5155.6  331.64    5178  330.73    5244  330.29  5415.7  330.32  5445.6  330.08
    5457  329.23  6090.1  334.73  6139.1  338.27  6144.2   337.9  6180.9  340.28
  6257.5  346.95  6262.6  346.58    6299  349.12  6370.8  353.27  6560.2  357.51
#Mann= 6 ,-1 , 0
  4202.7     .05       0  4355.3      .1       0  4416.1     .12       0
  4961.8     .07       0  5035.9     .12       0    6299     .05       0
#XS Ineff= 2 , 0
       0  4946.6  331.73 5111.41       0  331.73
Permanent Ineff=
       T       T
Bank Sta=4961.8,5030.7
XS Rating Curve= 0 ,0
Exp/Cntr=0.3,0.1

Chan Stop Cuts=-1
Use User Specified Reach Order=0
Composite Channel Slope=5