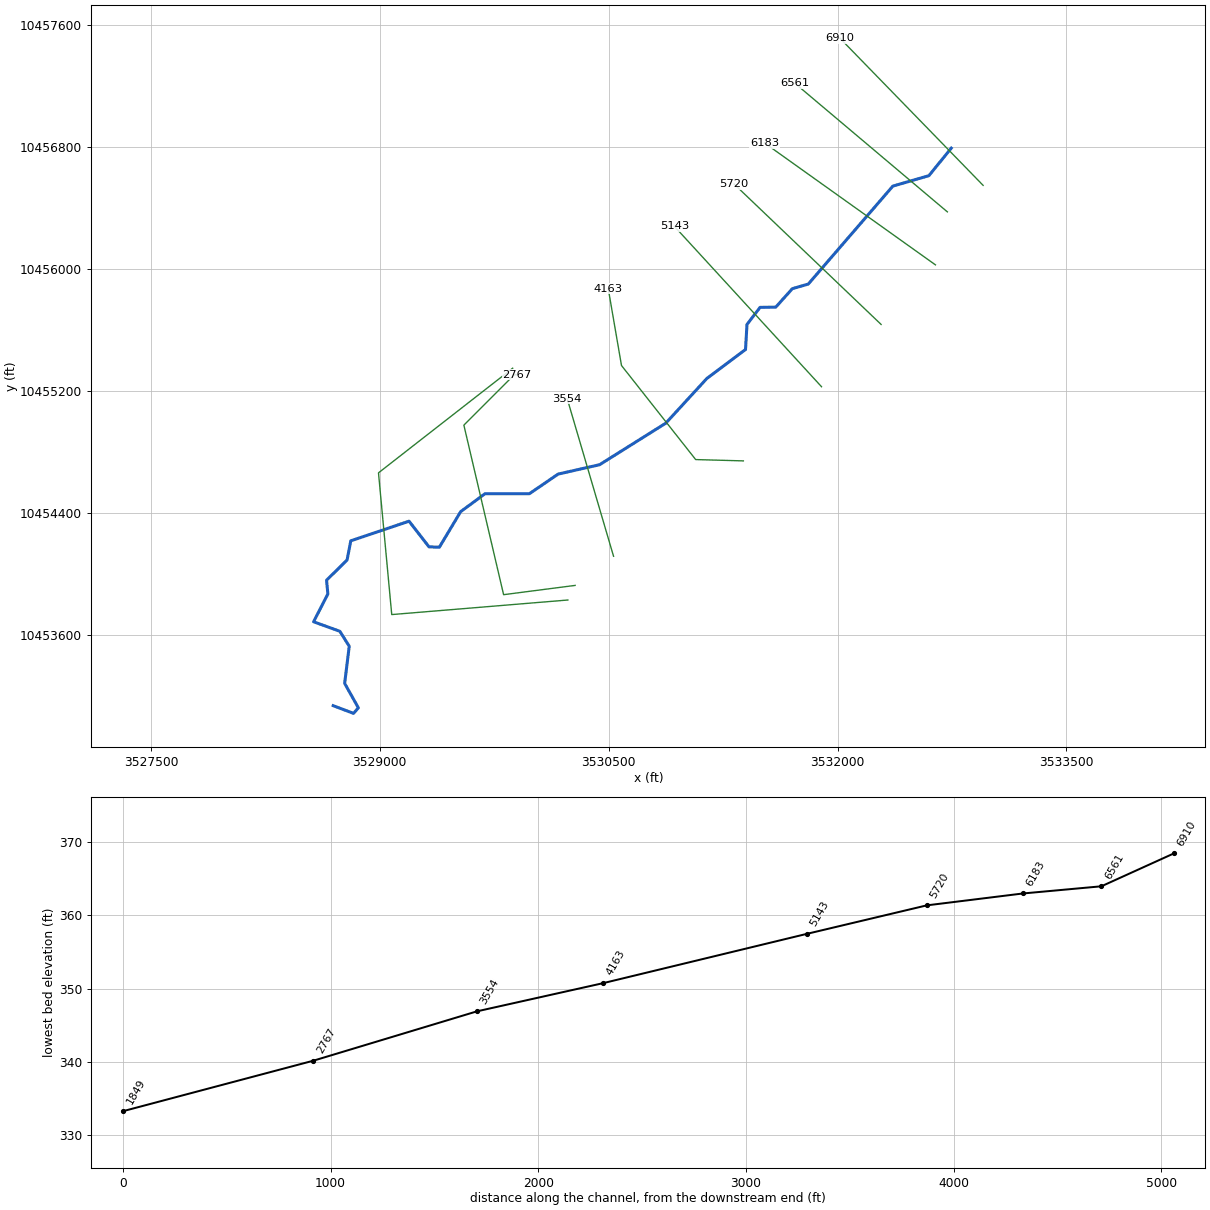
--- STEELE CREEK TRIB 17 1.prj (project) ---

Proj Title=STEELE CREEK TRIB 17 1 Base Level Engineering
Current Plan=p01
Default Exp/Contr=0.3,0.1
English Units
Geom File=g01
Flow File=f01
Plan File=p01
BEGIN DESCRIPTION:
STEELE CREEK TRIB 17 1
END DESCRIPTION:

--- STEELE CREEK TRIB 17 1.p01 (plan) ---

Plan Title=Multiple Run
Short Identifier=Multiple
Geom File=g01
Flow File=f01
Subcritical Flow
K Sum by GR= 0
Std Step Tol= 0.01
Critical Tol= 0.01
Num of Std Step Trials= 20
Max Error Tol= 0.3
Flow Tol Ratio= 0.001
Split Flow NTrial= 30
Split Flow Tol= 0.02
Split Flow Ratio= 0.02
Log Output Level= 0
Friction Slope Method= 1
Unsteady Friction Slope Method= 2
Unsteady Bridges Friction Slope Method= 1
Parabolic Critical Depth
Global Vel Dist=  1 , 1 , 1
Global Log Level= 0
CheckData=True
Encroach Param= -1, 0, 0, 0
BEGIN DESCRIPTION:
Multiple Run
END DESCRIPTION:

--- STEELE CREEK TRIB 17 1.f01 (steady flow) ---

Flow Title=Multiple
Number of Profiles=7
Profile Names=10-year,25-year,50-year,1pct_min,100-year,1pct_plu,500-year
River Rch & RM= STEELE CREEK TRI,Reach-1,6910
     790    1072    1301    1154    1560    2110    2235
Boundary for River Rch & Prof#=STEELE CREEK TRI,Reach-1,1
Up Type=0
Dn Type=3
Dn Slope=0.005
Boundary for River Rch & Prof#=STEELE CREEK TRI,Reach-1,2
Up Type=0
Dn Type=3
Dn Slope=0.005
Boundary for River Rch & Prof#=STEELE CREEK TRI,Reach-1,3
Up Type=0
Dn Type=3
Dn Slope=0.005
Boundary for River Rch & Prof#=STEELE CREEK TRI,Reach-1,4
Up Type=0
Dn Type=3
Dn Slope=0.005
Boundary for River Rch & Prof#=STEELE CREEK TRI,Reach-1,5
Up Type=0
Dn Type=3
Dn Slope=0.005
Boundary for River Rch & Prof#=STEELE CREEK TRI,Reach-1,6
Up Type=0
Dn Type=3
Dn Slope=0.005
Boundary for River Rch & Prof#=STEELE CREEK TRI,Reach-1,7
Up Type=0
Dn Type=3
Dn Slope=0.005

--- STEELE CREEK TRIB 17 1.g01 (geometry) ---

Geom Title=Existing Conditions

River Reach=STEELE CREEK TRI,Reach-1
Reach XY= 30
      3532745.04     10456789.72      3532598.42     10456609.44
      3532362.35     10456541.18      3531808.15     10455899.19
      3531703.72     10455869.00      3531594.93     10455747.99
      3531492.11     10455746.39      3531406.44     10455634.67
      3531396.81     10455470.41      3531143.34     10455280.41
      3530874.31     10454987.49      3530440.52     10454715.33
      3530168.84     10454653.91      3529980.59     10454525.31
      3529689.56     10454525.11      3529529.85     10454407.53
      3529390.59     10454174.82      3529322.60     10454176.97
      3529191.83     10454345.19      3528809.98     10454216.52
      3528785.73     10454090.63      3528651.29     10453958.59
      3528659.73     10453868.17      3528566.25     10453686.14
      3528738.43     10453623.66      3528799.89     10453525.74
      3528769.83     10453282.35      3528859.58     10453122.26
      3528827.98     10453085.78      3528694.57     10453136.29

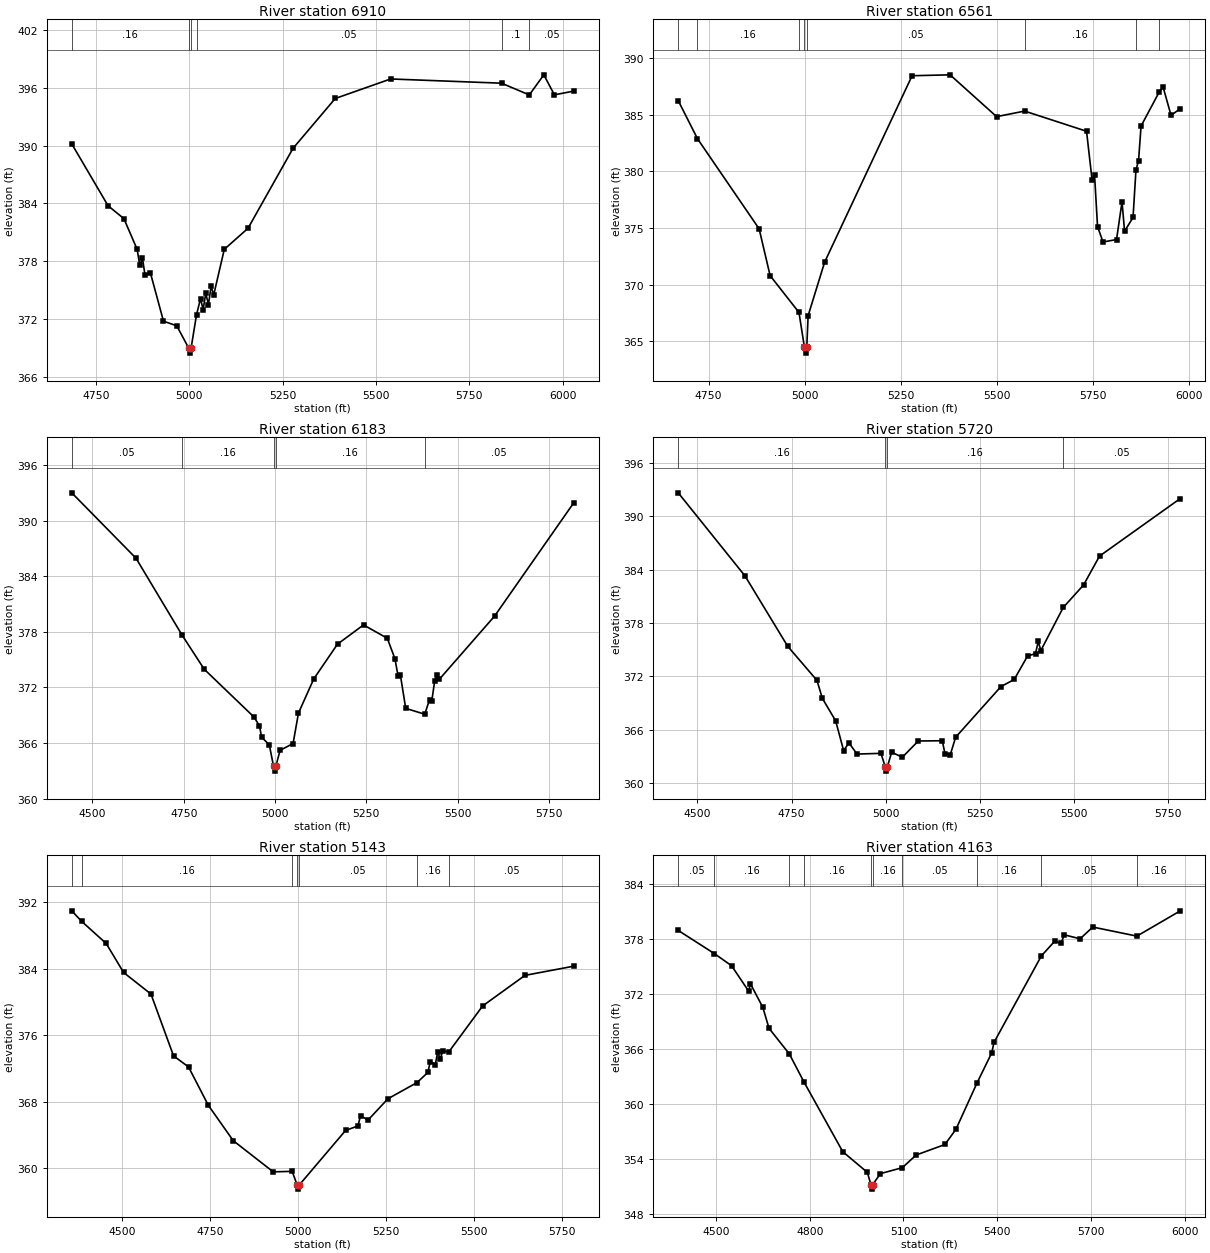
Type RM Length L Ch R = 1,6910,349,349,349
BEGIN DESCRIPTION:
STEELE CREEK TRIB 17.1 13.0
END DESCRIPTION:
XS GIS Cut Line= 2
      3532953.89     10456545.93      3532016.36     10457509.50
#Sta/Elev= 30
  4685.3  390.18  4782.5  383.75  4824.9  382.41  4860.4  379.21  4867.4  377.55
  4874.6  378.30  4881.5  376.51  4895.7  376.80  4930.9  371.75  4966.4  371.27
  4998.7  368.93  5001.4  368.43  5004.7  368.93  5019.3  372.41  5030.0  374.09
  5037.1  372.96  5044.1  374.65  5051.3  373.48  5058.3  375.37  5065.4  374.49
  5093.7  379.22  5157.3  381.41  5277.6  389.71  5390.8  394.90  5539.2  396.93
  5836.1  396.49  5910.4  395.27  5949.3  397.36  5977.6  395.28  6029.7  395.67
#Mann=6,-1,0
  4685.3    0.16       0  4998.7    0.07       0  5004.7    0.16       0
  5019.3    0.05       0  5836.1     0.1       0  5910.4    0.05       0
Bank Sta=4998.7,5004.7
Exp/Cntr=0.3,0.1

Type RM Length L Ch R = 1,6561,378,378,378
BEGIN DESCRIPTION:
STEELE CREEK TRIB 17.1 12.0
END DESCRIPTION:
XS GIS Cut Line= 2
      3532719.53     10456372.31      3531721.23     10457214.35
#Sta/Elev= 30
  4671.1  386.23  4721.2  382.87  4881.5  374.92  4910.1  370.79  4985.2  367.54
  4999.4  364.45  5002.2  363.95  5005.4  364.45  5009.0  367.26  5051.9  371.98
  5279.4  388.43  5378.2  388.51  5499.2  384.82  5572.1  385.31  5733.2  383.53
  5747.5  379.26  5754.1  379.64  5761.8  375.11  5776.1  373.76  5811.2  373.97
  5825.5  377.31  5832.1  374.71  5854.1  375.92  5861.8  380.14  5868.4  380.91
  5875.0  383.99  5921.7  386.96  5932.1  387.46  5953.0  384.93  5977.1  385.53
#Mann=8,-1,0
  4671.1    0.05       0  4721.2    0.16       0  4985.2    0.05       0
  4999.4    0.03       0  5005.4    0.05       0  5572.1    0.16       0
  5861.8     0.1       0  5921.7    0.05       0
Bank Sta=4999.4,5005.4
Exp/Cntr=0.3,0.1

Type RM Length L Ch R = 1,6183,463,463,463
BEGIN DESCRIPTION:
STEELE CREEK TRIB 17.1 11.0
END DESCRIPTION:
XS GIS Cut Line= 2
      3532641.39     10456025.09      3531521.60     10456823.71
#Sta/Elev= 30
  4443.3  392.99  4619.4  385.93  4745.5  377.64  4806.2  373.96  4942.6  368.80
  4957.4  367.86  4963.5  366.62  4984.4  365.81  4996.2  363.47  4998.9  362.97
  5002.2  363.47  5013.9  365.21  5049.6  365.95  5064.3  369.23  5106.1  372.91
  5171.3  376.67  5242.6  378.74  5307.7  377.30  5328.6  375.09  5337.2  373.22
  5343.4  373.37  5358.1  369.74  5410.3  369.11  5423.3  370.68  5429.4  370.49
  5437.3  372.65  5444.2  373.39  5450.3  372.88  5601.5  379.69  5818.7  391.93
#Mann=5,-1,0
  4443.3    0.05       0  4745.5    0.16       0  4996.2    0.07       0
  5002.2    0.16       0  5410.3    0.05       0
Bank Sta=4996.2,5002.2
Exp/Cntr=0.3,0.1

Type RM Length L Ch R = 1,5720,577,577,577
BEGIN DESCRIPTION:
STEELE CREEK TRIB 17.1 10.0
END DESCRIPTION:
XS GIS Cut Line= 2
      3532285.50     10455634.46      3531321.97     10456554.59
#Sta/Elev= 30
  4449.3  392.66  4626.5  383.31  4739.7  375.40  4817.4  371.56  4831.6  369.55
  4867.1  367.00  4888.2  363.66  4902.3  364.53  4923.7  363.27  4987.3  363.35
  4998.4  361.85  5001.2  361.35  5004.4  361.85  5015.6  363.48  5043.9  362.91
  5086.3  364.74  5149.9  364.77  5157.1  363.33  5171.3  363.21  5185.4  365.16
  5305.6  370.86  5340.8  371.66  5376.3  374.30  5397.4  374.57  5404.6  375.94
  5411.5  374.92  5470.9  379.76  5524.8  382.29  5567.2  385.54  5781.6  392.02
#Mann=4,-1,0
  4449.3    0.16       0  4998.4    0.07       0  5004.4    0.16       0
  5470.9    0.05       0
Bank Sta=4998.4,5004.4
Exp/Cntr=0.3,0.1

Type RM Length L Ch R = 1,5143,980,980,980
BEGIN DESCRIPTION:
STEELE CREEK TRIB 17.1 9.0
END DESCRIPTION:
XS GIS Cut Line= 2
      3531894.87     10455226.47      3530931.44     10456276.71
#Sta/Elev= 30
  4357.3  390.97  4385.4  389.70  4455.0  387.04  4504.4  383.55  4582.1  380.95
  4646.2  373.51  4688.7  372.18  4744.8  367.57  4815.7  363.30  4929.2  359.55
  4982.9  359.61  4997.1  357.97  4999.9  357.47  5003.1  357.97  5134.5  364.53
  5169.7  365.08  5177.1  366.33  5198.0  365.77  5254.8  368.35  5337.5  370.30
  5368.2  371.52  5375.0  372.83  5389.2  372.47  5396.0  373.97  5403.4  373.11
  5410.2  374.09  5427.8  374.00  5523.6  379.52  5643.8  383.20  5782.5  384.31
#Mann=7,-1,0
  4357.3    0.05       0  4385.4    0.16       0  4982.9    0.05       0
  4997.1    0.03       0  5003.1    0.05       0  5337.5    0.16       0
  5427.8    0.05       0
Bank Sta=4997.1,5003.1
Exp/Cntr=0.3,0.1

Type RM Length L Ch R = 1,4163,609,609,609
BEGIN DESCRIPTION:
STEELE CREEK TRIB 17.1 7.0
END DESCRIPTION:
XS GIS Cut Line= 4
      3531382.73     10454740.37      3531070.21     10454749.05
      3530584.10     10455365.37      3530497.48     10455867.76
#Sta/Elev= 30
  4379.0  378.98  4494.9  376.45  4549.7  375.13  4604.8  372.34  4609.8  373.18
  4649.7  370.60  4669.7  368.30  4734.6  365.51  4780.9  362.49  4905.8  354.84
  4984.4  352.59  4995.8  351.26  4998.6  350.76  5001.8  351.26  5026.1  352.45
  5096.4  353.10  5140.7  354.48  5232.9  355.63  5268.1  357.29  5335.4  362.33
  5382.7  365.63  5390.0  366.77  5541.5  376.20  5584.4  377.81  5604.7  377.58
  5614.9  378.50  5665.6  378.07  5706.2  379.35  5847.4  378.36  5986.4  381.12
#Mann=10,-1,0
  4379.0    0.05       0  4494.9    0.16       0  4734.6    0.05       0
  4780.9    0.16       0  4995.8    0.07       0  5001.8    0.16       0
  5096.4    0.05       0  5335.4    0.16       0  5541.5    0.05       0
  5847.4    0.16       0
Bank Sta=4995.8,5001.8
Exp/Cntr=0.3,0.1

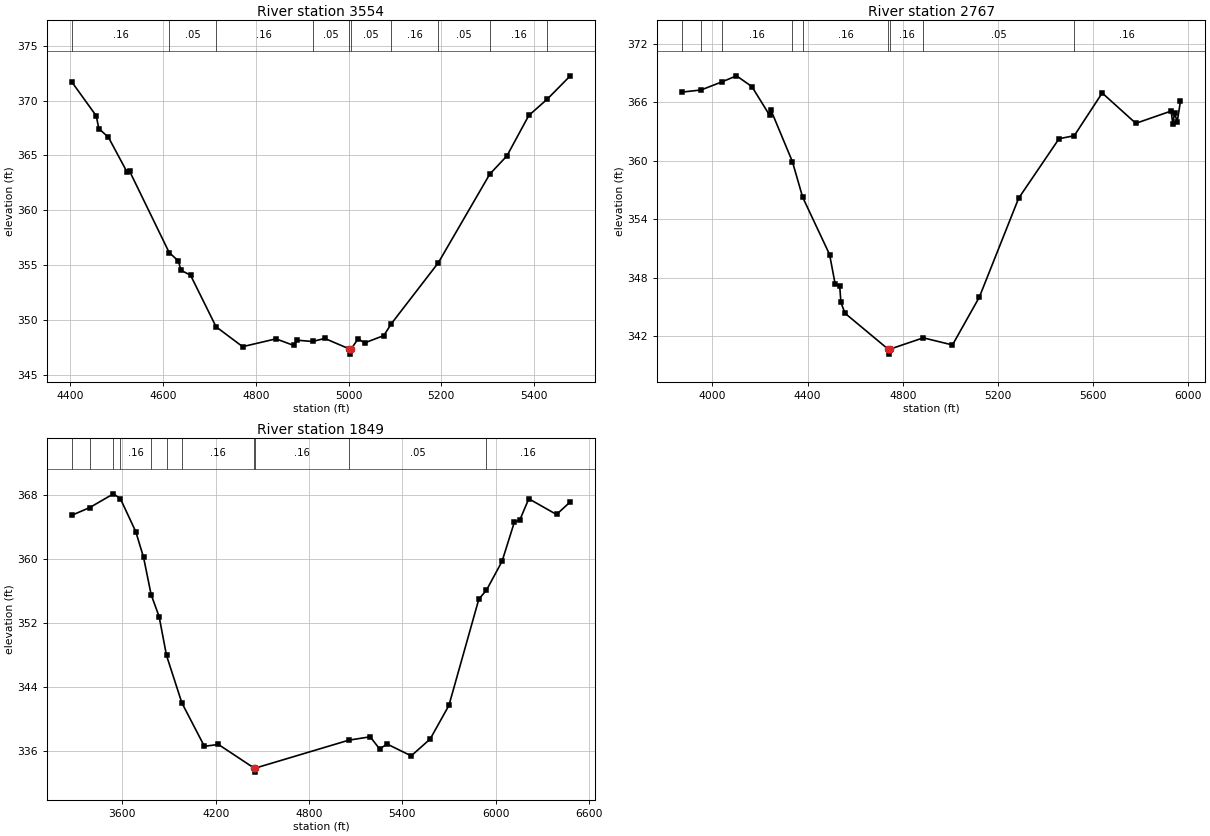
Type RM Length L Ch R = 1,3554,787,787,787
BEGIN DESCRIPTION:
STEELE CREEK TRIB 17.1 5.0
END DESCRIPTION:
XS GIS Cut Line= 2
      3530532.02     10454115.35      3530228.44     10455147.53
#Sta/Elev= 30
  4402.4  371.72  4455.6  368.60  4461.1  367.45  4481.9  366.65  4522.3  363.47
  4527.5  363.57  4612.9  356.16  4632.8  355.39  4638.3  354.55  4659.1  354.09
  4714.1  349.40  4771.4  347.59  4843.3  348.30  4881.9  347.70  4888.4  348.18
  4922.2  348.06  4948.6  348.34  5000.1  347.41  5002.9  346.91  5006.1  347.41
  5020.5  348.31  5034.4  347.93  5076.1  348.60  5091.7  349.65  5193.6  355.23
  5304.6  363.30  5341.6  364.96  5388.8  368.64  5428.7  370.13  5478.3  372.25
#Mann=10,-1,0
  4402.4    0.16       0  4612.9    0.05       0  4714.1    0.16       0
  4922.2    0.05       0  5000.1    0.03       0  5006.1    0.05       0
  5091.7    0.16       0  5193.6    0.05       0  5304.6    0.16       0
  5428.7    0.05       0
Bank Sta=5000.1,5006.1
Exp/Cntr=0.3,0.1

Type RM Length L Ch R = 1,2767,918,918,918
BEGIN DESCRIPTION:
STEELE CREEK TRIB 17.1 1.2
END DESCRIPTION:
XS GIS Cut Line= 5
      3530280.24     10453924.39      3529811.53     10453863.64
      3529551.11     10454974.75      3529880.97     10455304.61
      3529897.73     10455304.61
#Sta/Elev= 30
  3871.1  367.05  3952.1  367.27  4038.7  368.09  4101.1  368.72  4165.7  367.62
  4239.9  364.70  4245.0  365.26  4336.1  359.93  4379.3  356.28  4492.6  350.40
  4516.3  347.34  4535.1  347.19  4540.2  345.50  4557.4  344.38  4739.2  340.69
  4742.0  340.19  4745.2  340.69  4886.5  341.86  5009.3  341.13  5122.3  346.03
  5287.6  356.17  5457.4  362.27  5521.4  362.58  5639.0  366.96  5780.4  363.85
  5928.9  365.11  5936.0  363.77  5943.1  364.91  5954.5  364.02  5968.2  366.13
#Mann=9,-1,0
  3871.1    0.16       0  3952.1    0.05       0  4038.7    0.16       0
  4336.1     0.1       0  4379.3    0.16       0  4739.2    0.03       0
  4745.2    0.16       0  4886.5    0.05       0  5521.4    0.16       0
Bank Sta=4739.2,4745.2
Exp/Cntr=0.3,0.1

Type RM Length L Ch R = 1,1849,0,0,0
BEGIN DESCRIPTION:
STEELE CREEK TRIB 17.1 1.0
END DESCRIPTION:
XS GIS Cut Line= 4
      3530232.95     10453828.72      3529078.41     10453733.23
      3528991.60     10454662.05      3529871.08     10455347.83
#Sta/Elev= 30
  3273.5  365.50  3389.5  366.47  3542.5  368.20  3587.2  367.59  3685.8  363.47
  3735.9  360.26  3784.9  355.56  3836.3  352.80  3883.8  347.93  3982.6  341.98
  4127.3  336.54  4217.6  336.77  4447.7  333.80  4450.5  333.30  4453.7  333.80
  5056.7  337.31  5193.5  337.73  5254.0  336.21  5302.4  336.82  5457.1  335.34
  5579.2  337.45  5699.6  341.66  5892.2  355.00  5940.9  356.11  6041.5  359.74
  6120.2  364.63  6155.5  364.92  6213.4  367.58  6391.6  365.61  6480.1  367.19
#Mann=11,-1,0
  3273.5    0.05       0  3389.5    0.16       0  3542.5    0.05       0
  3587.2    0.16       0  3784.9     0.1       0  3883.8    0.05       0
  3982.6    0.16       0  4447.7    0.07       0  4453.7    0.16       0
  5056.7    0.05       0  5940.9    0.16       0
Bank Sta=4447.7,4453.7
Exp/Cntr=0.3,0.1

Chan Stop Cuts=-1