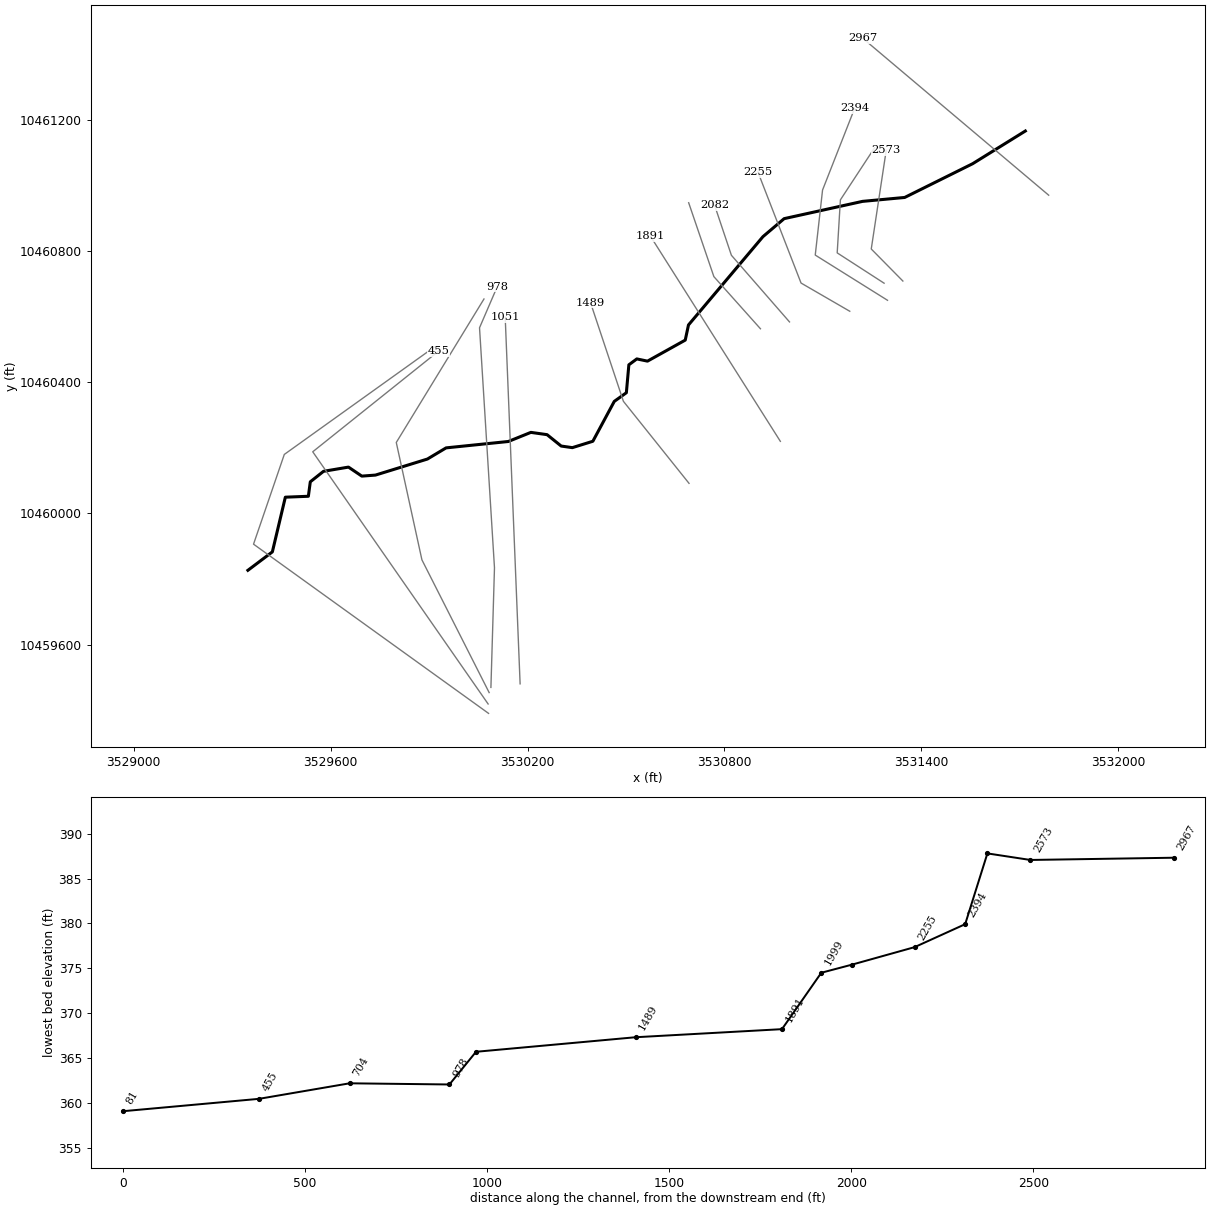
--- STEELE CREEK TRIB 17 2.prj (project) ---

Proj Title=STEELE CREEK TRIB 17 2 Base Level Engineering
Current Plan=p01
Default Exp/Contr=0.3,0.1
English Units
Geom File=g01
Flow File=f01
Plan File=p01
Y Axis Title=Elevation
X Axis Title(PF)=Main Channel Distance
X Axis Title(XS)=Station
BEGIN DESCRIPTION:
STEELE CREEK TRIB 17 2
END DESCRIPTION:
DSS Export Rating Curves= 0
DSS Export Rating Curve Sorted= 0
DSS Export Volume Flow Curves= 0
DXF OffsetX= 0
DXF OffsetY= 0
DXF ScaleX= 1
DXF ScaleY= 10

--- STEELE CREEK TRIB 17 2.p01 (plan) ---

Plan Title=Multiple Run
Short Identifier=Multiple
Geom File=g01
Flow File=f01
Subcritical Flow
K Sum by GR= 0
Std Step Tol= 0.01
Critical Tol= 0.01
Num of Std Step Trials= 20
Max Error Tol= 0.3
Flow Tol Ratio= 0.001
Split Flow NTrial= 30
Split Flow Tol= 0.02
Split Flow Ratio= 0.02
Log Output Level= 0
Friction Slope Method= 1
Unsteady Friction Slope Method= 2
Unsteady Bridges Friction Slope Method= 1
Parabolic Critical Depth
Global Vel Dist=  1 , 1 , 1
Global Log Level= 0
CheckData=True
Encroach Param= -1, 0, 0, 0
BEGIN DESCRIPTION:
Multiple Run
END DESCRIPTION:

--- STEELE CREEK TRIB 17 2.f01 (steady flow) ---

Flow Title=Multiple
Program Version=4.10
Number of Profiles= 7
Profile Names=10-year,25-year,50-year,1pct_min,100-year,1pct_plu,500-year
River Rch & RM=STEELE CREEK TRI,Reach-1         ,2967
     387     502     593     512     693     937     942
Boundary for River Rch & Prof#=STEELE CREEK TRI,Reach-1         , 1
Up Type= 0
Dn Type= 3
Dn Slope=0.007
Boundary for River Rch & Prof#=STEELE CREEK TRI,Reach-1         , 2
Up Type= 0
Dn Type= 3
Dn Slope=0.007
Boundary for River Rch & Prof#=STEELE CREEK TRI,Reach-1         , 3
Up Type= 0
Dn Type= 3
Dn Slope=0.007
Boundary for River Rch & Prof#=STEELE CREEK TRI,Reach-1         , 4
Up Type= 0
Dn Type= 3
Dn Slope=0.007
Boundary for River Rch & Prof#=STEELE CREEK TRI,Reach-1         , 5
Up Type= 0
Dn Type= 3
Dn Slope=0.007
Boundary for River Rch & Prof#=STEELE CREEK TRI,Reach-1         , 6
Up Type= 0
Dn Type= 3
Dn Slope=0.007
Boundary for River Rch & Prof#=STEELE CREEK TRI,Reach-1         , 7
Up Type= 0
Dn Type= 3
Dn Slope=0.007
DSS Import GetInterval= 0
DSS Import GetPeak= 0
DSS Import FillOption= 0

--- STEELE CREEK TRIB 17 2.g01 (geometry) ---

Geom Title=Existing Conditions
Program Version=4.10

River Reach=STEELE CREEK TRI,Reach-1
Reach XY= 30
      3531716.96     10461165.33      3531556.25     10461065.63
       3531349.3     10460962.85      3531220.84     10460950.92
      3530981.94     10460898.27      3530917.36     10460843.41
      3530690.45     10460574.34      3530680.55     10460528.13
      3530565.52     10460464.07      3530532.97     10460470.84
      3530508.75     10460452.87      3530501.13     10460367.81
      3530464.32     10460341.42      3530399.04      10460219.9
      3530336.54     10460200.45      3530302.52     10460205.31
      3530259.46     10460240.04      3530210.15     10460246.98
       3530141.4      10460219.2      3529951.82     10460199.76
      3529894.88     10460165.73      3529736.54     10460116.83
      3529694.95     10460113.72      3529654.33     10460141.15
      3529578.28     10460128.31      3529538.01     10460096.36
       3529532.1     10460052.27      3529461.97     10460049.49
      3529422.38     10459882.82      3529347.85     10459826.67

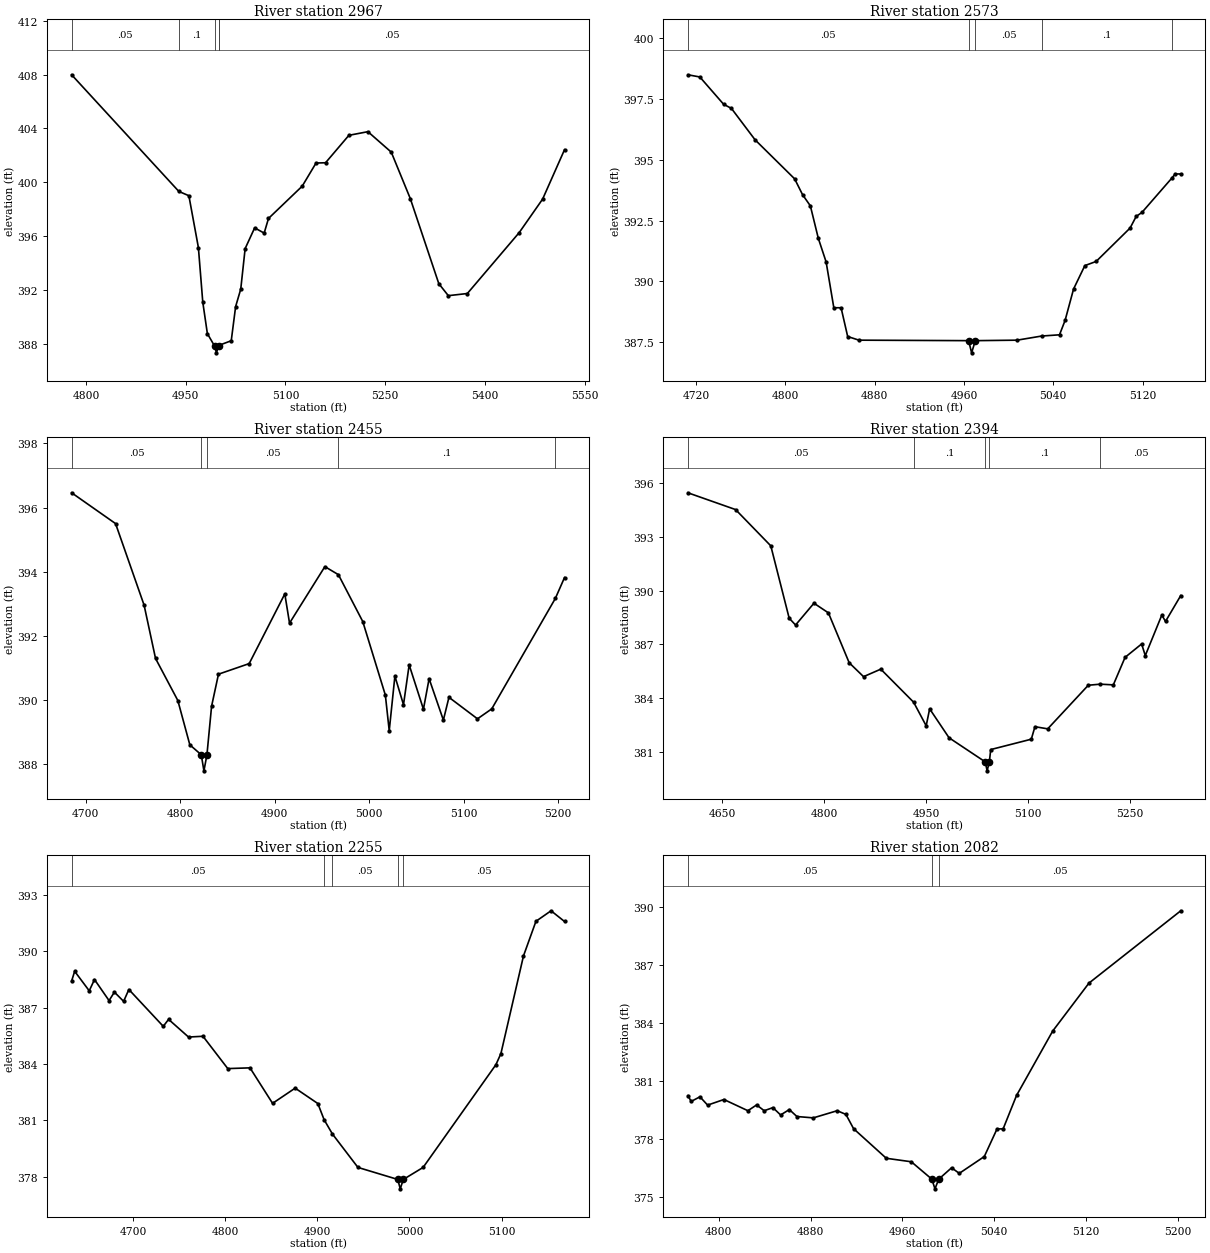
Type RM Length L Ch R = 1 ,2967    ,394,394,394
BEGIN DESCRIPTION:
STEELE CREEK TRIB 17.2 5.0
END DESCRIPTION:
XS GIS Cut Line= 2
      3531788.07     10460969.73      3531221.74     10461447.74
#Sta/Elev= 30
  4778.5  407.99  4939.7  399.32  4954.8     399  4969.1  395.15  4975.7  391.09
  4982.6  388.75  4993.5  387.82  4996.2  387.32  4999.5  387.82  5000.2  387.88
  5018.5  388.22  5025.1  390.76  5032.8  392.06  5039.4  395.07  5053.7  396.61
    5068  396.22  5074.5  397.31  5125.2  399.71    5146  401.43  5160.3  401.45
  5195.4  403.49    5224  403.76  5259.1  402.24  5287.7  398.79  5330.6  392.46
  5344.9  391.57  5373.5  391.73  5451.5  396.26  5486.7  398.75  5519.6  402.42
#Mann= 5 ,-1 , 0
  4778.5     .05       0  4939.7      .1       0  4993.5     .07       0
  4999.5      .1       0  5000.2     .05       0
Bank Sta=4993.5,4999.5
XS Rating Curve= 0 ,0
Exp/Cntr=0.3,0.1

Type RM Length L Ch R = 1 ,2573    ,118,118,118
BEGIN DESCRIPTION:
Mapping XS 48e66a41
END DESCRIPTION:
XS GIS Cut Line= 3
      3531343.75     10460708.15       3531247.4     10460805.78
      3531293.01     10461106.57
#Sta/Elev= 30
  4712.8  398.48  4723.5  398.39  4744.8  397.27  4751.8   397.1    4773  395.81
  4808.4  394.21  4815.5  393.56  4822.5   393.1  4829.6  391.77  4836.6   390.8
  4843.5  388.92    4850  388.92  4855.9  387.74    4866  387.59  4964.2  387.57
  4966.9  387.07  4970.2  387.57  5007.6  387.59  5029.7  387.76  5045.6  387.81
  5050.6   388.4  5058.2  389.69  5068.3  390.65  5078.4  390.82  5108.8  392.19
  5114.3  392.67  5119.4  392.83  5146.2  394.24  5149.2  394.41  5154.2  394.41
#Mann= 5 ,-1 , 0
  4712.8     .05       0  4964.2     .03       0  4970.2     .05       0
  5029.7      .1       0  5146.2     .05       0
Bank Sta=4964.2,4970.2
XS Rating Curve= 0 ,0
Exp/Cntr=0.3,0.1

Type RM Length L Ch R = 1 ,2455    ,61,61,61
BEGIN DESCRIPTION:
STEELE CREEK TRIB 17.2 4.0
END DESCRIPTION:
XS GIS Cut Line= 4
      3531286.51      10460701.6       3531143.6     10460793.96
      3531153.36     10460955.52      3531257.32     10461114.06
#Sta/Elev= 30
  4685.1  396.46  4731.6   395.5  4761.8  392.96  4773.9   391.3  4797.5  389.99
  4810.2  388.61  4822.3   388.3  4825.1   387.8  4828.3   388.3  4833.2  389.81
  4840.5  390.81    4873  391.14  4910.7  393.31  4915.7   392.4  4953.1  394.16
  4967.4  393.91  4993.2  392.45  5017.1  390.16  5021.2  389.05  5027.2  390.75
  5036.3  389.86  5042.3   391.1  5057.4  389.72  5063.4  390.67  5078.5  389.38
  5084.4  390.09  5114.6  389.42  5129.7  389.73    5197  393.17  5206.7  393.82
#Mann= 5 ,-1 , 0
  4685.1     .05       0  4822.3     .07       0  4828.3     .05       0
  4967.4      .1       0    5197     .05       0
Bank Sta=4822.3,4828.3
XS Rating Curve= 0 ,0
Exp/Cntr=0.3,0.1

Type RM Length L Ch R = 1 ,2394    ,139,139,139
BEGIN DESCRIPTION:
Mapping XS 46f0cb79
END DESCRIPTION:
XS GIS Cut Line= 4
      3531296.93     10460649.51      3531076.71     10460787.27
        3531099.     10460985.46      3531196.66     10461234.18
#Sta/Elev= 30
  4599.1  395.48  4669.4  394.54  4721.3  392.51  4748.4  388.46  4757.8  388.08
  4784.9   389.3  4806.2  388.76  4836.8  385.97    4858  385.19  4883.4  385.61
  4931.8  383.76  4950.3  382.44  4955.4  383.39    4984  381.77  5037.4  380.42
  5040.1  379.92  5043.4  380.42  5045.4  381.11  5105.2  381.69  5110.6  382.39
  5129.4  382.27  5189.2  384.71  5206.9  384.77  5226.1  384.73  5243.4  386.27
  5267.8  387.02  5273.2  386.37  5297.6  388.64    5303  388.28  5325.5  389.73
#Mann= 5 ,-1 , 0
  4599.1     .05       0  4931.8      .1       0  5037.4     .07       0
  5043.4      .1       0  5206.9     .05       0
Bank Sta=5037.4,5043.4
XS Rating Curve= 0 ,0
Exp/Cntr=0.3,0.1

Type RM Length L Ch R = 1 ,2255    ,173,173,173
BEGIN DESCRIPTION:
Mapping XS 5b0b0210
END DESCRIPTION:
XS GIS Cut Line= 3
      3531181.88     10460616.09      3531033.45     10460702.03
      3530901.94     10461040.57
#Sta/Elev= 30
  4633.5  388.42  4636.8  388.94  4652.6   387.9  4658.3   388.5  4674.1  387.38
  4679.9  387.83  4689.9  387.34  4695.6  387.97  4732.9  386.01  4738.7  386.38
  4760.3  385.44    4776  385.48  4802.9  383.76    4827   383.8  4851.5  381.91
    4876  382.72  4900.6   381.9  4907.4  381.04  4916.4  380.28  4944.1   378.5
  4987.3  377.86    4990  377.36  4993.3  377.86  5014.8   378.5  5093.8  383.97
  5099.2  384.56  5123.7  389.76  5137.2   391.6  5153.6  392.16  5168.2  391.59
#Mann= 5 ,-1 , 0
  4633.5     .05       0  4907.4      .1       0  4916.4     .05       0
  4987.3     .03       0  4993.3     .05       0
Bank Sta=4987.3,4993.3
XS Rating Curve= 0 ,0
Exp/Cntr=0.3,0.1

Type RM Length L Ch R = 1 ,2082    ,83,83,83
BEGIN DESCRIPTION:
Mapping XS a789c3b8
END DESCRIPTION:
XS GIS Cut Line= 3
      3530998.27     10460583.57      3530821.21     10460786.67
      3530770.25      10460938.4
#Sta/Elev= 30
    4773  380.22  4775.9  379.92  4783.5  380.16  4790.2  379.73  4804.4  380.02
  4825.3  379.44  4832.9  379.74  4839.5  379.44  4847.1   379.6  4853.8  379.22
  4861.4   379.5    4868  379.14  4882.3  379.07  4903.1  379.44  4910.7  379.25
  4917.4  378.51  4945.9  376.98  4967.7   376.8  4985.6   375.9  4988.3   375.4
  4991.6   375.9  5002.8  376.49  5009.5   376.2  5031.3  377.07  5042.4   378.5
  5047.7   378.5  5059.4  380.23  5090.9  383.56  5122.5  386.04  5202.5  389.78
#Mann= 3 ,-1 , 0
    4773     .05       0  4985.6     .03       0  4991.6     .05       0
Bank Sta=4985.6,4991.6
XS Rating Curve= 0 ,0
Exp/Cntr=0.3,0.1

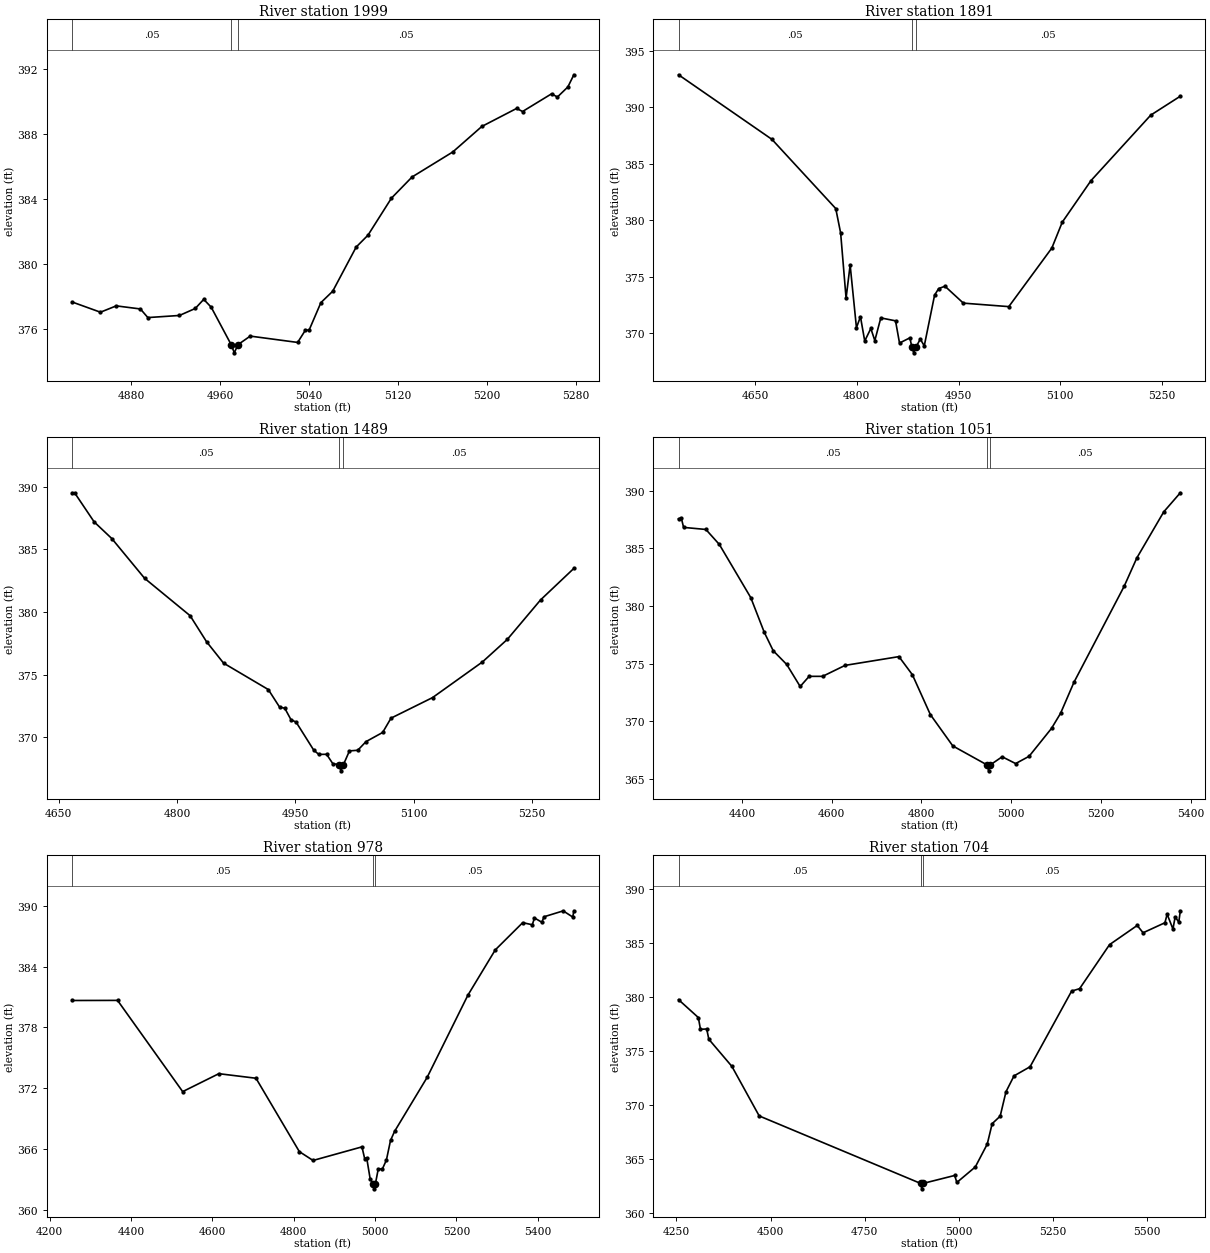
Type RM Length L Ch R = 1 ,1999    ,108,108,108
BEGIN DESCRIPTION:
Mapping XS 704af8b9
END DESCRIPTION:
XS GIS Cut Line= 3
      3530909.72     10460562.74      3530767.82     10460721.56
      3530691.02     10460946.75
#Sta/Elev= 30
    4827  377.64  4852.5  377.01  4866.7   377.4  4888.4  377.21  4895.1  376.68
  4923.5  376.81  4937.7  377.24  4945.3   377.8    4952  377.32    4970  375.01
  4972.8  374.51    4976  375.01  4987.1  375.54  5029.7  375.15  5036.7  375.91
    5040  375.91  5050.6   377.6  5061.2   378.3  5082.3  381.02  5092.9  381.75
    5114  384.03  5132.5  385.33  5169.1  386.87  5195.2  388.44  5226.5  389.55
  5231.8  389.36  5257.9  390.45  5263.1  390.25  5272.5  390.87  5277.9  391.62
#Mann= 3 ,-1 , 0
    4827     .05       0    4970     .03       0    4976     .05       0
Bank Sta=4970,4976
XS Rating Curve= 0 ,0
Exp/Cntr=0.3,0.1

Type RM Length L Ch R = 1 ,1891    ,402,402,402
BEGIN DESCRIPTION:
STEELE CREEK TRIB 17.2 3.0
END DESCRIPTION:
XS GIS Cut Line= 2
      3530970.39      10460219.7      3530574.56      10460844.7
#Sta/Elev= 30
  4537.1   392.9  4674.8  387.17  4768.9  381.03  4776.1  378.86  4784.1  373.08
  4790.1  376.02  4799.4  370.46  4805.3  371.44  4811.6  369.28  4820.6  370.39
  4826.5  369.32  4835.3  371.33    4857  371.07  4862.9   369.1  4878.2  369.56
  4881.1  368.73  4883.9  368.23  4887.1  368.73  4893.5  369.45  4899.4  368.85
  4914.6  373.35  4920.6  373.93  4929.9  374.14    4957  372.64    5024  372.33
  5087.5  377.53  5102.8  379.82  5145.2  383.51  5233.3  389.32  5276.9     391
#Mann= 3 ,-1 , 0
  4537.1     .05       0  4881.1     .03       0  4887.1     .05       0
Bank Sta=4881.1,4887.1
XS Rating Curve= 0 ,0
Exp/Cntr=0.3,0.1

Type RM Length L Ch R = 1 ,1489    ,438,438,438
BEGIN DESCRIPTION:
STEELE CREEK TRIB 17.2 2.0
END DESCRIPTION:
XS GIS Cut Line= 3
      3530692.09     10460091.66      3530492.11     10460341.64
      3530392.09     10460641.68
#Sta/Elev= 30
  4666.8   389.5    4670   389.5  4694.8  387.18  4717.2  385.85  4758.8  382.68
  4816.5   379.7  4837.3  377.63  4858.9  375.92  4915.7  373.81  4930.1   372.4
  4936.5  372.33  4944.5   371.4  4950.9  371.22  4973.3  368.98  4979.7  368.64
  4989.6  368.65  4997.5   367.9    5005  367.83  5007.8  367.33    5011  367.83
  5018.6  368.92  5029.1  368.97  5039.6  369.66  5060.7  370.39  5071.3  371.53
    5124  373.17  5187.2  376.01  5218.8  377.81    5261  380.96  5303.2  383.47
#Mann= 3 ,-1 , 0
  4666.8     .05       0    5005     .03       0    5011     .05       0
Bank Sta=5005,5011
XS Rating Curve= 0 ,0
Exp/Cntr=0.3,0.1

Type RM Length L Ch R = 1 ,1051    ,73,73,73
BEGIN DESCRIPTION:
Mapping XS 20e25dd7
END DESCRIPTION:
XS GIS Cut Line= 2
      3530177.37     10459480.68      3530131.88     10460598.56
#Sta/Elev= 30
  4258.3  387.56  4264.6   387.6  4269.6  386.81  4319.3  386.63  4349.3  385.33
  4419.4  380.72  4449.4  377.72  4469.4  376.12  4499.5  374.93  4529.5  373.02
  4549.5   373.9  4579.5   373.9  4629.6  374.85  4749.7  375.61  4779.7  374.04
  4819.7  370.59  4869.8  367.87  4946.8  366.21  4949.6  365.71  4952.8  366.21
  4979.9  366.93  5009.9  366.34  5039.9  366.97  5089.9  369.39    5110  370.69
    5140  373.39  5251.8   381.7  5280.1  384.16  5340.2  388.16  5377.1  389.81
#Mann= 3 ,-1 , 0
  4258.3     .05       0  4946.8     .03       0  4952.8     .05       0
Bank Sta=4946.8,4952.8
XS Rating Curve= 0 ,0
Exp/Cntr=0.3,0.1

Type RM Length L Ch R = 1 ,978     ,274,274,274
BEGIN DESCRIPTION:
Mapping XS 8604e875
END DESCRIPTION:
XS GIS Cut Line= 4
       3530088.4     10459469.84      3530099.25     10459834.42
      3530053.68     10460565.76      3530107.51     10460690.66
#Sta/Elev= 30
  4255.3  380.65  4367.1  380.66  4527.2  371.66  4616.1  373.43  4707.4  372.98
    4814  365.74  4847.7  364.87  4967.9  366.21  4974.5  365.06  4979.5  365.13
    4988  363.07    4995  362.57  4997.7  362.07    5001  362.57    5008  364.04
    5018  364.02    5028  364.91  5038.1  366.84  5048.1  367.74  5128.2  373.07
  5228.4  381.18  5295.6  385.64  5363.1  388.33  5386.6  388.12    5392  388.79
  5410.1  388.37  5415.5  388.91  5462.6  389.49  5486.1  388.88  5488.8   389.5
#Mann= 3 ,-1 , 0
  4255.3     .05       0    4995     .03       0    5001     .05       0
Bank Sta=4995,5001
XS Rating Curve= 0 ,0
Exp/Cntr=0.3,0.1

Type RM Length L Ch R = 1 ,704     ,249,249,249
BEGIN DESCRIPTION:
Mapping XS 0c9eb5
END DESCRIPTION:
XS GIS Cut Line= 4
      3530083.01     10459454.01      3529878.13     10459858.57
        3529800.     10460216.21      3530067.22     10460653.47
#Sta/Elev= 30
  4255.5  379.74  4308.1  378.08  4313.7  376.99  4330.3  377.02  4335.9  376.07
  4397.2  373.55  4469.6  368.96  4898.3   362.7  4901.1   362.2  4904.3   362.7
  4988.5  363.44  4994.3  362.79  5043.3  364.23    5075  366.35    5088  368.24
  5109.3  368.94  5124.7   371.2    5146  372.67  5188.7  373.52  5298.9  380.53
  5320.2  380.76  5399.6  384.84  5473.1  386.62  5488.6  385.94  5546.6  386.87
  5552.5  387.66  5567.9  386.29  5573.8  387.41  5583.4  386.93  5587.5  387.98
#Mann= 3 ,-1 , 0
  4255.5     .05       0  4898.3     .04       0  4904.3     .05       0
Bank Sta=4898.3,4904.3
XS Rating Curve= 0 ,0
Exp/Cntr=0.3,0.1

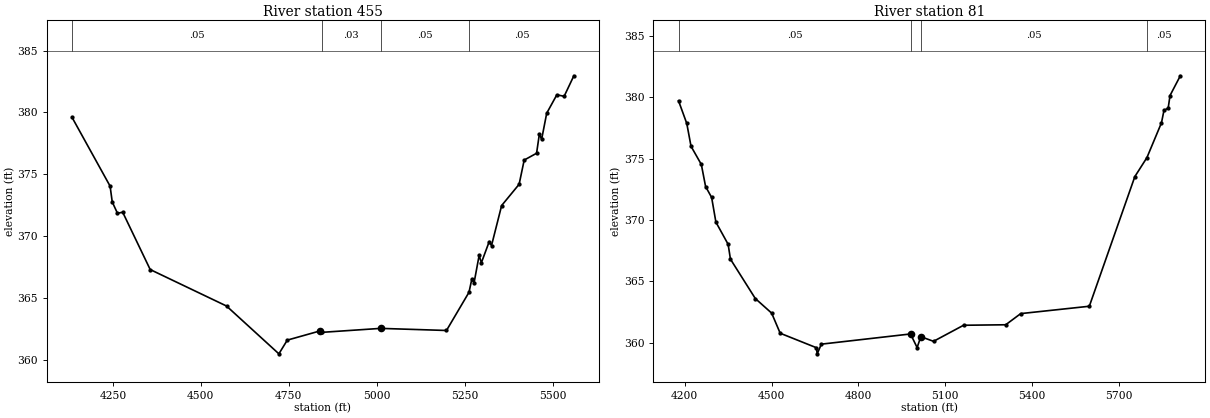
Type RM Length L Ch R = 1 ,455     ,374,374,374
BEGIN DESCRIPTION:
Mapping XS 0c9eb5d3
END DESCRIPTION:
XS GIS Cut Line= 3
      3530079.88     10459419.34      3529545.42     10460187.84
      3529928.29     10460494.14
#Sta/Elev= 30
  4133.9   379.6    4242  374.04  4248.1  372.76    4263  371.84  4277.8  371.93
    4356  367.29  4572.9  364.34  4721.8  360.47  4745.7  361.58  4838.2  362.32
  4844.3  362.21    5011  362.53  5198.2  362.36  5262.2  365.45  5270.2  366.51
  5276.6  366.21    5291  368.43  5297.4  367.84  5319.8  369.56  5326.2  369.23
    5355  372.47  5404.7  374.19  5419.1  376.15  5454.3   376.7  5462.3  378.26
  5468.7  377.83  5483.1  379.94  5511.9  381.43  5532.7  381.31  5560.3  382.97
#Mann= 4 ,-1 , 0
  4133.9     .05       0  4844.3     .03       0    5011     .05       0
  5262.2     .05       0
Bank Sta=4838.2,5011
XS Rating Curve= 0 ,0
Exp/Cntr=0.3,0.1

Type RM Length L Ch R = 1 ,81      ,0,0,0
BEGIN DESCRIPTION:
Mapping XS 59de13c6
END DESCRIPTION:
XS GIS Cut Line= 4
      3530081.19      10459390.7      3529365.03     10459906.33
      3529458.78     10460179.77      3529916.22     10460507.25
#Sta/Elev= 30
  4178.7  379.72  4207.2  377.87  4221.9  376.01  4257.5  374.53  4272.2  372.73
  4293.1  371.84  4307.8  369.83  4350.1  368.02  4358.1  366.81    4444   363.6
  4500.5  362.41    4530  360.77  4655.1  359.59  4657.9  359.09  4672.3  359.88
  4980.4  360.71  5003.2   359.6    5016  360.49  5059.9  360.11  5163.6  361.42
  5309.4  361.46  5361.2  362.37  5598.3  362.97  5755.6  373.54  5797.4  375.09
  5847.7  377.93  5856.3  378.94  5870.8  379.12  5877.2  380.15  5912.8  381.76
#Mann= 4 ,-1 , 0
  4178.7     .05       0  4980.4     .03       0    5016     .05       0
  5797.4     .05       0
Bank Sta=4980.4,5016
XS Rating Curve= 0 ,0
Exp/Cntr=0.3,0.1

Chan Stop Cuts=-1
Use User Specified Reach Order=0
Composite Channel Slope=5