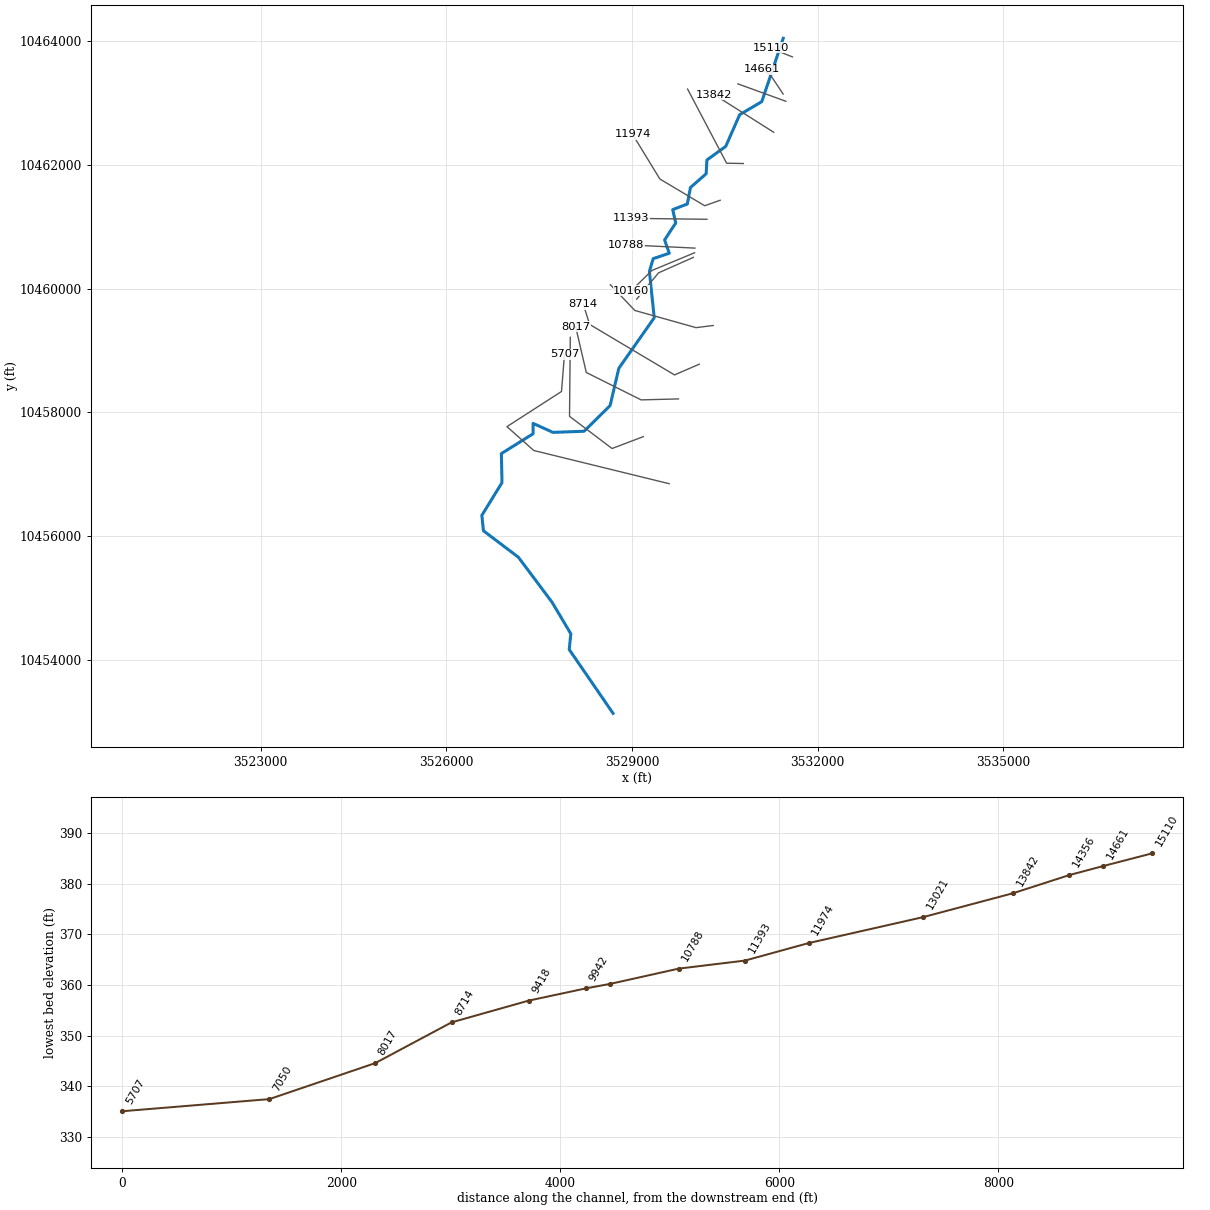
--- STEELE CREEK TRIB 17.prj (project) ---

Proj Title=STEELE CREEK TRIB 17 Base Level Engineering
Current Plan=p01
Default Exp/Contr=0.3,0.1
English Units
Geom File=g01
Flow File=f01
Plan File=p01
Y Axis Title=Elevation
X Axis Title(PF)=Main Channel Distance
X Axis Title(XS)=Station
BEGIN DESCRIPTION:
STEELE CREEK TRIB 17
END DESCRIPTION:
DSS Export Rating Curves= 0
DSS Export Rating Curve Sorted= 0
DSS Export Volume Flow Curves= 0
DXF OffsetX= 0
DXF OffsetY= 0
DXF ScaleX= 1
DXF ScaleY= 10

--- STEELE CREEK TRIB 17.p01 (plan) ---

Plan Title=Multiple Run
Short Identifier=Multiple
Geom File=g01
Flow File=f01
Subcritical Flow
K Sum by GR= 0
Std Step Tol= 0.01
Critical Tol= 0.01
Num of Std Step Trials= 20
Max Error Tol= 0.3
Flow Tol Ratio= 0.001
Split Flow NTrial= 30
Split Flow Tol= 0.02
Split Flow Ratio= 0.02
Log Output Level= 0
Friction Slope Method= 1
Unsteady Friction Slope Method= 2
Unsteady Bridges Friction Slope Method= 1
Parabolic Critical Depth
Global Vel Dist=  1 , 1 , 1
Global Log Level= 0
CheckData=True
Encroach Param= -1, 0, 0, 0
BEGIN DESCRIPTION:
Multiple Run
END DESCRIPTION:

--- STEELE CREEK TRIB 17.f01 (steady flow) ---

Flow Title=Multiple
Number of Profiles=7
Profile Names=10-year,25-year,50-year,1pct_min,100-year,1pct_plu,500-year
River Rch & RM= STEELE CREEK TRI,Reach-1,15110
     663     890    1072     944    1277    1727    1805
River Rch & RM= STEELE CREEK TRI,Reach-1,9418
    1328    1847    2278    2048    2769    3745    4082
Boundary for River Rch & Prof#=STEELE CREEK TRI,Reach-1,1
Up Type=0
Dn Type=3
Dn Slope=0.005
Boundary for River Rch & Prof#=STEELE CREEK TRI,Reach-1,2
Up Type=0
Dn Type=3
Dn Slope=0.005
Boundary for River Rch & Prof#=STEELE CREEK TRI,Reach-1,3
Up Type=0
Dn Type=3
Dn Slope=0.005
Boundary for River Rch & Prof#=STEELE CREEK TRI,Reach-1,4
Up Type=0
Dn Type=3
Dn Slope=0.005
Boundary for River Rch & Prof#=STEELE CREEK TRI,Reach-1,5
Up Type=0
Dn Type=3
Dn Slope=0.005
Boundary for River Rch & Prof#=STEELE CREEK TRI,Reach-1,6
Up Type=0
Dn Type=3
Dn Slope=0.005
Boundary for River Rch & Prof#=STEELE CREEK TRI,Reach-1,7
Up Type=0
Dn Type=3
Dn Slope=0.005

--- STEELE CREEK TRIB 17.g01 (geometry) ---

Geom Title=Existing Conditions
Program Version=4.10

River Reach=STEELE CREEK TRI,Reach-1
Reach XY= 30
      3531443.14     10464041.54      3531096.81     10463018.91
      3530739.67     10462807.63      3530514.17     10462295.41
      3530210.57     10462076.24      3530198.42     10461853.75
      3529943.98     10461630.84      3529894.16     10461365.22
      3529658.26     10461274.34      3529706.68     10461058.51
      3529526.79     10460784.61      3529602.48     10460569.51
      3529342.28      10460481.8      3529281.52     10460273.47
       3529359.8      10459527.4      3528787.21     10458711.13
      3528646.71     10458108.92      3528226.76     10457693.91
      3527722.71     10457675.95      3527402.81     10457821.25
      3527401.47     10457652.92      3526889.94       10457333.
      3526900.36     10456864.25      3526574.84     10456335.61
      3526600.23     10456086.03       3527164.6     10455659.03
      3527707.13      10454934.3      3528012.11     10454421.64
      3527985.77     10454168.38      3528694.57     10453136.29

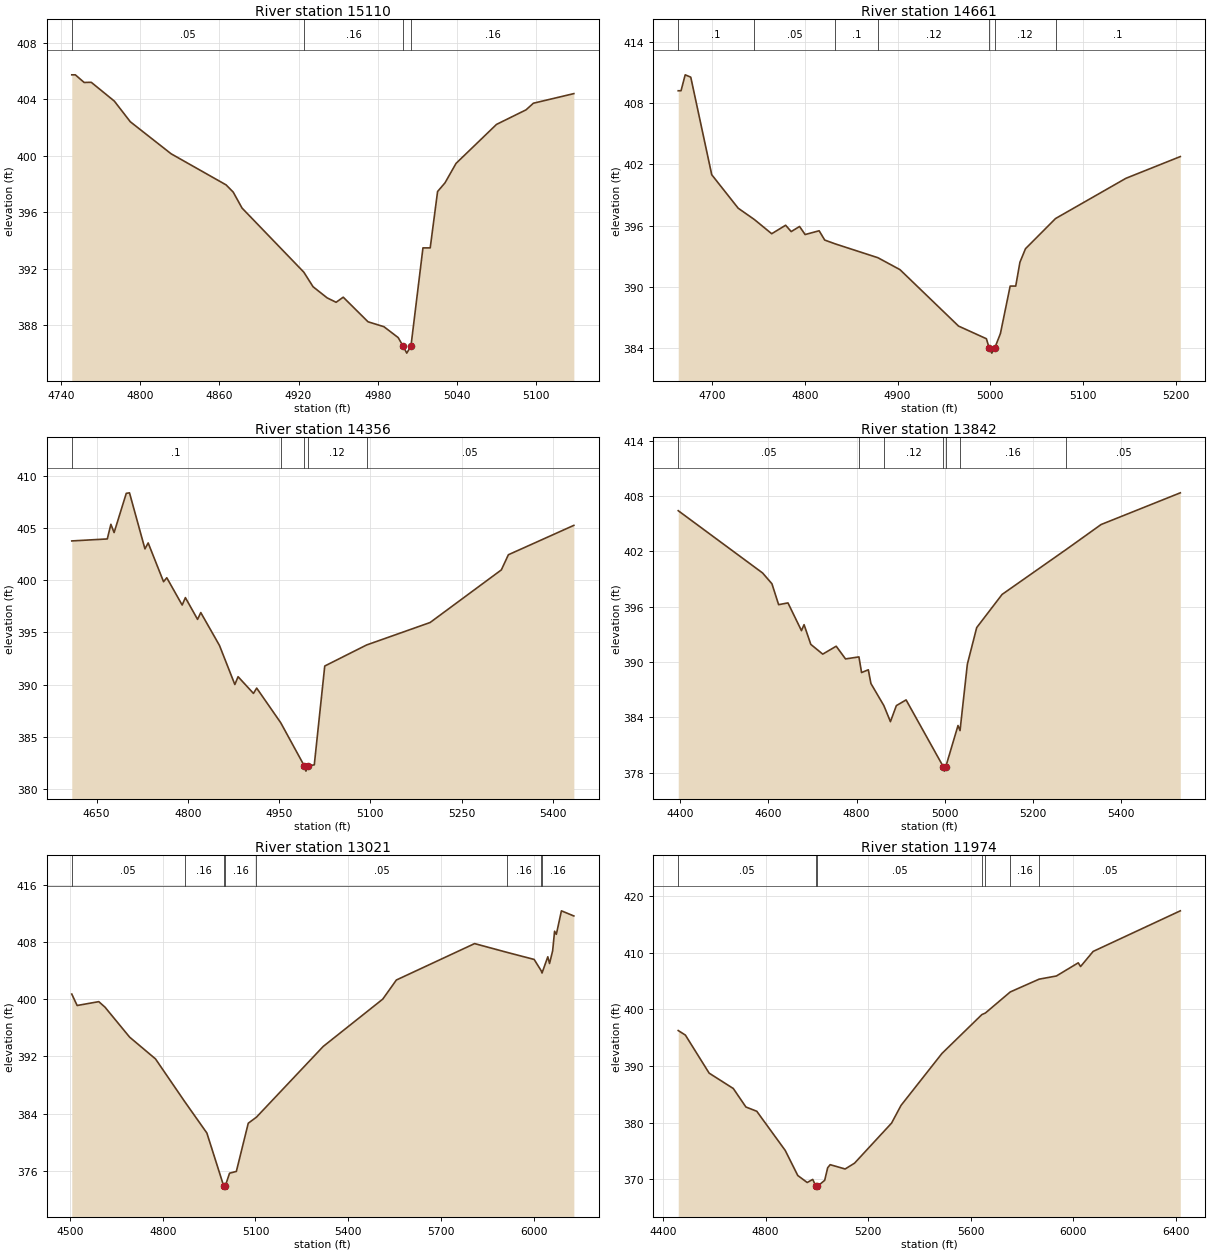
Type RM Length L Ch R = 1 ,15110   ,449,449,449
BEGIN DESCRIPTION:
STEELE CREEK TRIB 17 19.0
END DESCRIPTION:
XS GIS Cut Line= 3
      3531592.08     10463741.65      3531342.11     10463841.64
      3531242.13     10463891.63
#Sta/Elev= 30
  4747.9  405.72  4750.6  405.72  4757.3  405.18  4762.7  405.19  4780.2  403.86
  4792.3   402.4  4823.3  400.13    4865  397.93  4870.4  397.42  4877.1  396.29
    4924  391.75    4931  390.72  4941.7  389.93  4948.5  389.62  4953.9  389.98
  4972.7  388.24  4984.8  387.89  4995.6  387.12  4999.3  386.52  5002.1  386.02
  5005.3  386.52  5014.4  393.47  5019.9  393.47  5025.5  397.46  5031.1  398.07
  5039.5  399.45  5070.2  402.21  5092.6  403.24  5098.2  403.71  5128.9  404.39
#Mann= 4 ,-1 , 0
  4747.9     .05       0    4924     .16       0  4999.3     .07       0
  5005.3     .16       0
Bank Sta=4999.3,5005.3
XS Rating Curve= 0 ,0
Exp/Cntr=0.3,0.1

Type RM Length L Ch R = 1 ,14661   ,305,305,305
BEGIN DESCRIPTION:
STEELE CREEK TRIB 17 18.0
END DESCRIPTION:
XS GIS Cut Line= 3
      3531442.12     10463141.62      3531242.11     10463441.64
      3531092.07     10463541.67
#Sta/Elev= 30
  4663.7  409.21  4666.7  409.21  4671.2  410.77  4677.2  410.54  4699.8  400.98
  4728.3   397.7  4745.6   396.6  4764.4   395.2  4779.4  396.03  4785.4  395.41
  4794.4  395.91  4800.4  395.12  4815.5  395.49  4821.5  394.58    4833   394.2
  4878.8  392.85  4902.6  391.68  4965.7  386.15  4995.7  384.91  4998.7     384
  5001.5   383.5  5004.7     384  5010.8  385.42  5021.3  390.07  5027.3  390.07
  5031.8   392.4  5037.8  393.73  5070.2  396.69    5146  400.63  5204.6  402.76
#Mann= 7 ,-1 , 0
  4663.7      .1       0  4745.6     .05       0    4833      .1       0
  4878.8     .12       0  4998.7     .07       0  5004.7     .12       0
  5070.2      .1       0
Bank Sta=4998.7,5004.7
XS Rating Curve= 0 ,0
Exp/Cntr=0.3,0.1

Type RM Length L Ch R = 1 ,14356   ,514,514,514
BEGIN DESCRIPTION:
STEELE CREEK TRIB 17 17.0
END DESCRIPTION:
XS GIS Cut Line= 2
      3531486.98     10463024.51      3530710.97     10463305.75
#Sta/Elev= 30
  4609.2  403.75  4667.6  403.94  4673.5  405.34  4678.8  404.55  4698.8   408.3
  4704.1  408.35  4729.5  402.99  4734.8  403.56  4760.1  399.85  4765.4  400.23
  4790.7  397.62    4796  398.33    4816  396.25  4821.3   396.9    4852  393.76
  4877.3  390.02  4882.6  390.77  4907.9  389.17  4913.2  389.68  4952.7  386.37
  4991.5  382.24  4994.2  381.74  4997.5  382.24  5007.9  382.34  5025.1  391.79
  5093.8   393.8  5198.3  395.95  5315.4  400.98    5327  402.43  5434.6  405.24
#Mann= 5 ,-1 , 0
  4609.2      .1       0  4952.7     .12       0  4991.5     .07       0
  4997.5     .12       0  5093.8     .05       0
Bank Sta=4991.5,4997.5
XS Rating Curve= 0 ,0
Exp/Cntr=0.3,0.1

Type RM Length L Ch R = 1 ,13842   ,821,821,821
BEGIN DESCRIPTION:
STEELE CREEK TRIB 17 16.0
END DESCRIPTION:
XS GIS Cut Line= 2
      3531289.09     10462524.49      3530326.28     10463133.41
#Sta/Elev= 30
  4395.3  406.42  4586.7  399.66  4607.9  398.49  4623.1  396.22  4644.3  396.41
  4674.9   393.4  4680.8  394.05  4696.1  391.91  4723.2  390.85  4753.7  391.71
  4774.9  390.33  4805.3  390.55  4811.3  388.85  4826.6  389.15  4832.5  387.66
  4861.9  385.26  4876.8  383.52  4890.2  385.26  4912.3  385.88  4996.5  378.65
  4999.3  378.15  5002.5  378.65  5030.1   383.1  5034.7  382.55  5051.3  389.76
  5072.5  393.73  5130.1  397.33  5275.9  402.22  5354.8  404.92  5534.5  408.36
#Mann= 7 ,-1 , 0
  4395.3     .05       0  4805.3     .16       0  4861.9     .12       0
  4996.5     .07       0  5002.5     .12       0  5034.7     .16       0
  5275.9     .05       0
Bank Sta=4996.5,5002.5
XS Rating Curve= 0 ,0
Exp/Cntr=0.3,0.1

Type RM Length L Ch R = 1 ,13021   ,1047,1047,1047
BEGIN DESCRIPTION:
STEELE CREEK TRIB 17 14.0
END DESCRIPTION:
XS GIS Cut Line= 3
      3530799.46      10462019.3      3530528.65     10462024.51
      3529898.46     10463222.39
#Sta/Elev= 30
  4505.7  400.74  4523.1  399.14  4593.1  399.68  4613.1  398.91  4693.1   394.7
  4776.6  391.66  4870.6  385.71  4942.8  381.28  4996.8  373.92  4999.6  373.42
  5002.8  373.92  5016.2  375.65  5038.2   375.9  5076.7  382.65  5103.2   383.5
  5319.1   393.4  5511.8  400.03  5555.9  402.71    5809  407.81  5914.2  406.58
  6001.7  405.59  6024.6     404  6027.2  403.69  6045.8  405.96  6051.5  405.02
  6061.5   406.8  6067.8  409.54  6073.5  409.11  6089.9   412.4  6130.1  411.68
#Mann= 8 ,-1 , 0
  4505.7     .05       0  4870.6     .16       0  4996.8     .07       0
  5002.8     .16       0  5103.2     .05       0  5914.2     .16       0
  6024.6     .05       0  6027.2     .16       0
Bank Sta=4996.8,5002.8
XS Rating Curve= 0 ,0
Exp/Cntr=0.3,0.1

Type RM Length L Ch R = 1 ,11974   ,581,581,581
BEGIN DESCRIPTION:
STEELE CREEK TRIB 17 12.0
END DESCRIPTION:
XS GIS Cut Line= 4
       3530424.5     10461425.55      3530174.49     10461337.01
      3529450.53      10461769.3      3529007.83     10462493.24
#Sta/Elev= 30
  4459.5  396.24  4487.4  395.44    4580  388.73  4674.2  386.02  4723.3  382.76
  4765.6  382.01  4876.6   375.1  4925.5  370.68  4962.2  369.45  4983.7  369.99
  4996.1  368.78  4998.9  368.28  5002.1  368.78  5030.3  369.83    5042  372.05
  5051.7  372.59  5110.1  371.83  5146.8  372.86    5291  379.92    5328  383.05
  5487.6  392.21  5642.9  399.05  5656.7  399.33  5753.8  403.05  5866.1   405.3
  5933.4  405.86  6018.7  408.18  6027.8  407.53  6076.7  410.19  6416.5  417.35
#Mann= 7 ,-1 , 0
  4459.5     .05       0  4996.1    .035       0  5002.1     .05       0
  5642.9     .16       0  5656.7     .05       0  5753.8     .16       0
  5866.1     .05       0
Bank Sta=4996.1,5002.1
XS Rating Curve= 0 ,0
Exp/Cntr=0.3,0.1

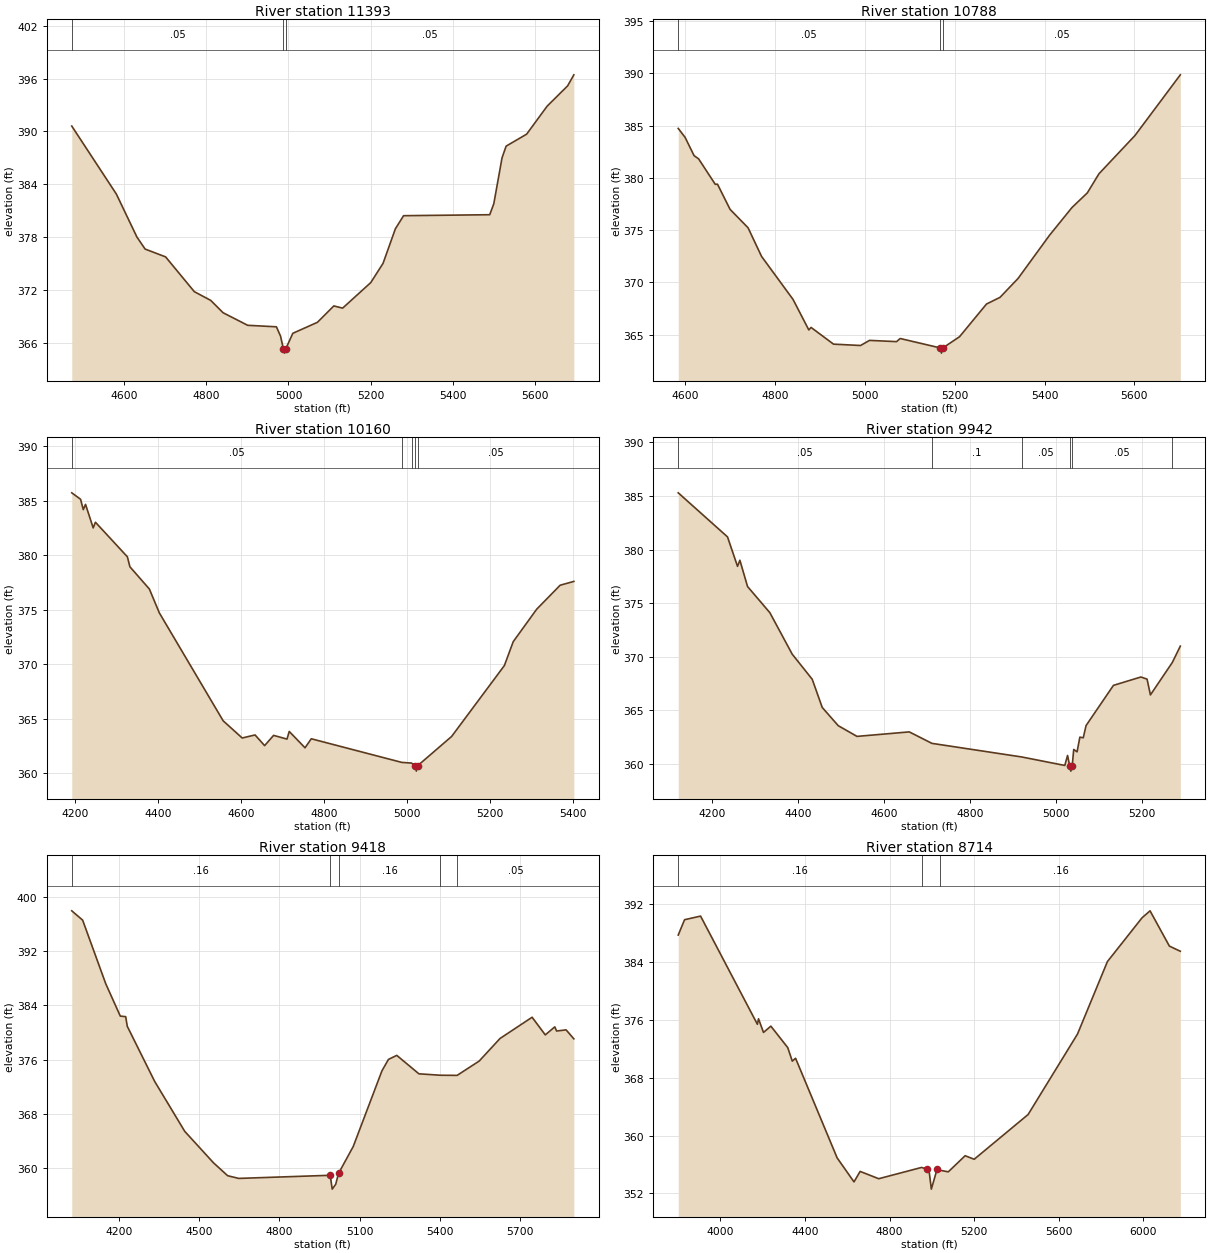
Type RM Length L Ch R = 1 ,11393   ,605,605,605
BEGIN DESCRIPTION:
STEELE CREEK TRIB 17 11.0
END DESCRIPTION:
XS GIS Cut Line= 2
      3530210.92     10461118.26      3528987.02     10461133.88
#Sta/Elev= 30
  4471.7  390.61  4580.5  382.88  4630.5  378.01  4650.5  376.64  4700.5  375.75
  4770.5   371.8  4810.5  370.81  4840.5  369.41  4900.6  367.98  4970.6  367.81
  4980.6  366.76  4987.6  365.32  4990.3  364.82  4993.6  365.32  5010.6  367.07
  5070.6  368.32  5110.6  370.18    5132  369.93  5200.6  372.83  5230.6  375.02
  5260.6  378.94  5280.6  380.43  5490.6  380.54  5500.6  381.79  5520.6  386.99
  5530.6  388.33  5580.6  389.69  5630.6  392.87  5680.6  395.18  5695.7  396.43
#Mann= 3 ,-1 , 0
  4471.7     .05       0  4987.6     .03       0  4993.6     .05       0
Bank Sta=4987.6,4993.6
XS Rating Curve= 0 ,0
Exp/Cntr=0.3,0.1

Type RM Length L Ch R = 1 ,10788   ,628,628,628
BEGIN DESCRIPTION:
STEELE CREEK TRIB 17 10.0
END DESCRIPTION:
XS GIS Cut Line= 2
      3530017.34     10460652.55      3528901.35     10460706.72
#Sta/Elev= 30
  4584.8  384.74    4600  383.89  4620.1  382.13  4630.1  381.83  4667.2  379.39
  4672.2   379.4  4700.2  376.99  4740.2  375.23  4770.2  372.49  4840.3  368.37
  4875.4  365.45  4880.4  365.69  4930.4  364.09  4990.5  363.96  5010.5  364.45
  5070.6  364.33  5078.7  364.63  5167.7  363.73  5170.5  363.23  5173.7  363.73
  5210.8   364.8  5270.8  367.93  5300.9  368.57  5340.9  370.37    5411  374.51
  5461.1  377.17  5495.2  378.57  5521.1   380.4  5601.2  384.06  5702.1  389.87
#Mann= 3 ,-1 , 0
  4584.8     .05       0  5167.7     .03       0  5173.7     .05       0
Bank Sta=5167.7,5173.7
XS Rating Curve= 0 ,0
Exp/Cntr=0.3,0.1

Type RM Length L Ch R = 1 ,10160   ,218,218,218
BEGIN DESCRIPTION:
Mapping XS aa85c134
END DESCRIPTION:
XS GIS Cut Line= 3
      3530011.66     10460577.76      3529321.93     10460291.28
      3528990.35     10459966.65
#Sta/Elev= 30
  4191.7  385.74  4212.9  385.15  4219.5   384.2  4224.9  384.68  4243.4  382.52
  4248.8  383.04  4325.8  379.87    4332  378.95  4378.9  376.91  4402.8  374.73
  4556.8  364.82  4602.7  363.24  4633.8  363.52  4656.8  362.54  4678.5  363.48
  4710.8  363.14  4716.2  363.84  4754.3  362.34  4769.3  363.17  4987.7     361
  5011.1  360.94    5020   360.7  5022.7   360.2    5026   360.7  5107.8  363.38
  5235.1  369.89  5256.4  372.08    5313  375.06  5369.6  377.26  5402.6  377.61
#Mann= 5 ,-1 , 0
  4191.7     .05       0  4987.7      .1       0  5011.1     .05       0
    5020     .07       0    5026     .05       0
Bank Sta=5020,5026
XS Rating Curve= 0 ,0
Exp/Cntr=0.3,0.1

Type RM Length L Ch R = 1 ,9942    ,524,524,524
BEGIN DESCRIPTION:
Mapping XS 33b7466d
END DESCRIPTION:
XS GIS Cut Line= 3
       3529992.1      10460503.1      3529429.57     10460253.09
      3529076.28      10459828.8
#Sta/Elev= 30
    4122  385.29  4236.6  381.18  4259.9  378.43  4265.4     379  4283.2  376.55
  4335.1  374.11  4387.1  370.24  4433.6   367.9  4456.9  365.27  4494.1  363.57
  4537.8  362.57  4659.3  362.99    4712  361.92    4921  360.65    5021  359.86
  5027.5  360.79  5032.3  359.83  5035.1  359.33  5038.3  359.83  5041.8  361.35
  5049.6  361.13  5056.1   362.5    5064  362.44  5070.5  363.58  5134.2  367.33
    5198  368.11  5212.4  367.91  5220.2  366.44  5271.2  369.47  5289.7  370.99
#Mann= 6 ,-1 , 0
    4122     .05       0    4712      .1       0    4921     .05       0
  5032.3     .03       0  5038.3     .05       0  5271.2      .1       0
Bank Sta=5032.3,5038.3
XS Rating Curve= 0 ,0
Exp/Cntr=0.3,0.1

Type RM Length L Ch R = 1 ,9418    ,704,704,704
BEGIN DESCRIPTION:
STEELE CREEK TRIB 17 8.0
END DESCRIPTION:
XS GIS Cut Line= 4
      3530312.51     10459402.55      3530034.73     10459367.82
      3529045.15      10459645.6      3528650.74     10460061.44
#Sta/Elev= 30
  4021.9  397.93  4062.6  396.56  4149.2  387.18  4203.7  382.41  4223.9  382.33
  4229.8  380.91  4332.5  372.78  4445.1  365.42  4552.6  360.79  4605.8  358.88
  4647.3  358.48  4990.1  358.94  4997.6   356.9  5010.8  357.62  5021.2  359.21
  5076.4  363.19  5183.9  374.34  5208.2  376.02  5239.4  376.62  5322.4   373.9
  5402.6  373.69  5465.5  373.67  5548.2  375.78  5626.3  379.11  5746.4  382.24
  5795.8  379.64  5831.4  380.82  5838.2  380.21  5873.8  380.38  5902.8  379.06
#Mann= 5 ,-1 , 0
  4021.9     .16       0  4990.1     .12       0  5021.2     .16       0
  5402.6      .1       0  5465.5     .05       0
Bank Sta=4990.1,5021.2
XS Rating Curve= 0 ,0
Exp/Cntr=0.3,0.1

Type RM Length L Ch R = 1 ,8714    ,697,697,697
BEGIN DESCRIPTION:
STEELE CREEK TRIB 17 6.0
END DESCRIPTION:
XS GIS Cut Line= 4
      3530086.85     10458777.56      3529687.51     10458603.93
      3528315.98     10459419.91      3528212.32     10459748.17
#Sta/Elev= 30
  3800.1  387.74    3830  389.86  3905.8  390.36  4174.6   375.4    4180  376.16
  4203.5  374.27  4238.4  375.14  4318.3  372.17  4339.7   370.3  4355.3   370.7
    4552  356.92  4631.8   353.6  4660.7  355.05  4748.7  354.04  4951.6   355.6
  4974.9  355.37  4988.2  354.83  4997.7   352.6  5025.2  355.38  5040.8   355.2
  5077.8  354.99  5157.7  357.22  5200.5  356.73  5455.6  362.92  5689.3  374.05
  5830.8  384.07  5994.8  390.13  6032.5  391.09  6124.1  386.21  6175.7   385.5
#Mann= 3 ,-1 , 0
  3800.1     .16       0  4951.6     .12       0  5040.8     .16       0
Bank Sta=4974.9,5025.2
XS Rating Curve= 0 ,0
Exp/Cntr=0.3,0.1

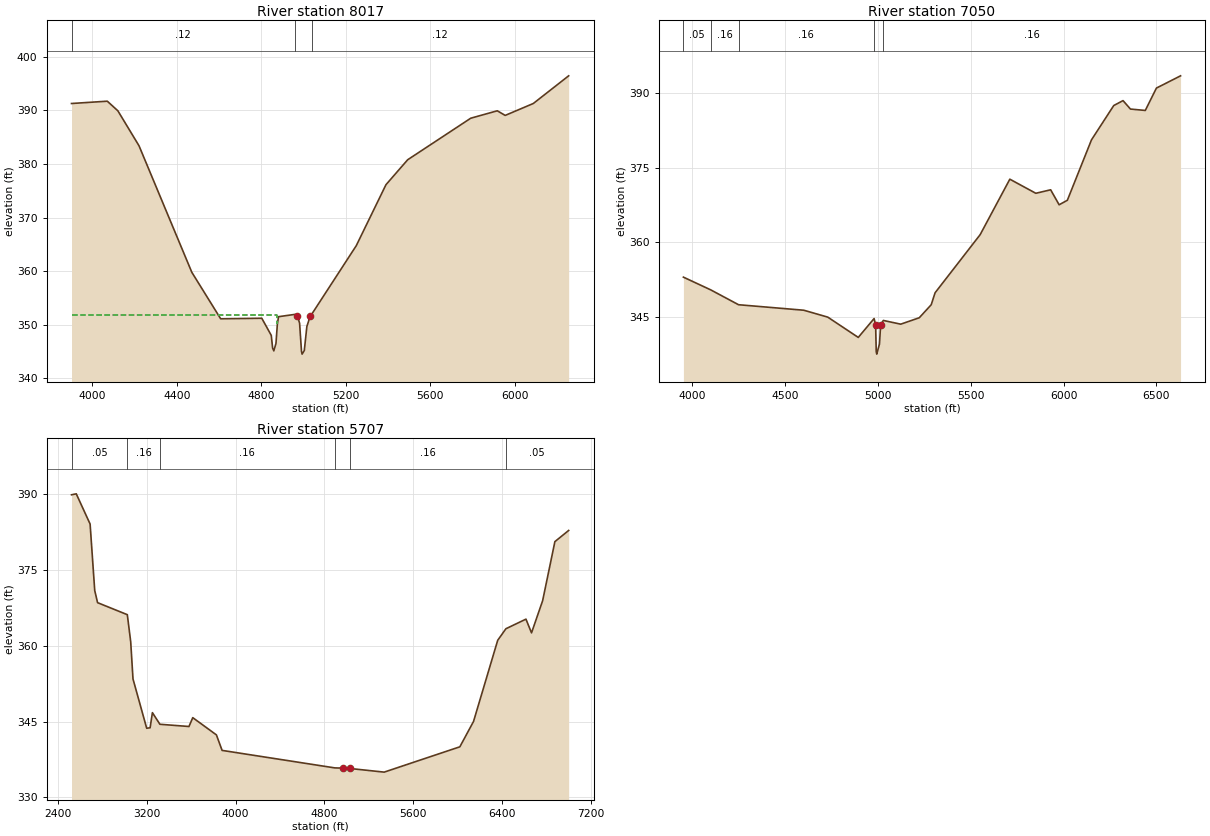
Type RM Length L Ch R = 1 ,8017    ,967,967,967
BEGIN DESCRIPTION:
Mapping XS f37951e1
END DESCRIPTION:
XS GIS Cut Line= 4
      3529751.45     10458216.37      3529147.28     10458200.74
      3528261.86     10458643.45      3528089.99     10459383.04
#Sta/Elev= 30
  3900.9  391.27  4070.3   391.7  4120.3  389.91  4220.4  383.39  4470.4   359.8
    4607  351.13  4801.7  351.23  4846.5  348.04    4853  345.66  4858.6  345.15
  4868.8  346.52  4875.3  350.08  4880.9  351.52  4958.3  351.95  4970.4  351.65
  4980.6  350.32  4989.7  345.04  4992.5  344.54    5003  345.22  5015.1   349.7
  5031.9  351.72  5037.4  351.94    5249  364.76  5389.6  376.13  5492.3  380.78
  5791.1  388.53  5916.6  389.91  5954.1  389.05  6087.1  391.27  6254.5  396.43
#Mann= 3 ,-1 , 0
  3900.9     .12       0  4958.3     .05       0  5037.4     .12       0
#XS Ineff= 2 , 0
       0 4875.57  351.79               0
Permanent Ineff=
       T       F
Bank Sta=4970.4,5031.9
XS Rating Curve= 0 ,0
Exp/Cntr=0.3,0.1

Type RM Length L Ch R = 1 ,7050    ,1343,1343,1343
BEGIN DESCRIPTION:
STEELE CREEK TRIB 17 1.1
END DESCRIPTION:
XS GIS Cut Line= 4
      3529183.72     10457606.99      3528677.94     10457415.17
      3527991.03     10457935.12      3528003.48     10459211.61
#Sta/Elev= 30
  3951.5  352.94    4099  350.37  4248.6  347.38  4600.3  346.27  4729.3  344.88
  4893.7  340.79    4979  344.59  4987.3  343.33  4990.6  337.92  4993.3  337.42
  5008.1  339.48  5014.4  343.38  5028.9  344.21  5122.5  343.46  5222.4  344.75
  5286.9  347.38  5307.7  349.79  5550.5   361.5  5710.5  372.69  5850.5  369.85
  5930.5  370.55  5976.2  367.53  6020.5  368.44  6150.5  380.62  6270.5  387.54
  6320.5  388.53  6360.5  386.83  6440.5  386.55  6500.5  391.06  6630.5  393.53
#Mann= 5 ,-1 , 0
  3951.5     .05       0    4099     .16       0  4248.6     .16       0
    4979     .12       0  5028.9     .16       0
Bank Sta=4987.3,5014.4
XS Rating Curve= 0 ,0
Exp/Cntr=0.3,0.1

Type RM Length L Ch R = 1 ,5707    ,0,0,0
BEGIN DESCRIPTION:
STEELE CREEK TRIB 17 1.0
END DESCRIPTION:
XS GIS Cut Line= 5
      3529600.16     10456846.82      3527412.69     10457383.27
       3526980.4     10457768.68      3527861.47     10458336.39
      3527909.21     10458935.31
#Sta/Elev= 30
  2521.1  389.91  2563.9   390.1  2688.6  384.12  2730.2  370.97  2755.9  368.56
    3024  366.18  3054.5  360.82  3075.1  353.46  3198.6   343.7  3229.3   343.8
  3250.1  346.79  3317.7  344.49  3579.6  344.05  3613.8   345.8  3826.9  342.39
  3878.2  339.32  4893.4  335.86  4963.6  335.81    5028  335.82  5034.7  335.73
  5338.8  335.02  6020.8  340.03  6144.2  345.05    6362  361.11    6436   363.4
  6616.6   365.3  6666.8  362.58  6767.1  368.96  6877.4  380.64  7001.5  382.85
#Mann= 6 ,-1 , 0
  2521.1     .05       0    3024     .16       0  3317.7     .16       0
  4893.4     .12       0  5034.7     .16       0    6436     .05       0
Bank Sta=4963.6,5028
XS Rating Curve= 0 ,0
Exp/Cntr=0.3,0.1

Chan Stop Cuts=-1
Use User Specified Reach Order=0
Composite Channel Slope=5