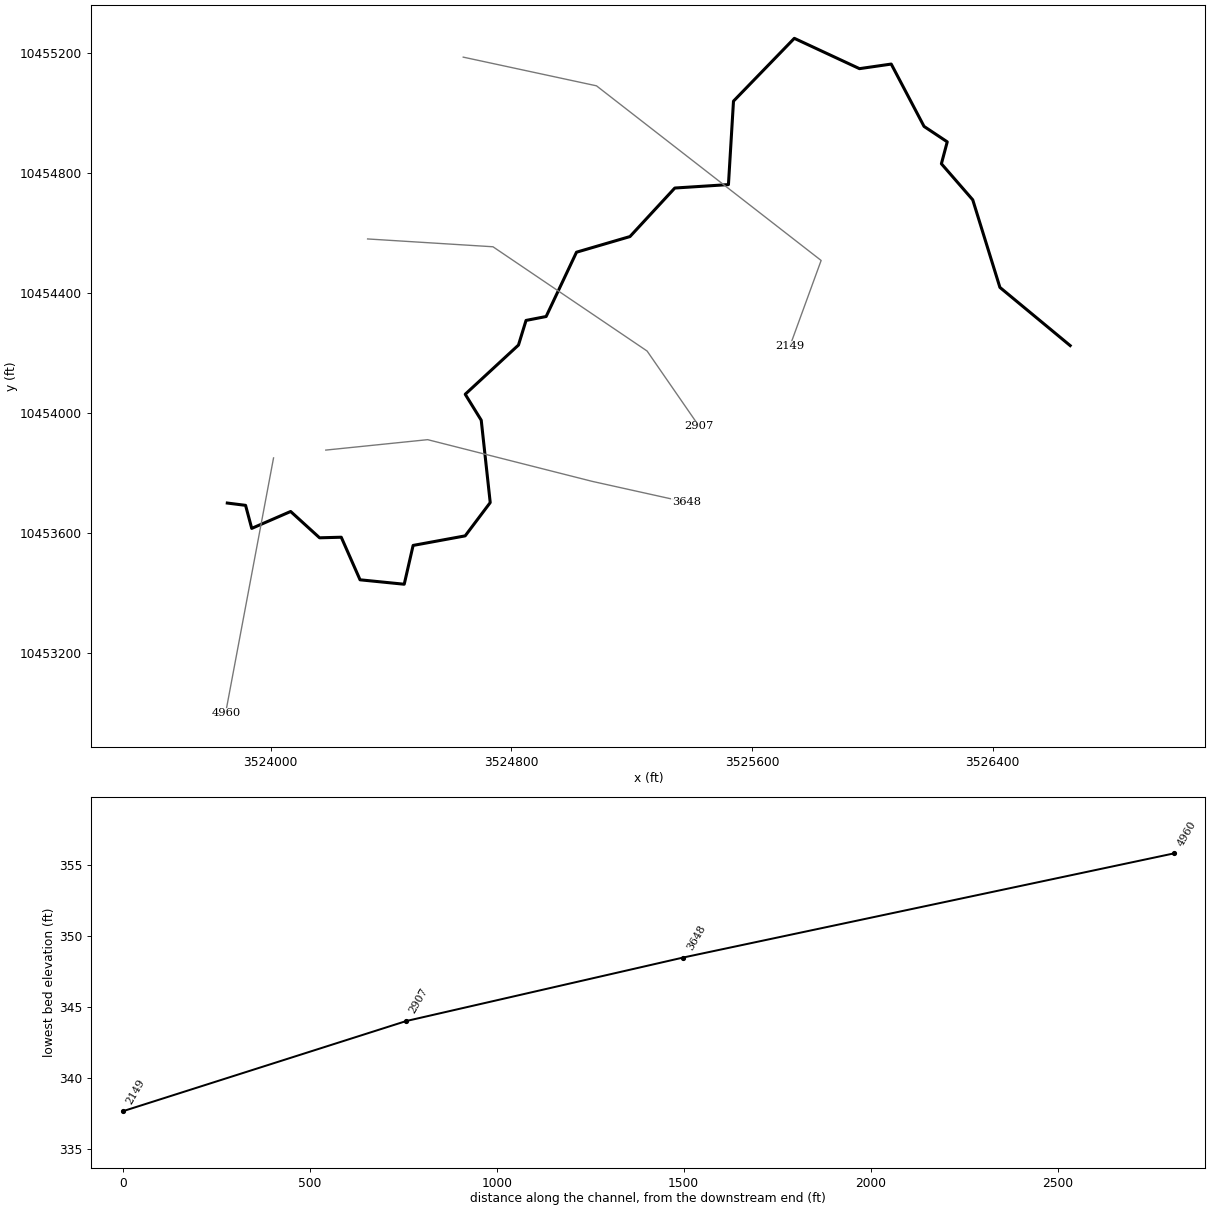
--- STEELE CREEK TRIB 18.prj (project) ---

Proj Title=STEELE CREEK TRIB 18 Base Level Engineering
Current Plan=p01
Default Exp/Contr=0.3,0.1
English Units
Geom File=g01
Flow File=f01
Plan File=p01
BEGIN DESCRIPTION:
STEELE CREEK TRIB 18
END DESCRIPTION:

--- STEELE CREEK TRIB 18.p01 (plan) ---

Plan Title=Multiple Run
Short Identifier=Multiple
Geom File=g01
Flow File=f01
Subcritical Flow
K Sum by GR= 0
Std Step Tol= 0.01
Critical Tol= 0.01
Num of Std Step Trials= 20
Max Error Tol= 0.3
Flow Tol Ratio= 0.001
Split Flow NTrial= 30
Split Flow Tol= 0.02
Split Flow Ratio= 0.02
Log Output Level= 0
Friction Slope Method= 1
Unsteady Friction Slope Method= 2
Unsteady Bridges Friction Slope Method= 1
Parabolic Critical Depth
Global Vel Dist=  1 , 1 , 1
Global Log Level= 0
CheckData=True
Encroach Param= -1, 0, 0, 0
BEGIN DESCRIPTION:
Multiple Run
END DESCRIPTION:

--- STEELE CREEK TRIB 18.f01 (steady flow) ---

Flow Title=Multiple
Number of Profiles=7
Profile Names=10-year,25-year,50-year,1pct_min,100-year,1pct_plu,500-year
River Rch & RM= STEELE CREEK TRI,Reach-1,4960
     544     722     863     755    1022    1382    1425
Boundary for River Rch & Prof#=STEELE CREEK TRI,Reach-1,1
Up Type=0
Dn Type=3
Dn Slope=0.005
Boundary for River Rch & Prof#=STEELE CREEK TRI,Reach-1,2
Up Type=0
Dn Type=3
Dn Slope=0.005
Boundary for River Rch & Prof#=STEELE CREEK TRI,Reach-1,3
Up Type=0
Dn Type=3
Dn Slope=0.005
Boundary for River Rch & Prof#=STEELE CREEK TRI,Reach-1,4
Up Type=0
Dn Type=3
Dn Slope=0.005
Boundary for River Rch & Prof#=STEELE CREEK TRI,Reach-1,5
Up Type=0
Dn Type=3
Dn Slope=0.005
Boundary for River Rch & Prof#=STEELE CREEK TRI,Reach-1,6
Up Type=0
Dn Type=3
Dn Slope=0.005
Boundary for River Rch & Prof#=STEELE CREEK TRI,Reach-1,7
Up Type=0
Dn Type=3
Dn Slope=0.005

--- STEELE CREEK TRIB 18.g01 (geometry) ---

Geom Title=Existing Conditions

River Reach=STEELE CREEK TRI,Reach-1
Reach XY= 30
      3523856.27     10453700.00      3523917.03     10453692.32
      3523937.48     10453615.57      3524066.77     10453671.89
      3524162.91     10453584.24      3524234.97     10453586.18
      3524297.43     10453444.37      3524444.23     10453429.63
      3524473.77     10453558.85      3524646.77     10453590.69
      3524729.99     10453701.56      3524700.12     10453975.84
      3524646.90     10454062.23      3524823.86     10454226.09
      3524849.02     10454308.12      3524915.78     10454321.13
      3525016.72     10454535.31      3525194.38     10454587.40
      3525343.37     10454749.02      3525521.59     10454760.43
      3525538.38     10455038.38      3525740.52     10455247.50
      3525957.01     10455146.54      3526062.57     10455161.82
      3526171.59     10454954.18      3526248.68     10454902.79
      3526229.23     10454829.87      3526333.40     10454709.74
      3526423.68     10454418.07      3526657.19     10454224.30

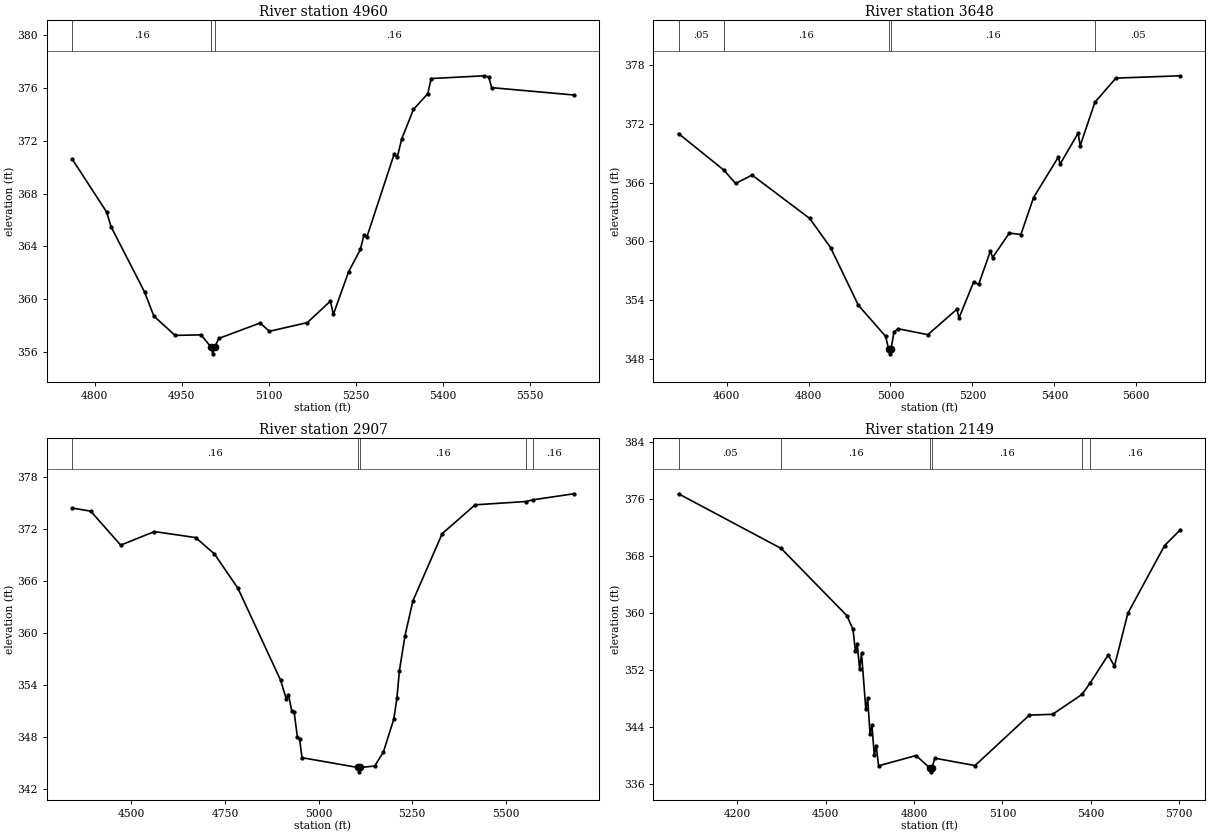
Type RM Length L Ch R = 1,4960,1312,1312,1312
BEGIN DESCRIPTION:
STEELE CREEK TRIB 18 7.0
END DESCRIPTION:
XS GIS Cut Line= 3
      3524009.98     10453850.26      3523853.73     10453016.95
      3523853.73     10452999.58
#Sta/Elev= 30
  4760.9  370.63  4820.5  366.60  4828.2  365.48  4885.8  360.54  4901.9  358.71
  4938.4  357.24  4983.3  357.28  5000.7  356.34  5003.4  355.84  5006.7  356.34
  5013.9  357.01  5085.1  358.18  5101.2  357.55  5166.5  358.21  5206.3  359.84
  5211.4  358.83  5237.7  362.07  5258.0  363.76  5264.0  364.84  5269.1  364.69
  5316.5  371.03  5321.6  370.75  5329.3  372.15  5349.6  374.39  5374.2  375.58
  5380.1  376.73  5471.7  376.94  5479.3  376.85  5484.4  376.04  5626.1  375.48
#Mann=3,-1,0
  4760.9    0.16       0  5000.7    0.07       0  5006.7    0.16       0
Bank Sta=5000.7,5006.7
Exp/Cntr=0.3,0.1

Type RM Length L Ch R = 1,3648,741,741,741
BEGIN DESCRIPTION:
STEELE CREEK TRIB 18 4.0
END DESCRIPTION:
XS GIS Cut Line= 4
      3524183.56     10453876.32      3524522.13     10453911.05
      3525069.01     10453772.16      3525381.50     10453702.71
#Sta/Elev= 30
  4482.8  371.02  4593.6  367.28  4622.1  365.92  4662.3  366.78  4803.0  362.34
  4854.1  359.35  4921.7  353.47  4988.2  350.29  4995.5  349.00  4998.2  348.50
  5001.5  349.00  5008.8  350.77  5019.2  351.06  5091.4  350.46  5162.2  353.06
  5167.4  352.17  5203.2  355.86  5215.2  355.59  5244.1  359.02  5249.3  358.35
  5290.2  360.85  5318.4  360.70  5349.3  364.48  5409.4  368.59  5414.5  367.93
  5458.0  371.06  5463.1  369.78  5499.0  374.22  5550.2  376.69  5707.5  376.93
#Mann=5,-1,0
  4482.8    0.05       0  4593.6    0.16       0  4995.5    0.07       0
  5001.5    0.16       0  5499.0    0.05       0
Bank Sta=4995.5,5001.5
Exp/Cntr=0.3,0.1

Type RM Length L Ch R = 1,2907,758,758,758
BEGIN DESCRIPTION:
STEELE CREEK TRIB 18 2.0
END DESCRIPTION:
XS GIS Cut Line= 4
      3524322.51     10454579.45      3524739.15     10454553.41
      3525251.30     10454206.19      3525424.17     10453955.53
#Sta/Elev= 30
  4341.3  374.38  4391.1  374.02  4471.2  370.11  4561.3  371.67  4671.5  370.98
  4721.6  369.10  4784.5  365.14  4898.4  354.57  4913.4  352.45  4919.4  352.92
  4928.3  351.04  4934.4  350.95  4943.3  348.04  4949.3  347.80  4955.6  345.65
  5105.0  344.52  5107.8  344.02  5111.0  344.52  5150.0  344.69  5173.1  346.30
  5200.9  350.09  5209.3  352.52  5215.9  355.67  5230.8  359.68  5251.8  363.68
  5330.2  371.43  5418.2  374.75  5554.6  375.13  5573.2  375.33  5682.0  376.02
#Mann=5,-1,0
  4341.3    0.16       0  5105.0    0.07       0  5111.0    0.16       0
  5554.6    0.05       0  5573.2    0.16       0
Bank Sta=5105,5111
Exp/Cntr=0.3,0.1

Type RM Length L Ch R = 1,2149,0,0,0
BEGIN DESCRIPTION:
STEELE CREEK TRIB 18 1.0
END DESCRIPTION:
XS GIS Cut Line= 4
      3524640.32     10455184.89      3525083.05     10455089.40
      3525829.58     10454507.81      3525725.40     10454221.31
#Sta/Elev= 30
  4000.2  376.72  4348.8  369.04  4571.9  359.60  4592.7  357.67  4600.9  354.59
  4607.2  355.61  4615.3  352.04  4621.7  354.34  4636.2  346.43  4642.5  348.00
  4650.6  342.95  4657.0  344.20  4665.1  339.96  4671.4  341.35  4679.6  338.51
  4806.9  339.95  4854.6  338.16  4857.3  337.66  4860.6  338.16  4870.5  339.58
  5007.1  338.54  5191.7  345.63  5270.4  345.74  5370.8  348.55  5396.9  350.07
  5459.2  354.07  5480.5  352.50  5526.1  359.93  5650.7  369.44  5704.3  371.66
#Mann=6,-1,0
  4000.2    0.05       0  4348.8    0.16       0  4854.6    0.07       0
  4860.6    0.16       0  5370.8    0.05       0  5396.9    0.16       0
Bank Sta=4854.6,4860.6
Exp/Cntr=0.3,0.1

Chan Stop Cuts=-1