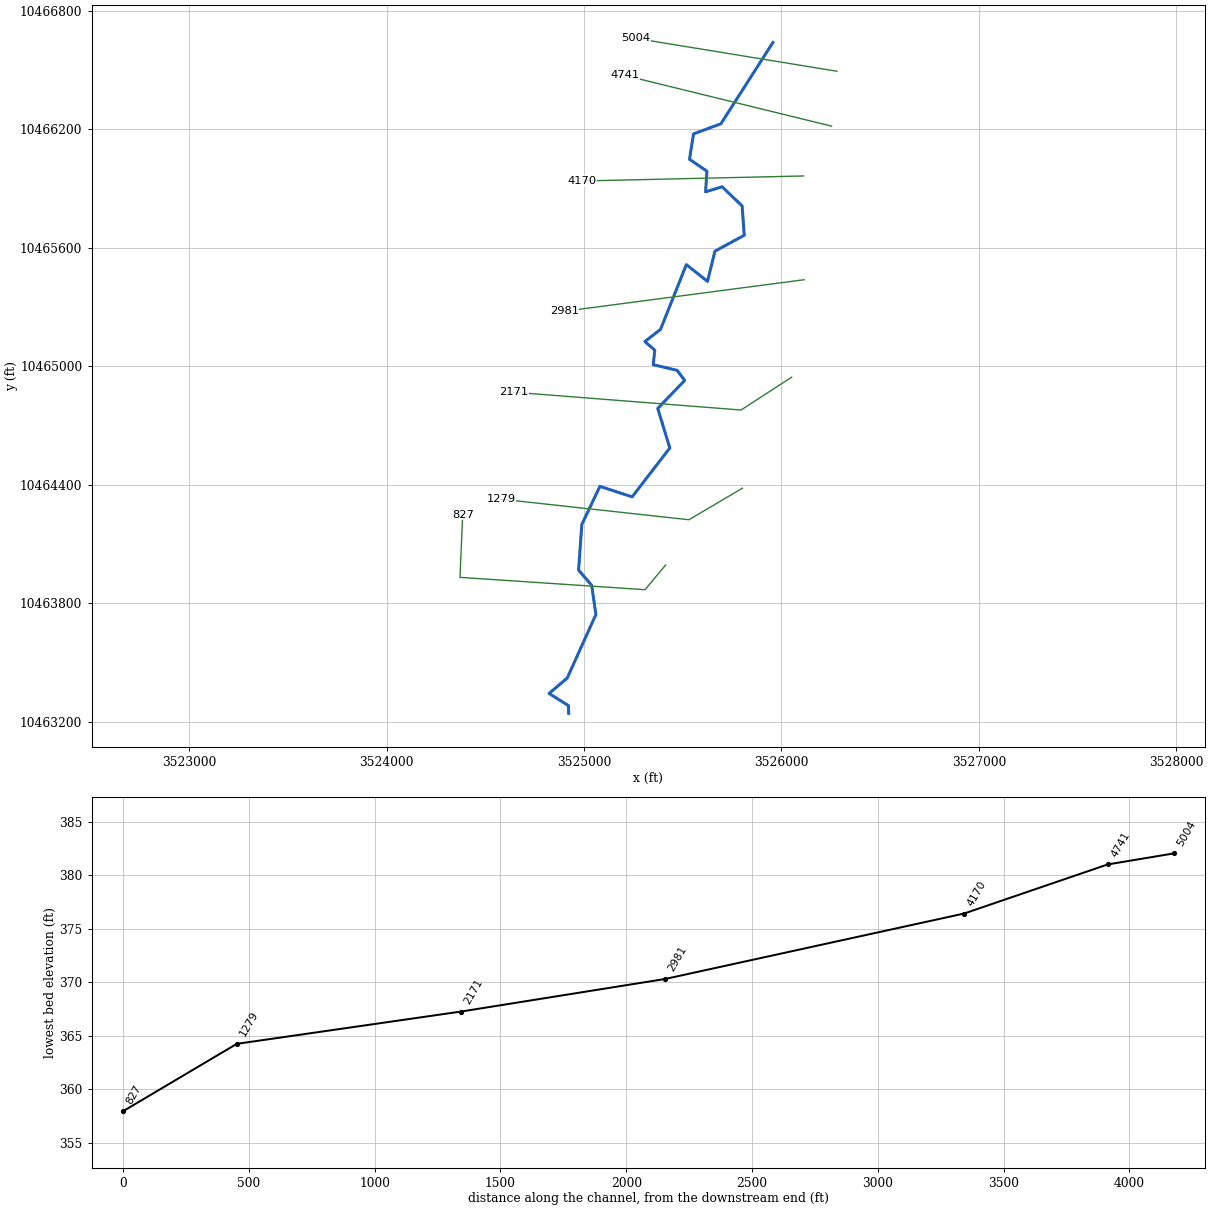
--- STEELE CREEK TRIB 19 3.prj (project) ---

Proj Title=STEELE CREEK TRIB 19 3 Base Level Engineering
Current Plan=p01
Default Exp/Contr=0.3,0.1
English Units
Geom File=g01
Flow File=f01
Plan File=p01
BEGIN DESCRIPTION:
STEELE CREEK TRIB 19 3
END DESCRIPTION:

--- STEELE CREEK TRIB 19 3.p01 (plan) ---

Plan Title=Multiple Run
Short Identifier=Multiple
Geom File=g01
Flow File=f01
Subcritical Flow
K Sum by GR= 0
Std Step Tol= 0.01
Critical Tol= 0.01
Num of Std Step Trials= 20
Max Error Tol= 0.3
Flow Tol Ratio= 0.001
Split Flow NTrial= 30
Split Flow Tol= 0.02
Split Flow Ratio= 0.02
Log Output Level= 0
Friction Slope Method= 1
Unsteady Friction Slope Method= 2
Unsteady Bridges Friction Slope Method= 1
Parabolic Critical Depth
Global Vel Dist=  1 , 1 , 1
Global Log Level= 0
CheckData=True
Encroach Param= -1, 0, 0, 0
BEGIN DESCRIPTION:
Multiple Run
END DESCRIPTION:

--- STEELE CREEK TRIB 19 3.f01 (steady flow) ---

Flow Title=Multiple
Number of Profiles=7
Profile Names=10-year,25-year,50-year,1pct_min,100-year,1pct_plu,500-year
River Rch & RM= STEELE CREEK TRI,Reach-1,5004
     523     690     822     717     969    1311    1341
Boundary for River Rch & Prof#=STEELE CREEK TRI,Reach-1,1
Up Type=0
Dn Type=3
Dn Slope=0.005
Boundary for River Rch & Prof#=STEELE CREEK TRI,Reach-1,2
Up Type=0
Dn Type=3
Dn Slope=0.005
Boundary for River Rch & Prof#=STEELE CREEK TRI,Reach-1,3
Up Type=0
Dn Type=3
Dn Slope=0.005
Boundary for River Rch & Prof#=STEELE CREEK TRI,Reach-1,4
Up Type=0
Dn Type=3
Dn Slope=0.005
Boundary for River Rch & Prof#=STEELE CREEK TRI,Reach-1,5
Up Type=0
Dn Type=3
Dn Slope=0.005
Boundary for River Rch & Prof#=STEELE CREEK TRI,Reach-1,6
Up Type=0
Dn Type=3
Dn Slope=0.005
Boundary for River Rch & Prof#=STEELE CREEK TRI,Reach-1,7
Up Type=0
Dn Type=3
Dn Slope=0.005

--- STEELE CREEK TRIB 19 3.g01 (geometry) ---

Geom Title=Existing Conditions

River Reach=STEELE CREEK TRI,Reach-1
Reach XY= 30
      3525956.45     10466638.03      3525692.99     10466226.64
      3525554.55     10466175.81      3525534.18     10466047.22
      3525622.40     10465986.81      3525615.66     10465882.37
      3525699.31     10465907.95      3525800.72     10465810.97
      3525811.35     10465662.39      3525662.75     10465581.38
      3525625.43     10465428.95      3525518.20     10465513.61
      3525387.23     10465185.57      3525308.09     10465124.37
      3525358.35     10465080.44      3525350.44     10465007.03
      3525471.30     10464978.56      3525509.77     10464927.40
      3525373.47     10464785.69      3525434.38     10464585.37
      3525243.64     10464338.00      3525080.36     10464391.16
      3524988.73     10464198.11      3524972.38     10463967.00
      3525038.55     10463890.33      3525060.15     10463742.32
      3524914.78     10463420.40      3524822.80     10463342.50
      3524920.68     10463281.17      3524922.11     10463241.64

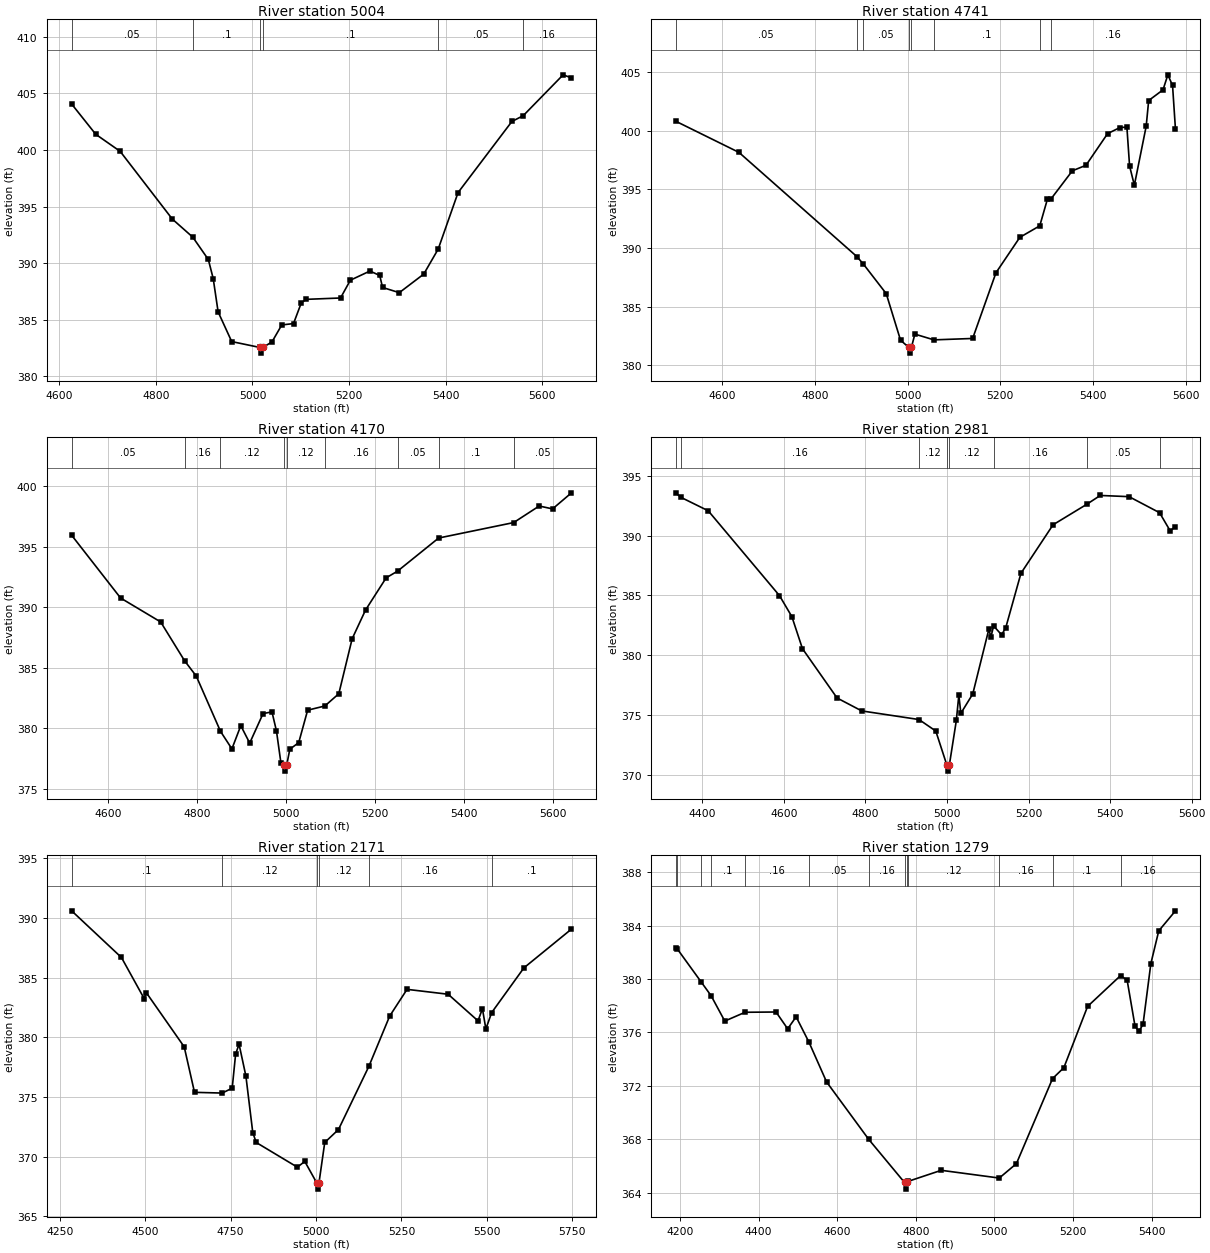
Type RM Length L Ch R = 1,5004,263,263,263
BEGIN DESCRIPTION:
STEELE CREEK TRIB 19.3 10.0
END DESCRIPTION:
XS GIS Cut Line= 2
      3526281.23     10466492.83      3525260.44     10466659.49
#Sta/Elev= 30
  4625.9  404.06  4675.7  401.39  4726.3  399.88  4834.2  393.90  4876.6  392.30
  4908.7  390.33  4918.8  388.65  4929.0  385.70  4957.1  383.08  5015.5  382.56
  5018.3  382.06  5021.5  382.56  5040.4  383.05  5060.7  384.55  5085.0  384.67
  5101.2  386.51  5111.4  386.81  5182.3  386.93  5202.6  388.50  5243.1  389.31
  5263.4  388.92  5269.3  387.86  5303.9  387.40  5354.5  389.04  5384.4  391.25
  5425.5  396.24  5536.9  402.52  5560.3  403.03  5642.9  406.64  5660.2  406.37
#Mann=6,-1,0
  4625.9    0.05       0  4876.6     0.1       0  5015.5    0.07       0
  5021.5     0.1       0  5384.4    0.05       0  5560.3    0.16       0
Bank Sta=5015.5,5021.5
Exp/Cntr=0.3,0.1

Type RM Length L Ch R = 1,4741,571,571,571
BEGIN DESCRIPTION:
STEELE CREEK TRIB 19.3 9.0
END DESCRIPTION:
XS GIS Cut Line= 2
      3526253.47     10466215.05      3525205.96     10466471.72
#Sta/Elev= 30
  4499.6  400.80  4636.2  398.14  4890.6  389.26  4904.7  388.62  4954.0  386.10
  4984.9  382.13  5002.4  381.53  5005.2  381.03  5008.4  381.53  5015.8  382.65
  5057.0  382.16  5140.5  382.28  5190.8  387.88  5242.3  390.90  5285.3  391.88
  5301.8  394.15  5309.1  394.15  5355.6  396.57  5385.0  397.04  5431.7  399.74
  5458.5  400.26  5473.3  400.29  5479.1  396.98  5489.4  395.34  5514.9  400.36
  5520.3  402.56  5551.2  403.47  5561.7  404.75  5571.8  403.85  5578.1  400.11
#Mann=8,-1,0
  4499.6    0.05       0  4890.6     0.1       0  4904.7    0.05       0
  5002.4    0.03       0  5008.4    0.05       0  5057.0     0.1       0
  5285.3    0.05       0  5309.1    0.16       0
Bank Sta=5002.4,5008.4
Exp/Cntr=0.3,0.1

Type RM Length L Ch R = 1,4170,1189,1189,1189
BEGIN DESCRIPTION:
STEELE CREEK TRIB 19.3 8.0
END DESCRIPTION:
XS GIS Cut Line= 2
      3526111.94     10465962.63      3524989.63     10465937.27
#Sta/Elev= 30
  4518.3  395.95  4628.2  390.76  4718.2  388.78  4771.9  385.57  4798.2  384.30
  4852.6  379.73  4878.2  378.28  4898.2  380.20  4918.2  378.76  4948.2  381.20
  4968.2  381.34  4978.3  379.76  4988.3  377.12  4995.3  376.94  4998.0  376.44
  5001.3  376.94  5008.3  378.25  5028.3  378.80  5048.3  381.48  5087.0  381.83
  5118.3  382.84  5148.3  387.39  5178.3  389.76  5224.7  392.43  5250.2  392.98
  5342.5  395.72  5511.1  397.00  5568.4  398.37  5598.4  398.13  5640.9  399.46
#Mann=9,-1,0
  4518.3    0.05       0  4771.9    0.16       0  4852.6    0.12       0
  4995.3    0.07       0  5001.3    0.12       0  5087.0    0.16       0
  5250.2    0.05       0  5342.5     0.1       0  5511.1    0.05       0
Bank Sta=4995.3,5001.3
Exp/Cntr=0.3,0.1

Type RM Length L Ch R = 1,2981,810,810,810
BEGIN DESCRIPTION:
STEELE CREEK TRIB 19.3 6.0
END DESCRIPTION:
XS GIS Cut Line= 2
      3526114.63     10465437.27      3524899.28     10465277.54
#Sta/Elev= 30
  4334.5  393.57  4348.2  393.18  4414.4  392.07  4589.2  384.98  4619.5  383.23
  4645.5  380.55  4730.4  376.43  4790.9  375.35  4931.3  374.63  4972.5  373.67
  4999.7  370.82  5002.5  370.32  5005.7  370.82  5022.9  374.55  5029.0  376.67
  5034.0  375.15  5063.2  376.77  5102.6  382.17  5107.7  381.53  5114.3  382.45
  5133.8  381.71  5143.9  382.28  5181.4  386.85  5260.1  390.90  5342.2  392.60
  5375.9  393.35  5446.5  393.25  5521.3  391.91  5547.4  390.39  5560.3  390.75
#Mann=8,-1,0
  4334.5    0.05       0  4348.2    0.16       0  4931.3    0.12       0
  4999.7    0.07       0  5005.7    0.12       0  5114.3    0.16       0
  5342.2    0.05       0  5521.3     0.1       0
Bank Sta=4999.7,5005.7
Exp/Cntr=0.3,0.1

Type RM Length L Ch R = 1,2171,892,892,892
BEGIN DESCRIPTION:
STEELE CREEK TRIB 19.3 5.0
END DESCRIPTION:
XS GIS Cut Line= 3
      3526052.08     10464944.21      3525795.15     10464777.55
      3524642.33     10464867.83
#Sta/Elev= 30
  4284.8  390.60  4430.5  386.69  4497.1  383.24  4503.1  383.75  4614.2  379.20
  4644.3  375.39  4725.3  375.33  4754.6  375.74  4764.6  378.60  4774.7  379.42
  4794.7  376.75  4814.8  372.02  4824.8  371.19  4945.2  369.12  4967.0  369.60
  5002.4  367.78  5005.1  367.28  5008.4  367.78  5025.4  371.19  5065.5  372.27
  5154.4  377.56  5215.4  381.78  5266.2  384.02  5386.5  383.61  5473.9  381.38
  5486.8  382.40  5496.9  380.70  5513.8  382.07  5608.2  385.82  5747.4  389.07
#Mann=6,-1,0
  4284.8     0.1       0  4725.3    0.12       0  5002.4    0.07       0
  5008.4    0.12       0  5154.4    0.16       0  5513.8     0.1       0
Bank Sta=5002.4,5008.4
Exp/Cntr=0.3,0.1

Type RM Length L Ch R = 1,1279,452,452,452
BEGIN DESCRIPTION:
STEELE CREEK TRIB 19.3 4.0
END DESCRIPTION:
XS GIS Cut Line= 3
      3525802.11     10464381.72      3525531.26     10464221.99
      3524579.89     10464326.15
#Sta/Elev= 30
  4189.2  382.36  4193.5  382.25  4253.7  379.80  4279.4  378.75  4314.2  376.85
  4365.9  377.51  4444.6  377.53  4474.2  376.27  4495.7  377.17  4528.5  375.26
  4573.2  372.29  4680.6  367.98  4771.4  364.76  4774.2  364.26  4777.4  364.76
  4780.4  364.84  4864.9  365.67  5012.5  365.09  5056.1  366.17  5148.0  372.54
  5176.8  373.36  5237.2  377.95  5321.1  380.26  5337.8  379.91  5357.9  376.46
  5367.9  376.09  5378.2  376.61  5398.1  381.16  5418.2  383.61  5460.7  385.11
#Mann=13,-1,0
  4189.2    0.05       0  4193.5     0.1       0  4253.7    0.05       0
  4279.4     0.1       0  4365.9    0.16       0  4528.5    0.05       0
  4680.6    0.16       0  4771.4    0.07       0  4777.4    0.16       0
  4780.4    0.12       0  5012.5    0.16       0  5148.0     0.1       0
  5321.1    0.16       0
Bank Sta=4771.4,4777.4
Exp/Cntr=0.3,0.1

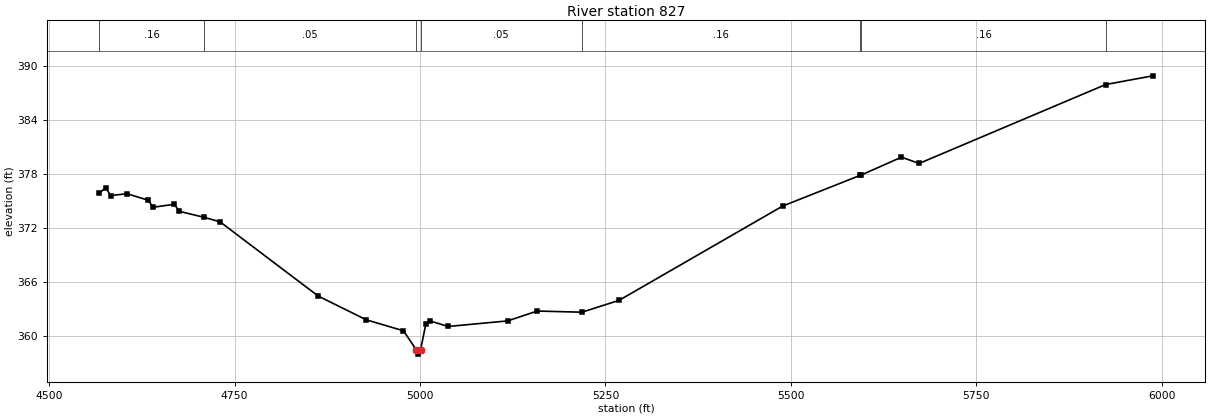
Type RM Length L Ch R = 1,827,0,0,0
BEGIN DESCRIPTION:
STEELE CREEK TRIB 19.3 1.0
END DESCRIPTION:
XS GIS Cut Line= 4
      3525413.17     10463992.79      3525309.03     10463867.82
      3524371.53     10463930.32      3524385.35     10464248.17
#Sta/Elev= 30
  4567.5  375.92  4576.2  376.50  4582.7  375.62  4604.9  375.83  4633.5  375.10
  4640.0  374.32  4668.7  374.65  4675.2  373.87  4709.2  373.19  4730.2  372.70
  4862.6  364.43  4927.5  361.78  4977.6  360.56  4994.7  358.46  4997.4  357.96
  5000.7  358.46  5007.7  361.29  5012.9  361.67  5037.8  361.04  5118.0  361.66
  5158.0  362.76  5218.3  362.63  5268.3  363.95  5488.8  374.45  5593.0  377.86
  5595.1  377.92  5649.1  379.90  5672.9  379.20  5924.4  387.99  5987.9  388.96
#Mann=8,-1,0
  4567.5    0.16       0  4709.2    0.05       0  4994.7   0.035       0
  5000.7    0.05       0  5218.3    0.16       0  5593.0    0.05       0
  5595.1    0.16       0  5924.4    0.05       0
Bank Sta=4994.7,5000.7
Exp/Cntr=0.3,0.1

Chan Stop Cuts=-1