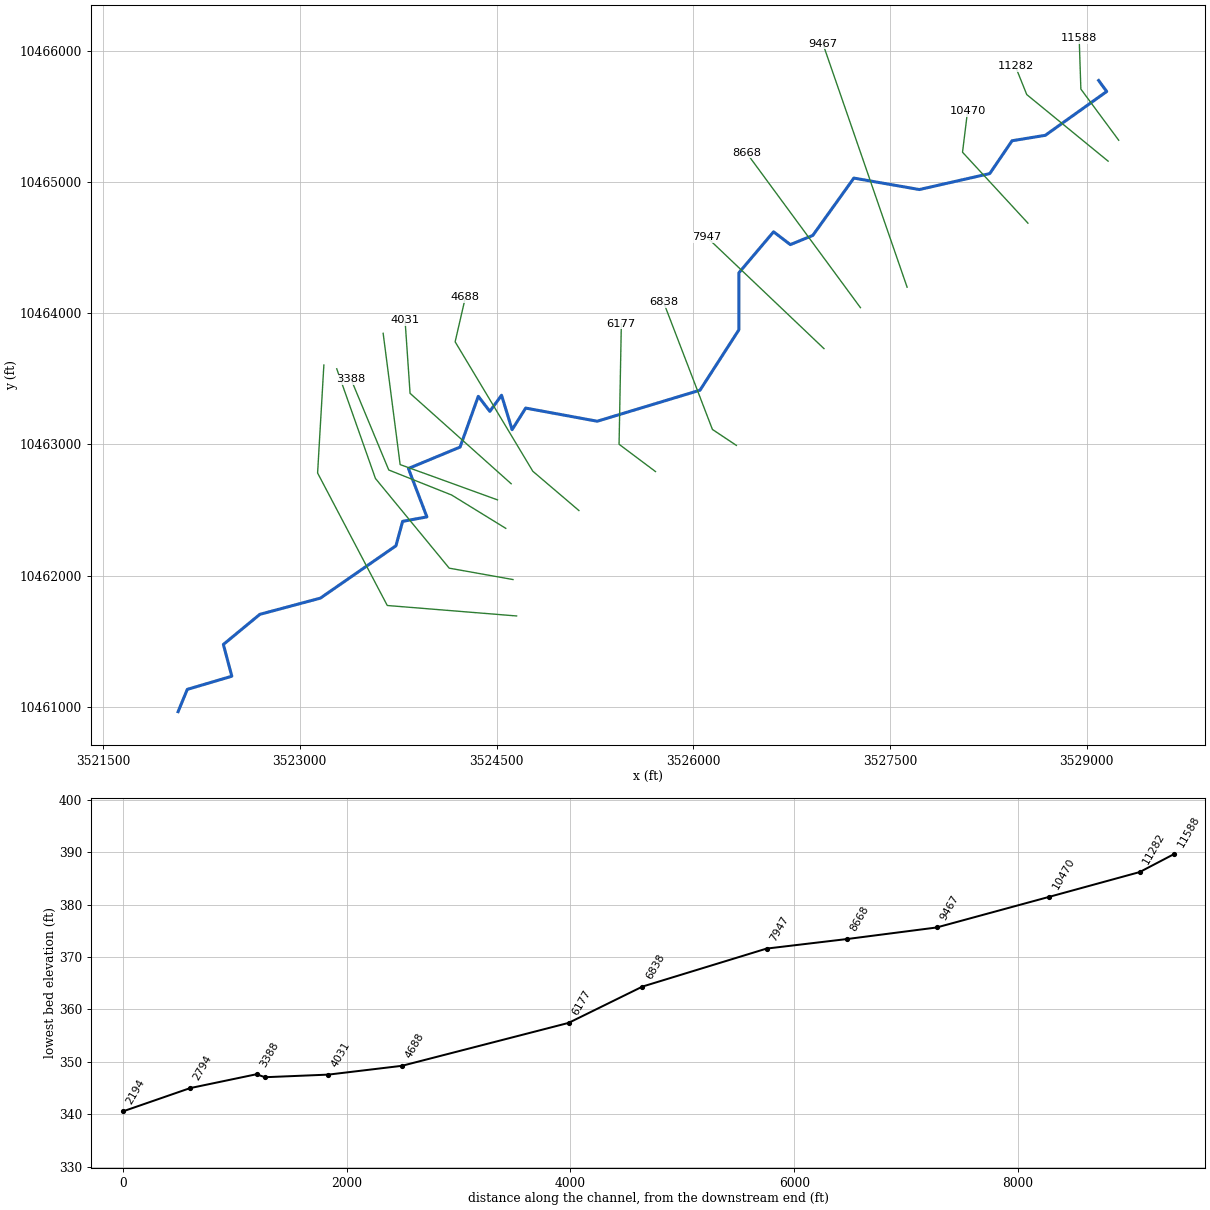
--- STEELE CREEK TRIB 19.prj (project) ---

Proj Title=STEELE CREEK TRIB 19 Base Level Engineering
Current Plan=p01
Default Exp/Contr=0.3,0.1
English Units
Geom File=g01
Flow File=f01
Plan File=p01
BEGIN DESCRIPTION:
STEELE CREEK TRIB 19
END DESCRIPTION:

--- STEELE CREEK TRIB 19.p01 (plan) ---

Plan Title=Multiple Run
Short Identifier=Multiple
Geom File=g01
Flow File=f01
Subcritical Flow
K Sum by GR= 0
Std Step Tol= 0.01
Critical Tol= 0.01
Num of Std Step Trials= 20
Max Error Tol= 0.3
Flow Tol Ratio= 0.001
Split Flow NTrial= 30
Split Flow Tol= 0.02
Split Flow Ratio= 0.02
Log Output Level= 0
Friction Slope Method= 1
Unsteady Friction Slope Method= 2
Unsteady Bridges Friction Slope Method= 1
Parabolic Critical Depth
Global Vel Dist=  1 , 1 , 1
Global Log Level= 0
CheckData=True
Encroach Param= -1, 0, 0, 0
BEGIN DESCRIPTION:
Multiple Run
END DESCRIPTION:

--- STEELE CREEK TRIB 19.f01 (steady flow) ---

Flow Title=Multiple
Number of Profiles=7
Profile Names=10-year,25-year,50-year,1pct_min,100-year,1pct_plu,500-year
River Rch & RM= STEELE CREEK TRI,Reach-1,11588
     730     985    1192    1054    1425    1927    2030
River Rch & RM= STEELE CREEK TRI,Reach-1,4688
    1130    1560    1915    1715    2319    3137    3392
Boundary for River Rch & Prof#=STEELE CREEK TRI,Reach-1,1
Up Type=0
Dn Type=3
Dn Slope=0.005
Boundary for River Rch & Prof#=STEELE CREEK TRI,Reach-1,2
Up Type=0
Dn Type=3
Dn Slope=0.005
Boundary for River Rch & Prof#=STEELE CREEK TRI,Reach-1,3
Up Type=0
Dn Type=3
Dn Slope=0.005
Boundary for River Rch & Prof#=STEELE CREEK TRI,Reach-1,4
Up Type=0
Dn Type=3
Dn Slope=0.005
Boundary for River Rch & Prof#=STEELE CREEK TRI,Reach-1,5
Up Type=0
Dn Type=3
Dn Slope=0.005
Boundary for River Rch & Prof#=STEELE CREEK TRI,Reach-1,6
Up Type=0
Dn Type=3
Dn Slope=0.005
Boundary for River Rch & Prof#=STEELE CREEK TRI,Reach-1,7
Up Type=0
Dn Type=3
Dn Slope=0.005

--- STEELE CREEK TRIB 19.g01 (geometry) ---

Geom Title=Existing Conditions

River Reach=STEELE CREEK TRI,Reach-1
Reach XY= 30
      3529091.16     10465775.36      3529152.60     10465691.63
      3528684.69     10465357.45      3528430.92     10465315.84
      3528260.92     10465065.53      3527723.95     10464943.75
      3527224.61     10465031.08      3526911.37     10464593.72
      3526740.32     10464523.77      3526612.46     10464621.36
      3526347.79     10464308.47      3526347.65     10463873.40
      3526051.60     10463413.58      3525267.90     10463176.68
      3524722.31     10463277.03      3524618.75     10463112.17
      3524538.47     10463375.04      3524449.01     10463252.05
      3524360.96     10463366.80      3524222.07     10462979.64
      3523828.08     10462816.28      3523969.18     10462447.18
      3523784.10     10462413.16      3523733.07     10462226.70
      3523156.68     10461827.39      3522695.46     10461704.00
      3522417.28     10461474.22      3522481.78     10461231.88
      3522142.11     10461131.64      3522072.11     10460961.64

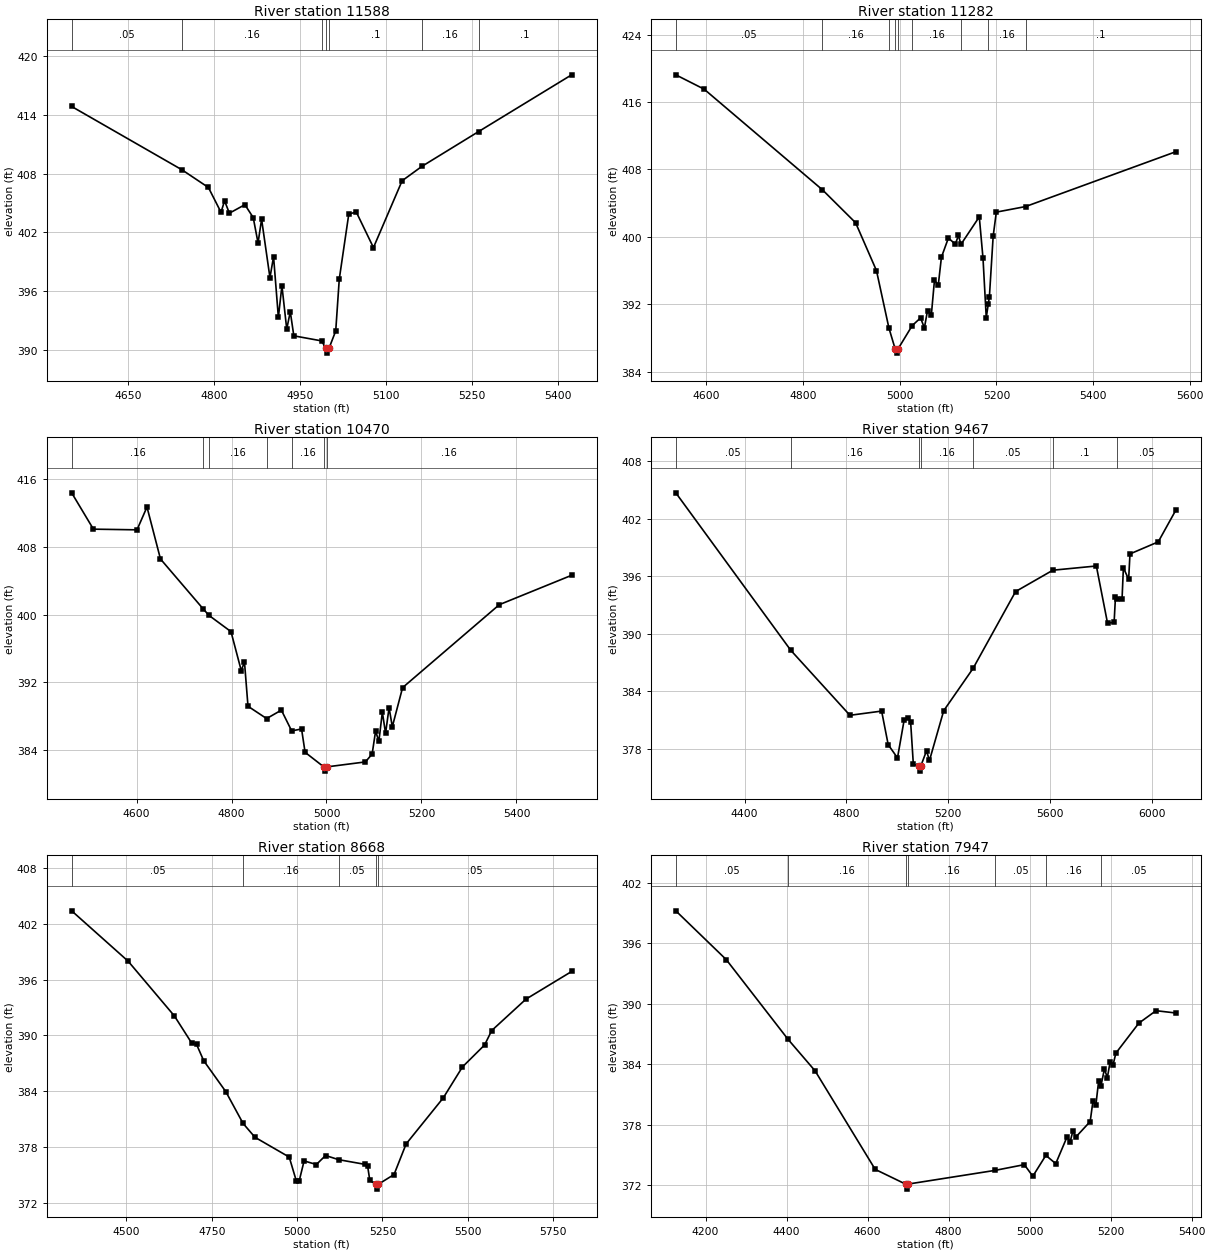
Type RM Length L Ch R = 1,11588,306,306,306
BEGIN DESCRIPTION:
STEELE CREEK TRIB 19 19.0
END DESCRIPTION:
XS GIS Cut Line= 3
      3529244.20     10465319.57      3528955.55     10465709.86
      3528942.56     10466097.61
#Sta/Elev= 30
  4551.2  414.88  4743.9  408.40  4790.1  406.59  4812.1  404.05  4818.3  405.23
  4826.7  403.96  4853.8  404.83  4868.4  403.51  4876.8  400.91  4883.0  403.34
  4897.6  397.36  4903.9  399.52  4912.3  393.30  4918.5  396.54  4926.9  392.10
  4933.1  393.88  4939.3  391.41  4988.1  390.89  4994.8  390.14  4997.6  389.64
  5000.8  390.14  5012.5  391.91  5018.7  397.22  5035.3  403.87  5048.4  404.08
  5078.4  400.44  5128.5  407.28  5163.0  408.75  5262.3  412.32  5424.6  418.12
#Mann=7,-1,0
  4551.2    0.05       0  4743.9    0.16       0  4988.1     0.1       0
  4994.8    0.07       0  5000.8     0.1       0  5163.0    0.16       0
  5262.3     0.1       0
Bank Sta=4994.8,5000.8
Exp/Cntr=0.3,0.1

Type RM Length L Ch R = 1,11282,812,812,812
BEGIN DESCRIPTION:
STEELE CREEK TRIB 19 18.0
END DESCRIPTION:
XS GIS Cut Line= 3
      3529163.19     10465160.30      3528542.83     10465668.15
      3528456.76     10465882.61
#Sta/Elev= 30
  4537.7  419.22  4596.2  417.52  4840.7  405.58  4909.1  401.68  4952.2  396.01
  4977.9  389.21  4990.8  386.72  4993.6  386.22  4996.8  386.72  5026.0  389.48
  5043.3  390.40  5051.2  389.21  5057.7  391.27  5065.6  390.77  5072.0  394.85
  5079.9  394.29  5086.4  397.59  5100.8  399.87  5115.1  399.14  5121.6  400.18
  5126.7  399.11  5164.6  402.38  5172.3  397.47  5179.0  390.44  5183.2  392.04
  5185.5  392.92  5193.3  400.10  5199.8  402.94  5260.3  403.60  5570.5  410.10
#Mann=9,-1,0
  4537.7    0.05       0  4840.7    0.16       0  4977.9     0.1       0
  4990.8    0.07       0  4996.8     0.1       0  5026.0    0.16       0
  5126.7     0.1       0  5183.2    0.16       0  5260.3     0.1       0
Bank Sta=4990.8,4996.8
Exp/Cntr=0.3,0.1

Type RM Length L Ch R = 1,10470,1003,1003,1003
BEGIN DESCRIPTION:
STEELE CREEK TRIB 19 16.0
END DESCRIPTION:
XS GIS Cut Line= 3
      3528552.08     10464687.28      3528053.13     10465228.43
      3528091.84     10465542.80
#Sta/Elev= 30
  4463.4  414.41  4509.2  410.11  4601.0  410.03  4622.0  412.73  4650.4  406.58
  4740.2  400.68  4752.6  399.90  4798.9  397.98  4820.5  393.37  4827.3  394.39
  4834.7  389.15  4873.9  387.69  4905.0  388.69  4926.7  386.23  4947.5  386.46
  4954.9  383.70  4994.4  381.97  4997.2  381.47  5000.4  381.97  5081.9  382.56
  5096.1  383.49  5103.4  386.21  5110.3  384.99  5117.6  388.45  5124.4  385.95
  5131.8  388.98  5138.6  386.72  5160.2  391.35  5363.9  401.17  5516.2  404.65
#Mann=7,-1,0
  4463.4    0.16       0  4740.2    0.05       0  4752.6    0.16       0
  4873.9    0.05       0  4926.7    0.16       0  4994.4    0.07       0
  5000.4    0.16       0
Bank Sta=4994.4,5000.4
Exp/Cntr=0.3,0.1

Type RM Length L Ch R = 1,9467,799,799,799
BEGIN DESCRIPTION:
STEELE CREEK TRIB 19 14.0
END DESCRIPTION:
XS GIS Cut Line= 2
      3527630.58     10464199.15      3526988.24     10466056.73
#Sta/Elev= 30
  4129.4  404.70  4581.3  388.26  4813.9  381.47  4938.5  381.91  4964.4  378.40
  5000.9  377.02  5026.8  380.94  5042.0  381.23  5052.6  380.75  5063.2  376.36
  5086.1  376.14  5088.9  375.64  5092.1  376.14  5115.0  377.76  5126.6  376.75
  5182.6  381.95  5298.1  386.37  5465.2  394.39  5611.7  396.62  5782.7  397.06
  5826.6  391.10  5852.5  391.17  5857.8  393.81  5865.0  393.64  5883.7  393.61
  5889.0  396.88  5909.6  395.66  5914.9  398.32  6026.0  399.58  6094.9  402.88
#Mann=7,-1,0
  4129.4    0.05       0  4581.3    0.16       0  5086.1    0.07       0
  5092.1    0.16       0  5298.1    0.05       0  5611.7     0.1       0
  5865.0    0.05       0
Bank Sta=5086.1,5092.1
Exp/Cntr=0.3,0.1

Type RM Length L Ch R = 1,8668,721,721,721
BEGIN DESCRIPTION:
STEELE CREEK TRIB 19 12.0
END DESCRIPTION:
XS GIS Cut Line= 2
      3527274.68     10464042.91      3526406.83     10465223.18
#Sta/Elev= 30
  4339.4  403.40  4504.8  397.98  4640.5  392.08  4690.7  389.19  4705.3  389.03
  4726.2  387.27  4791.0  383.94  4841.7  380.51  4876.6  379.02  4976.9  376.89
  4997.8  374.31  5006.2  374.34  5020.5  376.48  5056.4  376.09  5083.4  377.06
  5121.9  376.61  5198.4  376.11  5206.7  375.90  5213.0  374.39  5230.9  373.94
  5233.6  373.44  5236.9  373.94  5284.0  375.01  5319.5  378.31  5428.2  383.26
  5484.6  386.60  5549.4  388.96  5570.2  390.51  5670.5  393.89  5804.4  396.87
#Mann=5,-1,0
  4339.4    0.05       0  4841.7    0.16       0  5121.9    0.05       0
  5230.9    0.07       0  5236.9    0.05       0
Bank Sta=5230.9,5236.9
Exp/Cntr=0.3,0.1

Type RM Length L Ch R = 1,7947,1109,1109,1109
BEGIN DESCRIPTION:
STEELE CREEK TRIB 19 11.0
END DESCRIPTION:
XS GIS Cut Line= 2
      3526996.91     10463730.41      3526102.76     10464581.15
#Sta/Elev= 30
  4126.6  399.23  4251.1  394.39  4403.8  386.47  4470.4  383.35  4618.8  373.57
  4693.8  372.11  4696.6  371.61  4699.8  372.11  4914.6  373.47  4986.9  374.04
  5007.9  372.89  5040.1  374.96  5064.5  374.14  5092.8  376.83  5099.7  376.26
  5107.0  377.40  5113.9  376.77  5149.5  378.32  5156.4  380.35  5163.6  379.97
  5170.5  382.38  5176.1  381.87  5184.7  383.53  5191.9  382.68  5198.8  384.25
  5206.1  383.96  5213.0  385.11  5269.6  388.08  5312.1  389.32  5360.8  389.09
#Mann=7,-1,0
  4126.6    0.05       0  4403.8    0.16       0  4693.8    0.03       0
  4699.8    0.16       0  4914.6    0.05       0  5040.1    0.16       0
  5176.1    0.05       0
Bank Sta=4693.8,4699.8
Exp/Cntr=0.3,0.1

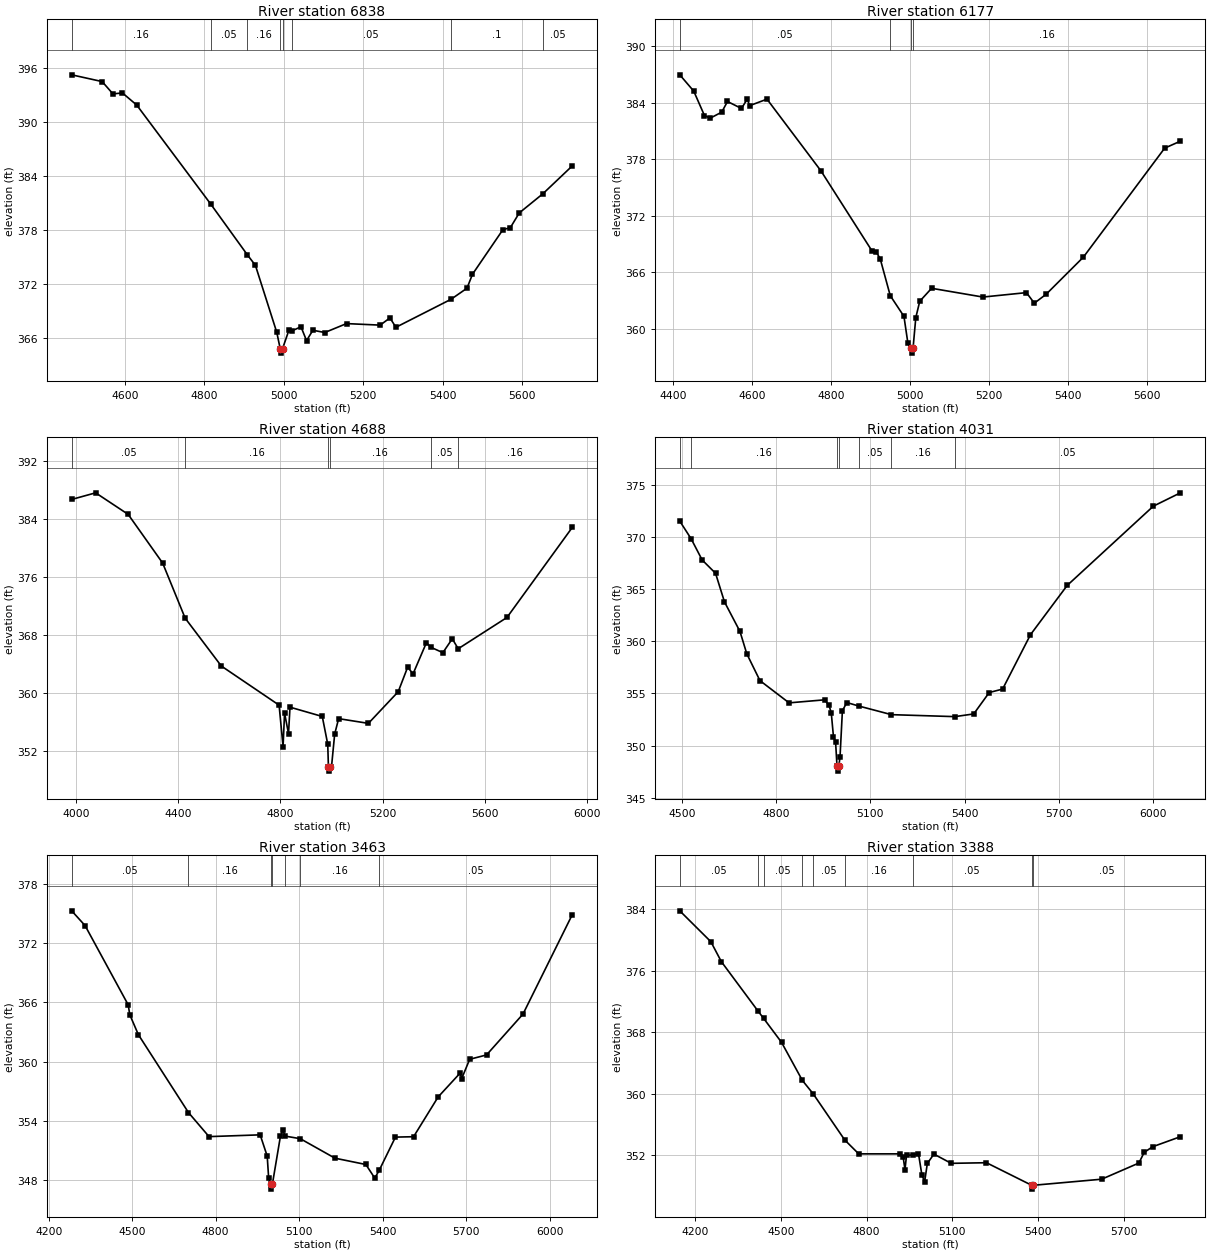
Type RM Length L Ch R = 1,6838,661,661,661
BEGIN DESCRIPTION:
STEELE CREEK TRIB 19 9.0
END DESCRIPTION:
XS GIS Cut Line= 3
      3526328.53     10462992.55      3526146.19     10463114.11
      3525772.91     10464086.37
#Sta/Elev= 30
  4465.8  395.27  4542.5  394.52  4569.7  393.15  4593.5  393.26  4629.6  391.91
  4816.3  380.89  4907.6  375.31  4928.4  374.11  4982.2  366.67  4990.8  364.86
  4993.5  364.36  4996.8  364.86  5013.1  366.95  5019.5  366.81  5043.1  367.29
  5057.2  365.75  5073.1  366.90  5103.2  366.65  5157.8  367.64  5242.5  367.47
  5267.2  368.27  5282.2  367.23  5421.0  370.34  5461.2  371.57  5475.0  373.12
  5551.3  378.05  5570.6  378.31  5592.8  379.93  5652.3  382.06  5726.4  385.16
#Mann=8,-1,0
  4465.8    0.16       0  4816.3    0.05       0  4907.6    0.16       0
  4990.8    0.07       0  4996.8    0.16       0  5019.5    0.05       0
  5421.0     0.1       0  5652.3    0.05       0
Bank Sta=4990.8,4996.8
Exp/Cntr=0.3,0.1

Type RM Length L Ch R = 1,6177,1489,1489,1489
BEGIN DESCRIPTION:
STEELE CREEK TRIB 19 7.0
END DESCRIPTION:
XS GIS Cut Line= 3
      3525712.13     10462792.95      3525434.39     10463001.26
      3525451.75     10463921.42
#Sta/Elev= 30
  4416.9  386.95  4452.3  385.22  4479.4  382.63  4493.9  382.35  4523.1  382.99
  4537.7  384.12  4573.1  383.38  4587.7  384.37  4593.9  383.68  4637.7  384.37
  4774.5  376.75  4903.8  368.25  4914.5  368.15  4924.5  367.41  4949.8  363.52
  4984.5  361.32  4994.5  358.47  5001.5  357.92  5004.3  357.42  5007.5  357.92
  5014.5  361.19  5024.5  362.92  5054.5  364.30  5184.5  363.37  5294.6  363.84
  5314.6  362.72  5344.6  363.67  5438.9  367.61  5644.6  379.17  5684.4  379.91
#Mann=4,-1,0
  4416.9    0.05       0  4949.8    0.16       0  5001.5    0.07       0
  5007.5    0.16       0
Bank Sta=5001.5,5007.5
Exp/Cntr=0.3,0.1

Type RM Length L Ch R = 1,4688,657,657,657
BEGIN DESCRIPTION:
STEELE CREEK TRIB 19 6.0
END DESCRIPTION:
XS GIS Cut Line= 4
      3525128.37     10462495.64      3524776.84     10462795.10
      3524184.39     10463782.51      3524262.50     10464121.01
#Sta/Elev= 30
  3982.6  386.66  4076.4  387.57  4203.8  384.60  4338.9  377.89  4427.0  370.30
  4568.6  363.71  4794.9  358.32  4810.4  352.62  4816.3  357.22  4831.8  354.40
  4837.6  358.04  4964.0  356.76  4985.4  352.94  4988.2  349.73  4990.9  349.23
  4994.2  349.73  5000.1  349.80  5012.6  354.34  5028.1  356.46  5144.7  355.81
  5261.4  360.17  5298.3  363.54  5319.7  362.64  5372.1  366.94  5388.2  366.31
  5436.3  365.55  5473.2  367.46  5496.4  366.09  5687.4  370.40  5943.3  382.81
#Mann=6,-1,0
  3982.6    0.05       0  4427.0    0.16       0  4988.2    0.07       0
  4994.2    0.16       0  5388.2    0.05       0  5496.4    0.16       0
Bank Sta=4988.2,4994.2
Exp/Cntr=0.3,0.1

Type RM Length L Ch R = 1,4031,568,568,568
BEGIN DESCRIPTION:
Mapping XS d69fe856
END DESCRIPTION:
XS GIS Cut Line= 3
      3524611.49     10462700.29      3523840.92     10463389.44
      3523802.47     10463947.64
#Sta/Elev= 30
  4493.5  371.50  4529.8  369.80  4564.7  367.78  4607.4  366.50  4635.8  363.76
  4685.1  360.93  4706.8  358.79  4748.7  356.22  4841.4  354.09  4954.3  354.38
  4968.5  353.85  4975.6  353.15  4982.7  350.83  4989.4  350.34  4993.9  348.05
  4996.7  347.55  4999.9  348.05  5003.6  348.95  5011.1  353.34  5025.3  354.12
  5062.7  353.79  5167.2  352.96  5369.2  352.77  5429.1  353.03  5478.4  355.08
  5521.0  355.41  5609.7  360.62  5726.6  365.34  6000.6  372.93  6086.8  374.21
#Mann=7,-1,0
  4493.5    0.05       0  4529.8    0.16       0  4993.9    0.07       0
  4999.9    0.16       0  5062.7    0.05       0  5167.2    0.16       0
  5369.2    0.05       0
Bank Sta=4993.9,4999.9
Exp/Cntr=0.3,0.1

Type RM Length L Ch R = 1,3463,75,75,75
BEGIN DESCRIPTION:
Mapping XS 991ceede
END DESCRIPTION:
XS GIS Cut Line= 3
      3524507.31     10462577.06      3523765.15     10462846.15
      3523635.57     10463847.36
#Sta/Elev= 30
  4282.6  375.30  4330.7  373.80  4485.8  365.75  4491.1  364.77  4522.2  362.73
  4702.3  354.82  4776.1  352.38  4959.9  352.56  4985.2  350.40  4990.5  348.13
  4997.8  347.55  5000.6  347.05  5003.8  347.55  5032.7  352.42  5041.1  353.04
  5050.1  352.43  5104.0  352.17  5228.8  350.19  5339.7  349.55  5371.7  348.17
  5387.5  348.95  5446.0  352.33  5511.2  352.37  5599.5  356.41  5678.8  358.84
  5683.9  358.26  5712.8  360.23  5773.3  360.67  5904.4  364.82  6081.6  374.92
#Mann=7,-1,0
  4282.6    0.05       0  4702.3    0.16       0  4997.8    0.07       0
  5003.8    0.16       0  5050.1    0.05       0  5104.0    0.16       0
  5387.5    0.05       0
Bank Sta=4997.8,5003.8
Exp/Cntr=0.3,0.1

Type RM Length L Ch R = 1,3388,594,594,594
BEGIN DESCRIPTION:
Mapping XS 0bd27f1f
END DESCRIPTION:
XS GIS Cut Line= 4
      3524570.26     10462360.04      3524157.94     10462613.94
      3523678.34     10462804.92      3523390.28     10463497.99
#Sta/Elev= 30
  4146.8  383.77  4255.5  379.76  4292.2  377.17  4420.9  370.73  4440.3  369.79
  4502.7  366.69  4575.6  361.74  4613.2  360.01  4723.7  354.01  4772.7  352.20
  4917.2  352.20  4927.9  351.84  4934.5  350.16  4939.9  352.00  4962.2  352.06
  4981.7  352.24  4993.8  349.43  5003.3  348.60  5012.7  350.95  5035.6  352.17
  5096.3  350.97  5219.5  351.05  5377.8  348.12  5380.5  347.62  5383.8  348.12
  5622.5  348.91  5752.7  351.01  5771.1  352.39  5800.4  353.12  5897.8  354.43
#Mann=9,-1,0
  4146.8    0.05       0  4420.9     0.1       0  4440.3    0.05       0
  4575.6     0.1       0  4613.2    0.05       0  4723.7    0.16       0
  4962.2    0.05       0  5377.8    0.03       0  5383.8    0.05       0
Bank Sta=5377.8,5383.8
Exp/Cntr=0.3,0.1

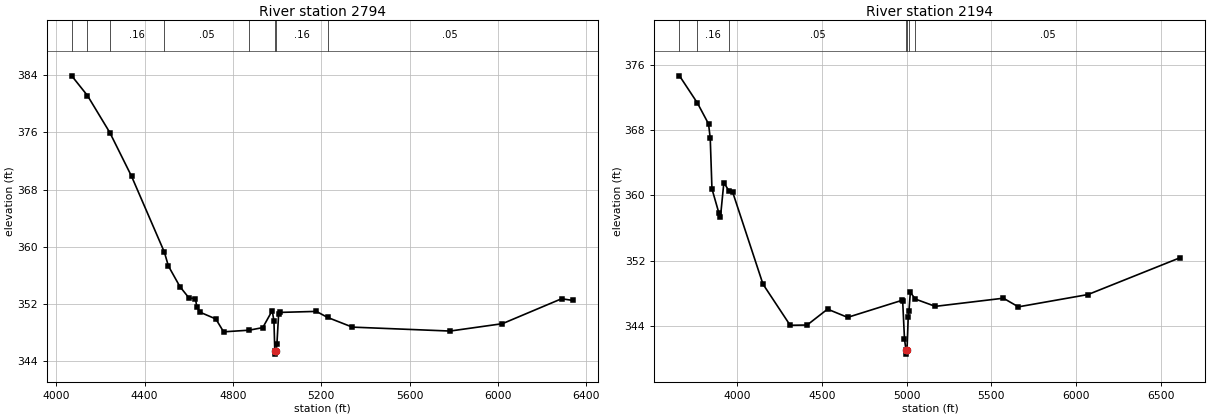
Type RM Length L Ch R = 1,2794,600,600,600
BEGIN DESCRIPTION:
Mapping XS 4a38fb60
END DESCRIPTION:
XS GIS Cut Line= 4
      3524625.37     10461969.36      3524139.22     10462056.17
      3523576.72     10462740.20      3523281.64     10463576.83
#Sta/Elev= 30
  4070.5  383.92  4141.7  381.16  4242.9  375.98  4341.3  369.86  4490.1  359.22
  4507.8  357.32  4560.3  354.41  4601.5  352.82  4630.2  352.75  4636.6  351.61
  4651.0  350.84  4722.7  349.89  4757.9  348.09  4873.2  348.32  4935.1  348.68
  4978.1  351.07  4985.7  349.56  4989.5  345.47  4992.2  344.97  4995.5  345.47
  4999.0  346.35  5006.8  350.52  5013.3  350.81  5177.6  350.95  5228.1  350.11
  5340.5  348.75  5782.5  348.20  6019.4  349.23  6287.2  352.72  6337.1  352.49
#Mann=8,-1,0
  4070.5    0.05       0  4141.7     0.1       0  4242.9    0.16       0
  4490.1    0.05       0  4873.2    0.16       0  4989.5    0.07       0
  4995.5    0.16       0  5228.1    0.05       0
Bank Sta=4989.5,4995.5
Exp/Cntr=0.3,0.1

Type RM Length L Ch R = 1,2194,0,0,0
BEGIN DESCRIPTION:
STEELE CREEK TRIB 19 1.0
END DESCRIPTION:
XS GIS Cut Line= 4
      3524653.08     10461691.59      3523666.99     10461771.45
      3523135.74     10462781.86      3523183.55     10463605.70
#Sta/Elev= 30
  3659.8  374.67  3765.7  371.33  3831.3  368.77  3841.3  366.99  3851.4  360.81
  3891.5  357.89  3901.6  357.35  3921.6  361.57  3953.4  360.50  3973.5  360.41
  4152.4  349.12  4312.9  344.07  4413.2  344.10  4533.6  346.05  4652.1  345.04
  4971.3  347.12  4977.0  347.04  4987.7  342.38  4996.6  341.03  4999.3  340.53
  5002.6  341.03  5009.7  345.06  5014.3  345.88  5022.2  348.10  5052.2  347.28
  5169.6  346.39  5571.5  347.39  5659.7  346.33  6070.9  347.84  6615.9  352.37
#Mann=7,-1,0
  3659.8    0.05       0  3765.7    0.16       0  3953.4    0.05       0
  4996.6    0.03       0  5002.6    0.05       0  5014.3    0.12       0
  5052.2    0.05       0
Bank Sta=4996.6,5002.6
Exp/Cntr=0.3,0.1

Chan Stop Cuts=-1