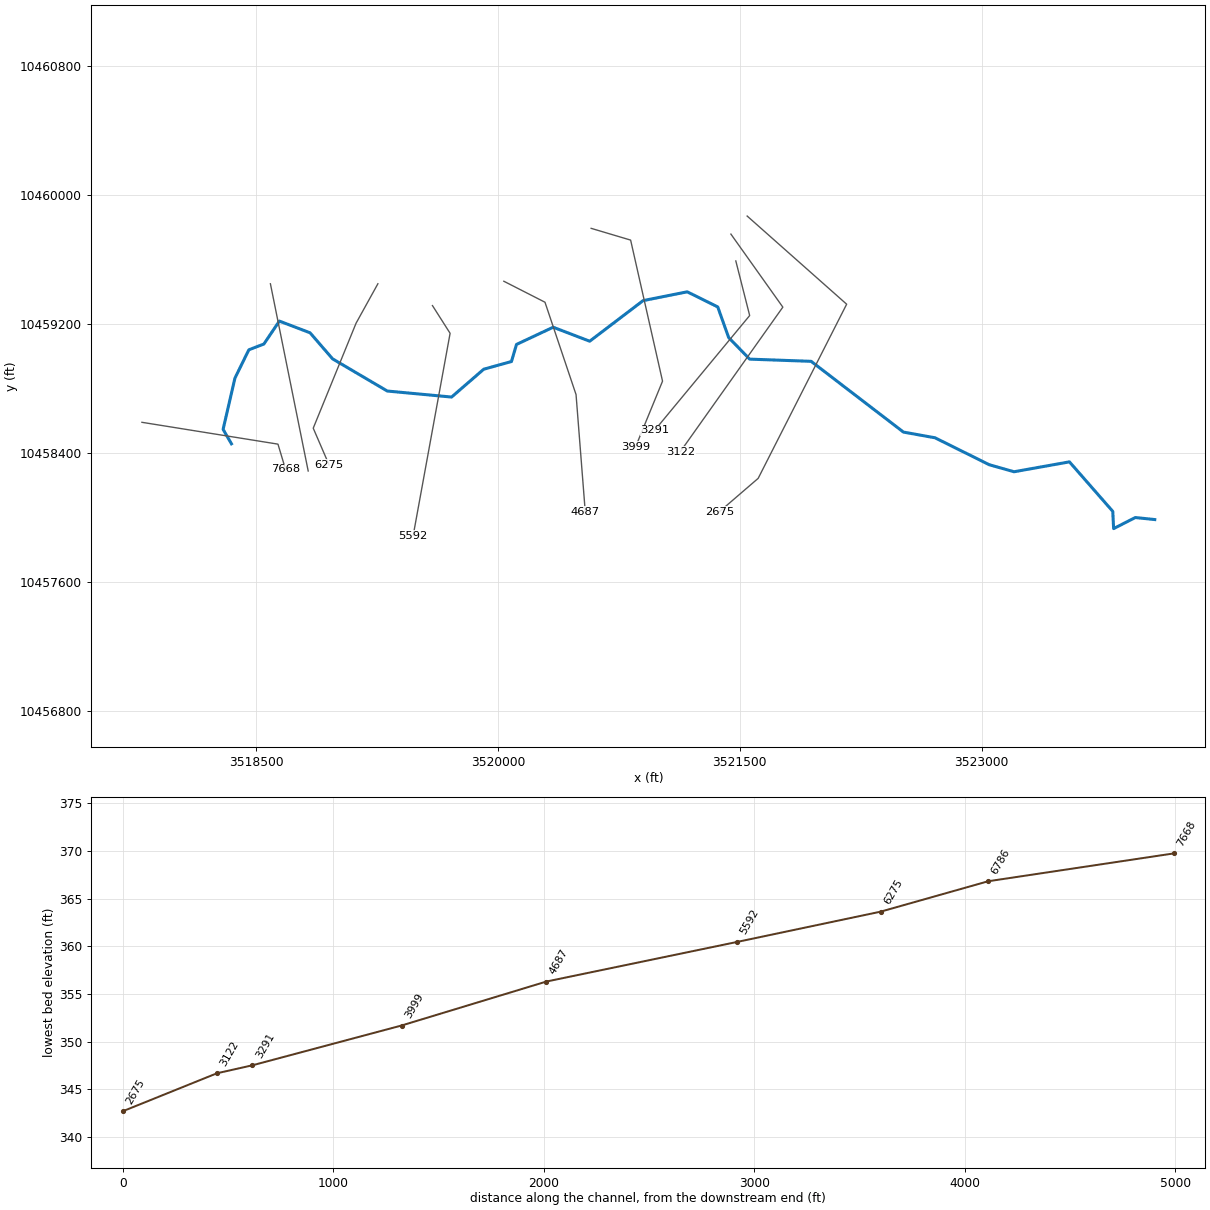
--- STEELE CREEK TRIB 20.prj (project) ---

Proj Title=STEELE CREEK TRIB 20 Base Level Engineering
Current Plan=p01
Default Exp/Contr=0.3,0.1
English Units
Geom File=g01
Flow File=f01
Plan File=p01
BEGIN DESCRIPTION:
STEELE CREEK TRIB 20
END DESCRIPTION:

--- STEELE CREEK TRIB 20.p01 (plan) ---

Plan Title=Multiple Run
Short Identifier=Multiple
Geom File=g01
Flow File=f01
Subcritical Flow
K Sum by GR= 0
Std Step Tol= 0.01
Critical Tol= 0.01
Num of Std Step Trials= 20
Max Error Tol= 0.3
Flow Tol Ratio= 0.001
Split Flow NTrial= 30
Split Flow Tol= 0.02
Split Flow Ratio= 0.02
Log Output Level= 0
Friction Slope Method= 1
Unsteady Friction Slope Method= 2
Unsteady Bridges Friction Slope Method= 1
Parabolic Critical Depth
Global Vel Dist=  1 , 1 , 1
Global Log Level= 0
CheckData=True
Encroach Param= -1, 0, 0, 0
BEGIN DESCRIPTION:
Multiple Run
END DESCRIPTION:

--- STEELE CREEK TRIB 20.f01 (steady flow) ---

Flow Title=Multiple
Number of Profiles=7
Profile Names=10-year,25-year,50-year,1pct_min,100-year,1pct_plu,500-year
River Rch & RM= STEELE CREEK TRI,Reach-1,7668
    1015    1397    1712    1530    2069    2799    3017
Boundary for River Rch & Prof#=STEELE CREEK TRI,Reach-1,1
Up Type=0
Dn Type=3
Dn Slope=0.005
Boundary for River Rch & Prof#=STEELE CREEK TRI,Reach-1,2
Up Type=0
Dn Type=3
Dn Slope=0.005
Boundary for River Rch & Prof#=STEELE CREEK TRI,Reach-1,3
Up Type=0
Dn Type=3
Dn Slope=0.005
Boundary for River Rch & Prof#=STEELE CREEK TRI,Reach-1,4
Up Type=0
Dn Type=3
Dn Slope=0.005
Boundary for River Rch & Prof#=STEELE CREEK TRI,Reach-1,5
Up Type=0
Dn Type=3
Dn Slope=0.005
Boundary for River Rch & Prof#=STEELE CREEK TRI,Reach-1,6
Up Type=0
Dn Type=3
Dn Slope=0.005
Boundary for River Rch & Prof#=STEELE CREEK TRI,Reach-1,7
Up Type=0
Dn Type=3
Dn Slope=0.005

--- STEELE CREEK TRIB 20.g01 (geometry) ---

Geom Title=Existing Conditions

River Reach=STEELE CREEK TRI,Reach-1
Reach XY= 30
      3518346.83     10458457.39      3518294.99     10458546.92
      3518368.42     10458864.45      3518454.62     10459040.23
      3518548.12     10459076.33      3518643.96     10459218.55
      3518834.36     10459145.88      3518974.02     10458984.35
      3519313.39     10458784.66      3519712.26     10458747.32
      3519911.86     10458920.02      3520083.73     10458967.77
      3520114.98     10459073.67      3520342.41     10459180.44
      3520568.98     10459093.63      3520900.04     10459345.39
      3521174.01     10459400.06      3521363.25     10459306.31
      3521430.96     10459116.20      3521561.16     10458982.52
      3521942.67     10458968.85      3522515.15     10458529.99
      3522710.90     10458494.68      3523047.28     10458327.58
      3523201.20     10458283.99      3523544.86     10458345.27
      3523813.51     10458038.22      3523818.78     10457931.23
      3523953.05     10457999.98      3524074.04     10457987.44

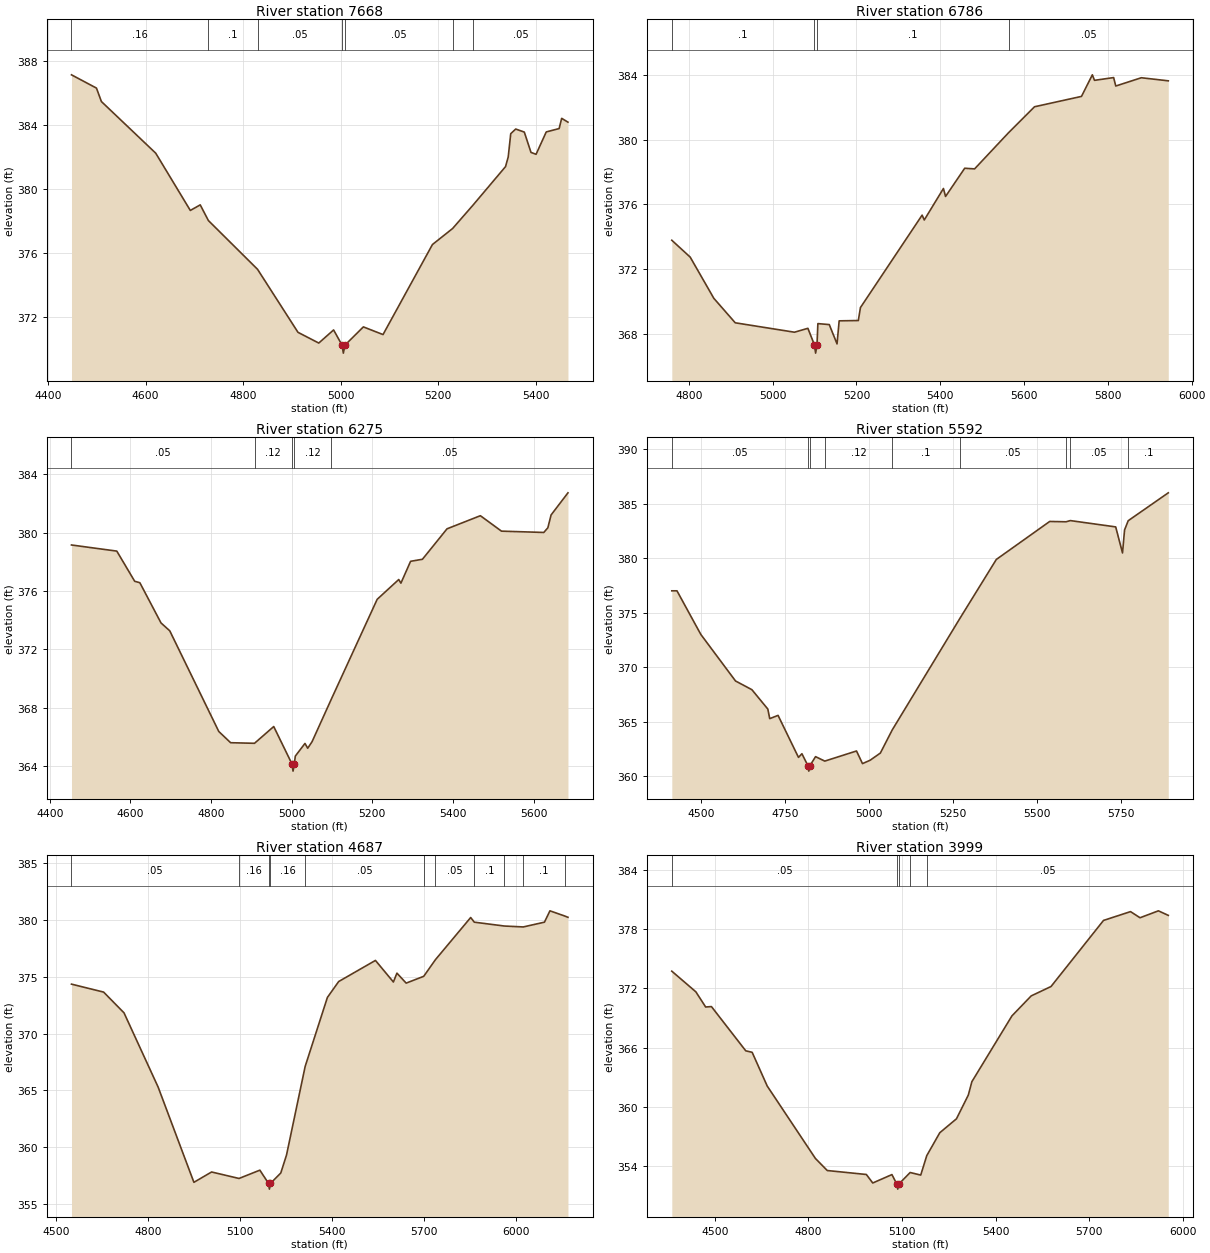
Type RM Length L Ch R = 1,7668,882,882,882
BEGIN DESCRIPTION:
STEELE CREEK TRIB 20 15.0
END DESCRIPTION:
XS GIS Cut Line= 3
      3517791.56     10458590.67      3518635.36     10458455.24
      3518682.22     10458299.01
#Sta/Elev= 30
  4448.2  387.15  4499.4  386.32  4509.5  385.48  4620.9  382.25  4691.8  378.67
  4712.1  379.02  4728.8  378.04  4829.6  374.99  4912.5  371.05  4955.1  370.38
  4985.5  371.20  5002.8  370.25  5005.5  369.75  5008.8  370.25  5046.5  371.39
  5086.8  370.91  5188.1  376.54  5229.4  377.54  5270.6  378.98  5337.9  381.41
  5343.4  382.01  5348.6  383.47  5358.8  383.76  5376.4  383.57  5390.1  382.30
  5400.5  382.18  5421.4  383.58  5447.8  383.79  5453.0  384.43  5465.9  384.19
#Mann=7,-1,0
  4448.2    0.16       0  4728.8     0.1       0  4829.6    0.05       0
  5002.8    0.03       0  5008.8    0.05       0  5229.4     0.1       0
  5270.6    0.05       0
Bank Sta=5002.8,5008.8
Exp/Cntr=0.3,0.1

Type RM Length L Ch R = 1,6786,511,511,511
BEGIN DESCRIPTION:
STEELE CREEK TRIB 20 14.0
END DESCRIPTION:
XS GIS Cut Line= 2
      3518588.49     10459450.00      3518822.85     10458288.62
#Sta/Elev= 30
  4759.4  373.79  4803.3  372.75  4859.7  370.21  4910.8  368.70  5052.1  368.12
  5084.2  368.36  5099.9  367.33  5102.6  366.83  5105.9  367.33  5108.0  368.65
  5135.2  368.59  5153.7  367.40  5158.8  368.82  5204.5  368.84  5209.6  369.64
  5356.8  375.34  5361.9  375.04  5407.6  376.98  5412.7  376.49  5458.4  378.23
  5482.0  378.19  5563.0  380.42  5624.9  382.02  5737.1  382.66  5763.0  383.99
  5768.1  383.65  5813.8  383.82  5818.9  383.30  5879.9  383.81  5944.2  383.62
#Mann=4,-1,0
  4759.4     0.1       0  5099.9    0.07       0  5105.9     0.1       0
  5563.0    0.05       0
Bank Sta=5099.9,5105.9
Exp/Cntr=0.3,0.1

Type RM Length L Ch R = 1,6275,683,683,683
BEGIN DESCRIPTION:
STEELE CREEK TRIB 20 13.0
END DESCRIPTION:
XS GIS Cut Line= 4
      3519255.13     10459450.01      3519119.73     10459205.24
      3518854.11     10458554.20      3518952.71     10458325.85
#Sta/Elev= 30
  4453.7  379.16  4566.1  378.74  4610.5  376.67  4623.3  376.57  4675.8  373.81
  4697.5  373.27  4819.1  366.36  4848.5  365.59  4907.7  365.55  4955.4  366.70
  5000.5  364.14  5003.3  363.64  5006.5  364.14  5008.9  364.67  5032.9  365.54
  5039.7  365.21  5050.5  365.66  5097.8  368.55  5212.0  375.43  5265.5  376.79
  5270.9  376.54  5294.9  378.04  5324.3  378.18  5385.3  380.27  5468.0  381.17
  5520.4  380.11  5625.3  380.02  5635.4  380.34  5643.4  381.22  5685.3  382.74
#Mann=5,-1,0
  4453.7    0.05       0  4907.7    0.12       0  5000.5    0.07       0
  5006.5    0.12       0  5097.8    0.05       0
Bank Sta=5000.5,5006.5
Exp/Cntr=0.3,0.1

Type RM Length L Ch R = 1,5592,905,905,905
BEGIN DESCRIPTION:
STEELE CREEK TRIB 20 11.0
END DESCRIPTION:
XS GIS Cut Line= 3
      3519593.70     10459314.61      3519703.06     10459142.74
      3519473.89     10457887.51
#Sta/Elev= 30
  4412.5  377.02  4427.9  377.02  4499.1  373.01  4602.4  368.74  4651.2  367.94
  4698.7  366.16  4704.4  365.28  4729.2  365.58  4790.1  361.72  4800.3  362.06
  4818.1  360.96  4820.8  360.46  4824.1  360.96  4841.0  361.79  4868.4  361.38
  4963.0  362.31  4980.8  361.15  5003.6  361.46  5034.1  362.12  5069.4  364.24
  5270.4  374.45  5379.7  379.90  5538.8  383.39  5587.5  383.36  5600.3  383.47
  5735.5  382.89  5755.8  380.50  5761.9  382.61  5772.8  383.46  5892.2  386.02
#Mann=9,-1,0
  4412.5    0.05       0  4818.1    0.07       0  4824.1    0.05       0
  4868.4    0.12       0  5069.4     0.1       0  5270.4    0.05       0
  5587.5     0.1       0  5600.3    0.05       0  5772.8     0.1       0
Bank Sta=4818.1,4824.1
Exp/Cntr=0.3,0.1

Type RM Length L Ch R = 1,4687,688,688,688
BEGIN DESCRIPTION:
STEELE CREEK TRIB 20 9.0
END DESCRIPTION:
XS GIS Cut Line= 4
      3520036.39     10459465.67      3520291.61     10459335.45
      3520484.31     10458762.54      3520541.47     10458035.05
#Sta/Elev= 30
  4550.0  374.37  4654.9  373.67  4721.5  371.84  4832.7  365.31  4949.6  356.91
  5007.3  357.82  5096.9  357.25  5164.9  357.98  5193.4  356.81  5196.1  356.31
  5199.4  356.81  5233.2  357.73  5252.0  359.32  5312.8  367.12  5385.4  373.20
  5422.2  374.60  5542.2  376.46  5600.8  374.56  5612.4  375.34  5642.5  374.46
  5699.8  375.06  5738.2  376.53  5853.1  380.24  5865.0  379.83  5963.1  379.49
  6024.8  379.41  6093.9  379.83  6111.9  380.83  6159.4  380.38  6170.7  380.26
#Mann=11,-1,0
  4550.0    0.05       0  5096.9    0.16       0  5193.4    0.03       0
  5199.4    0.16       0  5312.8    0.05       0  5699.8    0.16       0
  5738.2    0.05       0  5865.0     0.1       0  5963.1    0.05       0
  6024.8     0.1       0  6159.4    0.05       0
Bank Sta=5193.4,5199.4
Exp/Cntr=0.3,0.1

Type RM Length L Ch R = 1,3999,708,708,708
BEGIN DESCRIPTION:
STEELE CREEK TRIB 20 6.0
END DESCRIPTION:
XS GIS Cut Line= 4
      3520578.09     10459793.78      3520822.86     10459720.87
      3521020.77     10458845.87      3520854.11     10458439.62
#Sta/Elev= 30
  4361.9  373.73  4439.1  371.64  4470.4  370.11  4489.0  370.15  4599.0  365.68
  4619.5  365.53  4667.8  362.12  4822.3  354.80  4860.3  353.58  4985.6  353.18
  5006.1  352.32  5067.6  353.17  5083.4  352.20  5086.2  351.70  5089.4  352.20
  5126.0  353.38  5159.9  353.12  5179.2  355.08  5221.0  357.40  5274.5  358.81
  5312.5  361.21  5323.9  362.56  5452.3  369.21  5514.0  371.23  5577.6  372.18
  5745.9  378.86  5832.4  379.75  5863.0  379.13  5921.8  379.83  5953.5  379.37
#Mann=5,-1,0
  4361.9    0.05       0  5083.4    0.03       0  5089.4    0.05       0
  5126.0     0.1       0  5179.2    0.05       0
Bank Sta=5083.4,5089.4
Exp/Cntr=0.3,0.1

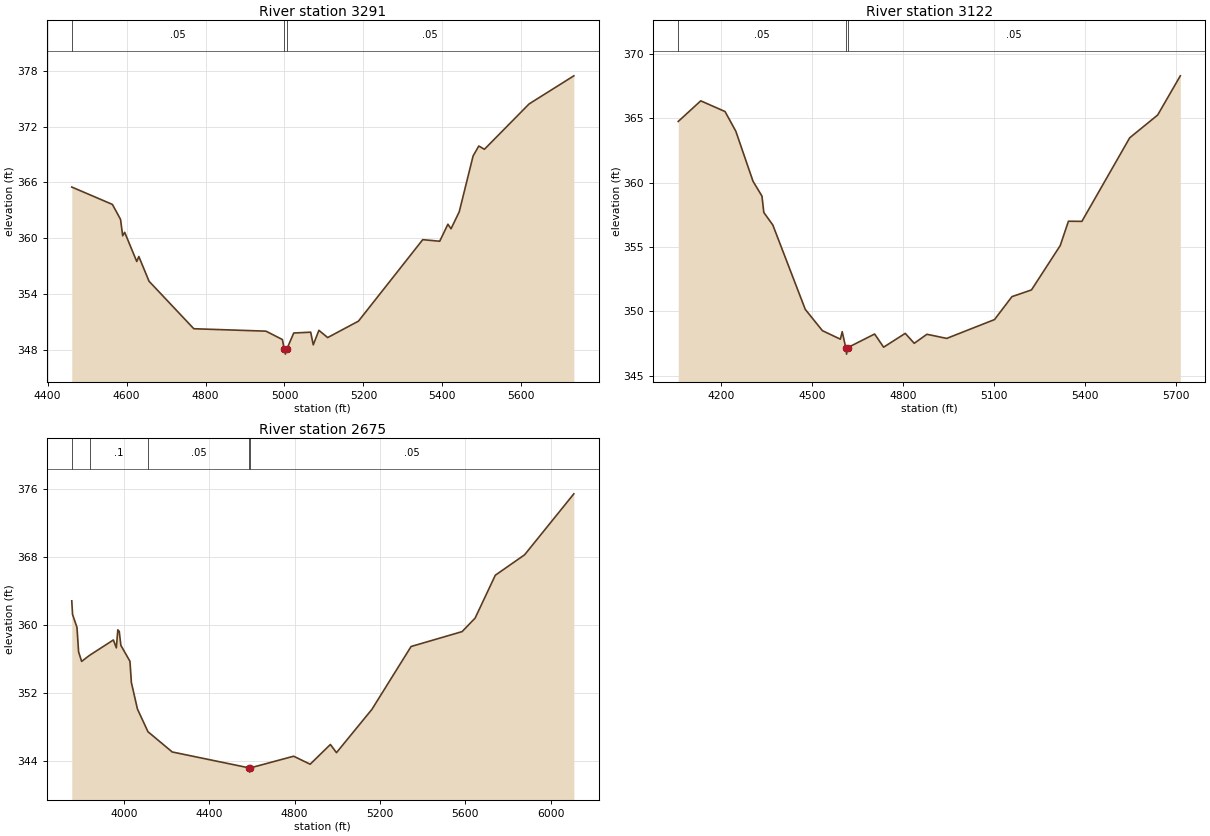
Type RM Length L Ch R = 1,3291,169,169,169
BEGIN DESCRIPTION:
Mapping XS 2c776a39
END DESCRIPTION:
XS GIS Cut Line= 3
      3521475.33     10459591.44      3521561.26     10459252.92
      3520972.71     10458541.98
#Sta/Elev= 30
  4461.1  365.50  4564.1  363.63  4584.7  362.02  4590.1  360.26  4595.2  360.63
  4625.8  357.49  4631.0  358.03  4656.9  355.37  4770.4  350.26  4953.2  350.00
  4994.8  349.10  4999.6  348.03  5002.4  347.53  5005.6  348.03  5023.5  349.80
  5066.5  349.89  5073.0  348.53  5087.3  350.09  5109.5  349.31  5187.6  351.08
  5350.4  359.84  5393.4  359.67  5414.2  361.50  5422.1  361.01  5442.9  362.84
  5478.0  368.84  5492.4  369.91  5506.7  369.56  5620.0  374.44  5733.3  377.46
#Mann=3,-1,0
  4461.1    0.05       0  4999.6    0.03       0  5005.6    0.05       0
Bank Sta=4999.6,5005.6
Exp/Cntr=0.3,0.1

Type RM Length L Ch R = 1,3122,447,447,447
BEGIN DESCRIPTION:
Mapping XS 8a77a1f8
END DESCRIPTION:
XS GIS Cut Line= 3
      3521444.83     10459758.14      3521766.99     10459305.01
      3521131.56     10458409.16
#Sta/Elev= 30
  4059.9  364.74  4134.1  366.34  4214.1  365.51  4249.7  363.98  4306.3  360.10
  4335.8  358.95  4341.9  357.68  4371.5  356.71  4478.5  350.16  4535.0  348.51
  4594.1  347.85  4600.2  348.43  4611.9  347.19  4614.6  346.69  4617.9  347.19
  4707.0  348.25  4736.6  347.23  4807.9  348.30  4837.5  347.53  4879.3  348.23
  4944.5  347.91  5102.0  349.37  5159.5  351.15  5223.8  351.67  5318.5  355.11
  5345.6  357.00  5389.9  356.99  5547.4  363.47  5639.6  365.24  5714.2  368.28
#Mann=3,-1,0
  4059.9    0.05       0  4611.9    0.04       0  4617.9    0.05       0
Bank Sta=4611.9,4617.9
Exp/Cntr=0.3,0.1

Type RM Length L Ch R = 1,2675,0,0,0
BEGIN DESCRIPTION:
STEELE CREEK TRIB 20 1.0
END DESCRIPTION:
XS GIS Cut Line= 4
      3521545.67     10459870.08      3522162.82     10459323.23
      3521614.04     10458243.06      3521372.61     10458035.42
#Sta/Elev= 30
  3754.8  362.85  3758.4  361.26  3779.3  359.72  3786.8  356.85  3801.0  355.73
  3838.2  356.44  3949.9  358.25  3963.8  357.32  3970.8  359.44  3977.5  359.25
  3985.0  357.62  4027.7  355.74  4034.4  353.24  4062.8  350.13  4112.2  347.46
  4225.9  345.08  4586.4  343.21  4589.1  342.71  4592.4  343.21  4795.3  344.58
  4872.8  343.64  4967.7  345.96  4996.2  345.00  5162.4  350.09  5346.1  357.48
  5585.3  359.23  5646.4  360.82  5741.1  365.86  5878.4  368.26  6109.4  375.43
#Mann=5,-1,0
  3754.8    0.05       0  3838.2     0.1       0  4112.2    0.05       0
  4586.4    0.03       0  4592.4    0.05       0
Bank Sta=4586.4,4592.4
Exp/Cntr=0.3,0.1

Chan Stop Cuts=-1