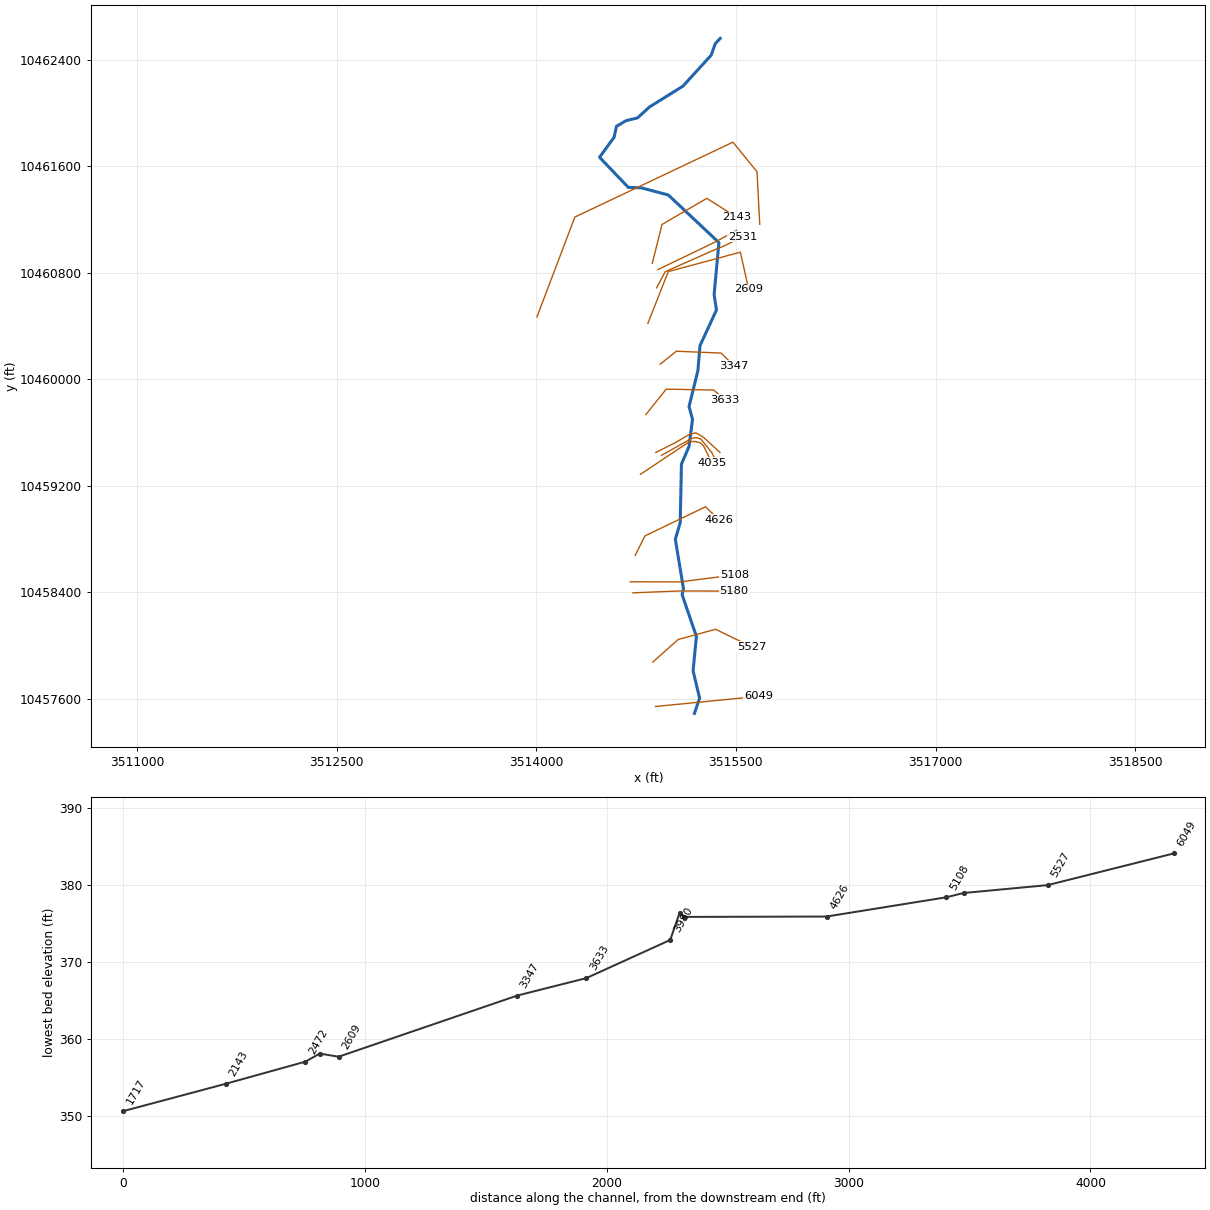
--- STEELE CREEK TRIB 23.prj (project) ---

Proj Title=STEELE CREEK TRIB 23 Base Level Engineering
Current Plan=p01
Default Exp/Contr=0.3,0.1
English Units
Geom File=g01
Flow File=f01
Plan File=p01
Y Axis Title=Elevation
X Axis Title(PF)=Main Channel Distance
X Axis Title(XS)=Station
BEGIN DESCRIPTION:
STEELE CREEK TRIB 23
END DESCRIPTION:
DSS Export Rating Curves= 0
DSS Export Rating Curve Sorted= 0
DSS Export Volume Flow Curves= 0
DXF OffsetX= 0
DXF OffsetY= 0
DXF ScaleX= 1
DXF ScaleY= 10

--- STEELE CREEK TRIB 23.p01 (plan) ---

Plan Title=Multiple Run
Short Identifier=Multiple
Geom File=g01
Flow File=f01
Subcritical Flow
K Sum by GR= 0
Std Step Tol= 0.01
Critical Tol= 0.01
Num of Std Step Trials= 20
Max Error Tol= 0.3
Flow Tol Ratio= 0.001
Split Flow NTrial= 30
Split Flow Tol= 0.02
Split Flow Ratio= 0.02
Log Output Level= 0
Friction Slope Method= 1
Unsteady Friction Slope Method= 2
Unsteady Bridges Friction Slope Method= 1
Parabolic Critical Depth
Global Vel Dist=  1 , 1 , 1
Global Log Level= 0
CheckData=True
Encroach Param= -1, 0, 0, 0
BEGIN DESCRIPTION:
Multiple Run
END DESCRIPTION:

--- STEELE CREEK TRIB 23.f01 (steady flow) ---

Flow Title=Multiple
Program Version=4.10
Number of Profiles= 7
Profile Names=10-year,25-year,50-year,1pct_min,100-year,1pct_plu,500-year
River Rch & RM=STEELE CREEK TRI,Reach-1         ,6049
     488     647     772     675     913    1235    1272
Boundary for River Rch & Prof#=STEELE CREEK TRI,Reach-1         , 1
Up Type= 0
Dn Type= 3
Dn Slope=0.005
Boundary for River Rch & Prof#=STEELE CREEK TRI,Reach-1         , 2
Up Type= 0
Dn Type= 3
Dn Slope=0.005
Boundary for River Rch & Prof#=STEELE CREEK TRI,Reach-1         , 3
Up Type= 0
Dn Type= 3
Dn Slope=0.005
Boundary for River Rch & Prof#=STEELE CREEK TRI,Reach-1         , 4
Up Type= 0
Dn Type= 3
Dn Slope=0.005
Boundary for River Rch & Prof#=STEELE CREEK TRI,Reach-1         , 5
Up Type= 0
Dn Type= 3
Dn Slope=0.005
Boundary for River Rch & Prof#=STEELE CREEK TRI,Reach-1         , 6
Up Type= 0
Dn Type= 3
Dn Slope=0.005
Boundary for River Rch & Prof#=STEELE CREEK TRI,Reach-1         , 7
Up Type= 0
Dn Type= 3
Dn Slope=0.005
DSS Import GetInterval= 0
DSS Import GetPeak= 0
DSS Import FillOption= 0

--- STEELE CREEK TRIB 23.g01 (geometry) ---

Geom Title=Existing Conditions
Program Version=4.10

River Reach=STEELE CREEK TRI,Reach-1
Reach XY= 30
      3515188.77     10457491.22      3515227.23     10457605.86
       3515178.4     10457809.85      3515202.93     10458070.05
      3515095.94     10458382.77      3515106.39     10458426.49
      3515044.94     10458799.43      3515081.83     10458924.22
      3515090.91     10459364.08      3515148.02     10459497.13
      3515174.06     10459700.04      3515148.02     10459796.61
      3515214.21     10460064.62      3515230.39     10460254.18
      3515353.68     10460520.51      3515336.32     10460636.83
       3515372.2     10461027.51      3514991.99     10461385.15
      3514788.86     10461438.97      3514691.79     10461441.96
      3514475.72     10461668.24      3514585.42     10461818.93
      3514602.78      10461900.6      3514675.52     10461943.35
      3514761.09     10461963.98      3514850.11     10462045.56
      3515102.17     10462202.54      3515314.44     10462435.09
      3515344.42     10462520.68      3515382.11     10462561.64

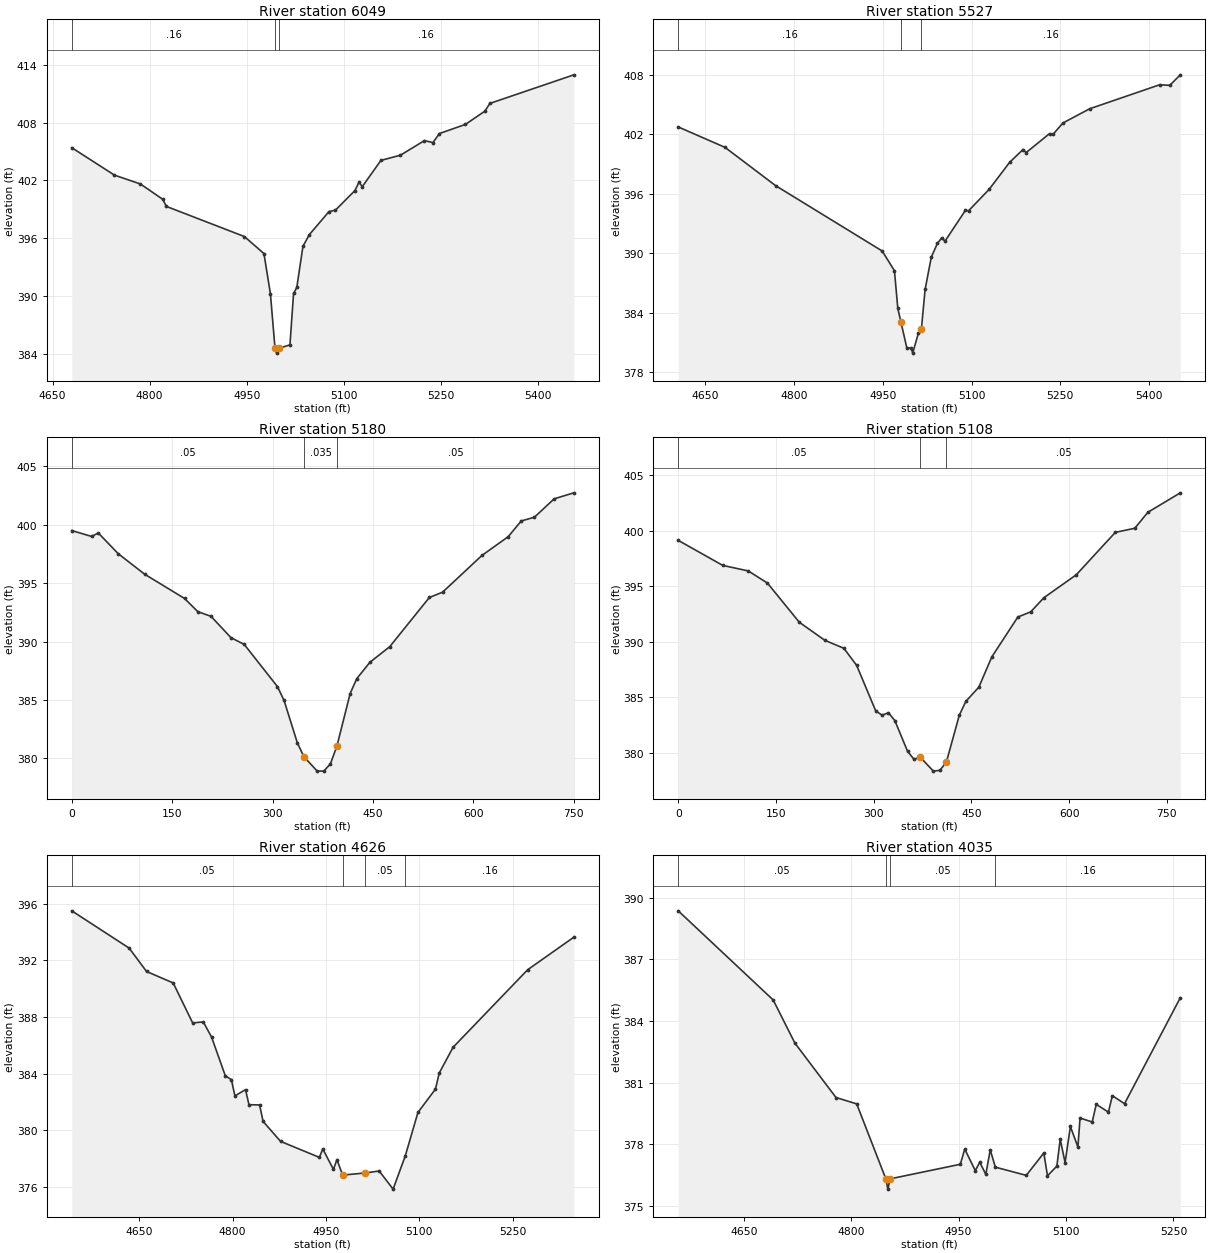
Type RM Length L Ch R = 1 ,6049    ,522,522,522
BEGIN DESCRIPTION:
STEELE CREEK TRIB 23 12.0
END DESCRIPTION:
XS GIS Cut Line= 2
      3514896.47     10457542.92      3515668.92     10457619.12
#Sta/Elev= 30
  4679.6   405.4  4745.6  402.55  4785.8  401.63  4820.2  400.04  4825.9   399.3
  4946.5  396.17  4976.7   394.4  4986.7  390.23  4993.8  384.56  4996.5  384.06
  4999.8  384.56  5016.9  384.92  5022.5  390.26  5027.5  390.88    5037  395.16
    5047  396.38  5077.2  398.76  5087.2  398.91  5117.4  400.95  5123.7  401.83
  5128.7  401.35  5157.5  404.08  5187.7  404.62  5224.9  406.14  5237.9  405.93
    5248  406.87  5288.2  407.82  5318.3   409.2    5326     410  5455.8  412.97
#Mann= 3 ,-1 , 0
  4679.6     .16       0  4993.8     .07       0  4999.8     .16       0
Bank Sta=4993.8,4999.8
XS Rating Curve= 0 ,0
Exp/Cntr=0.3,0.1

Type RM Length L Ch R = 1 ,5527    ,347,347,347
BEGIN DESCRIPTION:
STEELE CREEK TRIB 23 11.0
END DESCRIPTION:
XS GIS Cut Line= 4
      3514875.68     10457876.27      3515066.63     10458046.39
      3515347.88     10458122.78      3515617.95     10457991.21
#Sta/Elev= 30
  4604.9  402.73  4683.9  400.67  4769.2  396.82  4949.2  390.23  4969.9  388.24
  4975.6  384.44  4980.8  383.09  4990.7  380.49    4998  380.44  5000.8  379.94
  5010.2  381.94  5015.4  382.37  5021.7  386.37  5032.1   389.6  5042.5  391.01
    5050  391.56  5055.2  391.22  5089.8  394.33    5095  394.28  5129.6  396.43
  5164.2  399.15  5186.8  400.45  5192.3  400.15  5231.8  402.06  5237.4  401.97
  5254.4  403.13  5299.5  404.56  5417.7  406.98  5434.7  406.92  5452.5  407.98
#Mann= 3 , 0 , 0
  4604.9     .16       0  4980.8     .07       0  5015.4     .16       0
Bank Sta=4980.8,5015.4
XS Rating Curve= 0 ,0
Exp/Cntr=0.3,0.1

Type RM Length L Ch R = 1 ,5180    ,72,72,72
XS GIS Cut Line= 3
      3514726.58    10458396.645     3515079.227    10458410.751
     3515485.043    10458409.666
#Sta/Elev= 30
       0399.498529.74339398.991139.65786399.292569.40125  397.52109.0591395.7593
168.5459393.6891188.3748 392.561208.2038392.1576237.9472390.3341257.7761389.7576
307.3484386.1514317.2629384.9664337.0918381.3411346.9619380.1451366.7021378.9294
376.5723378.9193386.4424379.5269396.3125381.0744416.0527385.5581425.9228386.8329
445.6631388.2346475.2734389.5691534.4379393.7756554.0659394.2219612.9496397.3677
652.2054398.9745671.8334400.3204691.4613400.6403720.9032402.2118750.3451402.7258
#Mann= 3 , 0 , 0
       0     .05       0346.9619    .035       0396.3125     .05       0
Bank Sta=346.9619,396.3125
XS Rating Curve= 0 ,0
Exp/Cntr=0.3,0.1

Type RM Length L Ch R = 1 ,5108    ,495,495,495
XS GIS Cut Line= 3
     3514706.267    10458479.674     3515077.361    10458478.589
     3515488.233     10458531.02
#Sta/Elev= 30
       0399.120368.44231396.8645107.5522396.3697136.8846395.2781 185.772391.7559
224.8819390.1325254.2143389.4091273.7693387.8792303.1017383.7746312.8792383.3904
322.6566 383.612332.4341382.9029 351.989 380.137361.7665379.4248 371.544379.6096
391.4951378.3583401.4707378.4314411.4462379.1528431.3974383.3915441.3729384.6324
 461.324385.9099481.2751388.6353521.1774392.2197541.1285392.6955561.0797393.9555
610.9575 396.026670.8108  399.84700.7375400.2091720.6886401.6425770.5664403.3972
#Mann= 3 , 0 , 0
       0     .05       0 371.544    .035       0411.4462     .05       0
Bank Sta=371.544,411.4462
XS Rating Curve= 0 ,0
Exp/Cntr=0.3,0.1

Type RM Length L Ch R = 1 ,4626    ,591,591,591
BEGIN DESCRIPTION:
STEELE CREEK TRIB 23 10.0
END DESCRIPTION:
XS GIS Cut Line= 4
      3514743.74     10458678.38      3514816.63     10458824.17
       3515271.5     10459042.92      3515371.69     10458946.18
#Sta/Elev= 30
  4541.5   395.5  4633.7  392.87  4661.7  391.22  4704.5  390.41  4735.8  387.59
  4752.9  387.66  4766.1   386.6  4788.2  383.87  4798.1  383.58  4803.7  382.44
  4820.8  382.88  4826.3  381.82  4843.4   381.8    4849  380.64  4877.1  379.23
  4939.5   378.1    4945  378.69  4962.1  377.25  4967.7  377.94  4976.9  376.85
  5012.9     377  5035.6  377.14    5058  375.86  5077.6  378.21  5097.9  381.27
  5126.1  382.92  5132.2  384.06  5154.4  385.87  5274.2  391.34  5348.5  393.64
#Mann= 4 ,-1 , 0
  4541.5     .05       0  4976.9    .035       0  5012.9     .05       0
  5077.6     .16       0
Bank Sta=4976.9,5012.9
XS Rating Curve= 0 ,0
Exp/Cntr=0.3,0.1

Type RM Length L Ch R = 1 ,4035    ,16,16,16
BEGIN DESCRIPTION:
STEELE CREEK TRIB 23 9.0
END DESCRIPTION:
XS GIS Cut Line= 6
      3514782.72     10459286.69       3515150.4     10459531.63
      3515191.63      10459533.8      3515232.87     10459522.95
      3515256.74     10459501.25      3515319.18     10459372.63
#Sta/Elev= 30
  4558.5  389.36  4691.1  385.02  4721.4  382.92  4778.8  380.27  4807.7  379.96
  4848.4  376.31  4851.2  375.81  4854.4  376.31  4952.4  377.02  4958.6  377.76
  4973.3  376.71  4979.5  377.12    4988  376.53  4994.2  377.72  5001.3  376.88
  5044.5  376.48    5069  377.57  5074.1  376.46  5087.2  376.93  5091.9  378.24
  5098.7   377.1  5106.1  378.86  5116.6  377.86  5119.6  379.27  5136.6  379.08
  5142.2  379.94  5159.2  379.56  5164.7  380.36  5181.7  379.97  5259.6  385.13
#Mann= 4 ,-1 , 0
  4558.5     .05       0  4848.4     .03       0  4854.4     .05       0
  5001.3     .16       0
Bank Sta=4848.4,4854.4
XS Rating Curve= 0 ,0
Exp/Cntr=0.3,0.1

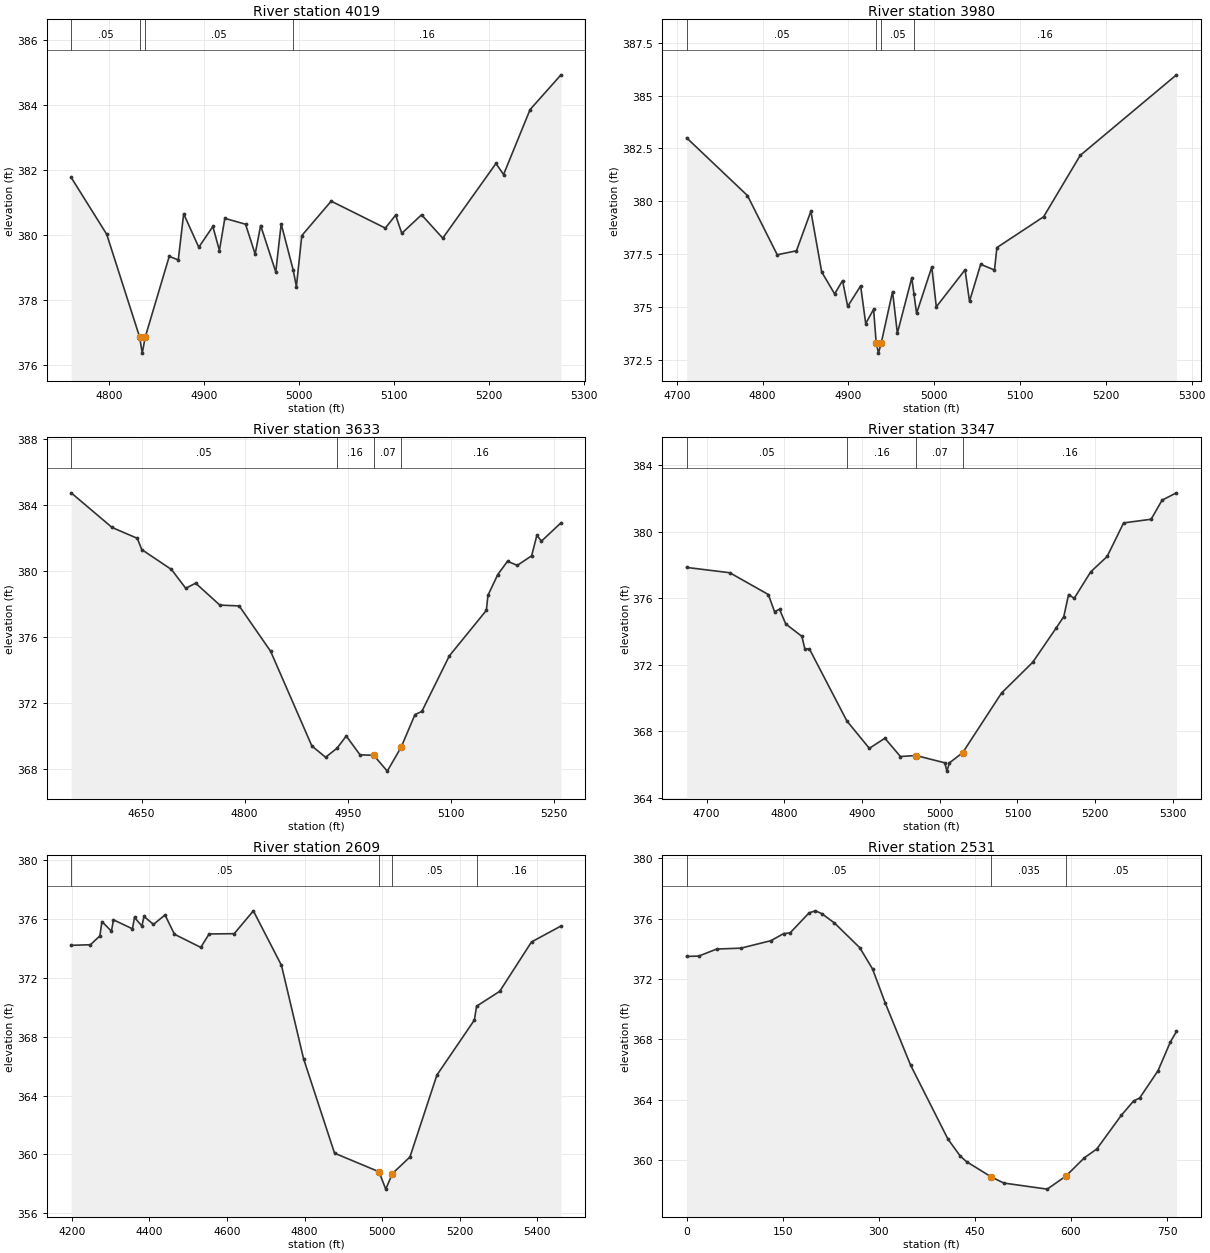
Type RM Length L Ch R = 1 ,4019    ,39,39,39
BEGIN DESCRIPTION:
STEELE CREEK TRIB 23 8.0
END DESCRIPTION:
XS GIS Cut Line= 6
       3514942.1     10459429.65      3515169.93     10459557.68
      3515204.66     10459562.02      3515237.21     10459551.16
      3515317.88     10459451.19      3515343.92     10459401.28
#Sta/Elev= 30
  4760.4  381.78  4797.8  380.03  4832.4  376.87  4835.2  376.37  4838.4  376.87
  4863.6  379.35  4873.1  379.24  4878.8  380.66  4894.7  379.63  4909.5  380.27
  4916.4  379.53  4922.1  380.52  4943.9  380.34    4954  379.42  4959.8   380.3
  4975.7  378.87  4981.4  380.35  4994.1  378.92  4997.4  378.42  5003.1  379.99
    5034  381.05    5091  380.22  5101.8  380.62  5108.3  380.06  5129.1  380.63
  5151.4  379.91  5207.4  382.21  5215.4  381.87  5243.3  383.87  5275.8  384.94
#Mann= 4 ,-1 , 0
  4760.4     .05       0  4832.4     .07       0  4838.4     .05       0
  4994.1     .16       0
Bank Sta=4832.4,4838.4
XS Rating Curve= 0 ,0
Exp/Cntr=0.3,0.1

Type RM Length L Ch R = 1 ,3980    ,347,347,347
BEGIN DESCRIPTION:
STEELE CREEK TRIB 23 6.0
END DESCRIPTION:
XS GIS Cut Line= 6
      3514898.71     10459451.36      3515041.89     10459522.95
      3515146.06     10459583.72      3515198.14     10459598.91
      3515254.57     10459566.36      3515380.42     10459451.35
#Sta/Elev= 30
  4711.4     383  4782.3  380.27    4817  377.47  4839.4  377.66  4856.2  379.53
  4868.8  376.66  4883.9  375.62  4893.1  376.25  4899.1  375.03  4914.2     376
  4920.1  374.22  4929.3  374.89  4932.3  373.32    4935  372.82  4938.3  373.32
  4951.4  375.73    4957  373.76  4973.8  376.38  4976.3  375.63  4979.4   374.7
  4997.1  376.89  5002.4  375.01  5035.9  376.76  5041.1  375.27  5054.1  377.02
  5070.2  376.75    5073  377.81  5127.5  379.27  5170.1  382.17  5282.3  385.98
#Mann= 4 ,-1 , 0
  4711.4     .05       0  4932.3     .07       0  4938.3     .05       0
  4976.3     .16       0
Bank Sta=4932.3,4938.3
XS Rating Curve= 0 ,0
Exp/Cntr=0.3,0.1

Type RM Length L Ch R = 1 ,3633    ,286,286,286
BEGIN DESCRIPTION:
STEELE CREEK TRIB 23 7.0
END DESCRIPTION:
XS GIS Cut Line= 4
      3514823.57     10459735.62      3514976.36      10459926.6
        3515334.     10459919.65      3515417.24     10459846.81
#Sta/Elev= 30
  4547.6  384.74  4607.1  382.64  4643.9  381.98  4650.3   381.3  4693.6  380.09
  4714.4  378.95  4728.8  379.26    4764  377.93  4792.2  377.88  4837.9  375.13
  4897.9  369.39  4917.9   368.7  4934.5  369.25    4948  369.99    4968  368.85
    4988  368.82  5007.7  367.86    5028  369.32    5048  371.29    5058  371.48
    5098  374.85  5151.9  377.61  5154.2  378.52  5168.5  379.78  5182.7  380.59
  5196.9  380.34  5217.8  380.92  5225.4  382.16  5232.1  381.81  5260.5  382.92
#Mann= 4 ,-1 , 0
  4547.6     .05       0  4934.5     .16       0    4988     .07       0
    5028     .16       0
Bank Sta=4988,5028
XS Rating Curve= 0 ,0
Exp/Cntr=0.3,0.1

Type RM Length L Ch R = 1 ,3347    ,738,738,738
BEGIN DESCRIPTION:
STEELE CREEK TRIB 23 5.0
END DESCRIPTION:
XS GIS Cut Line= 4
      3514931.19     10460114.07      3515052.75     10460211.32
      3515389.55     10460197.43      3515486.81     10460100.18
#Sta/Elev= 30
  4674.3  377.85  4729.8  377.53  4779.4  376.22  4787.4  375.19  4793.8  375.33
  4801.8  374.45  4822.6   373.7  4826.4  372.95  4832.2  372.95  4880.5  368.61
  4909.4  366.96  4929.4  367.57  4949.4  366.47  4969.4  366.53  5006.5  366.09
  5009.2  365.59  5012.5  366.09  5029.5   366.7  5079.5  370.29  5119.6  372.14
  5149.6  374.19  5159.6  374.89  5165.8  376.22    5173  375.99  5194.2  377.58
  5215.4  378.51  5236.6  380.53    5272  380.75  5286.1   381.9  5304.6  382.34
#Mann= 4 ,-1 , 0
  4674.3     .05       0  4880.5     .16       0  4969.4     .07       0
  5029.5     .16       0
Bank Sta=4969.4,5029.5
XS Rating Curve= 0 ,0
Exp/Cntr=0.3,0.1

Type RM Length L Ch R = 1 ,2609    ,78,78,78
BEGIN DESCRIPTION:
STEELE CREEK TRIB 23 4.0
END DESCRIPTION:
XS GIS Cut Line= 4
      3514838.91     10460420.52      3514991.69     10460809.41
      3515533.36     10460955.24      3515595.86     10460677.47
#Sta/Elev= 30
    4198  374.19  4247.7  374.23  4272.1  374.83  4277.4   375.8  4301.9  375.15
  4307.2  375.92  4356.1  375.31  4361.4  376.08  4380.5   375.5  4385.9  376.15
  4410.3  375.61  4440.1  376.25  4464.5  374.94  4532.3  374.05  4553.9  374.96
  4618.6  374.98    4668  376.53  4740.5  372.83  4797.5   366.5  4877.4  360.09
    4992  358.83  5009.5  357.65  5026.8  358.71  5071.9  359.83  5141.5  365.39
  5238.1  369.12  5243.8  370.06  5303.5  371.07  5385.5  374.42  5461.5   375.5
#Mann= 4 ,-1 , 0
    4198     .05       0    4992    .035       0  5026.8     .05       0
  5243.8     .16       0
Bank Sta=4992,5026.8
XS Rating Curve= 0 ,0
Exp/Cntr=0.3,0.1

Type RM Length L Ch R = 1 ,2531    ,59,59,59
XS GIS Cut Line= 5
     3514904.597    10460687.582     3514968.399    10460808.676
     3515344.701    10460975.343     3515415.014    10461003.989
     3515547.826    10461070.395
#Sta/Elev= 30
       0373.499418.80929373.520447.02322373.989484.64181374.0466 131.665374.5444
151.4745375.0147161.3792 375.056191.0934376.3866200.9981376.5233210.9029376.3383
230.7123375.7186270.3312374.0722290.1407372.6701309.9502370.4127349.5691366.2861
407.8961361.3779 427.265360.2448436.9495359.8806475.6873358.8645495.0562358.4633
562.8475358.0602591.9009358.9239620.9542 360.144640.2052 360.724678.4713 362.958
697.6043 363.906707.1708364.1082735.8704365.9223755.0034367.8195764.5699368.5209
#Mann= 3 , 0 , 0
       0     .05       0475.6873    .035       0591.9009     .05       0
Bank Sta=475.6873,591.9009
XS Rating Curve= 0 ,0
Exp/Cntr=0.3,0.1

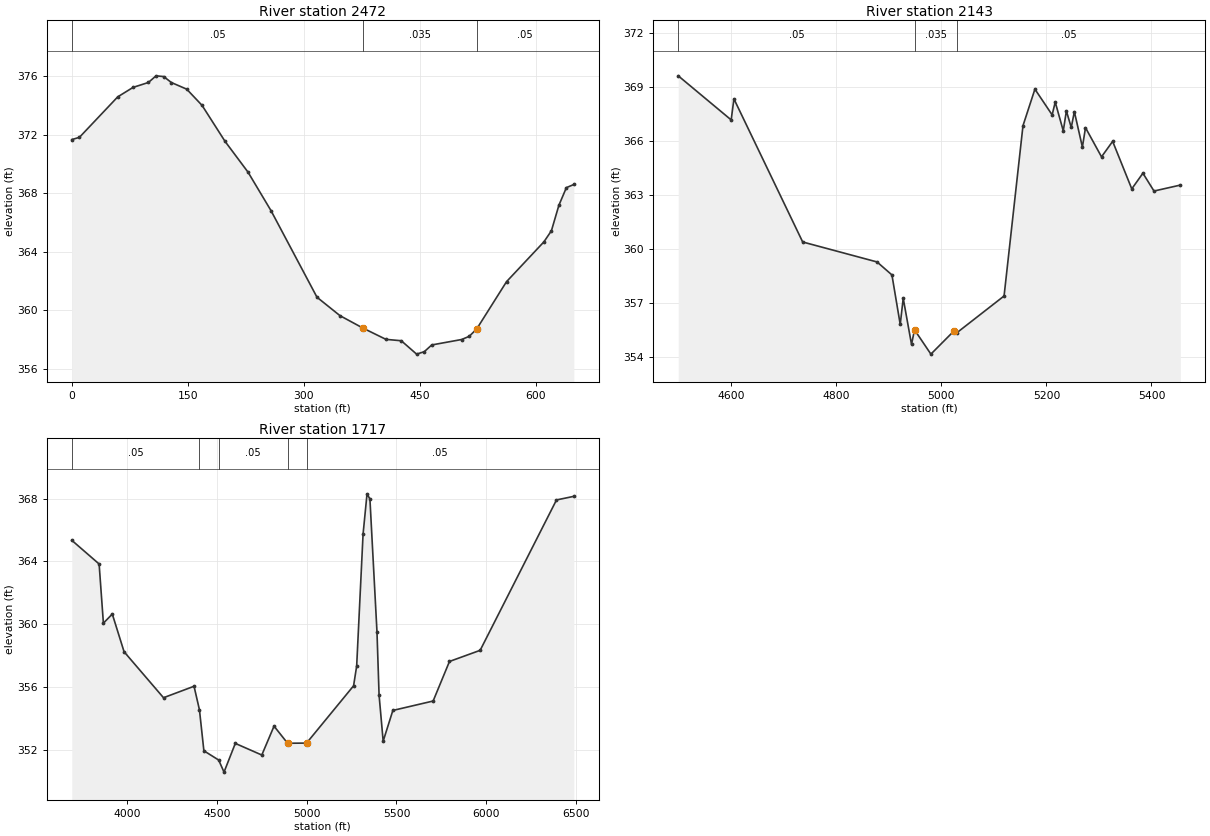
Type RM Length L Ch R = 1 ,2472    ,329,329,329
XS GIS Cut Line= 3
     3514913.712    10460824.301     3515332.983    10461026.124
     3515504.858    10461118.572
#Sta/Elev= 30
       0371.66389.913503371.817959.48101374.582879.30802 375.22899.13503 375.563
109.0485376.0175 118.962375.9665128.8755375.5593148.7025 375.107168.5295374.0008
198.2701371.5434228.0106  369.44257.7511366.8111317.2321360.8983346.9726359.6403
376.7131358.7909406.4536358.0209426.2806357.9268446.1076357.0131456.0211357.1794
 465.696357.6397504.3958358.0113514.0707358.2259523.7456358.7228562.4453361.9611
610.8199364.6815620.4949365.4368630.1698367.1774639.8447 368.381649.5197368.5976
#Mann= 3 , 0 , 0
       0     .05       0376.7131    .035       0523.7456     .05       0
Bank Sta=376.7131,523.7456
XS Rating Curve= 0 ,0
Exp/Cntr=0.3,0.1

Type RM Length L Ch R = 1 ,2143    ,426,426,426
BEGIN DESCRIPTION:
Mapping XS df3d22cd
END DESCRIPTION:
XS GIS Cut Line= 4
      3514871.91     10460871.83      3514944.84     10461163.54
      3515281.64     10461359.72      3515505.57     10461217.37
#Sta/Elev= 30
  4499.1   369.6  4599.9  367.15  4605.1  368.32    4736  360.37  4877.6  359.26
  4905.9  358.54  4921.7  355.79  4927.4  357.24  4943.2  354.68  4948.9  355.49
  4980.1  354.14  5023.4  355.41  5029.2  355.32  5119.4  357.37  5155.4  366.83
  5178.1  368.86  5210.9  367.43  5216.8  368.14  5232.1  366.54    5238  367.65
  5247.3  366.73  5253.2  367.61  5268.5  365.64  5274.4  366.72  5304.9   365.1
  5326.1  365.96  5362.5  363.32  5383.7  364.19  5404.8   363.2  5454.9  363.53
#Mann= 3 ,-1 , 0
  4499.1     .05       0  4948.9    .035       0  5029.2     .05       0
Bank Sta=4948.9,5023.4
XS Rating Curve= 0 ,0
Exp/Cntr=0.3,0.1

Type RM Length L Ch R = 1 ,1717    ,0,0,0
BEGIN DESCRIPTION:
STEELE CREEK TRIB 23 1.0
END DESCRIPTION:
XS GIS Cut Line= 5
      3514005.59     10460469.17       3514290.3     10461219.13
       3515477.8     10461781.63      3515658.36     10461559.41
      3515679.11     10461165.06
#Sta/Elev= 30
    3691  365.34  3843.4  363.83  3867.2  360.06  3916.8  360.64  3982.4  358.24
  4202.1  355.31  4372.2  356.04  4402.4  354.54  4427.1  351.93  4509.5  351.34
  4539.3  350.57  4602.2   352.4  4749.8  351.66    4818   353.5  4893.5  352.41
  4999.2  352.42  5261.2  356.07  5278.4  357.33    5314  365.73  5336.1   368.3
  5352.2  367.97  5391.5  359.51  5403.2  355.48    5426  352.54    5480   354.5
  5704.4   355.1  5795.4  357.62  5966.4  358.33  6391.7  367.91  6488.4  368.14
#Mann= 5 ,-1 , 0
    3691     .05       0  4402.4      .1       0  4509.5     .05       0
  4893.5    .035       0  4999.2     .05       0
#XS Ineff= 2 , 0
                         5395.45          357.56
Permanent Ineff=
       F       F
Bank Sta=4893.5,4999.2
XS Rating Curve= 0 ,0
Exp/Cntr=0.3,0.1
Stream Node=STEELE CREEK TRI,Reach-1         , 0 , 0 ,Upstream end
Stream Node=STEELE CREEK TRI,Reach-1         , 0 , 1 ,Downstream end

Chan Stop Cuts=-1
Use User Specified Reach Order=0
Composite Channel Slope=5