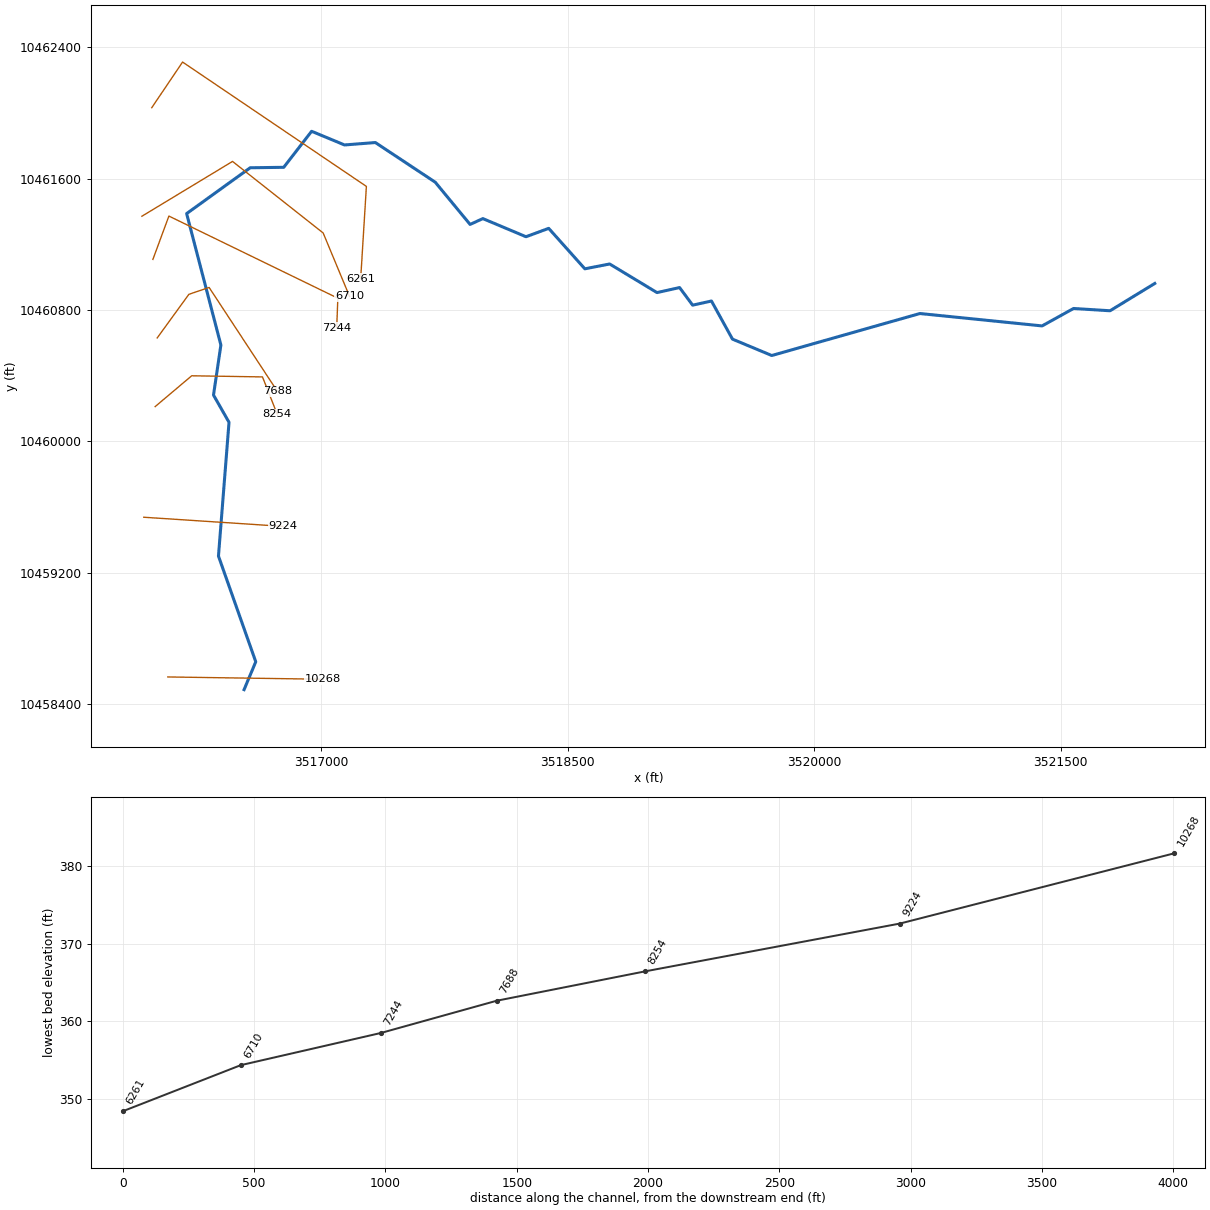
--- STEELE CREEK TRIB 24.prj (project) ---

Proj Title=STEELE CREEK TRIB 24 Base Level Engineering
Current Plan=p01
Default Exp/Contr=0.3,0.1
English Units
Geom File=g01
Flow File=f01
Plan File=p01
Y Axis Title=Elevation
X Axis Title(PF)=Main Channel Distance
X Axis Title(XS)=Station
BEGIN DESCRIPTION:
STEELE CREEK TRIB 24
END DESCRIPTION:
DSS Export Rating Curves= 0
DSS Export Rating Curve Sorted= 0
DSS Export Volume Flow Curves= 0
DXF OffsetX= 0
DXF OffsetY= 0
DXF ScaleX= 1
DXF ScaleY= 10

--- STEELE CREEK TRIB 24.p01 (plan) ---

Plan Title=Multiple Run
Short Identifier=Multiple
Geom File=g01
Flow File=f01
Subcritical Flow
K Sum by GR= 0
Std Step Tol= 0.01
Critical Tol= 0.01
Num of Std Step Trials= 20
Max Error Tol= 0.3
Flow Tol Ratio= 0.001
Split Flow NTrial= 30
Split Flow Tol= 0.02
Split Flow Ratio= 0.02
Log Output Level= 0
Friction Slope Method= 1
Unsteady Friction Slope Method= 2
Unsteady Bridges Friction Slope Method= 1
Parabolic Critical Depth
Global Vel Dist=  1 , 1 , 1
Global Log Level= 0
CheckData=True
Encroach Param= -1, 0, 0, 0
BEGIN DESCRIPTION:
Multiple Run
END DESCRIPTION:

--- STEELE CREEK TRIB 24.f01 (steady flow) ---

Flow Title=Multiple
Program Version=4.10
Number of Profiles= 7
Profile Names=10-year,25-year,50-year,1pct_min,100-year,1pct_plu,500-year
River Rch & RM=STEELE CREEK TRI,Reach-1         ,10268
     467     611     724     627     848    1146    1158
Boundary for River Rch & Prof#=STEELE CREEK TRI,Reach-1         , 1
Up Type= 0
Dn Type= 3
Dn Slope=0.005
Boundary for River Rch & Prof#=STEELE CREEK TRI,Reach-1         , 2
Up Type= 0
Dn Type= 3
Dn Slope=0.005
Boundary for River Rch & Prof#=STEELE CREEK TRI,Reach-1         , 3
Up Type= 0
Dn Type= 3
Dn Slope=0.005
Boundary for River Rch & Prof#=STEELE CREEK TRI,Reach-1         , 4
Up Type= 0
Dn Type= 3
Dn Slope=0.005
Boundary for River Rch & Prof#=STEELE CREEK TRI,Reach-1         , 5
Up Type= 0
Dn Type= 3
Dn Slope=0.005
Boundary for River Rch & Prof#=STEELE CREEK TRI,Reach-1         , 6
Up Type= 0
Dn Type= 3
Dn Slope=0.005
Boundary for River Rch & Prof#=STEELE CREEK TRI,Reach-1         , 7
Up Type= 0
Dn Type= 3
Dn Slope=0.005
DSS Import GetInterval= 0
DSS Import GetPeak= 0
DSS Import FillOption= 0

--- STEELE CREEK TRIB 24.g01 (geometry) ---

Geom Title=Existing Conditions
Program Version=4.10

River Reach=STEELE CREEK TRI,Reach-1
Reach XY= 30
      3516532.38       10458489.      3516603.48     10458658.85
      3516376.61     10459302.21      3516440.82     10460116.58
      3516346.46      10460282.1      3516391.34     10460586.92
      3516183.01      10461386.9      3516569.65     10461665.91
      3516773.63     10461668.63       3516943.2     10461887.89
      3517143.47     10461804.76      3517331.15     10461819.36
      3517695.32     10461577.88      3517907.19     10461321.01
      3517985.02      10461356.4      3518247.29     10461246.13
      3518385.36     10461297.05      3518605.35     10461050.81
      3518756.27     10461080.17      3519044.24     10460906.02
      3519181.54     10460936.61      3519260.95     10460829.61
      3519375.45     10460854.73      3519503.23     10460622.84
      3519742.32     10460522.99      3520643.28     10460778.64
      3521386.65     10460703.22      3521578.09     10460809.32
      3521800.01      10460795.4      3522072.11     10460961.64

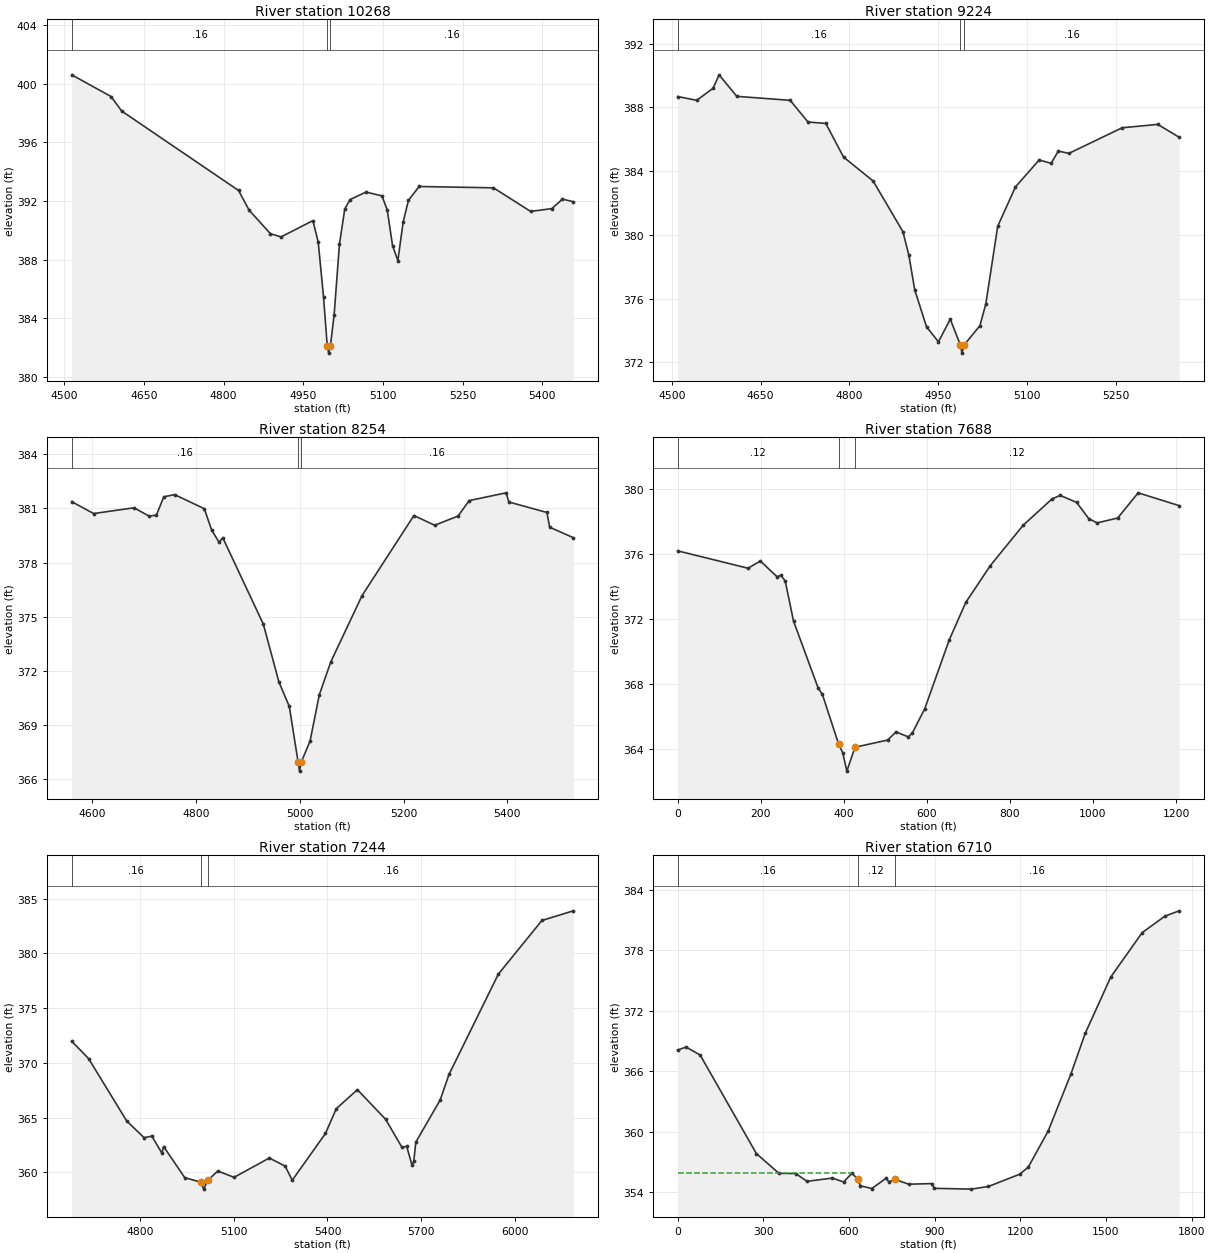
Type RM Length L Ch R = 1 ,10268   ,1043,1043,1043
BEGIN DESCRIPTION:
STEELE CREEK TRIB 24 15.0
END DESCRIPTION:
XS GIS Cut Line= 2
      3516068.09     10458566.36      3517012.49     10458552.47
#Sta/Elev= 30
  4514.1  400.61  4588.1  399.13  4608.1  398.14  4828.2  392.72  4848.2  391.37
  4888.2  389.77  4908.2  389.55  4968.2  390.66  4978.2   389.2  4988.2  385.48
  4995.2  382.12  4997.9  381.62  5001.2  382.12  5008.2  384.23  5018.2  389.05
  5028.2  391.45  5038.2   392.1  5068.2  392.61  5098.2  392.35  5108.2  391.39
  5118.2  388.96  5128.2  387.93  5138.2  390.57  5148.2  392.05  5168.2  392.99
  5308.2   392.9  5378.2  391.29  5418.2  391.48  5438.2  392.13  5458.6  391.95
#Mann= 3 ,-1 , 0
  4514.1     .16       0  4995.2     .07       0  5001.2     .16       0
Bank Sta=4995.2,5001.2
XS Rating Curve= 0 ,0
Exp/Cntr=0.3,0.1

Type RM Length L Ch R = 1 ,9224    ,970,970,970
BEGIN DESCRIPTION:
STEELE CREEK TRIB 24 13.0
END DESCRIPTION:
XS GIS Cut Line= 2
      3515922.28     10459538.58      3516768.27      10459483.1
#Sta/Elev= 30
  4509.8  388.68    4542  388.44  4569.8   389.2  4579.8  390.04  4609.8  388.69
    4700  388.44  4730.1  387.08  4760.2  386.99  4790.2  384.88  4840.2  383.38
  4890.4  380.21  4900.5  378.75  4910.5  376.55  4930.5  374.23  4950.6  373.29
  4970.6  374.71  4987.7  373.08  4990.4  372.58  4993.7  373.08  5020.7   374.3
  5030.7  375.67  5050.8  380.54  5080.8  383.01  5120.9   384.7    5141  384.49
  5153.3  385.26    5171  385.11  5261.2  386.72  5321.4  386.93  5357.6  386.12
#Mann= 3 ,-1 , 0
  4509.8     .16       0  4987.7     .07       0  4993.7     .16       0
Bank Sta=4987.7,4993.7
XS Rating Curve= 0 ,0
Exp/Cntr=0.3,0.1

Type RM Length L Ch R = 1 ,8254    ,566,566,566
BEGIN DESCRIPTION:
STEELE CREEK TRIB 24 11.0
END DESCRIPTION:
XS GIS Cut Line= 4
      3515991.69     10460212.19      3516213.91     10460399.69
      3516644.47     10460392.74      3516734.13     10460165.14
#Sta/Elev= 30
  4560.9  381.38    4603  380.72    4681  381.04  4709.6  380.58  4723.9  380.63
  4738.2  381.65  4759.1  381.77  4816.2  380.99  4830.5  379.79  4844.8  379.12
  4851.7  379.38  4929.9  374.58  4959.9  371.37  4979.9  370.01  4996.9  366.92
  4999.6  366.42  5002.9  366.92  5019.9  368.09  5037.7  370.66  5059.9  372.49
  5119.9  376.16  5219.9  380.61  5259.9  380.07  5304.9  380.58  5326.4  381.44
  5397.4  381.87  5402.8  381.36    5476  380.78  5481.4  379.96  5526.9  379.38
#Mann= 3 ,-1 , 0
  4560.9     .16       0  4996.9     .07       0  5002.9     .16       0
Bank Sta=4996.9,5002.9
XS Rating Curve= 0 ,0
Exp/Cntr=0.3,0.1

Type RM Length L Ch R = 1 ,7688    ,440,440,440
XS GIS Cut Line= 4
     3516003.894     10460629.89     3516196.602    10460895.515
     3516319.866    10460937.182     3516734.796    10460305.237
#Sta/Elev= 30
       0376.1926169.3427375.1206199.2267375.5639239.0721374.6019249.0334374.6767
258.9948374.3288278.9174371.8717 338.552367.7254348.3798367.3586387.6912364.2818
 397.519363.7551407.3469362.6269427.0026 364.099505.9043364.5419525.6716365.0459
555.3225364.7348565.2062364.9826594.8571366.4646654.1589370.7241693.6935373.0142
752.9953375.2885832.0644 377.772901.2499 379.386921.0172379.6052960.5517379.1735
990.2026378.1643 1009.97377.91331059.388  378.211108.806379.76361207.643378.9725
#Mann= 3 , 0 , 0
       0     .12       0387.6912     .07       0427.0026     .12       0
Bank Sta=387.6912,427.0026
XS Rating Curve= 0 ,0
Exp/Cntr=0.3,0.1

Type RM Length L Ch R = 1 ,7244    ,534,534,534
BEGIN DESCRIPTION:
STEELE CREEK TRIB 24 9.0
END DESCRIPTION:
XS GIS Cut Line= 4
      3515977.79     10461107.99      3516075.03     10461371.91
       3517102.8     10460871.91      3517095.86     10460691.35
#Sta/Elev= 30
  4581.8  371.98  4635.7   370.4  4757.5  364.71    4813  363.18  4838.1  363.32
  4870.2  361.77  4875.8  362.37  4943.4  359.53  4994.1  359.12  5004.1  358.48
  5016.7  359.28  5048.9  360.13  5101.3  359.56    5214  361.32  5264.7  360.58
  5287.3  359.29  5393.6  363.56  5428.1  365.82  5495.8  367.56    5586  364.86
  5638.3   362.3  5653.6  362.39  5670.6  360.66  5676.2  361.01  5682.7  362.77
  5760.6  366.61  5788.9  368.95  5946.8  378.11  6086.3  383.01  6186.7  383.89
#Mann= 3 , 0 , 0
  4581.8     .16       0  4994.1     .12       0  5016.7     .16       0
#XS Ineff= 2 , 0
                         5496.36          367.54
Permanent Ineff=
       F       F
Bank Sta=4994.1,5016.7
XS Rating Curve= 0 ,0
Exp/Cntr=0.3,0.1

Type RM Length L Ch R = 1 ,6710    ,449,449,449
XS GIS Cut Line= 4
     3515911.084     10461370.92     3516462.227    10461704.543
     3517013.515    10461268.924     3517174.105    10460882.639
#Sta/Elev= 30
       0368.102629.54745368.401578.79319367.6078275.7762357.8476354.5693355.8954
413.6642  355.87453.0608 355.098541.7032 355.424581.0997 355.036610.6472355.9086
630.3455355.3125640.1946 354.656680.0344354.3886729.8341355.4043739.7941355.0335
759.7139355.3019809.5136354.8161889.1931354.8761899.1531354.40841028.632354.3274
1088.392 354.5911197.951355.80541227.831356.50511297.551360.07751377.312365.7382
1427.213369.75171517.036 375.348 1626.82379.73411706.663381.37061756.564381.8944
#Mann= 3 , 0 , 0
       0     .16       0630.3455     .12       0759.7139     .16       0
#XS Ineff= 2 , 0
       0  610.23  355.96               0
Permanent Ineff=
       T       F
Bank Sta=630.3455,759.7139
XS Rating Curve= 0 ,0
Exp/Cntr=0.3,0.1

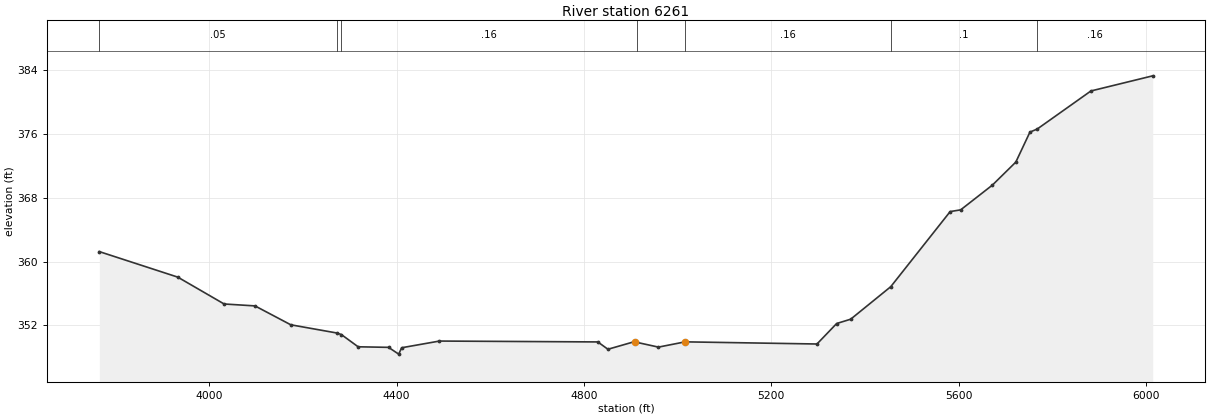
Type RM Length L Ch R = 1 ,6261    ,0,0,0
BEGIN DESCRIPTION:
STEELE CREEK TRIB 24 1.0
END DESCRIPTION:
XS GIS Cut Line= 4
      3515970.88     10462031.67      3516158.36     10462309.41
      3517276.41     10461552.47      3517241.69     10460989.92
#Sta/Elev= 30
  3765.5  361.25  3932.9  358.05  4031.9  354.68  4097.8  354.44  4174.2  352.07
  4272.6  351.04  4282.1  350.85    4318  349.31  4382.9  349.24  4404.6  348.39
  4410.9  349.19  4491.6  350.03  4829.7  349.92  4851.3     349  4908.2  349.96
  4914.2  349.85  4959.1  349.27  5016.1  349.93  5297.6  349.66  5339.6  352.23
  5369.5  352.77  5455.1  356.85  5581.9  366.27  5604.4  366.49    5672  369.59
  5722.1  372.48  5752.2  376.24  5767.9  376.63  5882.4   381.4  6014.4   383.3
#Mann= 7 ,-1 , 0
  3765.5     .05       0  4272.6      .1       0  4282.1     .16       0
  4914.2     .12       0  5016.1     .16       0  5455.1      .1       0
  5767.9     .16       0
Bank Sta=4908.2,5016.1
XS Rating Curve= 0 ,0
Exp/Cntr=0.3,0.1
Stream Node=STEELE CREEK TRI,Reach-1         , 0 , 0 ,Upstream end
Stream Node=STEELE CREEK TRI,Reach-1         , 0 , 1 ,Downstream end

Chan Stop Cuts=-1
Use User Specified Reach Order=0
Composite Channel Slope=5