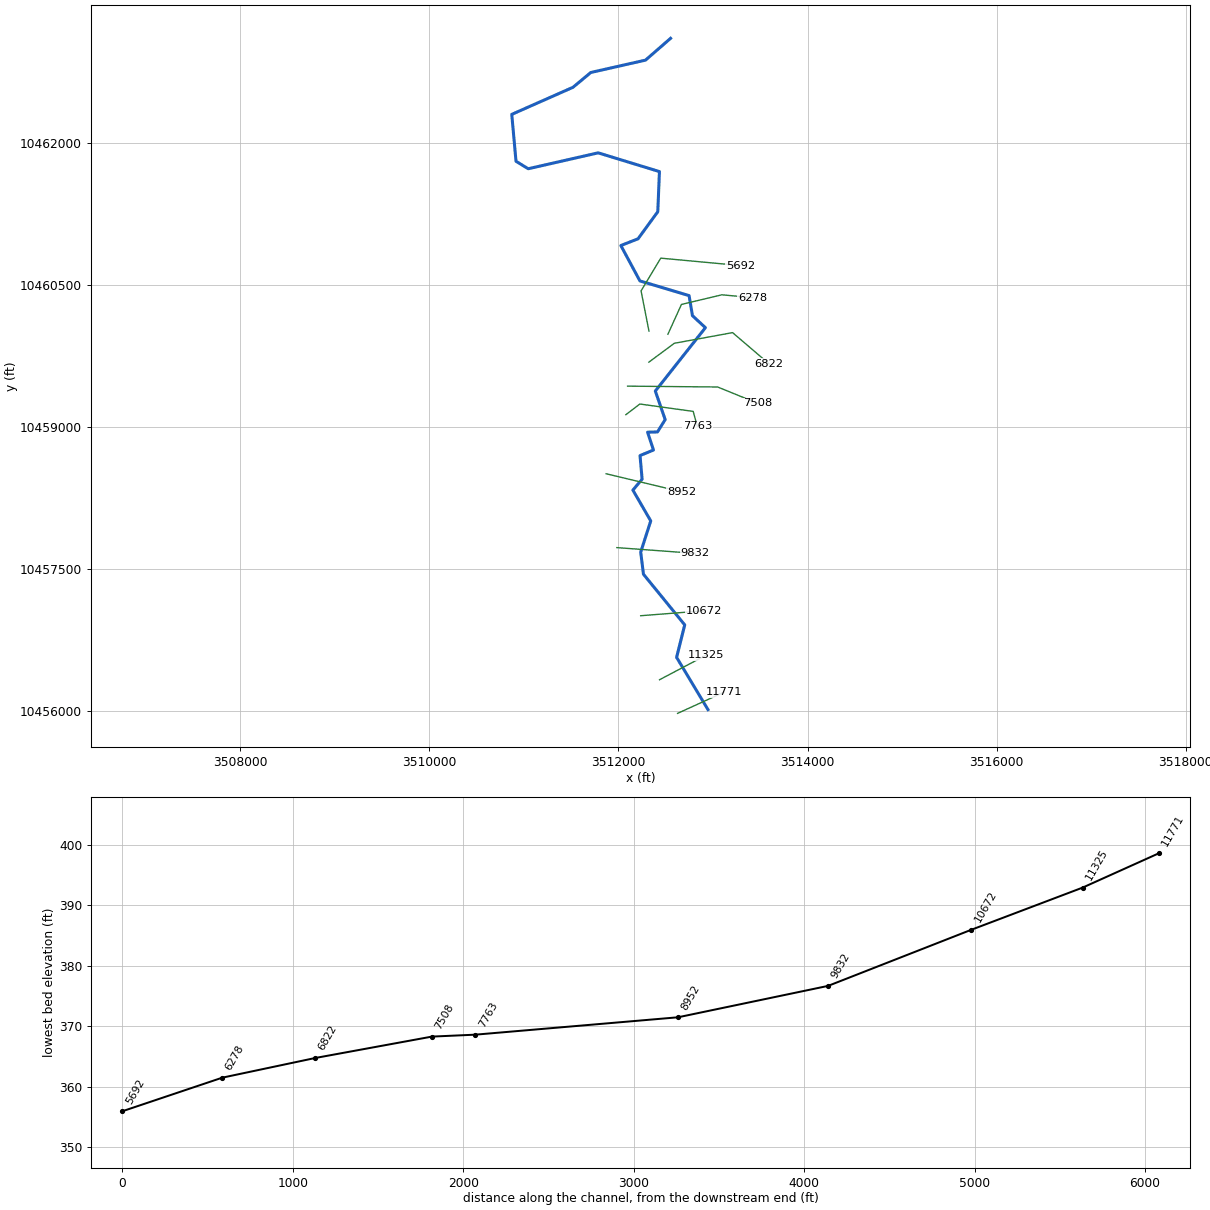
--- STEELE CREEK TRIB 25.prj (project) ---

Proj Title=STEELE CREEK TRIB 25 Base Level Engineering
Current Plan=p01
Default Exp/Contr=0.3,0.1
English Units
Geom File=g01
Flow File=f01
Plan File=p01
BEGIN DESCRIPTION:
STEELE CREEK TRIB 25
END DESCRIPTION:

--- STEELE CREEK TRIB 25.p01 (plan) ---

Plan Title=Multiple Run
Short Identifier=Multiple
Geom File=g01
Flow File=f01
Subcritical Flow
K Sum by GR= 0
Std Step Tol= 0.01
Critical Tol= 0.01
Num of Std Step Trials= 20
Max Error Tol= 0.3
Flow Tol Ratio= 0.001
Split Flow NTrial= 30
Split Flow Tol= 0.02
Split Flow Ratio= 0.02
Log Output Level= 0
Friction Slope Method= 1
Unsteady Friction Slope Method= 2
Unsteady Bridges Friction Slope Method= 1
Parabolic Critical Depth
Global Vel Dist=  1 , 1 , 1
Global Log Level= 0
CheckData=True
Encroach Param= -1, 0, 0, 0
BEGIN DESCRIPTION:
Multiple Run
END DESCRIPTION:

--- STEELE CREEK TRIB 25.f01 (steady flow) ---

Flow Title=Multiple
Number of Profiles=7
Profile Names=10-year,25-year,50-year,1pct_min,100-year,1pct_plu,500-year
River Rch & RM= STEELE CREEK TRI,Reach-1,11771
     719     970    1173    1035    1400    1893    1989
Boundary for River Rch & Prof#=STEELE CREEK TRI,Reach-1,1
Up Type=0
Dn Type=3
Dn Slope=0.005
Boundary for River Rch & Prof#=STEELE CREEK TRI,Reach-1,2
Up Type=0
Dn Type=3
Dn Slope=0.005
Boundary for River Rch & Prof#=STEELE CREEK TRI,Reach-1,3
Up Type=0
Dn Type=3
Dn Slope=0.005
Boundary for River Rch & Prof#=STEELE CREEK TRI,Reach-1,4
Up Type=0
Dn Type=3
Dn Slope=0.005
Boundary for River Rch & Prof#=STEELE CREEK TRI,Reach-1,5
Up Type=0
Dn Type=3
Dn Slope=0.005
Boundary for River Rch & Prof#=STEELE CREEK TRI,Reach-1,6
Up Type=0
Dn Type=3
Dn Slope=0.005
Boundary for River Rch & Prof#=STEELE CREEK TRI,Reach-1,7
Up Type=0
Dn Type=3
Dn Slope=0.005

--- STEELE CREEK TRIB 25.g01 (geometry) ---

Geom Title=Existing Conditions

River Reach=STEELE CREEK TRI,Reach-1
Reach XY= 30
      3512947.12     10456010.16      3512615.20     10456562.75
      3512701.14     10456906.50      3512264.51     10457442.58
      3512235.49     10457676.01      3512341.68     10458006.23
      3512152.69     10458332.39      3512250.48     10458447.26
      3512228.34     10458697.40      3512370.58     10458756.19
      3512308.14     10458944.77      3512412.94     10458947.61
      3512494.42     10459078.26      3512390.14     10459380.01
      3512920.00     10460050.49      3512782.94     10460177.31
      3512747.35     10460389.55      3512226.95     10460545.37
      3512025.56     10460919.50      3512207.41     10460990.68
      3512416.18     10461277.14      3512433.74     10461701.54
      3511785.54     10461899.97      3511045.52     10461731.57
      3510916.40     10461810.78      3510871.49     10462306.87
      3511519.03     10462593.20      3511707.57     10462749.80
      3512286.39     10462880.70      3512551.54     10463111.24

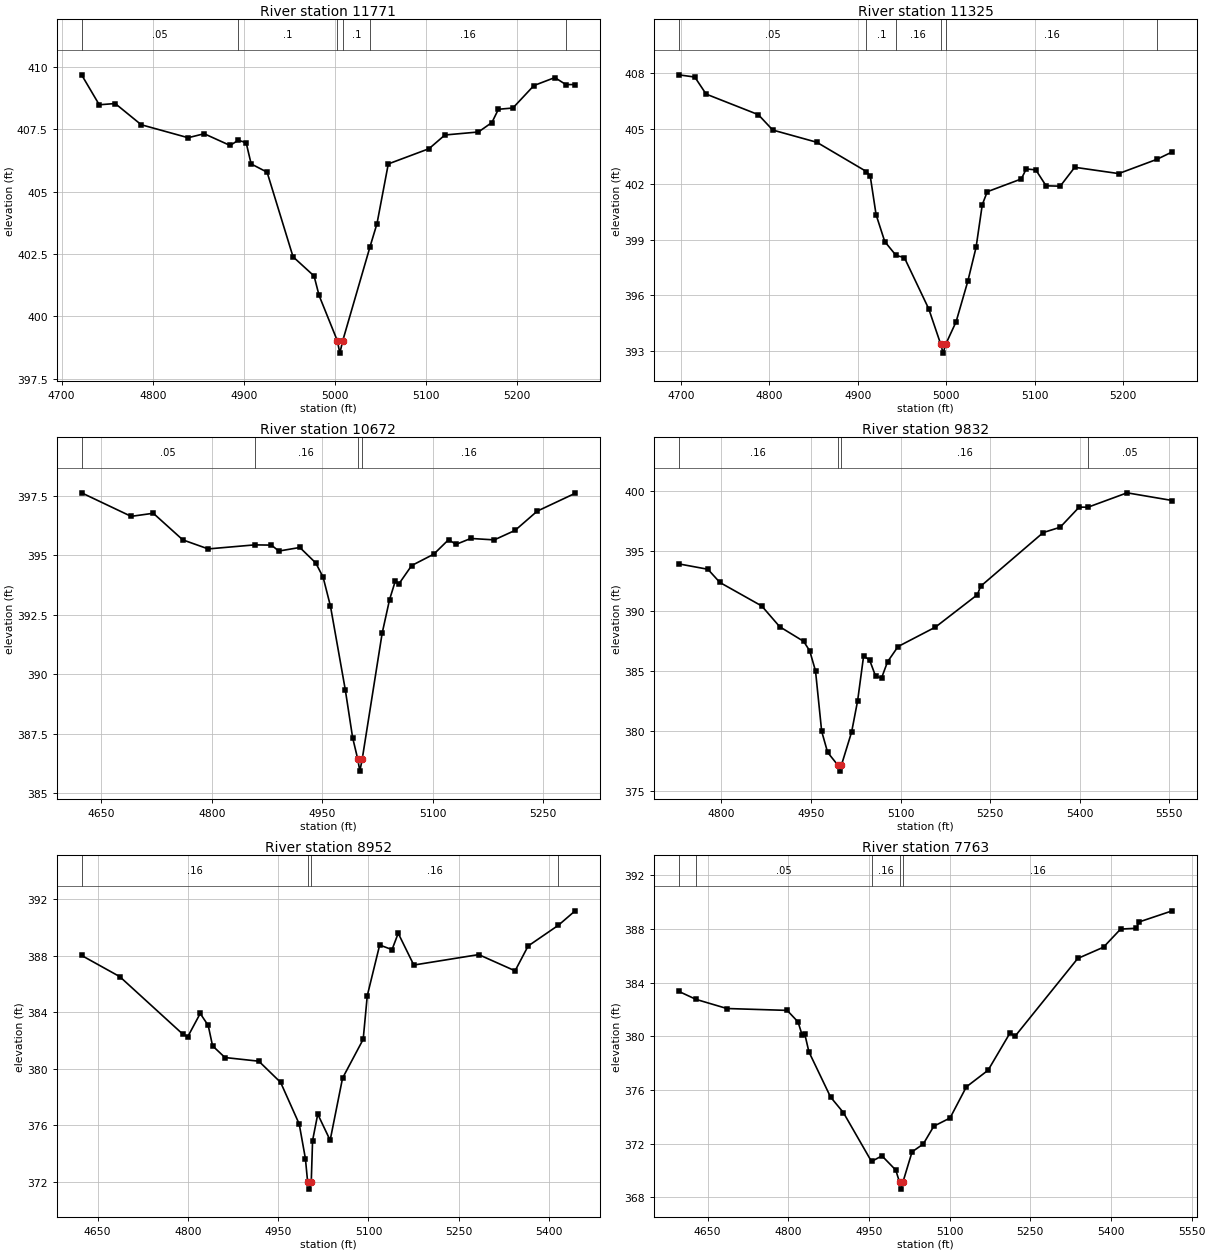
Type RM Length L Ch R = 1,11771,446,446,446
BEGIN DESCRIPTION:
STEELE CREEK TRIB 25 21.0
END DESCRIPTION:
XS GIS Cut Line= 2
      3512625.64     10455970.34      3513118.76     10456195.27
#Sta/Elev= 30
  4721.9  409.68  4741.3  408.48  4758.8  408.53  4787.4  407.68  4838.9  407.16
  4856.5  407.32  4885.0  406.85  4894.0  407.06  4902.6  406.96  4908.1  406.11
  4925.6  405.78  4954.1  402.39  4977.2  401.62  4982.7  400.84  5002.7  399.03
  5005.5  398.53  5008.7  399.03  5038.7  402.80  5046.3  403.72  5058.7  406.11
  5103.4  406.72  5120.9  407.27  5157.7  407.39  5172.5  407.77  5179.6  408.30
  5195.5  408.35  5218.6  409.25  5241.6  409.57  5253.7  409.29  5263.9  409.29
#Mann=6,-1,0
  4721.9    0.05       0  4894.0     0.1       0  5002.7    0.07       0
  5008.7     0.1       0  5038.7    0.16       0  5253.7    0.05       0
Bank Sta=5002.7,5008.7
Exp/Cntr=0.3,0.1

Type RM Length L Ch R = 1,11325,653,653,653
BEGIN DESCRIPTION:
STEELE CREEK TRIB 25 20.0
END DESCRIPTION:
XS GIS Cut Line= 2
      3512434.66     10456326.23      3512928.27     10456586.03
#Sta/Elev= 30
  4697.6  407.90  4715.8  407.78  4728.6  406.86  4787.6  405.75  4803.9  404.92
  4853.7  404.26  4909.8  402.68  4914.1  402.43  4920.7  400.35  4930.5  398.90
  4943.3  398.15  4952.6  398.04  4980.2  395.27  4993.6  393.38  4996.4  392.88
  4999.6  393.38  5011.1  394.57  5024.3  396.75  5033.7  398.59  5040.7  400.89
  5046.3  401.59  5084.8  402.28  5090.4  402.82  5101.2  402.77  5112.8  401.91
  5128.8  401.89  5145.2  402.91  5194.9  402.57  5238.1  403.34  5255.4  403.74
#Mann=6,-1,0
  4697.6    0.05       0  4909.8     0.1       0  4943.3    0.16       0
  4993.6    0.07       0  4999.6    0.16       0  5238.1    0.05       0
Bank Sta=4993.6,4999.6
Exp/Cntr=0.3,0.1

Type RM Length L Ch R = 1,10672,840,840,840
BEGIN DESCRIPTION:
STEELE CREEK TRIB 25 19.0
END DESCRIPTION:
XS GIS Cut Line= 2
      3512235.01     10457003.33      3512903.49     10457055.42
#Sta/Elev= 30
  4623.0  397.63  4690.3  396.64  4720.4  396.77  4760.5  395.65  4795.0  395.27
  4858.2  395.44  4880.9  395.43  4890.9  395.18  4919.5  395.33  4941.1  394.68
  4951.1  394.08  4961.1  392.86  4981.2  389.35  4991.2  387.33  4998.2  386.42
  5001.0  385.92  5004.2  386.42  5031.3  391.72  5041.4  393.14  5049.1  393.91
  5054.1  393.80  5071.4  394.57  5101.5  395.05  5121.6  395.66  5131.6  395.46
  5151.7  395.71  5183.6  395.65  5211.9  396.05  5242.0  396.86  5293.5  397.61
#Mann=4,-1,0
  4623.0    0.05       0  4858.2    0.16       0  4998.2    0.07       0
  5004.2    0.16       0
Bank Sta=4998.2,5004.2
Exp/Cntr=0.3,0.1

Type RM Length L Ch R = 1,9832,880,880,880
BEGIN DESCRIPTION:
STEELE CREEK TRIB 25 17.0
END DESCRIPTION:
XS GIS Cut Line= 2
      3511983.33     10457723.82      3512807.50     10457663.09
#Sta/Elev= 30
  4728.6  393.93  4777.5  393.48  4797.6  392.38  4867.7  390.42  4897.8  388.69
  4937.9  387.47  4948.0  386.68  4957.7  385.01  4968.0  379.98  4978.0  378.22
  4995.1  377.16  4997.9  376.66  5001.1  377.16  5018.2  379.93  5028.2  382.52
  5038.2  386.24  5048.2  385.93  5058.3  384.57  5068.3  384.42  5078.3  385.77
  5095.9  387.04  5158.5  388.66  5228.7  391.36  5234.1  392.06  5339.0  396.54
  5367.3  396.98  5399.2  398.66  5413.8  398.65  5479.4  399.85  5555.0  399.21
#Mann=4,-1,0
  4728.6    0.16       0  4995.1    0.07       0  5001.1    0.16       0
  5413.8    0.05       0
Bank Sta=4995.1,5001.1
Exp/Cntr=0.3,0.1

Type RM Length L Ch R = 1,8952,1189,1189,1189
BEGIN DESCRIPTION:
STEELE CREEK TRIB 25 15.0
END DESCRIPTION:
XS GIS Cut Line= 2
      3511870.43     10458505.08      3512668.04     10458314.34
#Sta/Elev= 30
  4623.3  388.03  4686.7  386.53  4791.6  382.45  4799.8  382.28  4820.4  383.92
  4833.7  383.07  4840.9  381.63  4861.5  380.80  4917.8  380.54  4954.0  379.04
  4984.9  376.09  4995.2  373.64  4998.9  371.98  5001.7  371.48  5004.9  371.98
  5007.1  374.92  5015.7  376.79  5036.3  374.94  5056.9  379.34  5091.2  382.09
  5098.0  385.18  5118.6  388.77  5139.1  388.44  5149.4  389.60  5175.3  387.35
  5283.1  388.09  5343.6  386.94  5365.3  388.70  5415.6  390.17  5443.4  391.19
#Mann=4,-1,0
  4623.3    0.16       0  4998.9    0.07       0  5004.9    0.16       0
  5415.6     0.1       0
Bank Sta=4998.9,5004.9
Exp/Cntr=0.3,0.1

Type RM Length L Ch R = 1,7763,255,255,255
BEGIN DESCRIPTION:
STEELE CREEK TRIB 25 12.0
END DESCRIPTION:
XS GIS Cut Line= 4
      3512078.78     10459130.07      3512226.36     10459242.92
      3512790.59     10459164.79      3512834.00     10459008.51
#Sta/Elev= 30
  4596.3  383.35  4628.6  382.75  4685.9  382.07  4798.0  381.93  4818.2  381.07
  4825.5  380.13  4830.6  380.19  4838.4  378.84  4878.7  375.47  4902.4  374.32
  4954.8  370.67  4974.2  371.09  4999.9  370.03  5007.0  369.11  5009.7  368.61
  5013.0  369.11  5030.2  371.39  5051.0  371.97  5070.6  373.30  5100.8  373.91
  5131.1  376.23  5171.5  377.47  5211.9  380.22  5222.0  380.02  5338.2  385.80
  5386.1  386.64  5417.9  387.99  5447.0  388.05  5452.2  388.52  5513.9  389.35
#Mann=5,-1,0
  4596.3    0.16       0  4628.6    0.05       0  4954.8    0.16       0
  5007.0    0.07       0  5013.0    0.16       0
Bank Sta=5007,5013
Exp/Cntr=0.3,0.1

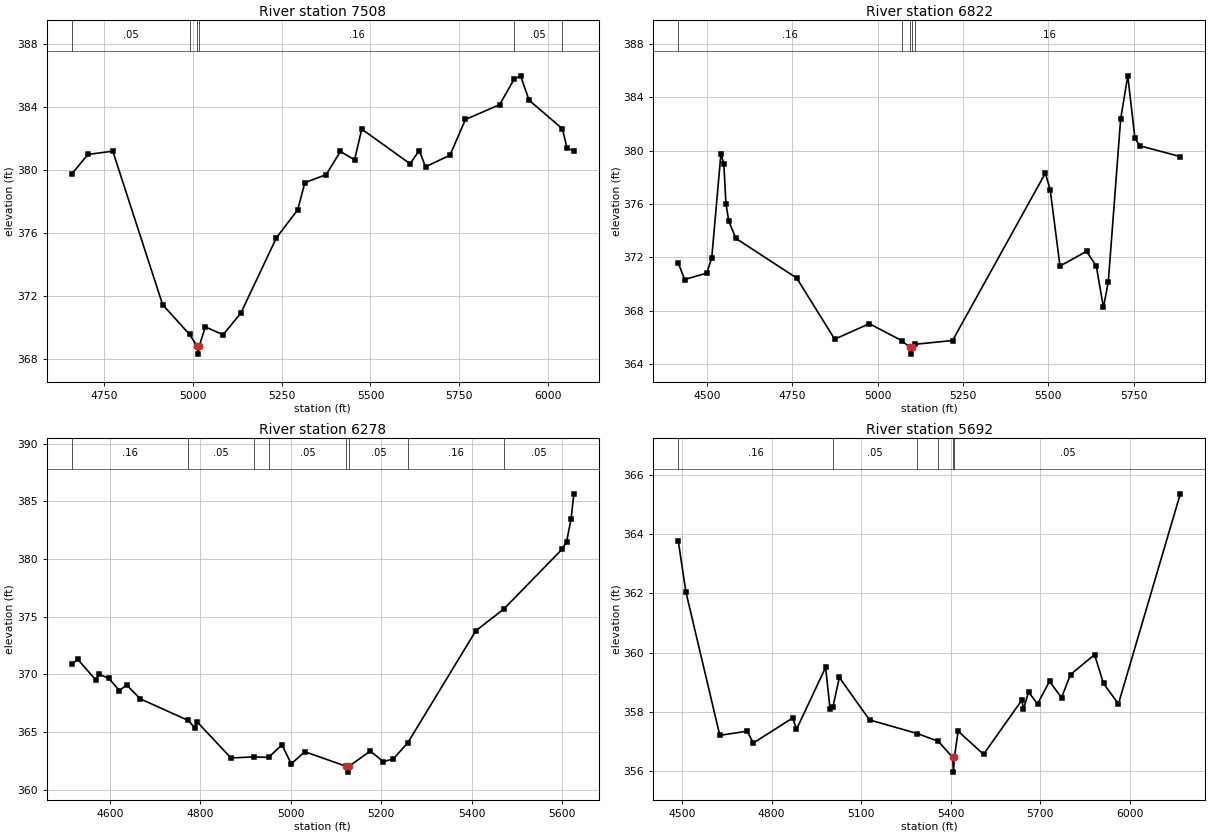
Type RM Length L Ch R = 1,7508,686,686,686
BEGIN DESCRIPTION:
Mapping XS 98382538
END DESCRIPTION:
XS GIS Cut Line= 3
      3512096.66     10459431.78      3513049.30     10459423.10
      3513474.65     10459249.49
#Sta/Elev= 30
  4659.9  379.72  4705.3  380.96  4775.3  381.17  4915.4  371.43  4991.2  369.54
  5012.4  368.79  5015.1  368.29  5018.4  368.79  5035.4  370.02  5085.4  369.52
  5135.4  370.89  5235.4  375.67  5295.4  377.45  5315.4  379.17  5375.4  379.68
  5415.4  381.15  5455.4  380.62  5475.4  382.57  5611.5  380.37  5637.2  381.21
  5654.8  380.18  5723.6  380.91  5767.1  383.18  5863.2  384.12  5904.0  385.73
  5922.1  385.95  5946.1  384.40  6039.8  382.59  6053.1  381.34  6072.0  381.21
#Mann=6,-1,0
  4659.9    0.05       0  4991.2    0.16       0  5012.4    0.07       0
  5018.4    0.16       0  5904.0    0.05       0  6039.8    0.16       0
Bank Sta=5012.4,5018.4
Exp/Cntr=0.3,0.1

Type RM Length L Ch R = 1,6822,544,544,544
BEGIN DESCRIPTION:
STEELE CREEK TRIB 25 11.0
END DESCRIPTION:
XS GIS Cut Line= 4
      3512321.83     10459685.62      3512590.94     10459885.28
      3513207.26     10459998.13      3513594.61     10459667.08
#Sta/Elev= 30
  4415.7  371.58  4434.5  370.34  4499.2  370.82  4513.8  371.95  4540.8  379.75
  4549.2  379.03  4555.5  376.02  4563.9  374.70  4584.7  373.42  4762.8  370.45
  4874.2  365.87  4975.5  367.03  5070.1  365.77  5094.6  365.25  5097.4  364.75
  5100.6  365.25  5110.6  365.49  5219.6  365.77  5491.5  378.31  5505.7  377.05
  5534.3  371.35  5612.2  372.45  5640.8  371.34  5661.6  368.25  5675.9  370.17
  5712.1  382.37  5733.0  385.60  5753.8  380.94  5768.1  380.36  5886.9  379.55
#Mann=5,-1,0
  4415.7    0.16       0  5070.1     0.1       0  5094.6    0.07       0
  5100.6     0.1       0  5110.6    0.16       0
Bank Sta=5094.6,5100.6
Exp/Cntr=0.3,0.1

Type RM Length L Ch R = 1,6278,586,586,586
BEGIN DESCRIPTION:
Mapping XS aa1e6e07
END DESCRIPTION:
XS GIS Cut Line= 4
      3512523.25     10459981.23      3512666.49     10460296.36
      3513093.57     10460397.93      3513418.07     10460369.37
#Sta/Elev= 30
  4515.2  370.86  4528.3  371.30  4569.0  369.48  4574.5  370.02  4597.5  369.64
  4620.6  368.58  4636.5  369.08  4666.7  367.87  4772.5  366.00  4787.6  365.35
  4793.1  365.85  4867.4  362.74  4917.5  362.83  4950.8  362.79  4980.2  363.88
  5000.8  362.23  5031.0  363.28  5122.6  362.01  5125.3  361.51  5128.6  362.01
  5175.5  363.34  5204.8  362.42  5226.9  362.66  5258.9  364.07  5409.3  373.78
  5471.1  375.66  5600.0  380.85  5610.1  381.51  5620.1  383.51  5626.1  385.66
#Mann=8,-1,0
  4515.2    0.16       0  4772.5    0.05       0  4917.5     0.1       0
  4950.8    0.05       0  5122.6    0.03       0  5128.6    0.05       0
  5258.9    0.16       0  5471.1    0.05       0
Bank Sta=5122.6,5128.6
Exp/Cntr=0.3,0.1

Type RM Length L Ch R = 1,5692,0,0,0
BEGIN DESCRIPTION:
STEELE CREEK TRIB 25 1.0
END DESCRIPTION:
XS GIS Cut Line= 4
      3512322.73     10460015.16      3512239.41     10460439.59
      3512447.74     10460785.95      3513288.01     10460707.90
#Sta/Elev= 30
  4487.7  363.77  4513.2  362.05  4626.8  357.21  4718.5  357.35  4738.9  356.95
  4871.4  357.80  4883.5  357.41  4981.0  359.50  4995.9  358.10  5005.1  358.15
  5027.0  359.16  5128.0  357.73  5288.2  357.27  5357.8  357.01  5406.1  356.47
  5408.9  355.97  5412.1  356.47  5424.6  357.35  5509.6  356.57  5638.2  358.40
  5643.2  358.09  5660.2  358.67  5690.3  358.27  5730.5  359.03  5770.7  358.48
  5800.8  359.26  5881.2  359.93  5911.3  358.96  5961.1  358.27  6168.3  365.35
#Mann=6,-1,0
  4487.7    0.16       0  5005.1    0.05       0  5288.2    0.16       0
  5357.8    0.05       0  5406.1    0.07       0  5412.1    0.05       0
Bank Sta=5406.1,5412.1
Exp/Cntr=0.3,0.1

Chan Stop Cuts=-1