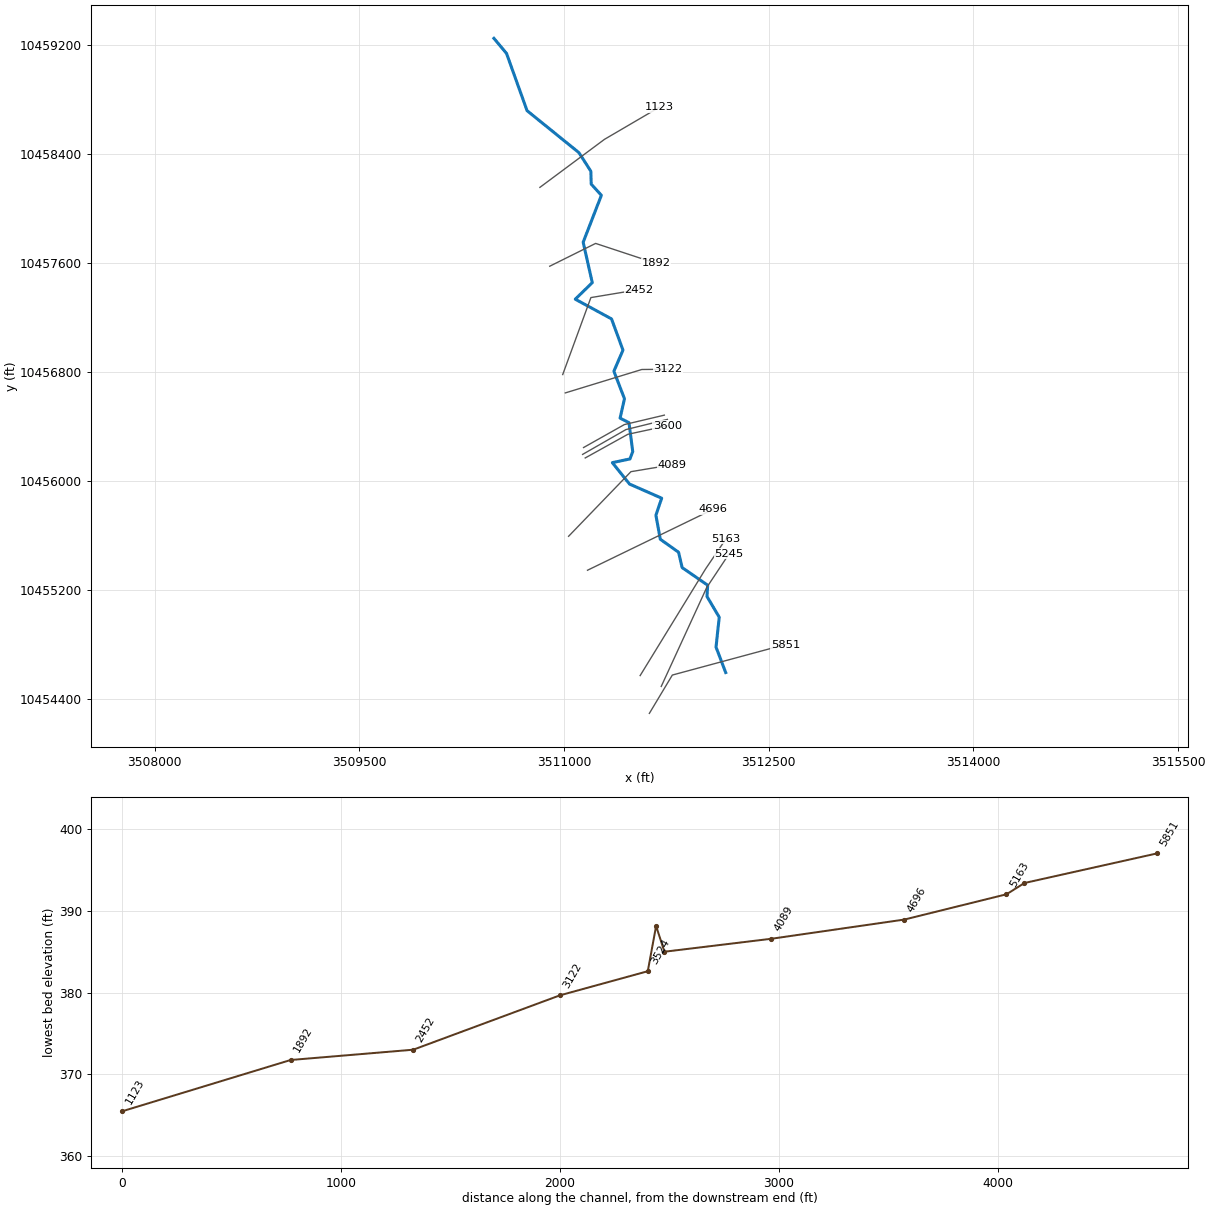
--- STEELE CREEK TRIB 26.prj (project) ---

Proj Title=STEELE CREEK TRIB 26 Base Level Engineering
Current Plan=p01
Default Exp/Contr=0.3,0.1
English Units
Geom File=g01
Flow File=f01
Plan File=p01
Y Axis Title=Elevation
X Axis Title(PF)=Main Channel Distance
X Axis Title(XS)=Station
BEGIN DESCRIPTION:
STEELE CREEK TRIB 26
END DESCRIPTION:
DSS Export Rating Curves= 0
DSS Export Rating Curve Sorted= 0
DSS Export Volume Flow Curves= 0
DXF OffsetX= 0
DXF OffsetY= 0
DXF ScaleX= 1
DXF ScaleY= 10

--- STEELE CREEK TRIB 26.p01 (plan) ---

Plan Title=Multiple Run
Short Identifier=Multiple
Geom File=g01
Flow File=f01
Subcritical Flow
K Sum by GR= 0
Std Step Tol= 0.01
Critical Tol= 0.01
Num of Std Step Trials= 20
Max Error Tol= 0.3
Flow Tol Ratio= 0.001
Split Flow NTrial= 30
Split Flow Tol= 0.02
Split Flow Ratio= 0.02
Log Output Level= 0
Friction Slope Method= 1
Unsteady Friction Slope Method= 2
Unsteady Bridges Friction Slope Method= 1
Parabolic Critical Depth
Global Vel Dist=  1 , 1 , 1
Global Log Level= 0
CheckData=True
Encroach Param= -1, 0, 0, 0
BEGIN DESCRIPTION:
Multiple Run
END DESCRIPTION:

--- STEELE CREEK TRIB 26.f01 (steady flow) ---

Flow Title=Multiple
Number of Profiles=7
Profile Names=10-year,25-year,50-year,1pct_min,100-year,1pct_plu,500-year
River Rch & RM= STEELE CREEK TRI,Reach-1,5851
     400     522     618     535     723     978     988
Boundary for River Rch & Prof#=STEELE CREEK TRI,Reach-1,1
Up Type=0
Dn Type=3
Dn Slope=0.005
Boundary for River Rch & Prof#=STEELE CREEK TRI,Reach-1,2
Up Type=0
Dn Type=3
Dn Slope=0.005
Boundary for River Rch & Prof#=STEELE CREEK TRI,Reach-1,3
Up Type=0
Dn Type=3
Dn Slope=0.005
Boundary for River Rch & Prof#=STEELE CREEK TRI,Reach-1,4
Up Type=0
Dn Type=3
Dn Slope=0.005
Boundary for River Rch & Prof#=STEELE CREEK TRI,Reach-1,5
Up Type=0
Dn Type=3
Dn Slope=0.005
Boundary for River Rch & Prof#=STEELE CREEK TRI,Reach-1,6
Up Type=0
Dn Type=3
Dn Slope=0.005
Boundary for River Rch & Prof#=STEELE CREEK TRI,Reach-1,7
Up Type=0
Dn Type=3
Dn Slope=0.005

--- STEELE CREEK TRIB 26.g01 (geometry) ---

Geom Title=Existing Conditions
Program Version=4.10

River Reach=STEELE CREEK TRI,Reach-1
Reach XY= 30
      3512184.52     10454596.67      3512113.68     10454783.12
      3512137.12     10455002.92      3512047.54     10455154.48
      3512052.22     10455237.81      3511865.25     10455366.98
       3511839.2     10455479.48      3511705.18     10455575.03
      3511673.06     10455751.35      3511715.25     10455876.35
      3511479.83       10455980.      3511353.79     10456137.29
       3511482.6     10456164.39      3511503.27     10456218.02
      3511475.66     10456430.69      3511410.38     10456463.68
      3511442.68     10456606.04      3511364.98      10456808.3
      3511431.65     10456962.98       3511347.8     10457192.15
      3511082.17     10457336.94      3511206.65      10457458.3
      3511139.98     10457754.65      3511273.32     10458099.44
      3511198.84     10458181.73      3511196.23     10458276.01
      3511108.93     10458412.44      3510728.67     10458720.62
       3510578.3     10459140.61      3510485.94      10459251.5

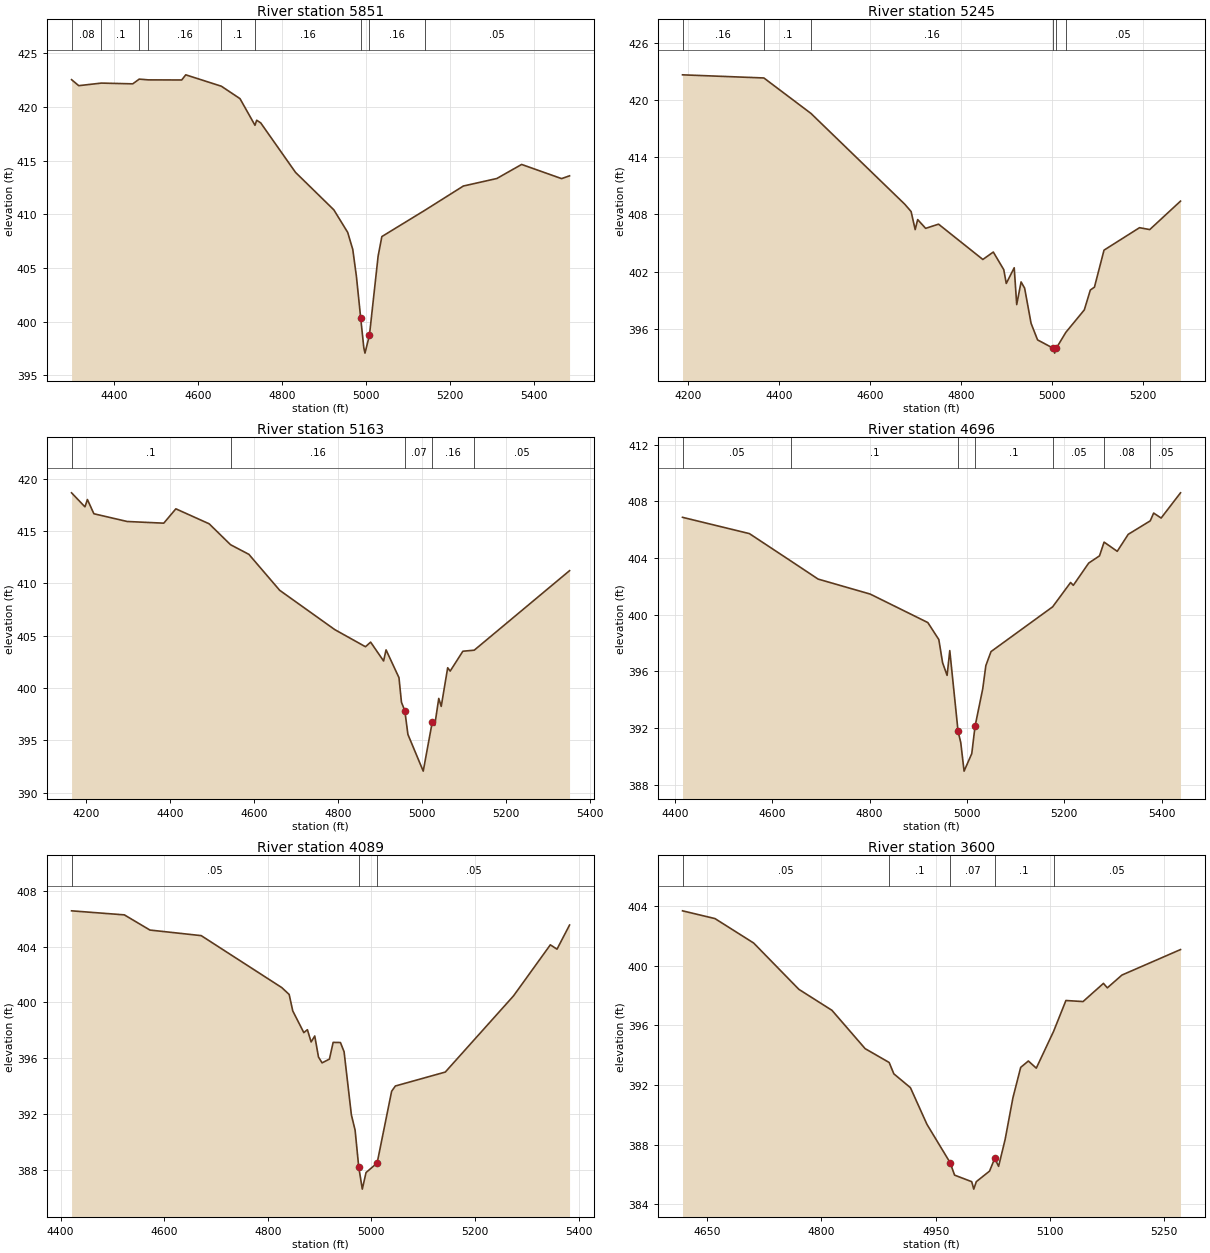
Type RM Length L Ch R = 1 ,5851    ,606,606,606
BEGIN DESCRIPTION:
STEELE CREEK TRIB 26 12.0
END DESCRIPTION:
XS GIS Cut Line= 3
      3511625.07     10454296.95      3511793.47     10454578.21
      3512622.36     10454802.42
#Sta/Elev= 30
    4298  422.54  4315.1  421.98  4369.1  422.22  4443.7  422.15  4459.3  422.59
  4480.8  422.52  4560.4  422.51  4570.1  422.99  4654.8  421.93  4699.3  420.77
    4735  418.29  4739.1  418.76  4748.7  418.51  4831.6   413.9  4922.9  410.41
  4955.9  408.31    4968  406.72  4976.6  404.24    4987  400.29  4994.3  397.56
  4997.1  397.06  5007.8  398.75  5028.4   406.1  5037.3  407.92  5140.2  410.38
  5231.5  412.63  5311.2  413.33  5370.3  414.64  5465.5  413.32  5484.5  413.58
#Mann= 9 ,-1 , 0
    4298     .08       0  4369.1      .1       0  4459.3     .08       0
  4480.8     .16       0  4654.8      .1       0    4735     .16       0
    4987     .07       0  5007.8     .16       0  5140.2     .05       0
Bank Sta=4987,5007.8
XS Rating Curve= 0 ,0
Exp/Cntr=0.3,0.1

Type RM Length L Ch R = 1 ,5245    ,82,82,82
BEGIN DESCRIPTION:
Mapping XS a506b83e
END DESCRIPTION:
XS GIS Cut Line= 3
      3511712.06     10454494.65      3512045.58     10455221.09
      3512209.43     10455468.04
#Sta/Elev= 30
  4187.3  422.67  4366.3  422.34    4470  418.61  4676.2  409.08  4690.2  408.31
  4699.2  406.41  4704.7  407.46  4722.2  406.54  4750.6  406.98  4848.1  403.27
  4871.1  404.05  4894.1   402.2  4899.6  400.75  4917.1   402.4  4922.6  398.53
  4932.2  400.91    4940  400.26  4954.2  396.56  4968.5  394.82  5003.4  393.93
  5006.1  393.43  5009.4  393.93  5030.8  395.62  5071.3  397.97  5084.6  400.06
  5093.6  400.36  5114.7  404.25  5192.8  406.61  5215.3  406.41    5283   409.4
#Mann= 6 ,-1 , 0
  4187.3     .16       0  4366.3      .1       0    4470     .16       0
  5003.4     .07       0  5009.4     .16       0  5030.8     .05       0
Bank Sta=5003.4,5009.4
XS Rating Curve= 0 ,0
Exp/Cntr=0.3,0.1

Type RM Length L Ch R = 1 ,5163    ,467,467,467
BEGIN DESCRIPTION:
Mapping XS dc3ba0eb
END DESCRIPTION:
XS GIS Cut Line= 3
      3511557.49     10454574.22      3512036.43      10455356.2
      3512187.75     10455579.94
#Sta/Elev= 30
  4164.9  418.65  4196.8  417.31  4202.7  418.01  4218.1  416.65  4297.5  415.91
  4384.7  415.75  4413.5  417.12  4492.9  415.69  4543.9  413.69  4587.6  412.77
  4661.1  409.33  4792.6  405.57  4865.5  403.94  4877.8  404.38  4908.7  402.58
  4914.6  403.64  4945.4  400.98  4951.3  398.63  4959.3  397.83  4966.7  395.56
  5003.2  392.05  5024.8  396.76  5030.6  396.42  5040.2     399  5046.1  398.24
  5061.5  401.93  5067.4  401.61  5097.7  403.51  5124.8  403.61    5352  411.21
#Mann= 5 ,-1 , 0
  4164.9      .1       0  4543.9     .16       0  4959.3     .07       0
  5024.8     .16       0  5124.8     .05       0
Bank Sta=4959.3,5024.8
XS Rating Curve= 0 ,0
Exp/Cntr=0.3,0.1

Type RM Length L Ch R = 1 ,4696    ,607,607,607
BEGIN DESCRIPTION:
Mapping XS 0997a4dc
END DESCRIPTION:
XS GIS Cut Line= 2
      3511171.61     10455347.51      3512091.76     10455794.57
#Sta/Elev= 30
  4415.7  406.87  4553.1  405.72  4637.7   403.8  4694.2  402.51  4801.3  401.45
  4919.6  399.44  4942.2  398.24  4949.9  396.61  4959.2  395.71  4964.7  397.46
  4981.7  391.77  4987.3  390.96  4994.1  388.95  5009.9  390.19  5016.6  392.11
  5032.4  394.76  5038.8   396.4  5049.4  397.39    5176  400.55  5212.9  402.27
  5218.5  402.07  5250.1  403.64  5272.3  404.15  5281.7  405.12  5308.7  404.47
  5331.3  405.67  5376.5  406.62  5383.5  407.17  5398.9  406.82  5438.7   408.6
#Mann= 7 ,-1 , 0
  4415.7     .05       0  4637.7      .1       0  4981.7     .05       0
  5016.6      .1       0    5176     .05       0  5281.7     .08       0
  5376.5     .05       0
Bank Sta=4981.7,5016.6
XS Rating Curve= 0 ,0
Exp/Cntr=0.3,0.1

Type RM Length L Ch R = 1 ,4089    ,489,489,489
BEGIN DESCRIPTION:
Mapping XS 0091ed32
END DESCRIPTION:
XS GIS Cut Line= 3
      3511033.13     10455596.72      3511489.94     10456070.93
      3511788.72     10456121.02
#Sta/Elev= 30
  4421.2  406.57  4523.1  406.28  4572.5  405.19  4671.5  404.79  4827.1  401.06
  4841.3  400.57  4848.2  399.39  4869.6  397.83  4876.5  398.04  4883.7  397.16
  4890.7  397.59  4897.9  396.08  4904.8  395.66    4919  395.93  4926.2  397.13
  4940.3  397.12  4947.3  396.46  4961.4  391.93  4968.6  390.83  4975.6  388.19
  4982.5   386.6  4989.7  387.79  5011.1  388.47  5039.1  393.62  5046.3     394
  5142.7     395  5274.5  400.47  5345.5  404.13  5358.4  403.82  5382.6  405.55
#Mann= 3 , 0 , 0
  4421.2     .05       0  4975.6    .035       0  5011.1     .05       0
Bank Sta=4975.6,5011.1
XS Rating Curve= 0 ,0
Exp/Cntr=0.3,0.1

Type RM Length L Ch R = 1 ,3600    ,38,38,38
BEGIN DESCRIPTION:
Mapping XS 15f47232
END DESCRIPTION:
XS GIS Cut Line= 3
      3511154.89     10456171.64      3511467.37     10456345.24
      3511757.25     10456407.73
#Sta/Elev= 30
  4617.5  403.69  4660.1  403.17  4710.9  401.53  4770.3  398.42  4813.8  397.01
  4857.3  394.44  4888.9  393.51    4895  392.75  4916.8  391.82  4938.5  389.36
  4968.9  386.79  4974.8  385.95  4997.3  385.51    5000  385.01  5003.3  385.51
  5020.7  386.22  5027.5  387.07  5032.6  386.54  5041.2  388.35  5051.4  391.14
  5061.6  393.18  5071.7  393.61  5082.1  393.13  5104.9  395.61    5121  397.67
  5143.5   397.6  5170.3  398.82  5175.4  398.52  5194.6  399.38  5271.5  401.09
#Mann= 5 ,-1 , 0
  4617.5     .05       0  4888.9      .1       0  4968.9     .07       0
  5027.5      .1       0  5104.9     .05       0
Bank Sta=4968.9,5027.5
XS Rating Curve= 0 ,0
Exp/Cntr=0.3,0.1

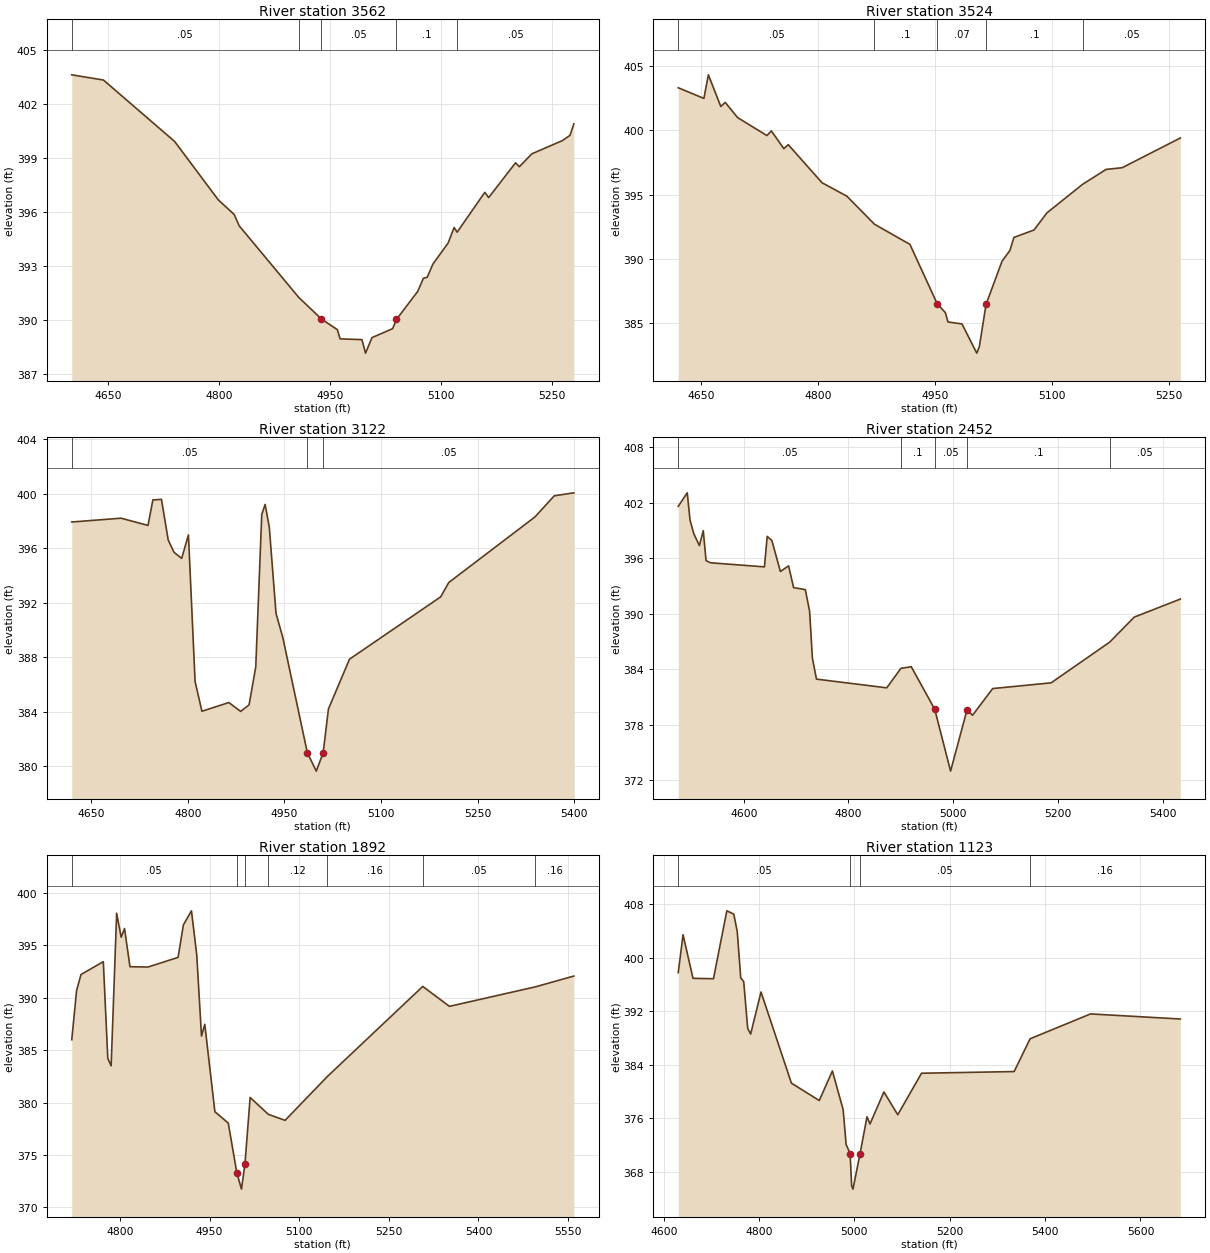
Type RM Length L Ch R = 1 ,3562    ,38,38,38
BEGIN DESCRIPTION:
Mapping XS 9df2d2c5
END DESCRIPTION:
XS GIS Cut Line= 3
      3511135.81     10456197.69      3511453.48     10456379.96
       3511757.2     10456454.59
#Sta/Elev= 30
  4600.4  403.61  4643.3  403.32  4739.6  399.91  4798.6  396.67  4820.1  395.86
  4826.7  395.24  4907.4  391.26  4938.1  390.06  4959.6  389.47  4963.3  388.96
  4992.8  388.92  4997.7  388.17  5006.4  389.03  5034.4  389.53  5039.5  390.04
  5068.2  391.59  5075.9  392.32  5081.1  392.38  5088.8  393.11  5109.4  394.28
  5117.5  395.14  5121.6  394.88    5159  397.09  5164.2   396.8  5200.6  398.73
  5205.7  398.51  5222.7  399.23  5263.9  399.96  5274.2  400.25  5279.4  400.89
#Mann= 5 ,-1 , 0
  4600.4     .05       0  4907.4      .1       0  4938.1     .05       0
  5039.5      .1       0  5121.6     .05       0
Bank Sta=4938.1,5039.5
XS Rating Curve= 0 ,0
Exp/Cntr=0.3,0.1

Type RM Length L Ch R = 1 ,3524    ,402,402,402
BEGIN DESCRIPTION:
Mapping XS 98f708e2
END DESCRIPTION:
XS GIS Cut Line= 3
      3511142.76     10456248.04      3511441.33     10456416.42
      3511734.75     10456485.87
#Sta/Elev= 30
  4620.2  403.33  4653.1   402.5  4658.9  404.34  4674.8  401.87  4680.5  402.19
  4696.4     401    4734   399.6  4739.7  399.96  4755.7  398.58  4761.4  398.89
  4804.7  395.92  4836.6  394.87    4872  392.68  4917.5  391.11  4952.4  386.49
    4963  385.78  4966.4  385.05  4984.3   384.9  5003.3  382.62  5006.6  383.12
  5015.2  386.42  5035.7  389.79  5045.8  390.63    5051  391.65  5076.8  392.23
  5093.2  393.56    5139  395.79  5169.3  396.96  5189.9  397.09  5264.5  399.41
#Mann= 5 ,-1 , 0
  4620.2     .05       0    4872      .1       0  4952.4     .07       0
  5015.2      .1       0    5139     .05       0
Bank Sta=4952.4,5015.2
XS Rating Curve= 0 ,0
Exp/Cntr=0.3,0.1

Type RM Length L Ch R = 1 ,3122    ,670,670,670
BEGIN DESCRIPTION:
Mapping XS 47993801
END DESCRIPTION:
XS GIS Cut Line= 3
        3511009.     10456649.04       3511569.8     10456820.93
      3511762.54     10456822.67
#Sta/Elev= 30
    4620  397.93  4696.5  398.21  4738.3  397.68  4745.9  399.55  4759.2  399.59
  4769.7  396.61  4778.7  395.71  4790.6  395.26  4801.1  396.98  4811.4  386.24
    4822  384.05  4863.8  384.69  4882.1  384.04  4895.2  384.52  4905.6  387.31
  4914.9  398.48  4920.1  399.22  4926.6  397.55    4937  391.23  4947.5  389.47
  4985.6  381.02  4999.5  379.66  5010.2     381  5018.4  384.22  5051.1  387.87
  5192.6  392.44  5205.1  393.49  5338.9   398.3  5368.9  399.85  5399.3  400.07
#Mann= 3 , 0 , 0
    4620     .05       0  4985.6    .035       0  5010.2     .05       0
Bank Sta=4985.6,5010.2
XS Rating Curve= 0 ,0
Exp/Cntr=0.3,0.1

Type RM Length L Ch R = 1 ,2452    ,560,560,560
BEGIN DESCRIPTION:
Mapping XS d2162188
END DESCRIPTION:
XS GIS Cut Line= 3
      3510989.98     10456783.73      3511196.54     10457348.71
      3511548.93     10457407.44
#Sta/Elev= 30
  4474.9  401.61  4492.1  403.07  4497.5  400.11  4504.6  398.65  4515.3  397.37
  4522.7  398.98    4528  395.75  4536.6  395.51  4639.5  395.07  4644.8  398.36
  4653.7  397.92    4670  394.57  4685.6  395.18  4695.2  392.83  4717.6  392.61
  4725.8  390.26  4731.1  385.21  4738.9  382.94  4873.1     382  4900.2  384.11
  4919.9  384.28  4964.7  379.69    4995     373  5026.3   379.6    5037  379.04
  5075.4  381.92    5187  382.54  5299.1  386.95  5345.7  389.64  5433.7  391.59
#Mann= 5 ,-1 , 0
  4474.9     .05       0  4900.2      .1       0  4964.7     .05       0
  5026.3      .1       0  5299.1     .05       0
Bank Sta=4964.7,5026.3
XS Rating Curve= 0 ,0
Exp/Cntr=0.3,0.1

Type RM Length L Ch R = 1 ,1892    ,769,769,769
BEGIN DESCRIPTION:
Mapping XS 99f0a771
END DESCRIPTION:
XS GIS Cut Line= 3
      3510894.87      10457578.9      3511231.26     10457746.28
      3511672.24     10457600.44
#Sta/Elev= 30
  4719.4  385.99  4727.5  390.69  4734.9  392.21  4772.2  393.43  4779.7  384.21
  4785.3   383.5  4794.5  398.05  4802.1  395.76  4807.7  396.59  4816.8  392.95
  4846.9  392.92  4897.3  393.84  4906.2  396.94  4919.7  398.28  4928.5  394.11
  4936.5  386.34    4942  387.46  4958.9  379.12  4981.3  378.04  4995.6   373.3
  5003.4  371.74  5009.2  374.13  5017.9  380.48  5048.4  378.87  5076.4   378.3
  5147.1  382.48  5306.8  391.07  5351.4  389.17  5495.2  391.03  5559.6  392.06
#Mann= 7 ,-1 , 0
  4719.4     .05       0  4995.6    .035       0  5009.2     .05       0
  5048.4     .12       0  5147.1     .16       0  5306.8     .05       0
  5495.2     .16       0
Bank Sta=4995.6,5009.2
XS Rating Curve= 0 ,0
Exp/Cntr=0.3,0.1

Type RM Length L Ch R = 1 ,1123    ,0,0,0
BEGIN DESCRIPTION:
STEELE CREEK TRIB 26 1.0
END DESCRIPTION:
XS GIS Cut Line= 3
      3510822.85     10458157.71      3511296.08     10458510.14
      3511695.52     10458744.18
#Sta/Elev= 30
  4630.5  397.75  4640.6  403.41  4661.5  396.91  4704.4  396.85  4732.4  406.98
    4747  406.49  4754.3  403.87  4761.6  396.96  4767.8  396.44  4776.2  389.44
  4782.4   388.6  4804.1  394.87  4867.9  381.27  4926.3  378.68  4953.8  383.09
  4976.4  377.31  4982.6  372.13    4991  370.76  4994.2  365.96    4997  365.46
  5011.8  370.74  5026.4  376.26  5032.7  375.18  5061.9  379.96  5090.9  376.56
  5140.8  382.75    5335     383  5368.5  387.89  5495.2   391.6  5683.5  390.84
#Mann= 4 ,-1 , 0
  4630.5     .05       0    4991    .035       0  5011.8     .05       0
  5368.5     .16       0
Bank Sta=4991,5011.8
XS Rating Curve= 0 ,0
Exp/Cntr=0.3,0.1

Chan Stop Cuts=-1
Use User Specified Reach Order=0
Composite Channel Slope=5