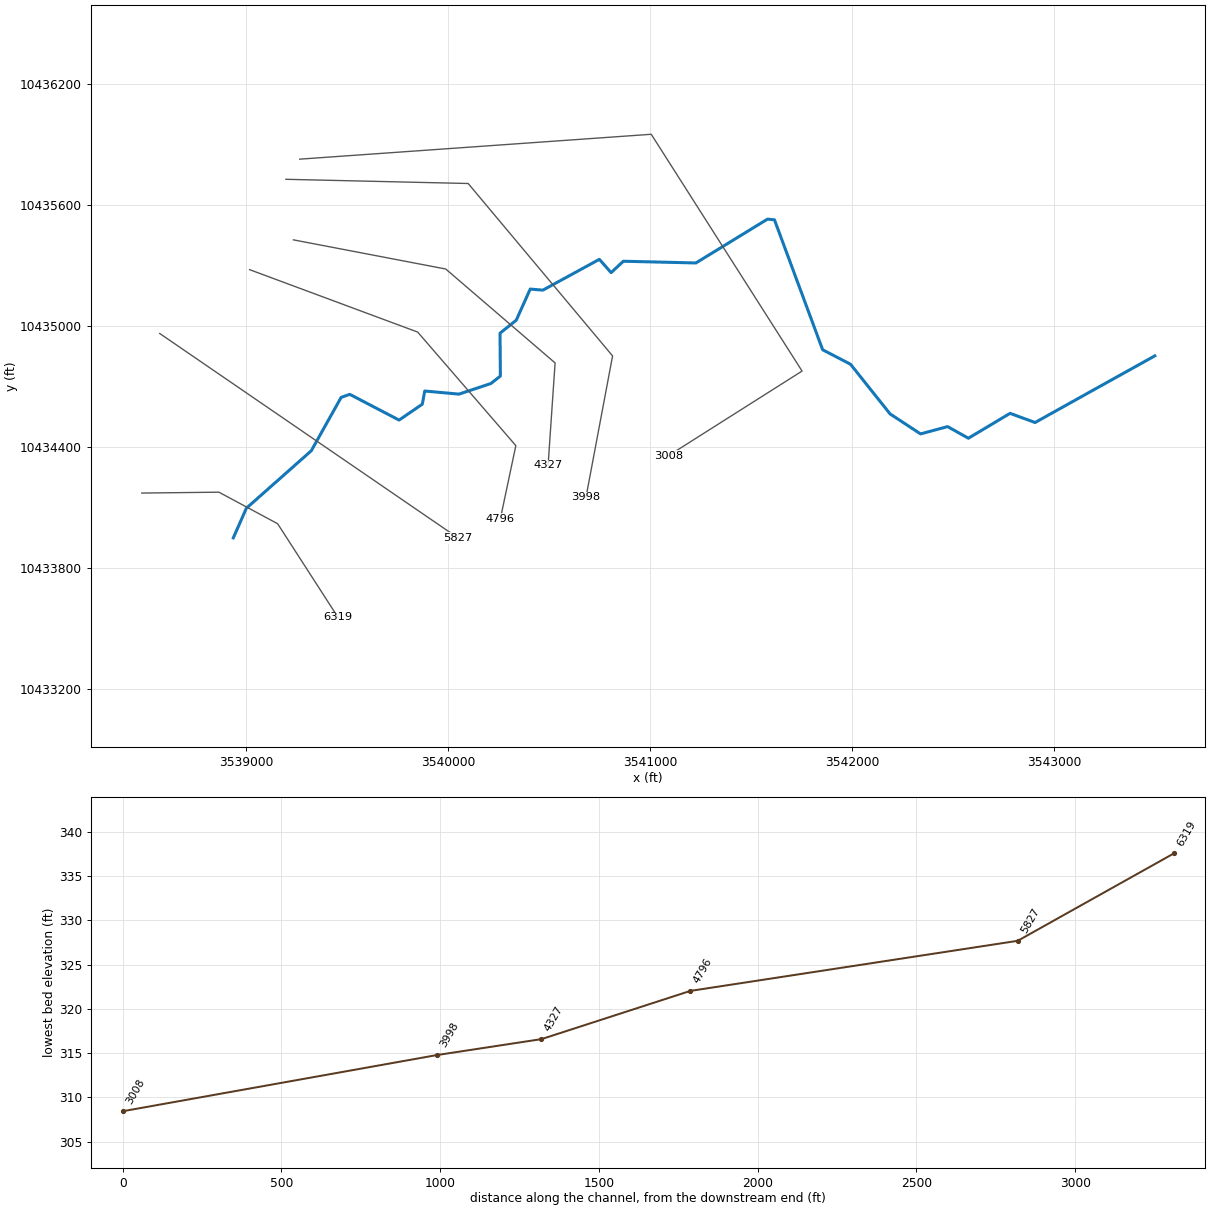
--- STEELE CREEK TRIB 4 1.prj (project) ---

Proj Title=STEELE CREEK TRIB 4 1 Base Level Engineering
Current Plan=p01
Default Exp/Contr=0.3,0.1
English Units
Geom File=g01
Flow File=f01
Plan File=p01
BEGIN DESCRIPTION:
STEELE CREEK TRIB 4 1
END DESCRIPTION:

--- STEELE CREEK TRIB 4 1.p01 (plan) ---

Plan Title=Multiple Run
Short Identifier=Multiple
Geom File=g01
Flow File=f01
Subcritical Flow
K Sum by GR= 0
Std Step Tol= 0.01
Critical Tol= 0.01
Num of Std Step Trials= 20
Max Error Tol= 0.3
Flow Tol Ratio= 0.001
Split Flow NTrial= 30
Split Flow Tol= 0.02
Split Flow Ratio= 0.02
Log Output Level= 0
Friction Slope Method= 1
Unsteady Friction Slope Method= 2
Unsteady Bridges Friction Slope Method= 1
Parabolic Critical Depth
Global Vel Dist=  1 , 1 , 1
Global Log Level= 0
CheckData=True
Encroach Param= -1, 0, 0, 0
BEGIN DESCRIPTION:
Multiple Run
END DESCRIPTION:

--- STEELE CREEK TRIB 4 1.f01 (steady flow) ---

Flow Title=Multiple
Number of Profiles=7
Profile Names=10-year,25-year,50-year,1pct_min,100-year,1pct_plu,500-year
River Rch & RM= STEELE CREEK TRI,Reach-1,6319
     796    1091    1335    1195    1616    2185    2357
Boundary for River Rch & Prof#=STEELE CREEK TRI,Reach-1,1
Up Type=0
Dn Type=3
Dn Slope=0.005
Boundary for River Rch & Prof#=STEELE CREEK TRI,Reach-1,2
Up Type=0
Dn Type=3
Dn Slope=0.005
Boundary for River Rch & Prof#=STEELE CREEK TRI,Reach-1,3
Up Type=0
Dn Type=3
Dn Slope=0.005
Boundary for River Rch & Prof#=STEELE CREEK TRI,Reach-1,4
Up Type=0
Dn Type=3
Dn Slope=0.005
Boundary for River Rch & Prof#=STEELE CREEK TRI,Reach-1,5
Up Type=0
Dn Type=3
Dn Slope=0.005
Boundary for River Rch & Prof#=STEELE CREEK TRI,Reach-1,6
Up Type=0
Dn Type=3
Dn Slope=0.005
Boundary for River Rch & Prof#=STEELE CREEK TRI,Reach-1,7
Up Type=0
Dn Type=3
Dn Slope=0.005

--- STEELE CREEK TRIB 4 1.g01 (geometry) ---

Geom Title=Existing Conditions

River Reach=STEELE CREEK TRI,Reach-1
Reach XY= 30
      3538935.07     10433950.58      3538999.88     10434097.51
      3539321.23     10434382.00      3539469.31     10434646.64
      3539512.11     10434661.64      3539756.32     10434534.19
      3539871.18     10434612.74      3539883.42     10434678.25
      3540052.75     10434662.73      3540210.97     10434715.25
      3540258.04     10434752.32      3540256.32     10434964.64
      3540336.68     10435028.96      3540405.91     10435183.11
      3540468.72     10435177.87      3540748.45     10435330.52
      3540806.60     10435264.59      3540867.22     10435321.09
      3541226.59     10435312.55      3541581.09     10435529.64
      3541615.74     10435526.28      3541854.40     10434882.46
      3541992.55     10434810.71      3542188.37     10434564.75
      3542339.38     10434465.66      3542473.44     10434501.81
      3542576.32     10434444.24      3542782.90     10434567.51
      3542906.51     10434522.10      3543499.56     10434852.27

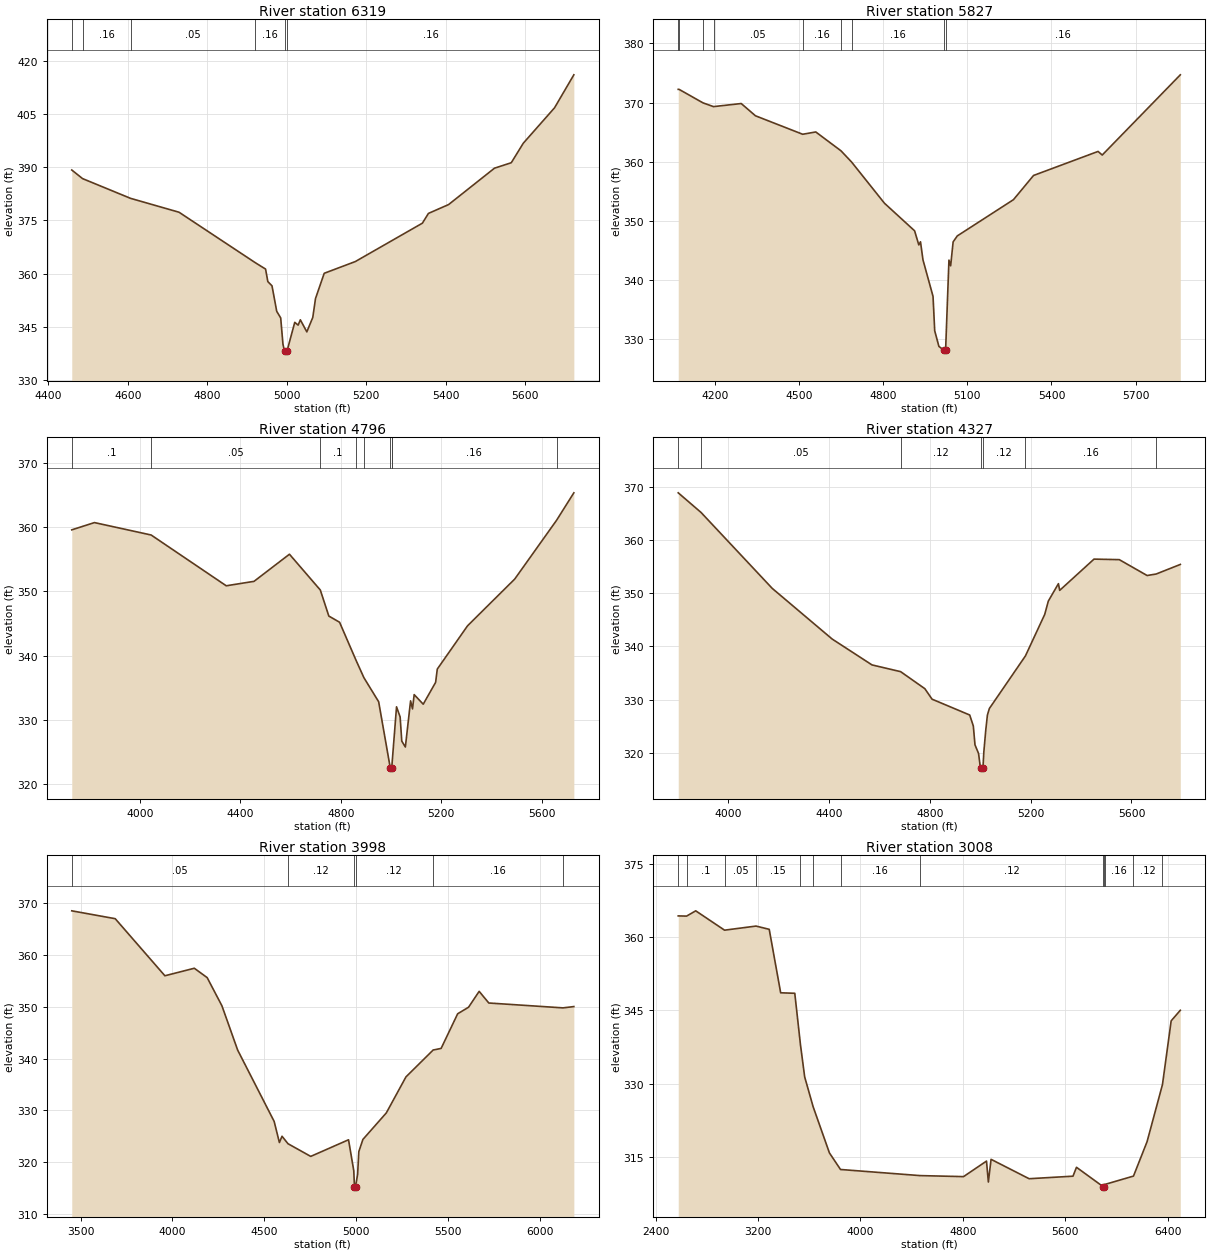
Type RM Length L Ch R = 1,6319,492,492,492
BEGIN DESCRIPTION:
STEELE CREEK TRIB 4.1 9.0
END DESCRIPTION:
XS GIS Cut Line= 4
      3538481.91     10434172.63      3538863.87     10434176.97
      3539154.67     10434020.72      3539454.04     10433556.48
#Sta/Elev= 30
  4458.7  389.25  4485.9  386.82  4606.8  381.25  4728.9  377.33  4920.1  363.15
  4946.8  361.29  4952.5  357.76  4963.0  356.56  4974.9  349.37  4984.9  347.50
  4990.6  340.09  4994.6  338.07  4997.4  337.57  5000.6  338.07  5020.3  346.26
  5028.8  345.47  5034.4  346.97  5050.7  343.57  5065.7  347.64  5072.6  352.99
  5094.5  360.10  5173.0  363.42  5341.8  374.25  5357.0  377.00  5407.7  379.49
  5523.3  389.76  5565.6  391.30  5595.9  396.81  5674.5  406.79  5723.2  416.11
#Mann=6,-1,0
  4458.7    0.05       0  4485.9    0.16       0  4606.8    0.05       0
  4920.1    0.16       0  4994.6    0.07       0  5000.6    0.16       0
Bank Sta=4994.6,5000.6
Exp/Cntr=0.3,0.1

Type RM Length L Ch R = 1,5827,1031,1031,1031
BEGIN DESCRIPTION:
STEELE CREEK TRIB 4.1 8.0
END DESCRIPTION:
XS GIS Cut Line= 2
      3538570.75     10434963.12      3540048.52     10433950.19
#Sta/Elev= 30
  4068.2  372.25  4071.0  372.25  4156.7  369.96  4194.1  369.33  4293.0  369.85
  4343.8  367.78  4512.3  364.66  4559.0  365.05  4649.1  361.86  4686.8  359.97
  4804.1  353.01  4911.7  348.35  4926.6  345.97  4932.7  346.50  4941.5  343.45
  4977.4  337.28  4983.4  331.47  4998.4  328.82  5016.3  328.19  5019.1  327.69
  5022.3  328.19  5034.2  343.40  5040.3  342.44  5049.1  346.48  5064.0  347.49
  5264.4  353.61  5336.1  357.70  5566.3  361.76  5581.2  361.15  5859.8  374.70
#Mann=9,-1,0
  4068.2     0.1       0  4071.0    0.05       0  4156.7     0.1       0
  4194.1    0.05       0  4512.3    0.16       0  4649.1    0.05       0
  4686.8    0.16       0  5016.3    0.07       0  5022.3    0.16       0
Bank Sta=5016.3,5022.3
Exp/Cntr=0.3,0.1

Type RM Length L Ch R = 1,4796,469,469,469
BEGIN DESCRIPTION:
STEELE CREEK TRIB 4.1 5.0
END DESCRIPTION:
XS GIS Cut Line= 4
      3539015.78     10435279.41      3539848.55     10434970.05
      3540334.66     10434407.55      3540258.30     10434046.56
#Sta/Elev= 30
  3728.1  359.56  3818.5  360.69  4044.4  358.76  4343.7  350.86  4454.4  351.55
  4595.6  355.77  4718.6  350.20  4752.5  346.15  4795.3  345.19  4860.4  339.32
  4892.2  336.57  4951.1  332.82  4997.4  322.53  5000.2  322.03  5003.4  322.53
  5004.8  323.35  5022.3  332.03  5036.6  330.47  5043.2  326.70  5057.5  325.78
  5078.3  332.96  5086.0  331.71  5092.6  333.93  5128.7  332.44  5178.1  335.84
  5184.7  337.90  5305.4  344.64  5493.4  351.91  5660.1  361.05  5728.9  365.32
#Mann=9,-1,0
  3728.1     0.1       0  4044.4    0.05       0  4718.6     0.1       0
  4860.4    0.16       0  4892.2     0.1       0  4997.4    0.07       0
  5003.4     0.1       0  5004.8    0.16       0  5660.1    0.05       0
Bank Sta=4997.4,5003.4
Exp/Cntr=0.3,0.1

Type RM Length L Ch R = 1,4327,329,329,329
BEGIN DESCRIPTION:
STEELE CREEK TRIB 4.1 4.0
END DESCRIPTION:
XS GIS Cut Line= 4
      3539232.82     10435426.97      3539987.44     10435282.55
      3540529.10     10434817.27      3540494.38     10434310.33
#Sta/Elev= 30
  3803.1  368.85  3893.4  365.17  4175.6  350.91  4413.3  341.39  4571.2  336.53
  4684.9  335.26  4780.9  332.06  4809.5  330.09  4958.7  327.12  4973.0  325.05
  4979.6  321.52  4993.8  319.89  5000.4  317.44  5005.1  317.08  5007.8  316.58
  5011.1  317.08  5014.7  320.22  5022.4  324.31  5028.9  327.13  5036.6  328.34
  5179.6  338.22  5256.1  346.02  5270.4  348.52  5310.4  351.79  5315.4  350.53
  5451.5  356.40  5551.7  356.30  5662.0  353.32  5697.9  353.60  5793.6  355.40
#Mann=7,-1,0
  3803.1     0.1       0  3893.4    0.05       0  4684.9    0.12       0
  5005.1    0.07       0  5011.1    0.12       0  5179.6    0.16       0
  5697.9    0.05       0
Bank Sta=5005.1,5011.1
Exp/Cntr=0.3,0.1

Type RM Length L Ch R = 1,3998,990,990,990
BEGIN DESCRIPTION:
STEELE CREEK TRIB 4.1 1.1
END DESCRIPTION:
XS GIS Cut Line= 4
      3539195.76     10435726.99      3540098.55     10435706.16
      3540813.83     10434851.99      3540681.89     10434150.63
#Sta/Elev= 30
  3452.4  368.52  3688.8  367.00  3958.9  355.98  4118.9  357.43  4188.9  355.62
  4269.0  350.19  4354.7  341.63  4553.1  327.86  4581.7  323.78  4596.0  324.99
  4628.4  323.55  4752.1  321.10  4957.7  324.31  4986.3  318.33  4989.9  315.28
  4992.6  314.78  4995.9  315.28  5007.2  317.65  5013.7  322.02  5035.8  324.37
  5163.3  329.50  5270.0  336.45  5417.9  341.64  5461.3  341.95  5551.3  348.64
  5610.7  349.91  5668.2  352.97  5720.7  350.72  6124.0  349.78  6183.2  350.03
#Mann=6,-1,0
  3452.4    0.05       0  4628.4    0.12       0  4989.9    0.07       0
  4995.9    0.12       0  5417.9    0.16       0  6124.0    0.12       0
Bank Sta=4989.9,4995.9
Exp/Cntr=0.3,0.1

Type RM Length L Ch R = 1,3008,0,0,0
BEGIN DESCRIPTION:
STEELE CREEK TRIB 4.1 1.0
END DESCRIPTION:
XS GIS Cut Line= 4
      3539264.05     10435826.76      3541005.37     10435950.02
      3541752.48     10434776.99      3541089.28     10434356.85
#Sta/Elev= 30
  2576.7  364.36  2642.1  364.32  2713.4  365.40  2938.5  361.44  3184.6  362.28
  3287.4  361.61  3376.8  348.62  3487.0  348.52  3531.4  337.99  3564.3  331.40
  3630.2  325.31  3757.7  315.84  3844.3  312.45  4464.8  311.20  4805.1  310.99
  4984.4  314.17  4999.0  309.88  5020.1  314.53  5317.3  310.56  5660.1  311.08
  5687.2  312.90  5895.8  308.93  5898.6  308.43  5901.8  308.93  5908.0  309.38
  6132.5  311.10  6238.7  318.15  6358.8  329.83  6426.8  342.88  6498.2  345.04
#Mann=13,-1,0
  2576.7    0.05       0  2642.1     0.1       0  2938.5    0.05       0
  3184.6    0.15       0  3531.4    0.05       0  3630.2    0.12       0
  3844.3    0.16       0  4464.8    0.12       0  5895.8    0.07       0
  5901.8    0.12       0  5908.0    0.16       0  6132.5    0.12       0
  6358.8    0.16       0
Bank Sta=5895.8,5901.8
Exp/Cntr=0.3,0.1

Chan Stop Cuts=-1