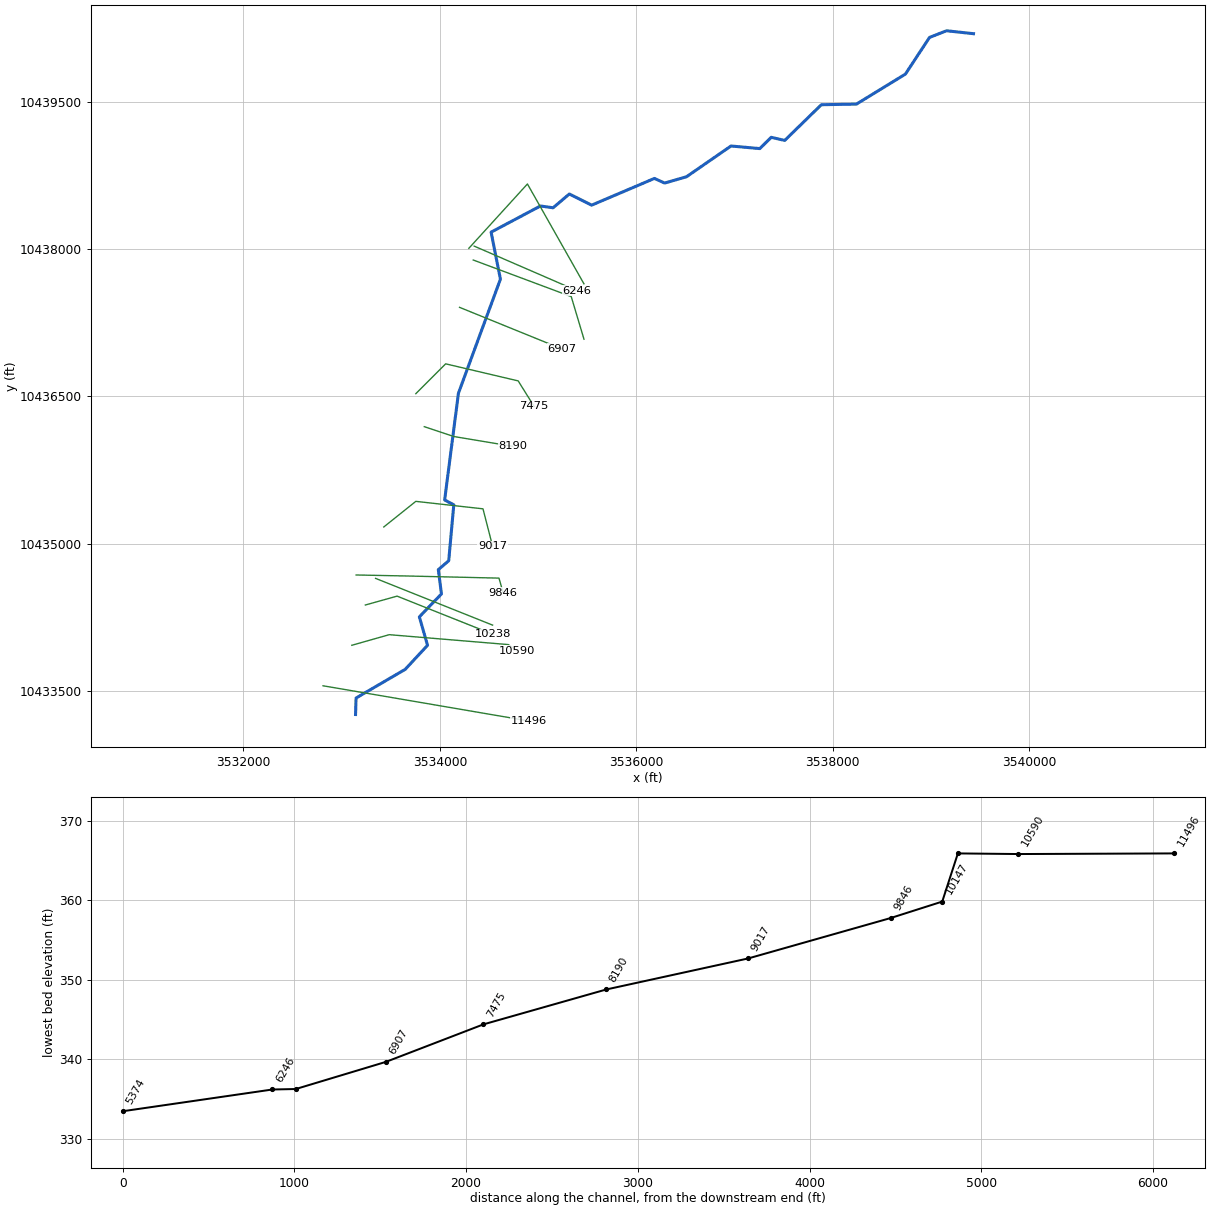
--- STEELE CREEK TRIB 7 1.prj (project) ---

Proj Title=STEELE CREEK TRIB 7 1 Base Level Engineering
Current Plan=p01
Default Exp/Contr=0.3,0.1
English Units
Geom File=g01
Flow File=f01
Plan File=p01
Y Axis Title=Elevation
X Axis Title(PF)=Main Channel Distance
X Axis Title(XS)=Station
BEGIN DESCRIPTION:
STEELE CREEK TRIB 7 1
END DESCRIPTION:
DSS Export Rating Curves= 0
DSS Export Rating Curve Sorted= 0
DSS Export Volume Flow Curves= 0
DXF OffsetX= 0
DXF OffsetY= 0
DXF ScaleX= 1
DXF ScaleY= 10

--- STEELE CREEK TRIB 7 1.p01 (plan) ---

Plan Title=Multiple Run
Short Identifier=Multiple
Geom File=g01
Flow File=f01
Subcritical Flow
K Sum by GR= 0
Std Step Tol= 0.01
Critical Tol= 0.01
Num of Std Step Trials= 20
Max Error Tol= 0.3
Flow Tol Ratio= 0.001
Split Flow NTrial= 30
Split Flow Tol= 0.02
Split Flow Ratio= 0.02
Log Output Level= 0
Friction Slope Method= 1
Unsteady Friction Slope Method= 2
Unsteady Bridges Friction Slope Method= 1
Parabolic Critical Depth
Global Vel Dist=  1 , 1 , 1
Global Log Level= 0
CheckData=True
Encroach Param= -1, 0, 0, 0
BEGIN DESCRIPTION:
Multiple Run
END DESCRIPTION:

--- STEELE CREEK TRIB 7 1.f01 (steady flow) ---

Flow Title=Multiple
Program Version=4.10
Number of Profiles= 7
Profile Names=10-year,25-year,50-year,1pct_min,100-year,1pct_plu,500-year
River Rch & RM=STEELE CREEK TRI,Reach-1         ,11496
    1286    1822    2280    2083    2817    3810    4290
River Rch & RM=STEELE CREEK TRI,Reach-1         ,5374
    1630    2327    2926    2682    3628    4906    5564
Boundary for River Rch & Prof#=STEELE CREEK TRI,Reach-1         , 1
Up Type= 0
Dn Type= 3
Dn Slope=0.003
Boundary for River Rch & Prof#=STEELE CREEK TRI,Reach-1         , 2
Up Type= 0
Dn Type= 3
Dn Slope=0.003
Boundary for River Rch & Prof#=STEELE CREEK TRI,Reach-1         , 3
Up Type= 0
Dn Type= 3
Dn Slope=0.003
Boundary for River Rch & Prof#=STEELE CREEK TRI,Reach-1         , 4
Up Type= 0
Dn Type= 3
Dn Slope=0.003
Boundary for River Rch & Prof#=STEELE CREEK TRI,Reach-1         , 5
Up Type= 0
Dn Type= 3
Dn Slope=0.003
Boundary for River Rch & Prof#=STEELE CREEK TRI,Reach-1         , 6
Up Type= 0
Dn Type= 3
Dn Slope=0.003
Boundary for River Rch & Prof#=STEELE CREEK TRI,Reach-1         , 7
Up Type= 0
Dn Type= 3
Dn Slope=0.003
DSS Import GetInterval= 0
DSS Import GetPeak= 0
DSS Import FillOption= 0

--- STEELE CREEK TRIB 7 1.g01 (geometry) ---

Geom Title=Existing Conditions
Program Version=4.10

River Reach=STEELE CREEK TRI,Reach-1
Reach XY= 30
      3533142.22      10433261.9      3533147.59     10433429.78
      3533647.59     10433721.44      3533875.02     10433966.23
      3533791.68     10434256.16      3534016.66     10434489.11
      3533984.65     10434736.32      3534090.55     10434827.01
       3534142.2     10435396.76      3534049.06     10435445.25
      3534189.51     10436532.25      3534616.75     10437692.61
      3534522.11     10438171.64      3535023.81      10438437.9
      3535152.83      10438419.8      3535318.28     10438559.78
      3535545.44     10438446.42        3536184.     10438718.43
      3536288.22     10438671.34      3536510.58     10438735.34
      3536963.62     10439048.53      3537257.36     10439022.02
      3537372.89     10439136.82      3537510.52     10439105.26
       3537883.3     10439468.57      3538240.49     10439475.01
      3538738.66     10439780.09      3538984.48     10440153.68
       3539157.5     10440221.42      3539432.11     10440191.64

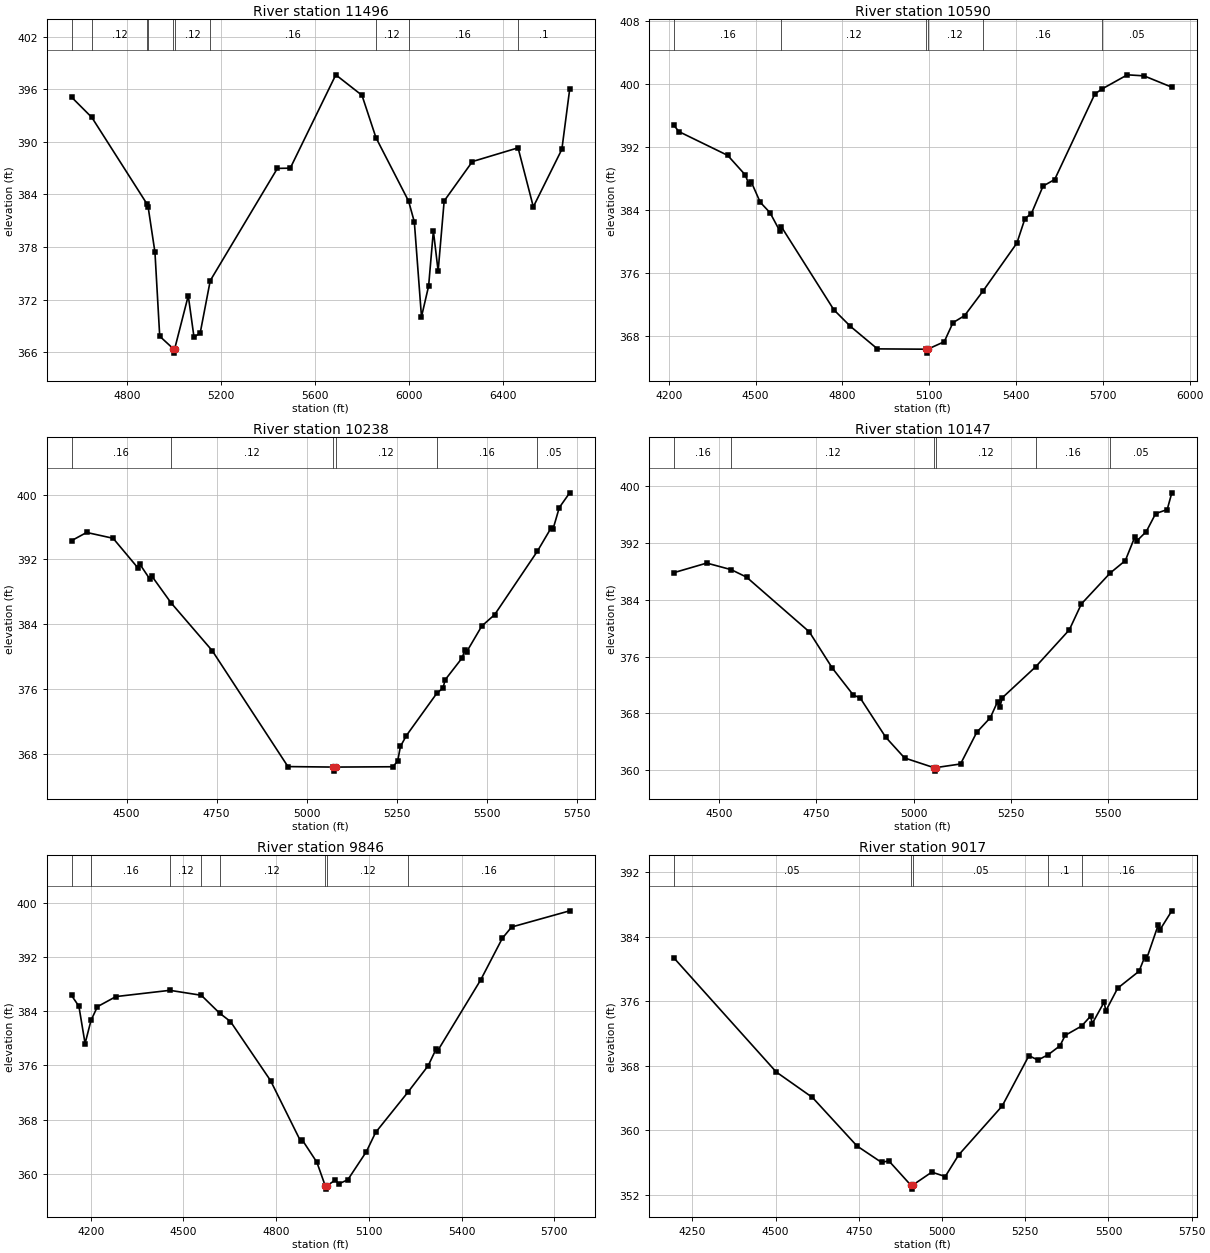
Type RM Length L Ch R = 1 ,11496   ,906,906,906
BEGIN DESCRIPTION:
STEELE CREEK TRIB 7.1 13.0
END DESCRIPTION:
XS GIS Cut Line= 2
      3532811.68     10433554.42        3534905.      10433196.5
#Sta/Elev= 30
  4562.4  395.12  4648.9   392.8  4884.1  382.91  4888.8  382.58  4917.9   377.4
  4938.2  367.81  4996.1  366.38  4998.8  365.88  5002.1  366.38  5059.9  372.44
  5084.3  367.71  5110.7  368.17  5153.6  374.16  5439.8  386.98  5494.8  387.01
  5688.9  397.67  5800.5  395.33  5860.3  390.48  5999.3  383.24  6023.7  380.87
  6054.2  370.03  6084.6  373.54  6104.9  379.84  6125.2  375.25  6150.9  383.26
  6271.1  387.76    6466  389.33    6531  382.59  6652.7  389.16  6686.1  396.03
#Mann= 10 ,-1 , 0
  4562.4     .16       0  4648.9     .12       0  4884.1     .16       0
  4888.8     .12       0  4996.1     .07       0  5002.1     .12       0
  5153.6     .16       0  5860.3     .12       0  5999.3     .16       0
    6466      .1       0
Bank Sta=4996.1,5002.1
XS Rating Curve= 0 ,0
Exp/Cntr=0.3,0.1

Type RM Length L Ch R = 1 ,10590   ,352,352,352
BEGIN DESCRIPTION:
STEELE CREEK TRIB 7.1 11.0
END DESCRIPTION:
XS GIS Cut Line= 4
      3533104.65     10433966.73      3533485.23     10434074.57
      3534697.04     10433973.87      3534786.56     10433912.47
#Sta/Elev= 30
  4217.2  394.79  4235.3  393.96  4403.6  390.94    4464  388.47  4476.6   387.3
  4484.8  387.58    4516  384.98  4549.7  383.66  4583.6  381.33  4589.1  381.86
  4770.2  371.31  4827.3  369.21  4920.7  366.34  5088.3   366.3    5091   365.8
  5094.3   366.3  5151.5  367.25  5181.6  369.67  5221.7  370.57  5284.5  373.65
  5402.3  379.79  5430.2  382.91  5452.5  383.55  5492.7  387.04  5532.8  387.87
  5671.4  398.74  5696.6  399.39  5783.7  401.18  5841.2  401.05  5937.3  399.61
#Mann= 6 ,-1 , 0
  4217.2     .16       0  4589.1     .12       0  5088.3     .07       0
  5094.3     .12       0  5284.5     .16       0  5696.6     .05       0
Bank Sta=5088.3,5094.3
XS Rating Curve= 0 ,0
Exp/Cntr=0.3,0.1

Type RM Length L Ch R = 1 ,10238   ,91,91,91
BEGIN DESCRIPTION:
Mapping XS 2d556590
END DESCRIPTION:
XS GIS Cut Line= 3
      3533242.19     10434376.65      3533565.09     10434466.93
      3534538.91     10434078.79
#Sta/Elev= 30
  4347.4  394.32  4389.3  395.33  4462.8  394.61    4531  390.99  4536.2  391.47
  4565.2  389.55  4570.4  389.94  4623.8  386.64  4738.1  380.74  4948.4  366.44
  5074.8  366.38  5077.5  365.88  5080.8  366.38  5239.3  366.42    5253  367.09
  5260.8  368.92  5277.3  370.26  5361.5  375.46  5379.2  376.15  5385.1  377.15
    5433  379.89  5439.1  380.83  5444.4  380.57  5486.8  383.78  5522.6  385.19
  5641.3  393.02    5679  395.86  5684.4   395.7  5702.1   398.4    5731  400.22
#Mann= 6 ,-1 , 0
  4347.4     .16       0  4623.8     .12       0  5074.8     .07       0
  5080.8     .12       0  5361.5     .16       0  5641.3     .05       0
Bank Sta=5074.8,5080.8
XS Rating Curve= 0 ,0
Exp/Cntr=0.3,0.1

Type RM Length L Ch R = 1 ,10147   ,301,301,301
BEGIN DESCRIPTION:
Mapping XS ea4b5ff9
END DESCRIPTION:
XS GIS Cut Line= 2
      3533346.31      10434647.5      3534537.22     10434171.82
#Sta/Elev= 30
  4382.5  387.82  4467.6  389.18  4530.6  388.25    4570   387.2  4731.6  379.48
  4790.9  374.36  4844.8  370.57  4862.5  370.16  4928.3  364.62  4976.8  361.69
  5051.9  360.33  5054.6  359.83  5057.9  360.33    5121  360.84  5162.7  365.31
  5197.7  367.37  5216.5  369.65  5221.9  368.86  5228.7  370.19  5314.4  374.55
    5401  379.76  5432.1  383.42  5506.3  387.78  5545.2  389.53  5569.4  392.83
  5574.8   392.3  5599.1  393.62  5623.3  396.16    5653  396.73  5664.9  399.09
#Mann= 6 ,-1 , 0
  4382.5     .16       0  4530.6     .12       0  5051.9     .07       0
  5057.9     .12       0  5314.4     .16       0  5506.3     .05       0
Bank Sta=5051.9,5057.9
XS Rating Curve= 0 ,0
Exp/Cntr=0.3,0.1

Type RM Length L Ch R = 1 ,9846    ,829,829,829
BEGIN DESCRIPTION:
STEELE CREEK TRIB 7.1 12.0
END DESCRIPTION:
XS GIS Cut Line= 4
      3533148.45      10434682.2      3533658.07     10434672.04
      3534602.08     10434650.34      3534645.49      10434498.4
#Sta/Elev= 30
  4138.1  386.33  4161.8  384.74  4181.8  379.24  4201.1  382.67  4221.8  384.68
  4281.8  386.17  4456.3  387.09  4557.9  386.36  4616.9  383.73  4652.3  382.49
  4781.9  373.78  4879.8  364.79  4884.8     365  4931.9  361.73  4958.9  358.26
  4961.7  357.76  4964.9  358.26    4992  359.12    5002  358.52    5032  359.14
    5092  363.28    5122  366.12    5227  372.09    5292  375.96  5317.4  378.39
  5322.4  378.14  5462.1  388.63  5532.1  394.77  5562.1  396.43  5750.1  398.82
#Mann= 8 ,-1 , 0
  4138.1     .05       0  4201.1     .16       0  4456.3     .12       0
  4557.9     .16       0  4616.9     .12       0  4958.9     .07       0
  4964.9     .12       0    5227     .16       0
Bank Sta=4958.9,4964.9
XS Rating Curve= 0 ,0
Exp/Cntr=0.3,0.1

Type RM Length L Ch R = 1 ,9017    ,827,827,827
BEGIN DESCRIPTION:
STEELE CREEK TRIB 7.1 8.0
END DESCRIPTION:
XS GIS Cut Line= 4
       3533430.2     10435171.17      3533755.73     10435431.59
      3534439.32     10435355.63      3534536.88     10434976.25
#Sta/Elev= 30
    4194  381.38  4502.1  367.21  4610.9  364.05  4744.6  358.04  4818.5     356
  4840.2   356.2  4906.1  353.19  4908.8  352.69  4912.1  353.19  4969.4   354.8
  5009.7  354.25  5049.9  356.92  5180.7  362.99  5261.2  369.24    5288  368.69
  5318.9  369.35  5354.4  370.46    5370  371.75  5419.2   372.9  5446.3  374.13
  5451.5  373.22    5487  375.87  5492.2  374.79  5527.7   377.6  5591.9   379.7
  5609.2  381.49  5614.4  381.21  5649.9  385.48  5655.1  384.86  5690.4  387.19
#Mann= 5 ,-1 , 0
    4194     .05       0  4906.1     .03       0  4912.1     .05       0
  5318.9      .1       0  5419.2     .16       0
Bank Sta=4906.1,4912.1
XS Rating Curve= 0 ,0
Exp/Cntr=0.3,0.1

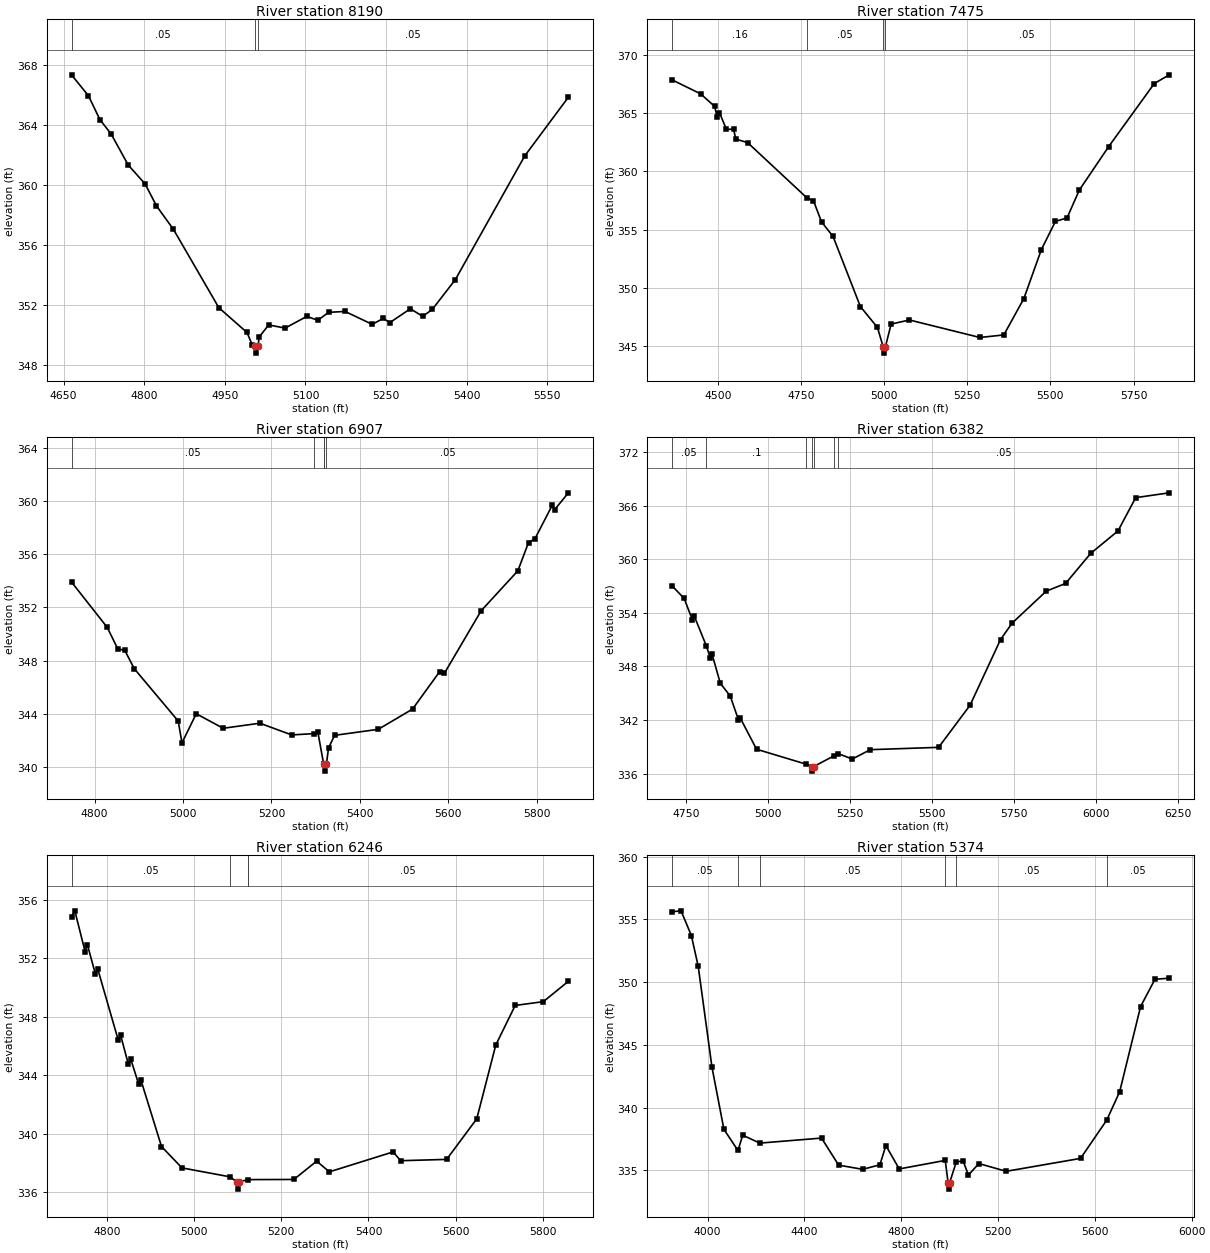
Type RM Length L Ch R = 1 ,8190    ,715,715,715
BEGIN DESCRIPTION:
STEELE CREEK TRIB 7.1 6.0
END DESCRIPTION:
XS GIS Cut Line= 3
       3533842.1     10436191.64      3534142.11     10436091.64
      3534742.09     10435991.64
#Sta/Elev= 30
  4664.7  367.35  4696.3  365.95  4717.4  364.37  4738.5   363.4  4770.1  361.34
  4801.7  360.07  4822.8  358.61  4854.4  357.04  4938.8  351.82  4991.1  350.17
  5001.2  349.32  5005.8  349.29  5008.6  348.79  5011.8  349.29  5013.9  349.87
  5031.6  350.67    5062  350.46  5102.6  351.24  5122.9  350.98  5143.1  351.51
  5173.6  351.57  5224.2  350.71  5244.5   351.1  5257.2  350.83  5295.2  351.75
    5318  351.24  5335.8   351.7  5378.8  353.69  5508.1  361.95  5589.2  365.86
#Mann= 3 ,-1 , 0
  4664.7     .05       0  5005.8     .03       0  5011.8     .05       0
Bank Sta=5005.8,5011.8
XS Rating Curve= 0 ,0
Exp/Cntr=0.3,0.1

Type RM Length L Ch R = 1 ,7475    ,568,568,568
BEGIN DESCRIPTION:
STEELE CREEK TRIB 7.1 4.0
END DESCRIPTION:
XS GIS Cut Line= 4
      3533755.76     10436527.54      3534059.55     10436831.33
      3534797.39     10436657.72      3534960.15     10436397.31
#Sta/Elev= 30
  4362.5  367.82  4447.7  366.63  4490.1  365.55  4497.2  364.64  4504.2  365.03
  4525.5  363.58  4546.7  363.61  4553.7  362.75  4589.1  362.45    4768   357.7
  4787.1  357.48  4811.4  355.66  4846.1  354.41  4928.3   348.4  4979.7  346.61
  4997.2  344.91    5000  344.41  5003.2  344.91  5020.8   346.9  5075.9  347.25
  5287.8  345.75  5359.8  345.97    5420  349.08  5472.8  353.29  5515.1   355.7
    5550     356    5587  358.39  5675.2  362.11  5812.3  367.51  5857.2  368.26
#Mann= 4 ,-1 , 0
  4362.5     .16       0    4768     .05       0  4997.2    .035       0
  5003.2     .05       0
Bank Sta=4997.2,5003.2
XS Rating Curve= 0 ,0
Exp/Cntr=0.3,0.1

Type RM Length L Ch R = 1 ,6907    ,525,525,525
BEGIN DESCRIPTION:
STEELE CREEK TRIB 7.1 2.0
END DESCRIPTION:
XS GIS Cut Line= 2
      3534200.62     10437406.41      3535242.24     10436983.25
#Sta/Elev= 30
  4747.7  353.91  4828.5   350.5  4852.6  348.87    4868  348.79  4889.6   347.4
  4989.2  343.46  4997.6  341.82  5029.9  344.01  5090.9  342.92  5173.9   343.3
  5245.8  342.42  5297.1  342.52  5305.1  342.63  5318.1  340.25  5318.4   340.2
  5321.1   339.7  5324.4   340.2  5329.2  341.44    5343  342.39  5441.7  342.84
  5519.3  344.36  5580.4  347.16  5591.2  347.04  5674.6  351.75  5757.6  354.75
  5781.7  356.87  5796.3  357.16  5835.2  359.66  5840.6  359.34    5872  360.61
#Mann= 5 ,-1 , 0
  4747.7     .05       0  5297.1     .16       0  5318.1     .05       0
  5318.4    .035       0  5324.4     .05       0
Bank Sta=5318.4,5324.4
XS Rating Curve= 0 ,0
Exp/Cntr=0.3,0.1

Type RM Length L Ch R = 1 ,6382    ,136,136,136
BEGIN DESCRIPTION:
Mapping XS 30b06f94
END DESCRIPTION:
XS GIS Cut Line= 3
      3534340.15     10437888.14      3535337.54     10437515.75
      3535467.43     10437081.92
#Sta/Elev= 30
  4706.7  356.99  4742.9  355.61  4767.8  353.24  4773.2  353.69  4810.7   350.3
  4823.1  348.92  4828.4  349.34  4853.4  346.11  4883.7  344.69  4908.7  342.04
    4914  342.25    4964  338.74  5116.2  337.06  5132.1  336.79  5134.9  336.29
  5138.1  336.79  5201.4  338.02  5212.7  338.26  5256.3  337.64  5311.6  338.69
    5520  338.95  5616.1  343.66  5709.2  351.01  5744.9  352.86  5848.7  356.42
  5907.7  357.28  5984.4  360.64  6067.9  363.16  6121.9  366.88  6224.2  367.42
#Mann= 7 ,-1 , 0
  4706.7     .05       0  4810.7      .1       0  5116.2     .05       0
  5132.1     .07       0  5138.1     .05       0  5201.4      .1       0
  5212.7     .05       0
Bank Sta=5132.1,5138.1
XS Rating Curve= 0 ,0
Exp/Cntr=0.3,0.1

Type RM Length L Ch R = 1 ,6246    ,872,872,872
BEGIN DESCRIPTION:
STEELE CREEK TRIB 7.1 1.1
END DESCRIPTION:
XS GIS Cut Line= 2
      3534349.68     10438029.49      3535394.85      10437576.3
#Sta/Elev= 30
  4719.2  354.84  4726.8  355.23  4750.3  352.45  4755.7  352.91  4773.8  350.93
  4779.2  351.27  4826.2  346.42  4831.6  346.76  4849.6  344.75  4855.1   345.1
  4873.1   343.4  4878.5  343.66  4925.5  339.14  4972.4  337.68  5082.6  337.07
  5097.7  336.73  5100.4  336.23  5103.7  336.73  5124.1  336.88  5228.9  336.89
  5281.3  338.14  5310.4  337.41  5456.5  338.77  5473.9  338.17  5579.2  338.26
  5648.3  341.03  5691.9  346.07  5736.4  348.77  5800.9  349.03  5858.4  350.42
#Mann= 4 ,-1 , 0
  4719.2     .05       0  5082.6     .03       0  5124.1      .1       0
  5124.1     .05       0
Bank Sta=5097.7,5103.7
XS Rating Curve= 0 ,0
Exp/Cntr=0.3,0.1

Type RM Length L Ch R = 1 ,5374    ,0,0,0
BEGIN DESCRIPTION:
STEELE CREEK TRIB 7.1 1.0
END DESCRIPTION:
XS GIS Cut Line= 3
      3534295.33     10438006.91      3534891.73     10438662.13
      3535466.63     10437646.23
#Sta/Elev= 30
  3853.8  355.62  3890.1  355.69  3932.6  353.72    3961  351.26  4017.8  343.22
  4067.1  338.27  4125.2  336.58  4144.8   337.8  4215.4  337.17  4470.5  337.57
  4541.4  335.41  4640.8  335.08  4711.7  335.44  4736.4  336.97  4791.7  335.11
  4981.7  335.79  4993.6     334  4996.4   333.5  4999.6     334  5027.6  335.68
  5055.8  335.74  5077.5  334.62  5120.7  335.54  5233.4  334.92  5540.8  335.95
    5649     339  5702.4  341.26    5789  348.06  5848.2  350.23  5907.1  350.32
#Mann= 6 ,-1 , 0
  3853.8     .05       0  4125.2      .1       0  4215.4     .05       0
  4981.7     .03       0  5027.6     .05       0    5649     .05       0
Bank Sta=4993.6,4999.6
XS Rating Curve= 0 ,0
Exp/Cntr=0.3,0.1

Chan Stop Cuts=-1
Use User Specified Reach Order=0
Composite Channel Slope=5