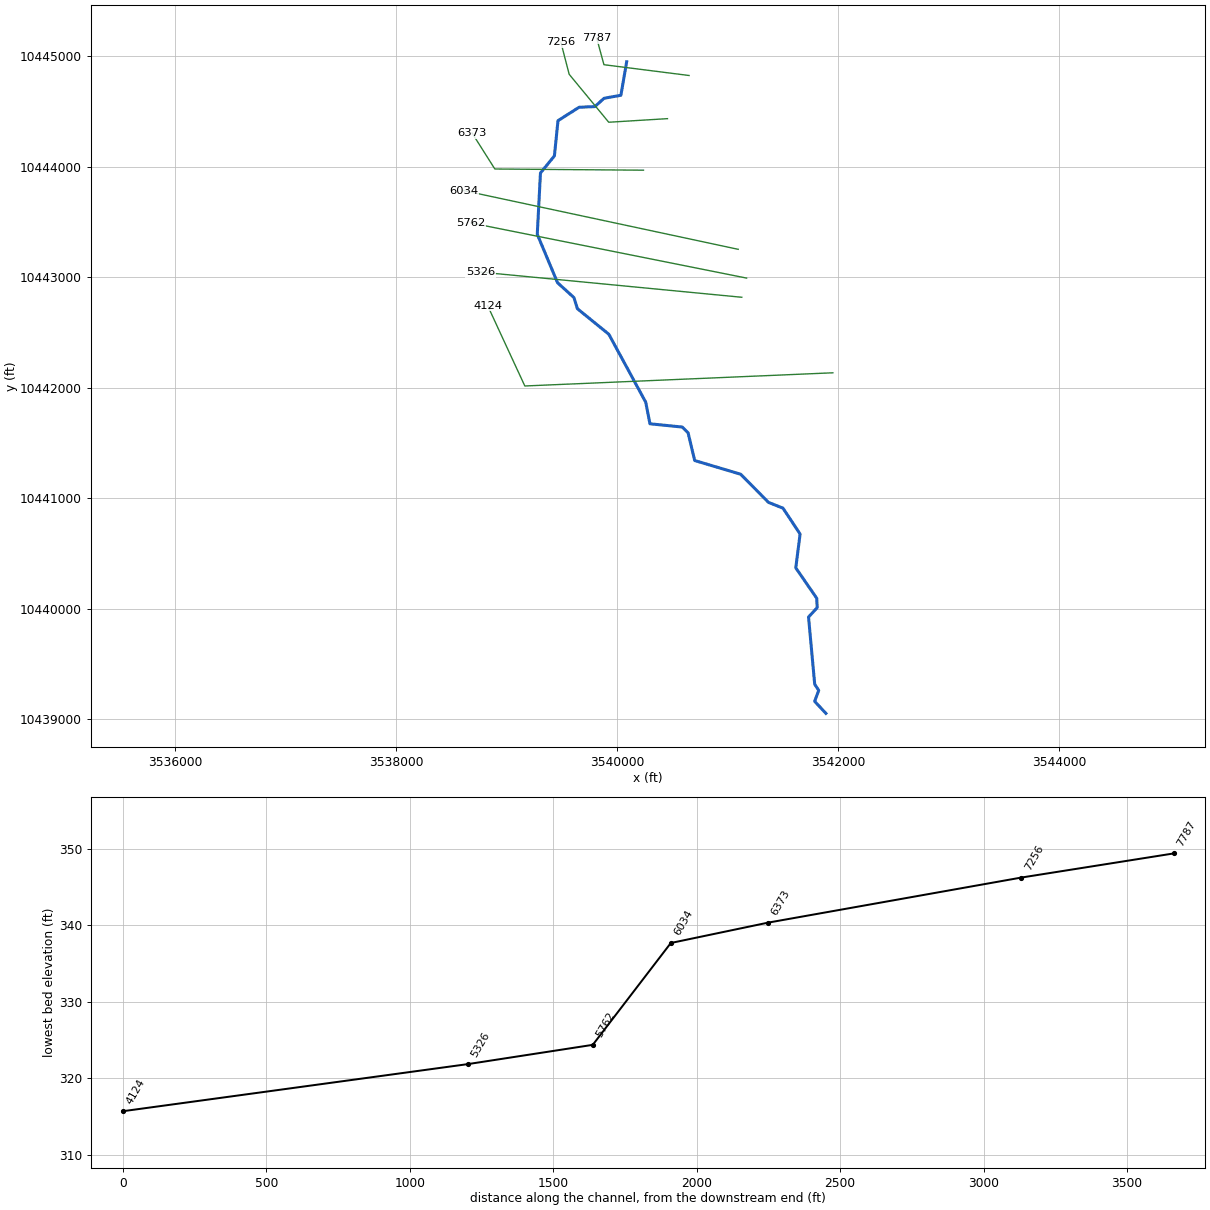
--- STEELE CREEK TRIB 8.prj (project) ---

Proj Title=STEELE CREEK TRIB 8 Base Level Engineering
Current Plan=p01
Default Exp/Contr=0.3,0.1
English Units
Geom File=g01
Flow File=f01
Plan File=p01
BEGIN DESCRIPTION:
STEELE CREEK TRIB 8
END DESCRIPTION:

--- STEELE CREEK TRIB 8.p01 (plan) ---

Plan Title=Multiple Run
Short Identifier=Multiple
Geom File=g01
Flow File=f01
Subcritical Flow
K Sum by GR= 0
Std Step Tol= 0.01
Critical Tol= 0.01
Num of Std Step Trials= 20
Max Error Tol= 0.3
Flow Tol Ratio= 0.001
Split Flow NTrial= 30
Split Flow Tol= 0.02
Split Flow Ratio= 0.02
Log Output Level= 0
Friction Slope Method= 1
Unsteady Friction Slope Method= 2
Unsteady Bridges Friction Slope Method= 1
Parabolic Critical Depth
Global Vel Dist=  1 , 1 , 1
Global Log Level= 0
CheckData=True
Encroach Param= -1, 0, 0, 0
BEGIN DESCRIPTION:
Multiple Run
END DESCRIPTION:

--- STEELE CREEK TRIB 8.f01 (steady flow) ---

Flow Title=Multiple
Number of Profiles=7
Profile Names=10-year,25-year,50-year,1pct_min,100-year,1pct_plu,500-year
River Rch & RM= STEELE CREEK TRI,Reach-1,7787
     792    1076    1307    1161    1570    2123    2256
Boundary for River Rch & Prof#=STEELE CREEK TRI,Reach-1,1
Up Type=0
Dn Type=3
Dn Slope=0.005
Boundary for River Rch & Prof#=STEELE CREEK TRI,Reach-1,2
Up Type=0
Dn Type=3
Dn Slope=0.005
Boundary for River Rch & Prof#=STEELE CREEK TRI,Reach-1,3
Up Type=0
Dn Type=3
Dn Slope=0.005
Boundary for River Rch & Prof#=STEELE CREEK TRI,Reach-1,4
Up Type=0
Dn Type=3
Dn Slope=0.005
Boundary for River Rch & Prof#=STEELE CREEK TRI,Reach-1,5
Up Type=0
Dn Type=3
Dn Slope=0.005
Boundary for River Rch & Prof#=STEELE CREEK TRI,Reach-1,6
Up Type=0
Dn Type=3
Dn Slope=0.005
Boundary for River Rch & Prof#=STEELE CREEK TRI,Reach-1,7
Up Type=0
Dn Type=3
Dn Slope=0.005

--- STEELE CREEK TRIB 8.g01 (geometry) ---

Geom Title=Existing Conditions

River Reach=STEELE CREEK TRI,Reach-1
Reach XY= 30
      3540084.11     10444949.36      3540031.80     10444646.43
      3539879.46     10444619.09      3539796.19     10444543.74
      3539653.76     10444537.91      3539462.43     10444416.62
      3539430.02     10444097.40      3539303.73     10443942.90
      3539274.87     10443388.00      3539458.25     10442949.63
      3539606.76     10442815.18      3539638.37     10442714.17
      3539922.44     10442483.48      3540256.64     10441868.03
      3540294.84     10441672.72      3540587.80     10441643.21
      3540639.89     10441591.12      3540699.78     10441340.25
      3541116.45     10441216.12      3541367.32     10440961.78
      3541499.26     10440908.83      3541653.78     10440674.46
      3541614.71     10440368.90      3541804.82     10440092.86
      3541808.29     10440008.66      3541730.16     10439923.59
      3541785.98     10439315.08      3541822.18     10439259.52
      3541785.72     10439160.57      3541887.35     10439051.68

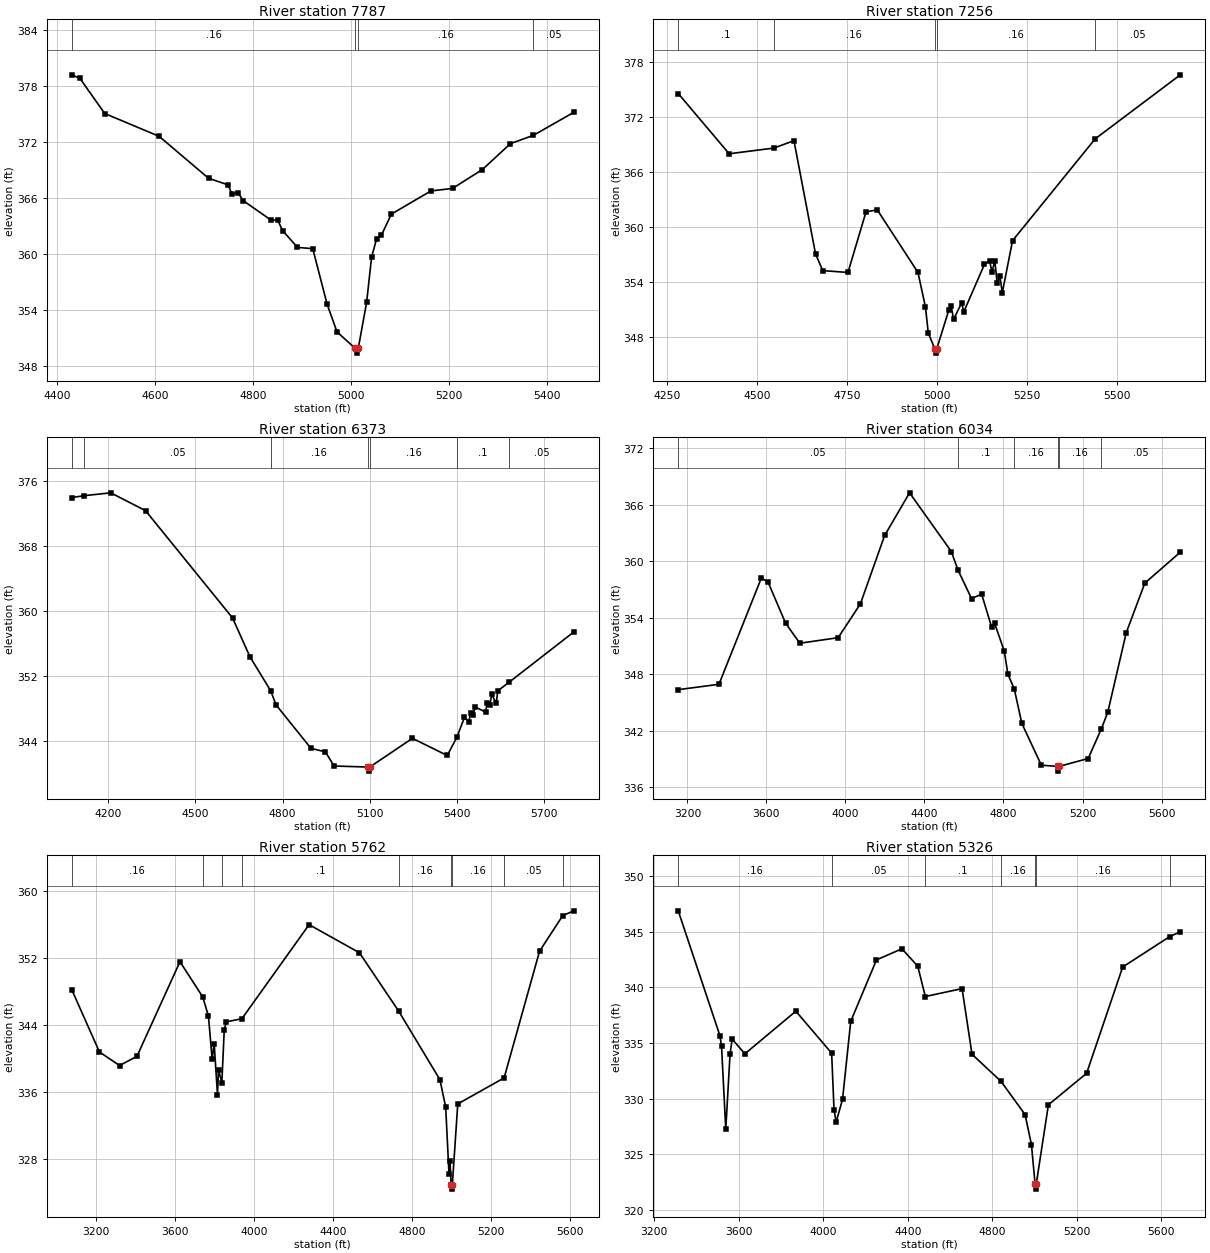
Type RM Length L Ch R = 1,7787,531,531,531
BEGIN DESCRIPTION:
STEELE CREEK TRIB 8 14.0
END DESCRIPTION:
XS GIS Cut Line= 3
      3540648.76     10444825.35      3539878.32     10444923.01
      3539813.22     10445161.69
#Sta/Elev= 30
  4430.6  379.18  4447.4  378.79  4497.8  375.04  4608.7  372.60  4709.5  368.11
  4749.8  367.39  4756.9  366.43  4770.0  366.54  4780.0  365.72  4837.0  363.63
  4850.6  363.62  4860.7  362.50  4890.9  360.71  4922.1  360.57  4951.4  354.62
  4971.6  351.66  5008.9  349.89  5011.6  349.39  5014.9  349.89  5032.0  354.84
  5042.1  359.67  5052.2  361.61  5062.3  362.03  5082.4  364.27  5163.1  366.75
  5207.2  367.02  5268.0  369.04  5325.4  371.82  5372.0  372.70  5454.6  375.17
#Mann=4,-1,0
  4430.6    0.16       0  5008.9    0.07       0  5014.9    0.16       0
  5372.0    0.05       0
Bank Sta=5008.9,5014.9
Exp/Cntr=0.3,0.1

Type RM Length L Ch R = 1,7256,883,883,883
BEGIN DESCRIPTION:
STEELE CREEK TRIB 8 13.0
END DESCRIPTION:
XS GIS Cut Line= 4
      3540453.44     10444434.74      3539921.72     10444402.18
      3539563.65     10444836.21      3539488.03     10445127.88
#Sta/Elev= 30
  4280.6  374.59  4422.2  368.01  4546.5  368.63  4602.5  369.44  4662.6  357.07
  4682.7  355.25  4752.8  355.05  4802.9  361.66  4834.2  361.89  4947.5  355.05
  4968.3  351.28  4976.2  348.44  4994.0  346.74  4996.8  346.24  5000.0  346.74
  5033.0  350.90  5040.0  351.37  5046.5  349.92  5068.7  351.71  5075.2  350.77
  5132.5  355.94  5146.9  356.31  5153.4  355.08  5161.2  356.35  5167.7  353.92
  5175.6  354.61  5182.0  352.83  5210.7  358.53  5440.5  369.64  5677.3  376.63
#Mann=5,-1,0
  4280.6     0.1       0  4546.5    0.16       0  4994.0    0.07       0
  5000.0    0.16       0  5440.5    0.05       0
Bank Sta=4994,5000
Exp/Cntr=0.3,0.1

Type RM Length L Ch R = 1,6373,339,339,339
BEGIN DESCRIPTION:
STEELE CREEK TRIB 8 11.0
END DESCRIPTION:
XS GIS Cut Line= 3
      3540236.44     10443968.15      3538890.90     10443979.00
      3538684.74     10444304.53
#Sta/Elev= 30
  4073.5  373.96  4116.4  374.19  4207.8  374.54  4327.8  372.35  4627.8  359.17
  4687.9  354.39  4759.0  350.24  4777.9  348.48  4897.9  343.16  4947.9  342.71
  4977.9  340.98  5094.9  340.85  5097.6  340.35  5100.9  340.85  5247.9  344.38
  5367.9  342.27  5401.7  344.55  5427.1  346.94  5442.4  346.41  5448.3  347.55
  5457.7  347.22  5463.6  348.25  5500.0  347.60  5506.0  348.75  5515.3  348.51
  5521.2  349.80  5536.5  348.66  5542.4  350.22  5581.5  351.28  5804.4  357.45
#Mann=7,-1,0
  4073.5     0.1       0  4116.4    0.05       0  4759.0    0.16       0
  5094.9    0.07       0  5100.9    0.16       0  5401.7     0.1       0
  5581.5    0.05       0
Bank Sta=5094.9,5100.9
Exp/Cntr=0.3,0.1

Type RM Length L Ch R = 1,6034,272,272,272
BEGIN DESCRIPTION:
STEELE CREEK TRIB 8 10.0
END DESCRIPTION:
XS GIS Cut Line= 2
      3541093.62     10443252.00      3538608.77     10443783.69
#Sta/Elev= 30
  3153.8  346.34  3359.9  346.91  3574.6  358.20  3608.3  357.76  3697.0  353.41
  3768.9  351.27  3963.2  351.86  4075.7  355.45  4198.4  362.71  4324.6  367.24
  4535.9  361.01  4569.3  359.06  4638.2  356.01  4689.3  356.49  4740.4  352.95
  4754.5  353.42  4803.9  350.43  4822.2  347.99  4854.5  346.42  4892.6  342.77
  4991.5  338.32  5074.9  338.19  5077.7  337.69  5080.9  338.19  5228.6  339.03
  5295.8  342.21  5327.6  343.93  5421.4  352.40  5515.2  357.65  5694.9  360.94
#Mann=6,-1,0
  3153.8    0.05       0  4569.3     0.1       0  4854.5    0.16       0
  5074.9    0.07       0  5080.9    0.16       0  5295.8    0.05       0
Bank Sta=5074.9,5080.9
Exp/Cntr=0.3,0.1

Type RM Length L Ch R = 1,5762,436,436,436
BEGIN DESCRIPTION:
STEELE CREEK TRIB 8 9.0
END DESCRIPTION:
XS GIS Cut Line= 2
      3541169.53     10442991.60      3538675.52     10443490.40
#Sta/Elev= 30
  3077.4  348.19  3217.5  340.76  3319.5  339.14  3407.6  340.24  3625.5  351.53
  3740.7  347.33  3769.7  345.05  3788.6  339.90  3798.8  341.76  3815.6  335.64
  3820.7  338.60  3837.7  337.10  3849.8  343.39  3860.0  344.35  3939.3  344.73
  4279.6  355.95  4534.5  352.60  4733.5  345.63  4942.4  337.45  4971.6  334.18
  4988.3  326.22  4993.4  327.79  4999.2  324.89  5002.0  324.39  5005.2  324.89
  5032.8  334.56  5267.6  337.66  5447.2  352.79  5564.9  357.04  5620.8  357.60
#Mann=9,-1,0
  3077.4    0.16       0  3740.7    0.05       0  3837.7    0.16       0
  3939.3     0.1       0  4733.5    0.16       0  4999.2    0.07       0
  5005.2    0.16       0  5267.6    0.05       0  5564.9    0.16       0
Bank Sta=4999.2,5005.2
Exp/Cntr=0.3,0.1

Type RM Length L Ch R = 1,5326,1202,1202,1202
BEGIN DESCRIPTION:
STEELE CREEK TRIB 8 8.0
END DESCRIPTION:
XS GIS Cut Line= 2
      3541126.10     10442817.98      3538760.65     10443045.85
#Sta/Elev= 30
  3313.7  346.88  3511.0  335.66  3518.6  334.73  3538.7  327.24  3558.8  333.97
  3568.9  335.35  3629.2  334.03  3870.3  337.86  4039.8  334.09  4051.1  329.00
  4061.1  327.90  4091.3  329.93  4130.2  336.95  4252.0  342.47  4372.6  343.47
  4447.4  341.90  4483.2  339.18  4657.2  339.89  4704.1  333.99  4841.7  331.55
  4955.3  328.57  4985.4  325.88  5002.5  322.37  5005.2  321.87  5008.5  322.37
  5065.8  329.45  5246.6  332.28  5417.4  341.83  5640.3  344.57  5690.1  345.00
#Mann=7,-1,0
  3313.7    0.16       0  4039.8    0.05       0  4483.2     0.1       0
  4841.7    0.16       0  5002.5    0.07       0  5008.5    0.16       0
  5640.3    0.05       0
Bank Sta=5002.5,5008.5
Exp/Cntr=0.3,0.1

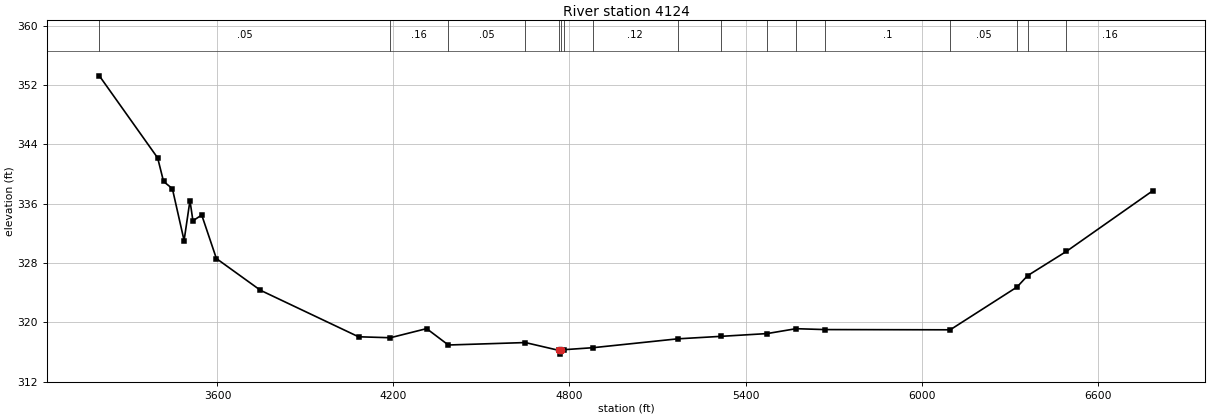
Type RM Length L Ch R = 1,4124,0,0,0
BEGIN DESCRIPTION:
STEELE CREEK TRIB 8 1.0
END DESCRIPTION:
XS GIS Cut Line= 3
      3541950.76     10442134.38      3539162.17     10442015.03
      3538826.47     10442740.58
#Sta/Elev= 30
  3197.5  353.25  3396.3  342.18  3416.4  339.00  3446.4  338.04  3486.4  331.04
  3506.4  336.43  3516.5  333.70  3546.5  334.48  3596.5  328.61  3746.7  324.33
  4081.0  318.06  4189.5  317.93  4313.1  319.16  4387.1  316.95  4649.6  317.28
  4764.6  316.22  4767.3  315.72  4770.6  316.22  4782.1  316.32  4880.9  316.59
  5168.3  317.78  5317.1  318.12  5473.4  318.49  5572.2  319.15  5671.0  319.03
  6097.7  319.00  6325.5  324.77  6361.5  326.30  6494.0  329.58  6788.1  337.75
#Mann=17,-1,0
  3197.5    0.05       0  4189.5    0.16       0  4387.1    0.05       0
  4649.6     0.1       0  4764.6    0.07       0  4770.6     0.1       0
  4782.1    0.05       0  4880.9    0.12       0  5168.3    0.16       0
  5317.1    0.12       0  5473.4    0.16       0  5572.2    0.05       0
  5671.0     0.1       0  6097.7    0.05       0  6325.5     0.1       0
  6361.5    0.05       0  6494.0    0.16       0
Bank Sta=4764.6,4770.6
Exp/Cntr=0.3,0.1

Chan Stop Cuts=-1