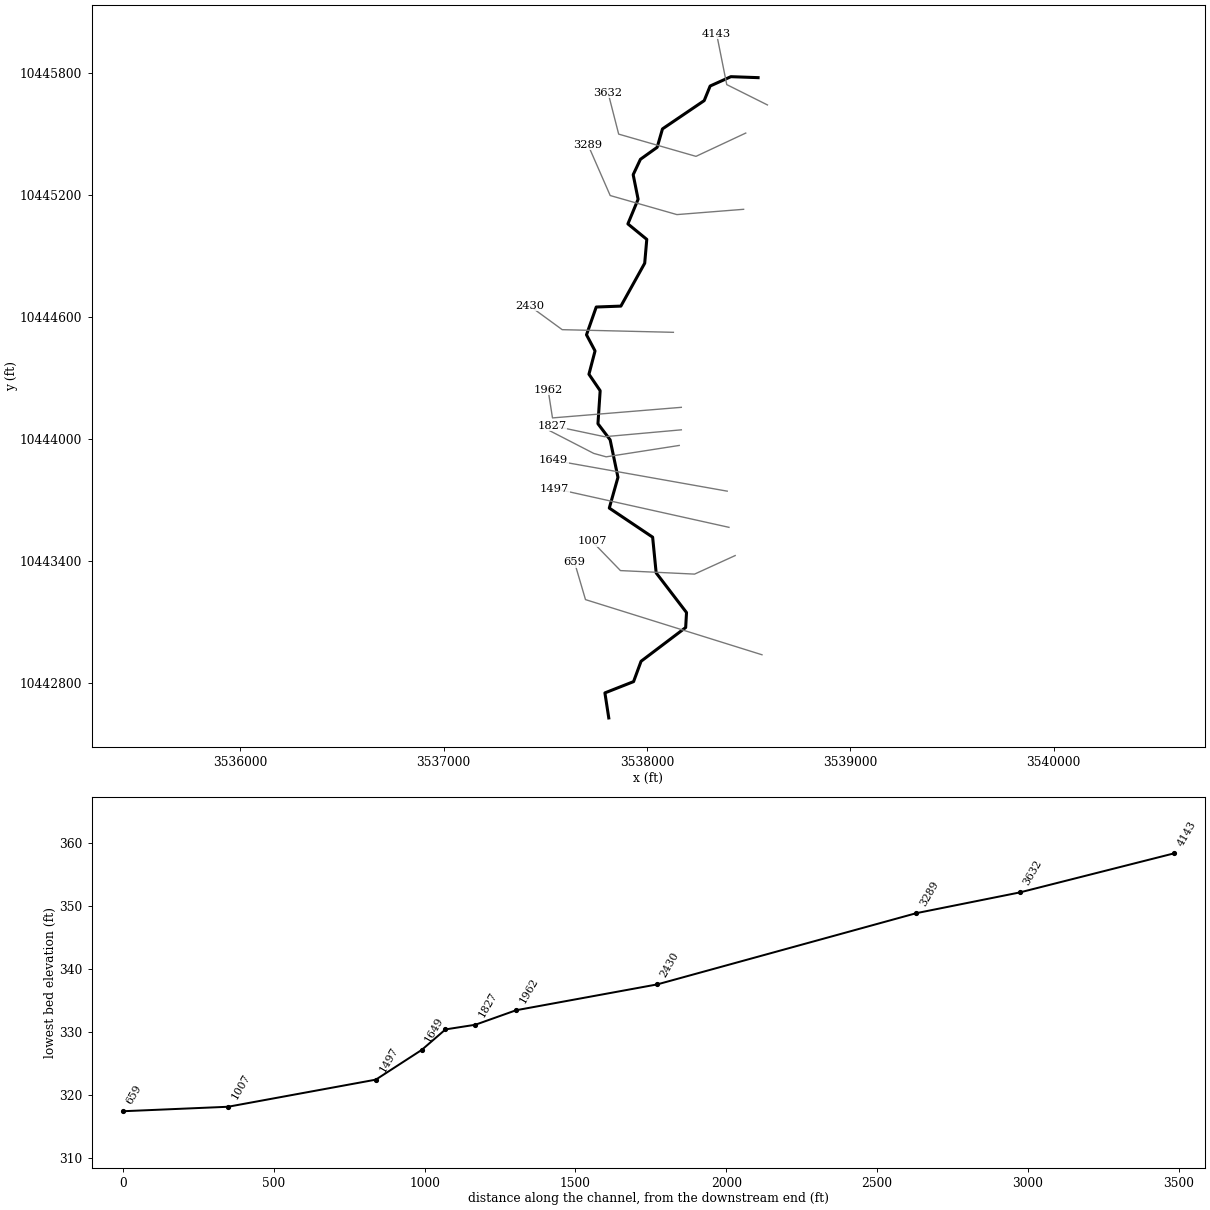
--- STEELE CREEK TRIB 9.prj (project) ---

Proj Title=STEELE CREEK TRIB 9 Base Level Engineering
Current Plan=p01
Default Exp/Contr=0.3,0.1
English Units
Geom File=g01
Flow File=f01
Plan File=p01
Y Axis Title=Elevation
X Axis Title(PF)=Main Channel Distance
X Axis Title(XS)=Station
BEGIN DESCRIPTION:
STEELE CREEK TRIB 9
END DESCRIPTION:
DSS Export Rating Curves= 0
DSS Export Rating Curve Sorted= 0
DSS Export Volume Flow Curves= 0
DXF OffsetX= 0
DXF OffsetY= 0
DXF ScaleX= 1
DXF ScaleY= 10

--- STEELE CREEK TRIB 9.p01 (plan) ---

Plan Title=Multiple Run
Short Identifier=Multiple
Geom File=g01
Flow File=f01
Subcritical Flow
K Sum by GR= 0
Std Step Tol= 0.01
Critical Tol= 0.01
Num of Std Step Trials= 20
Max Error Tol= 0.3
Flow Tol Ratio= 0.001
Split Flow NTrial= 30
Split Flow Tol= 0.02
Split Flow Ratio= 0.02
Log Output Level= 0
Friction Slope Method= 1
Unsteady Friction Slope Method= 2
Unsteady Bridges Friction Slope Method= 1
Parabolic Critical Depth
Global Vel Dist=  1 , 1 , 1
Global Log Level= 0
CheckData=True
Encroach Param= -1, 0, 0, 0
BEGIN DESCRIPTION:
Multiple Run
END DESCRIPTION:

--- STEELE CREEK TRIB 9.f01 (steady flow) ---

Flow Title=Multiple
Number of Profiles=7
Profile Names=10-year,25-year,50-year,1pct_min,100-year,1pct_plu,500-year
River Rch & RM= STEELE CREEK TRI,Reach-1,4143
     352     454     533     459     621     840     836
Boundary for River Rch & Prof#=STEELE CREEK TRI,Reach-1,1
Up Type=0
Dn Type=3
Dn Slope=0.005
Boundary for River Rch & Prof#=STEELE CREEK TRI,Reach-1,2
Up Type=0
Dn Type=3
Dn Slope=0.005
Boundary for River Rch & Prof#=STEELE CREEK TRI,Reach-1,3
Up Type=0
Dn Type=3
Dn Slope=0.005
Boundary for River Rch & Prof#=STEELE CREEK TRI,Reach-1,4
Up Type=0
Dn Type=3
Dn Slope=0.005
Boundary for River Rch & Prof#=STEELE CREEK TRI,Reach-1,5
Up Type=0
Dn Type=3
Dn Slope=0.005
Boundary for River Rch & Prof#=STEELE CREEK TRI,Reach-1,6
Up Type=0
Dn Type=3
Dn Slope=0.005
Boundary for River Rch & Prof#=STEELE CREEK TRI,Reach-1,7
Up Type=0
Dn Type=3
Dn Slope=0.005

--- STEELE CREEK TRIB 9.g01 (geometry) ---

Geom Title=Existing Conditions
Program Version=4.10

River Reach=STEELE CREEK TRI,Reach-1
Reach XY= 30
      3538546.23     10445775.84      3538412.51     10445780.67
      3538310.43     10445734.68      3538281.13     10445662.87
      3538075.99      10445523.8      3538049.81     10445433.17
      3537967.52     10445374.25      3537931.86     10445298.52
      3537956.13     10445177.83      3537905.86     10445056.55
      3537998.75     10444980.43      3537988.56     10444863.08
      3537871.45     10444652.18      3537750.23     10444647.72
       3537702.3     10444511.05       3537744.3      10444431.7
      3537714.32     10444317.12      3537769.47     10444236.17
      3537758.56     10444073.61      3537818.54     10443994.46
      3537857.04     10443809.99      3537814.37     10443658.79
      3538027.56     10443515.73      3538044.92     10443340.04
      3538194.23      10443144.9      3538190.06     10443071.29
      3537970.62     10442905.31      3537933.81     10442805.31
      3537792.84     10442749.76      3537811.82      10442626.6

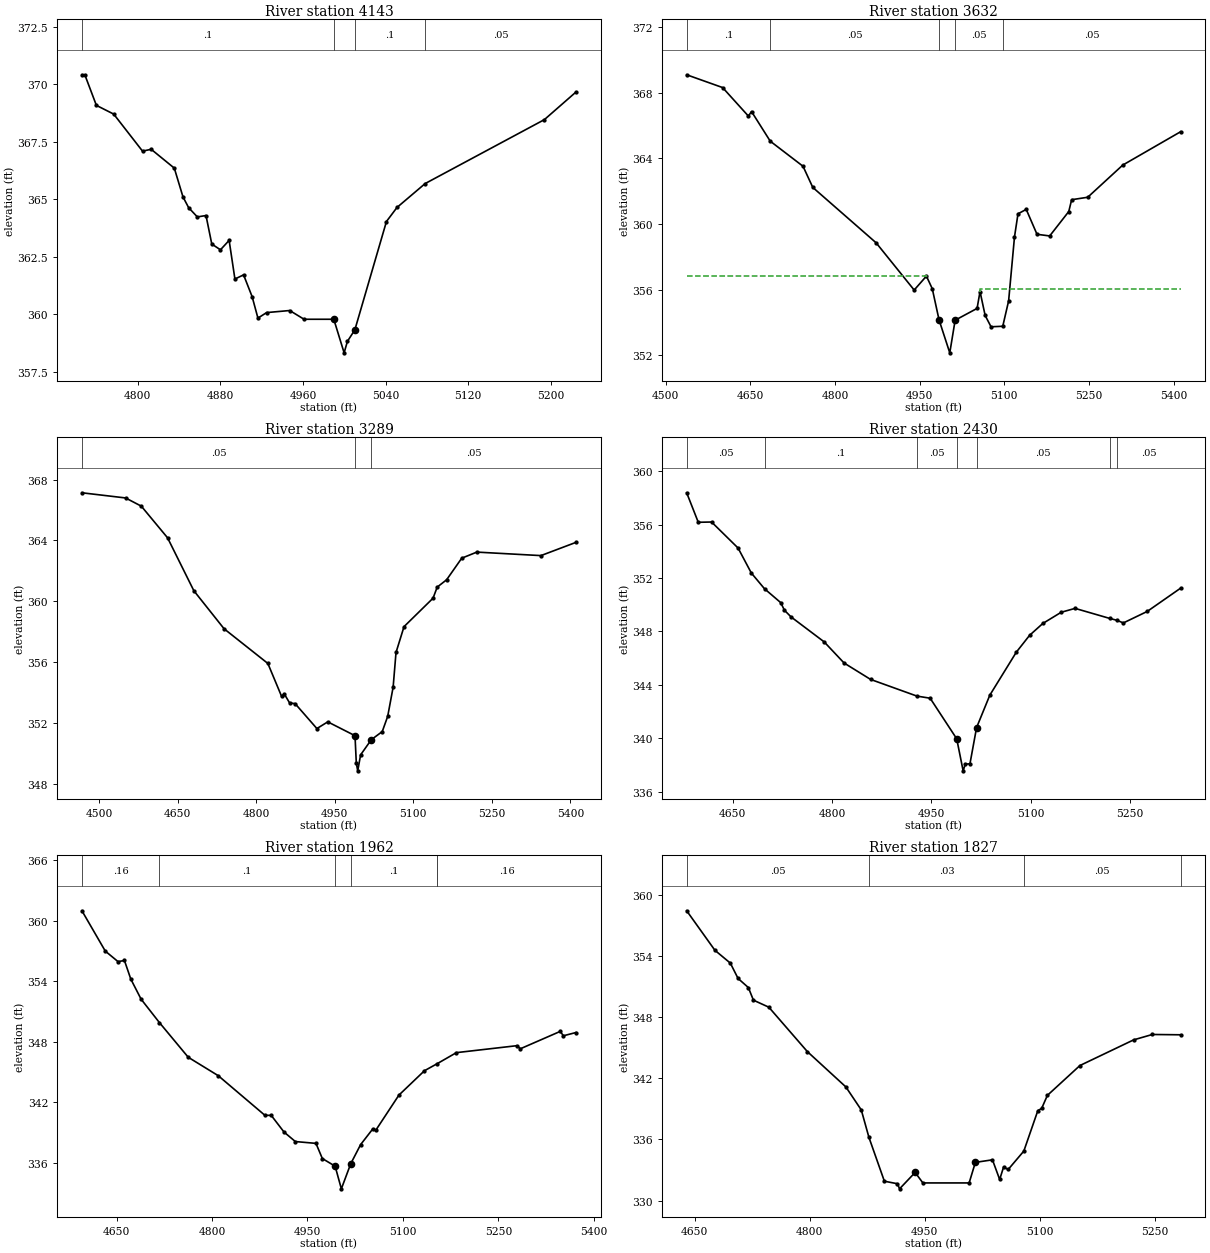
Type RM Length L Ch R = 1 ,4143    ,511,511,511
BEGIN DESCRIPTION:
STEELE CREEK TRIB 9 9.0
END DESCRIPTION:
XS GIS Cut Line= 3
      3538592.13     10445641.63      3538392.11     10445741.64
       3538342.1     10445991.66
#Sta/Elev= 30
  4745.9  370.42  4748.7  370.42  4759.9  369.09  4776.7  368.71  4804.6   367.1
    4813  367.18  4835.4  366.36  4843.8  365.11  4849.3  364.64  4857.7  364.24
  4866.1   364.3  4871.7  363.06  4880.1  362.81  4888.5  363.22  4894.1  361.54
  4902.5  361.72  4910.8  360.77  4916.4  359.84  4924.8  360.08  4947.2  360.17
  4961.1  359.79  4989.9  359.79  4999.9  358.33  5003.1  358.83  5010.3  359.33
  5040.9  364.04  5051.1  364.65  5078.4  365.69  5193.9  368.47  5224.5  369.67
#Mann= 4 ,-1 , 0
  4745.9      .1       0  4989.9    .035       0  5010.3      .1       0
  5078.4     .05       0
Bank Sta=4989.9,5010.3
XS Rating Curve= 0 ,0
Exp/Cntr=0.3,0.1

Type RM Length L Ch R = 1 ,3632    ,343,343,343
BEGIN DESCRIPTION:
STEELE CREEK TRIB 9 8.0
END DESCRIPTION:
XS GIS Cut Line= 4
      3538485.51      10445503.3      3538240.73     10445388.73
      3537860.52      10445498.1      3537808.44     10445701.23
#Sta/Elev= 30
  4537.1   369.1  4600.8  368.32  4646.5  366.58    4652  366.86  4685.2  365.05
  4743.3  363.52  4760.6  362.23  4872.9  358.85  4940.3  355.97    4962  356.82
  4972.4  356.05  4984.4  354.15  5003.4  352.14  5012.9  354.13  5051.8  354.85
    5057  355.88  5066.1  354.42  5076.5  353.73  5097.3  353.76  5107.7  355.31
  5118.1  359.21  5124.3  360.62  5138.9  360.89    5158  359.37  5180.5  359.27
  5214.3  360.76  5219.4  361.48  5247.9  361.63  5309.9  363.59  5412.7  365.63
#Mann= 5 ,-1 , 0
  4537.1      .1       0  4685.2     .05       0  4984.4    .035       0
  5012.9     .05       0  5097.3     .05       0
#XS Ineff= 2 , 0
          4962.5  356.82 5057.27          356.03
Permanent Ineff=
       F       F
Bank Sta=4984.4,5012.9
XS Rating Curve= 0 ,0
Exp/Cntr=0.3,0.1

Type RM Length L Ch R = 1 ,3289    ,859,859,859
BEGIN DESCRIPTION:
STEELE CREEK TRIB 9 7.0
END DESCRIPTION:
XS GIS Cut Line= 4
       3538475.1     10445128.31      3538146.98     10445102.27
      3537818.86     10445196.02      3537709.48     10445446.03
#Sta/Elev= 30
  4467.4  367.13  4550.7  366.79  4580.8  366.25  4630.9  364.17  4681.1  360.69
  4738.8  358.19  4822.4  355.91  4848.7  353.74  4853.9   353.9    4864  353.31
  4874.4  353.27    4916  351.63  4936.8  352.07  4988.8  351.16  4991.3  349.35
    4994  348.85  4999.5   349.9    5020   350.9  5040.8  351.43  5051.2  352.43
  5061.6  354.35  5067.1  356.63  5082.4  358.33  5137.8   360.2  5145.8  360.93
  5163.7  361.41  5192.6  362.83  5221.4  363.23  5343.8     363  5410.7  363.87
#Mann= 3 , 0 , 0
  4467.4     .05       0  4988.8    .035       0    5020     .05       0
Bank Sta=4988.8,5020
XS Rating Curve= 0 ,0
Exp/Cntr=0.3,0.1

Type RM Length L Ch R = 1 ,2430    ,468,468,468
BEGIN DESCRIPTION:
STEELE CREEK TRIB 9 6.0
END DESCRIPTION:
XS GIS Cut Line= 3
      3538129.65     10444523.27      3537582.74      10444536.3
      3537422.12     10444653.51
#Sta/Elev= 30
  4580.6  358.38  4598.1  356.17  4618.2  356.19  4658.2  354.24  4678.2  352.37
  4698.1  351.19  4722.6  350.15  4728.2  349.58  4738.2  349.08  4788.2  347.21
  4818.2  345.63  4858.2   344.4  4928.2  343.15  4948.2  342.99  4988.3  339.95
    4998  337.55  5001.3  338.05  5008.3  338.08  5018.3  340.79  5038.3  343.22
  5078.3  346.44  5098.3   347.7  5118.3  348.59  5146.1  349.43    5167  349.72
  5219.2  348.97    5230  348.83  5239.9  348.63  5275.9  349.49  5326.5  351.24
#Mann= 7 ,-1 , 0
  4580.6     .05       0  4698.1      .1       0  4928.2     .05       0
  4988.3    .035       0  5018.3     .05       0  5219.2      .1       0
    5230     .05       0
Bank Sta=4988.3,5018.3
XS Rating Curve= 0 ,0
Exp/Cntr=0.3,0.1

Type RM Length L Ch R = 1 ,1962    ,135,135,135
BEGIN DESCRIPTION:
STEELE CREEK TRIB 9 5.0
END DESCRIPTION:
XS GIS Cut Line= 3
      3538168.64     10444154.35        3537535.     10444102.27
      3537513.29      10444241.2
#Sta/Elev= 30
  4595.6  360.97  4632.3  356.98  4652.3  355.94  4662.4  356.05  4672.4  354.21
  4688.6  352.22  4717.3  349.91  4762.7  346.47  4809.8  344.65  4883.1  340.73
  4893.1  340.72  4913.2  339.07    4931  338.13  4963.4  337.95  4973.4  336.45
  4993.5  335.69  5003.3  333.45    5018  335.93  5033.6  337.83  5052.3  339.35
  5057.3  339.24  5093.8  342.73  5133.9  345.14    5154  345.84  5184.1  346.93
  5279.4  347.62  5284.5  347.31  5347.2  349.03  5352.3   348.6    5372  348.92
#Mann= 6 ,-1 , 0
  4595.6     .16       0  4717.3      .1       0  4993.5     .03       0
    5018      .1       0    5154     .05       0    5154     .16       0
Bank Sta=4993.5,5018
XS Rating Curve= 0 ,0
Exp/Cntr=0.3,0.1

Type RM Length L Ch R = 1 ,1827    ,99,99,99
BEGIN DESCRIPTION:
Mapping XS 4b1b4823
END DESCRIPTION:
XS GIS Cut Line= 3
      3538168.79     10444043.68      3537791.15     10444009.82
      3537532.01     10444064.51
#Sta/Elev= 30
  4639.7  358.46  4676.5  354.58  4696.6  353.32  4706.7  351.81  4720.1  350.92
  4726.7  349.68  4746.8  348.99    4797  344.63  4847.2  341.16  4867.3   338.9
  4877.3   336.2  4897.4   331.9  4914.5  331.65  4917.2  331.15  4937.5  332.76
  4947.6  331.73  5007.9  331.73 5016.02  333.75  5038.3     334  5047.7  332.07
  5052.8  333.29  5058.8  333.05  5079.2  334.86  5097.4  338.82  5102.5  339.06
  5109.9  340.33  5152.3  343.26  5222.3  345.78  5246.7  346.31  5283.7  346.28
#Mann= 4 ,-1 , 0
  4639.7     .05       0  4877.3     .03       0  5079.2     .05       0
  5283.7      .1       0
Bank Sta=4937.5,5016.02
XS Rating Curve= 0 ,0
Exp/Cntr=0.3,0.1

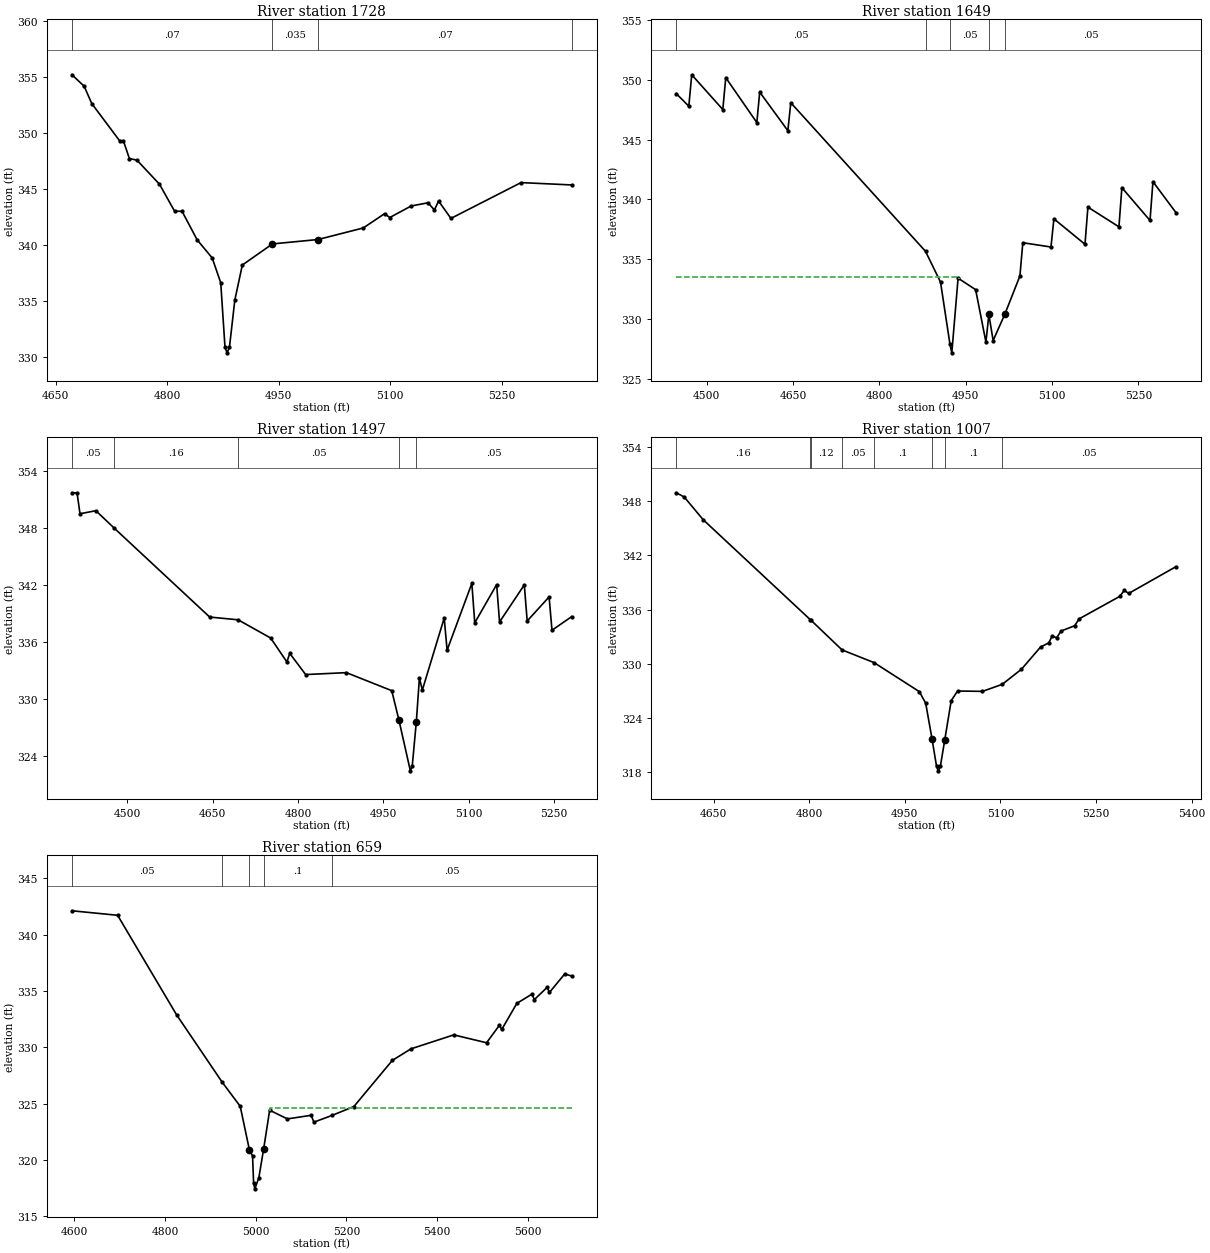
Type RM Length L Ch R = 1 ,1728    ,79,79,79
BEGIN DESCRIPTION:
Mapping XS 37821a97
END DESCRIPTION:
XS GIS Cut Line= 4
      3538158.35     10443966.86      3537798.96     10443910.86
      3537737.76     10443927.79      3537520.32     10444039.77
#Sta/Elev= 30
    4672  355.17  4688.4  354.15  4698.6  352.61  4736.2  349.28  4741.2  349.27
  4749.2  347.71  4759.3  347.57  4789.6  345.43  4809.9  343.03    4820  343.01
  4840.3  340.47  4860.5  338.86    4872  336.64  4877.7  330.91  4880.5  330.41
  4883.7  330.91  4890.9   335.1    4901  338.23  4941.5  340.11  5002.7   340.5
  5063.6  341.53  5092.2   342.8  5099.2  342.46  5128.1  343.49  5150.6  343.77
  5159.2  343.13  5164.8  343.93  5181.4  342.38  5275.7  345.57  5343.8  345.36
#Mann= 4 ,-1 , 0
    4672     .07       0  4941.5    .035       0  5002.7     .07       0
  5343.8      .1       0
#Block Obstruct= 2 , 0
         4934.55  339.95
Bank Sta=4941.5,5002.7
XS Rating Curve= 0 ,0
Exp/Cntr=0.3,0.1

Type RM Length L Ch R = 1 ,1649    ,152,152,152
BEGIN DESCRIPTION:
STEELE CREEK TRIB 9 4.0
END DESCRIPTION:
XS GIS Cut Line= 2
      3538394.36     10443742.03      3537539.35     10443893.93
#Sta/Elev= 30
    4447  348.86  4468.9   347.8    4474  350.43    4528  347.52  4533.1  350.19
  4587.1  346.43  4592.1  348.98    4641  345.75  4646.1  348.09  4880.2  335.65
  4906.3  333.07  4922.7  327.86  4925.9  327.15  4936.8   333.4  4967.3  332.44
  4985.2  328.05  4990.3  330.36  4997.7  328.18  5018.1  330.39  5044.2  333.58
  5049.3  336.37  5098.2  336.01  5103.3  338.37  5157.3  336.24  5162.4  339.35
  5216.3   337.7  5221.4  340.98  5270.3  338.23  5275.4  341.48  5315.4  338.89
#Mann= 5 ,-1 , 0
    4447     .05       0  4880.2      .1       0  4922.7     .05       0
  4990.3     .05       0  5018.1     .05       0
#XS Ineff= 2 , 0
         4938.07  333.49
Permanent Ineff=
       F       F
#Block Obstruct= 2 , 0
         4984.09  327.97
Bank Sta=4990.3,5018.1
XS Rating Curve= 0 ,0
Exp/Cntr=0.3,0.1

Type RM Length L Ch R = 1 ,1497    ,490,490,490
BEGIN DESCRIPTION:
STEELE CREEK TRIB 9 3.0
END DESCRIPTION:
XS GIS Cut Line= 2
      3538403.09     10443564.07      3537545.41     10443754.66
#Sta/Elev= 30
  4402.8  351.75  4411.8  351.73  4416.9  349.54  4444.8  349.86  4476.6  348.05
  4644.9  338.65  4694.9  338.36  4752.1  336.44  4780.6  333.92  4785.7  334.82
  4813.6  332.59  4885.3  332.79    4965  330.89  4977.5  327.82  4997.7  322.44
    5001  322.94  5008.2  327.61  5013.6  332.21  5018.8  330.96  5057.2  338.55
  5062.3  335.16  5105.8   342.2  5110.9  338.04  5149.4  342.07  5154.5  338.13
    5198  342.04  5203.1  338.24  5241.6  340.77  5246.7  337.26  5281.4   338.7
#Mann= 5 ,-1 , 0
  4402.8     .05       0  4476.6     .16       0  4694.9     .05       0
  4977.5     .05       0  5008.2     .05       0
Bank Sta=4977.5,5008.2
XS Rating Curve= 0 ,0
Exp/Cntr=0.3,0.1

Type RM Length L Ch R = 1 ,1007    ,348,348,348
BEGIN DESCRIPTION:
STEELE CREEK TRIB 9 2.0
END DESCRIPTION:
XS GIS Cut Line= 4
      3538433.47      10443425.2      3538233.79     10443334.04
       3537869.2      10443351.4      3537730.32     10443494.62
#Sta/Elev= 30
  4591.3  348.93  4603.8  348.47  4633.6  345.95  4801.5  334.89  4802.1  334.86
  4851.5  331.53  4901.8  330.12  4972.7  326.91  4982.7  325.63  4992.7  321.64
  4999.7  318.64  5002.5  318.14  5005.7  318.64  5012.7  321.61  5022.7  325.91
  5032.7  326.98  5071.8  326.94  5102.8  327.72  5132.9  329.39  5162.9  331.85
  5175.8  332.31    5181  333.07  5188.1  332.88  5195.1  333.62  5216.4  334.21
  5223.4  334.97  5287.2  337.46  5294.1  338.11  5301.3  337.79  5375.3  340.75
#Mann= 8 ,-1 , 0
  4591.3     .16       0  4801.5     .05       0  4802.1     .12       0
  4851.5     .05       0  4901.8      .1       0  4992.7     .05       0
  5012.7      .1       0  5102.8     .05       0
Bank Sta=4992.7,5012.7
XS Rating Curve= 0 ,0
Exp/Cntr=0.3,0.1

Type RM Length L Ch R = 1 ,659     ,0,0,0
BEGIN DESCRIPTION:
STEELE CREEK TRIB 9 1.0
END DESCRIPTION:
XS GIS Cut Line= 3
      3538565.36     10442937.34      3537697.33      10443208.6
      3537643.08     10443393.06
#Sta/Elev= 30
    4595  342.12  4695.6  341.72  4825.5  332.89  4926.5  326.88  4965.9  324.76
  4986.1   320.9  4993.1  320.35  4995.4  317.93  4998.1  317.43    5007  318.42
  5017.5  320.96  5030.8  324.41  5069.9  323.64  5122.3  323.96  5128.3  323.35
  5168.3  323.95  5216.5  324.74  5301.1  328.83  5342.3  329.86  5436.6   331.1
    5509   330.4  5537.2  331.95  5542.4  331.58  5575.7   333.9  5609.1  334.72
  5614.3  334.23  5642.4  335.32  5647.6  334.87    5681   336.5  5696.7  336.33
#Mann= 5 ,-1 , 0
    4595     .05       0  4926.5      .1       0  4986.1     .05       0
  5017.5      .1       0  5168.3     .05       0
#XS Ineff= 2 , 0
                         5032.39          324.61
Permanent Ineff=
       F       F
Bank Sta=4986.1,5017.5
XS Rating Curve= 0 ,0
Exp/Cntr=0.3,0.1

Chan Stop Cuts=-1
Use User Specified Reach Order=0
Composite Channel Slope=5