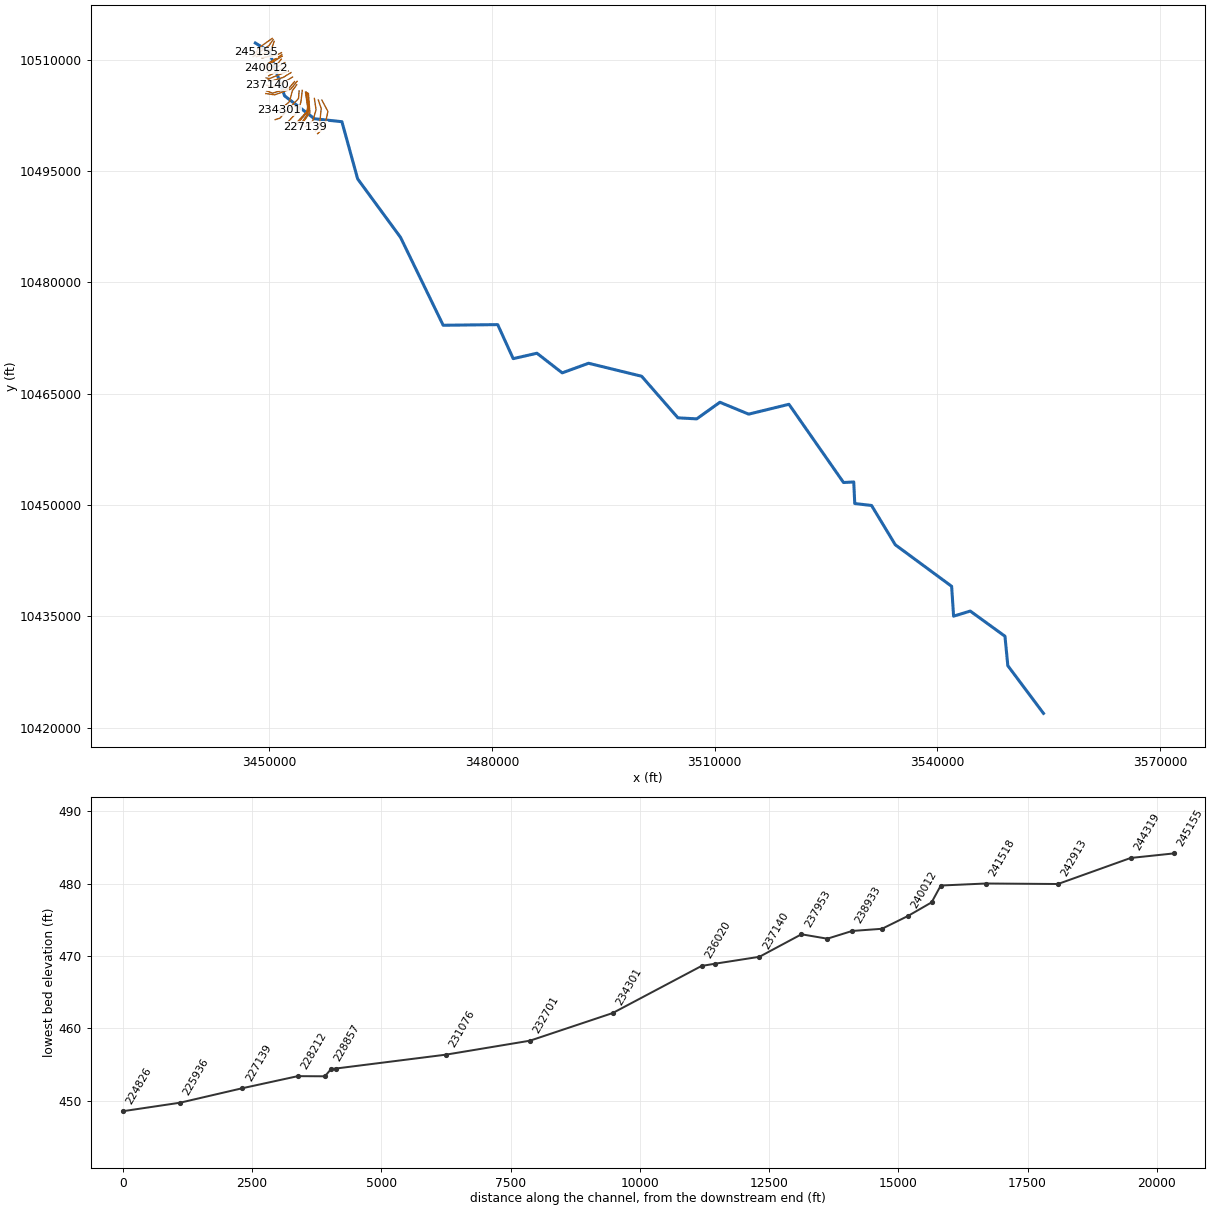
--- STEELE CREEK.prj (project) ---

Proj Title=STEELE CREEK Base Level Engineering
Current Plan=p01
Default Exp/Contr=0.3,0.1
English Units
Geom File=g01
Flow File=f01
Plan File=p01
Y Axis Title=Elevation
X Axis Title(PF)=Main Channel Distance
X Axis Title(XS)=Station
BEGIN DESCRIPTION:
STEELE CREEK
END DESCRIPTION:
DSS Export Rating Curves= 0
DSS Export Rating Curve Sorted= 0
DSS Export Volume Flow Curves= 0
DXF OffsetX= 0
DXF OffsetY= 0
DXF ScaleX= 1
DXF ScaleY= 10

--- STEELE CREEK.p01 (plan) ---

Plan Title=Multiple Run
Short Identifier=Multiple
Geom File=g01
Flow File=f01
Subcritical Flow
K Sum by GR= 0
Std Step Tol= 0.01
Critical Tol= 0.01
Num of Std Step Trials= 20
Max Error Tol= 0.3
Flow Tol Ratio= 0.001
Split Flow NTrial= 30
Split Flow Tol= 0.02
Split Flow Ratio= 0.02
Log Output Level= 0
Friction Slope Method= 1
Unsteady Friction Slope Method= 2
Unsteady Bridges Friction Slope Method= 1
Parabolic Critical Depth
Global Vel Dist=  1 , 1 , 1
Global Log Level= 0
CheckData=True
Encroach Param= -1, 0, 0, 0
BEGIN DESCRIPTION:
Multiple Run
END DESCRIPTION:

--- STEELE CREEK.f01 (steady flow) ---

Flow Title=Multiple
Program Version=4.10
Number of Profiles= 7
Profile Names=10-year,25-year,50-year,1pct_min,100-year,1pct_plu,500-year
River Rch & RM=STEELE CREEK,Reach-1         ,245155
    1499    2116    2637    2395    3239    4380    4876
River Rch & RM=STEELE CREEK,Reach-1         ,244319
    1954    2788    3499    3197    4323    5846    6588
River Rch & RM=STEELE CREEK,Reach-1         ,240647
    2214    3167    3982    3641    4924    6659    7520
River Rch & RM=STEELE CREEK,Reach-1         ,234301
    3780    5500    6993    6453    8727   11803   13577
River Rch & RM=STEELE CREEK,Reach-1         ,221312
    4485    6547    8341    7708   10424   14098   16262
River Rch & RM=STEELE CREEK,Reach-1         ,214549
    5089    7443    9495    8782   11877   16063   18559
River Rch & RM=STEELE CREEK,Reach-1         ,206387
    5563    8145   10397    9620   13010   17595   20343
River Rch & RM=STEELE CREEK,Reach-1         ,203420
    5563    8145   10397    9620   13010   17595   20343
River Rch & RM=STEELE CREEK,Reach-1         ,201023
    6272    9191   11741   10865   14694   19872   22981
River Rch & RM=STEELE CREEK,Reach-1         ,200708
    6272    9191   11741   10865   14694   19872   22981
River Rch & RM=STEELE CREEK,Reach-1         ,197421
    6272    9191   11741   10865   14694   19872   22981
River Rch & RM=STEELE CREEK,Reach-1         ,193447
    7103   10424   13329   12344   16693   22576   26140
River Rch & RM=STEELE CREEK,Reach-1         ,187108
    7103   10424   13329   12344   16693   22576   26140
River Rch & RM=STEELE CREEK,Reach-1         ,179781
   11072   16384   21073   19612   26523   35870   41922
River Rch & RM=STEELE CREEK,Reach-1         ,163593
   11072   16384   21073   19612   26523   35870   41922
River Rch & RM=STEELE CREEK,Reach-1         ,157650
   11072   16384   21073   19612   26523   35870   41922
River Rch & RM=STEELE CREEK,Reach-1         ,152647
   11369   16821   21634   20131   27225   36818   43017
River Rch & RM=STEELE CREEK,Reach-1         ,146019
   11214   16543   21232   19714   26662   36057   41943
River Rch & RM=STEELE CREEK,Reach-1         ,141951
   11350   16715   21429   19872   26875   36345   42170
River Rch & RM=STEELE CREEK,Reach-1         ,131886
   11350   16715   21429   19872   26875   36345   42170
River Rch & RM=STEELE CREEK,Reach-1         ,128685
   12854   18983   24385   22656   30640   41437   48250
River Rch & RM=STEELE CREEK,Reach-1         ,124384
   12854   18983   24385   22656   30640   41437   48250
River Rch & RM=STEELE CREEK,Reach-1         ,120492
   15513   22956   29538   27480   37164   50260   58661
River Rch & RM=STEELE CREEK,Reach-1         ,110799
   15563   23007   29583   27503   37194   50301   58624
River Rch & RM=STEELE CREEK,Reach-1         ,107287
   16219   23963   30803   28624   38710   52351   60956
River Rch & RM=STEELE CREEK,Reach-1         ,104642
   16219   23963   30803   28624   38710   52351   60956
River Rch & RM=STEELE CREEK,Reach-1         ,97040
   17347   25685   33068   30777   41622   56289   65737
River Rch & RM=STEELE CREEK,Reach-1         ,95545
   17900   26507   34130   31767   42962   58101   67858
River Rch & RM=STEELE CREEK,Reach-1         ,91543
   17691   26144   33616   31244   42253   57143   66545
River Rch & RM=STEELE CREEK,Reach-1         ,87660
   17962   26538   34116   31703   42874   57982   67493
River Rch & RM=STEELE CREEK,Reach-1         ,82661
   17962   26538   34116   31703   42874   57982   67493
River Rch & RM=STEELE CREEK,Reach-1         ,80691
   17962   26538   34116   31703   42874   57982   67493
River Rch & RM=STEELE CREEK,Reach-1         ,77769
   17989   26564   34137   31709   42883   57995   67454
River Rch & RM=STEELE CREEK,Reach-1         ,75918
   17937   26469   34000   31567   42690   57734   67086
River Rch & RM=STEELE CREEK,Reach-1         ,68399
   18157   26781   34389   31917   43165   58375   67782
River Rch & RM=STEELE CREEK,Reach-1         ,64019
   18157   26781   34389   31917   43165   58375   67782
River Rch & RM=STEELE CREEK,Reach-1         ,59877
   18927   27902   35818   33231   44941   60777   70510
River Rch & RM=STEELE CREEK,Reach-1         ,56975
   18927   27902   35818   33231   44941   60777   70510
River Rch & RM=STEELE CREEK,Reach-1         ,55329.35
   19148   28230   36242   33626   45476   61501   71358
River Rch & RM=STEELE CREEK,Reach-1         ,53239
   19148   28230   36242   33626   45476   61501   71358
River Rch & RM=STEELE CREEK,Reach-1         ,50937
   19258   28402   36472   33848   45775   61906   71863
River Rch & RM=STEELE CREEK,Reach-1         ,48139
   19084   28104   36052   33424   45202   61130   70813
River Rch & RM=STEELE CREEK,Reach-1         ,40563
   19602   28861   37020   34316   46408   62761   72677
River Rch & RM=STEELE CREEK,Reach-1         ,34169
   19869   29261   37541   34806   47071   63658   73742
River Rch & RM=STEELE CREEK,Reach-1         ,30283
   19869   29261   37541   34806   47071   63658   73742
River Rch & RM=STEELE CREEK,Reach-1         ,22937
   19760   29066   37260   34515   46678   63126   73000
River Rch & RM=STEELE CREEK,Reach-1         ,18527
   20380   29998   38473   35657   48221   65214   75482
River Rch & RM=STEELE CREEK,Reach-1         ,13295
   20380   29998   38473   35657   48221   65214   75482
River Rch & RM=STEELE CREEK,Reach-1         ,7816
   20504   30169   38683   35841   48471   65551   75830
Boundary for River Rch & Prof#=STEELE CREEK,Reach-1         , 1
Up Type= 0
Dn Type= 3
Dn Slope=0.001
Boundary for River Rch & Prof#=STEELE CREEK,Reach-1         , 2
Up Type= 0
Dn Type= 3
Dn Slope=0.001
Boundary for River Rch & Prof#=STEELE CREEK,Reach-1         , 3
Up Type= 0
Dn Type= 3
Dn Slope=0.001
Boundary for River Rch & Prof#=STEELE CREEK,Reach-1         , 4
Up Type= 0
Dn Type= 3
Dn Slope=0.001
Boundary for River Rch & Prof#=STEELE CREEK,Reach-1         , 5
Up Type= 0
Dn Type= 3
Dn Slope=0.001
Boundary for River Rch & Prof#=STEELE CREEK,Reach-1         , 6
Up Type= 0
Dn Type= 3
Dn Slope=0.001
Boundary for River Rch & Prof#=STEELE CREEK,Reach-1         , 7
Up Type= 0
Dn Type= 3
Dn Slope=0.001
DSS Import GetInterval= 0
DSS Import GetPeak= 0
DSS Import FillOption= 0

--- STEELE CREEK.g01 (geometry) ---

Geom Title=Existing Conditions
Program Version=4.10

River Reach=STEELE CREEK    ,Reach-1
Reach XY= 30
      3448160.73     10512261.23      3450051.29     10511104.69
      3452097.59     10505140.82      3456114.21     10502055.61
      3459817.26     10501653.79      3461938.01      10493948.9
      3467710.06     10486070.97      3473453.81     10474220.07
      3480794.76     10474307.44      3482882.21     10469721.85
      3486080.87     10470448.94      3489476.34     10467805.46
      3493027.55     10469098.86      3500173.11     10467348.33
      3505061.13      10461743.3      3507590.91       10461605.
      3510712.69      10463841.2       3514585.3     10462241.31
      3520011.06     10463569.11      3527359.57     10453025.44
      3528733.38     10453101.96      3528869.72     10450193.87
      3531132.49     10449930.73      3534330.11     10444631.65
      3541914.14     10439038.13      3542179.09     10435013.94
      3544419.95     10435701.35      3549093.47     10432309.33
      3549482.21     10428336.69      3554282.11     10421911.64

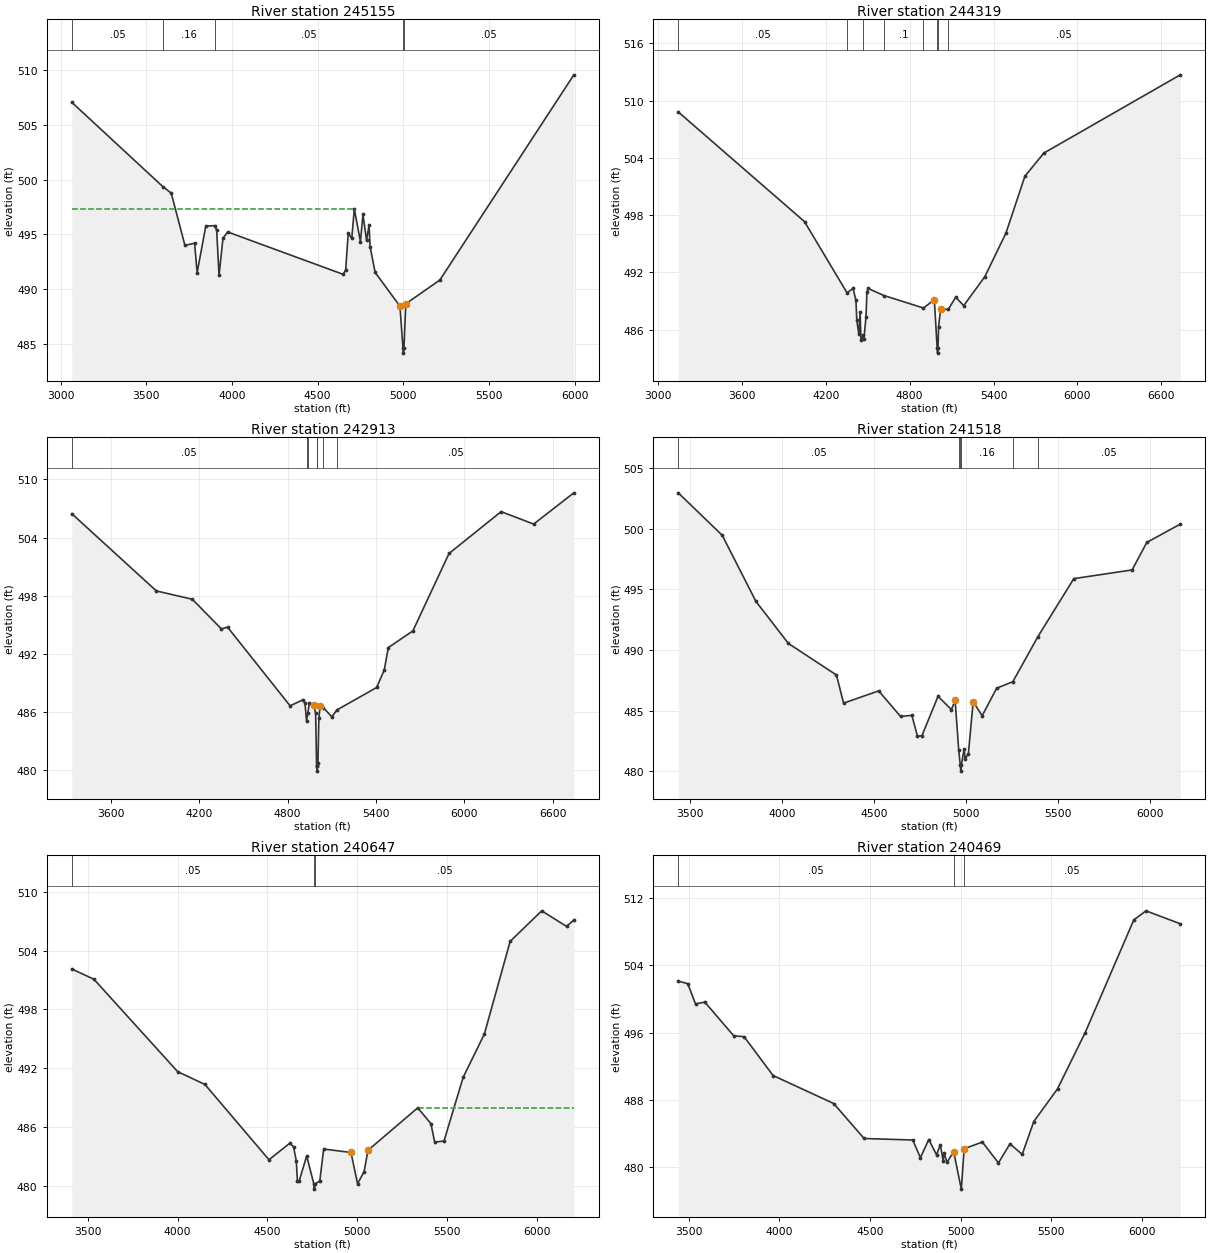
Type RM Length L Ch R = 1 ,245155  ,836,836,836
BEGIN DESCRIPTION:
STEELE CREEK 158.0
END DESCRIPTION:
XS GIS Cut Line= 3
      3450442.12     10512891.66      3448892.11     10511791.64
      3448242.08     10510991.61
#Sta/Elev= 30
  3064.5  507.08  3596.6  499.37  3645.2  498.78  3725.2  494.01  3781.7   494.2
  3796.5  491.51  3846.9  495.76  3899.7  495.81  3910.6  495.37  3924.4  491.28
  3947.4  494.66  3974.9  495.23    4649  491.36  4663.8  491.76  4678.5  495.11
  4699.5  494.65  4714.2  497.34  4749.9  494.35  4764.7  496.83  4785.6  494.48
  4800.3  495.84  4806.5  493.86    4836  491.53 4980.68  488.45  4998.1  484.66
  5000.9  484.16  5004.1  484.66 5014.77  488.67  5213.7  490.84    5996  509.59
#Mann= 5 ,-1 , 0
  3064.5     .05       0  3596.6     .16       0  3899.7     .05       0
  4998.1     .03       0  5004.1     .05       0
#XS Ineff= 2 , 0
         4716.48  497.31
Permanent Ineff=
       F       F
Bank Sta=4980.68,5014.77
XS Rating Curve= 0 ,0
Exp/Cntr=0.3,0.1

Type RM Length L Ch R = 1 ,244319  ,1406,1406,1406
BEGIN DESCRIPTION:
STEELE CREEK 156.0
END DESCRIPTION:
XS GIS Cut Line= 4
      3450568.33     10512716.86      3450000.64     10511920.01
      3448922.52     10511196.05      3447859.98     10510419.99
#Sta/Elev= 30
  3143.8  508.82  4047.4  497.32  4352.2  489.84  4394.4  490.32  4415.4  489.07
  4421.6  486.97  4436.4  485.49  4445.4   487.8  4451.4  484.87  4468.2  485.38
  4472.4  484.98  4487.4  487.32  4493.8  489.92  4502.4  490.31  4615.6  489.57
  4898.7  488.26  4976.5  489.13  4996.7  484.03  4999.5  483.53  5002.7  484.03
  5006.5  486.27  5021.5  488.13  5076.2  488.12  5129.5   489.4  5186.5  488.51
    5337  491.53  5488.5   496.1  5624.5  502.08  5760.4  504.51  6736.6  512.71
#Mann= 8 ,-1 , 0
  3143.8     .05       0  4352.2     .12       0  4468.2     .16       0
  4615.6      .1       0  4898.7     .16       0  4996.7     .07       0
  5002.7     .16       0  5076.2     .05       0
Bank Sta=4976.5,5021.5
XS Rating Curve= 0 ,0
Exp/Cntr=0.3,0.1

Type RM Length L Ch R = 1 ,242913  ,1395,1395,1395
BEGIN DESCRIPTION:
STEELE CREEK 154.0
END DESCRIPTION:
XS GIS Cut Line= 4
      3450693.33     10512492.88      3450323.56     10511420.01
      3449386.06     10510836.68      3448297.53     10510404.39
#Sta/Elev= 30
  3334.7  506.46  3909.3   498.5  4153.7  497.64  4351.4  494.58  4392.8  494.77
  4817.6  486.66  4906.2  487.29  4918.8  486.92  4929.3   485.1  4937.9  485.91
  4948.7  486.99  4977.7  486.73  4991.1  485.93  4997.6  480.43  5000.4  479.93
  5003.6  480.43  5006.5  480.76    5013  485.41  5021.8  486.66  5042.9  486.48
  5100.9  485.53  5136.3  486.24  5405.5  488.55  5457.4  490.36  5484.5  492.66
  5651.5  494.38  5897.1  502.36  6250.8  506.67  6472.1  505.39  6744.9  508.61
#Mann= 7 ,-1 , 0
  3334.7     .05       0  4929.3     .12       0  4937.9     .16       0
  4997.6     .07       0  5003.6     .16       0  5042.9     .12       0
  5136.3     .05       0
Bank Sta=4977.7,5021.8
XS Rating Curve= 0 ,0
Exp/Cntr=0.3,0.1

Type RM Length L Ch R = 1 ,241518  ,871,871,871
BEGIN DESCRIPTION:
STEELE CREEK 152.0
END DESCRIPTION:
XS GIS Cut Line= 4
      3451688.17     10510956.48      3451146.47     10510701.26
      3449719.39     10510388.76      3449063.14     10510268.97
#Sta/Elev= 30
  3437.4  502.96  3676.7  499.45    3859  494.01  4035.9  490.53  4296.6  487.93
  4335.4  485.61  4526.1  486.62  4644.7  484.51  4706.1   484.6  4736.8  482.88
  4760.7  482.92  4848.4  486.17  4921.1  485.08  4941.2  485.83  4960.6  481.77
  4969.2   480.5    4972     480  4975.2   480.5  4990.2  481.85  4995.3  481.01
  5013.2  481.43  5039.2  485.73  5088.1  484.57  5166.7  486.84  5254.8  487.38
  5390.2  491.08  5585.8  495.88  5902.4   496.6  5982.3  498.87  6164.2  500.38
#Mann= 6 ,-1 , 0
  3437.4     .05       0  4960.6     .16       0  4969.2     .07       0
  4975.2     .16       0  5254.8      .1       0  5390.2     .05       0
Bank Sta=4941.2,5039.2
XS Rating Curve= 0 ,0
Exp/Cntr=0.3,0.1

Type RM Length L Ch R = 1 ,240647  ,178,178,178
BEGIN DESCRIPTION:
STEELE CREEK 151.0
END DESCRIPTION:
XS GIS Cut Line= 2
      3451724.63     10510670.03       3449360.8     10509186.12
#Sta/Elev= 30
  3412.2  502.12  3535.3  501.08  4000.6  491.68  4152.6  490.37  4508.4  482.71
  4623.9  484.39  4645.1  484.03  4660.4  482.58  4666.7  480.51  4675.7  480.51
  4718.1   483.1  4758.2  480.22  4760.9  479.72  4764.2  480.22  4791.1  480.57
  4812.4   483.8  4964.3  483.45  5000.9  480.26  5037.4  481.51  5058.6  483.67
  5335.4  487.99  5408.5  486.39  5429.7  484.51  5481.4  484.61  5587.7  491.09
  5705.8   495.5  5849.1  504.93  6024.5  508.04  6162.5  506.46  6203.2  507.11
#Mann= 3 ,-1 , 0
  3412.2     .05       0  4758.2    .035       0  4764.2     .05       0
#XS Ineff= 2 , 0
                         5335.28             488
Permanent Ineff=
       F       F
Bank Sta=4964.3,5058.6
XS Rating Curve= 0 ,0
Exp/Cntr=0.3,0.1

Type RM Length L Ch R = 1 ,240469  ,457,457,457
BEGIN DESCRIPTION:
STEELE CREEK 150.0
END DESCRIPTION:
XS GIS Cut Line= 2
       3451776.7     10510487.73      3449422.51     10509029.38
#Sta/Elev= 30
  3441.8  502.13  3494.3  501.82  3537.1  499.41  3588.4  499.63  3747.4  495.63
  3805.3  495.51  3964.8   490.9  4299.2  487.57    4467  483.41  4735.2  483.23
  4777.7  481.13  4823.5  483.29  4866.4  481.47  4887.6  482.67    4903  480.78
  4908.9  481.64  4924.3  480.56  4960.9  481.86  5003.2  477.39  5018.8  482.19
  5119.2  482.99  5207.8  480.51  5271.6  482.77    5339  481.52  5402.8  485.42
  5533.9  489.32  5686.4     496  5954.6   509.4  6021.9  510.48  6211.1  508.94
#Mann= 3 , 0 , 0
  3441.8     .05       0  4960.9     .04       0  5018.8     .05       0
Bank Sta=4960.9,5018.8
XS Rating Curve= 0 ,0
Exp/Cntr=0.3,0.1

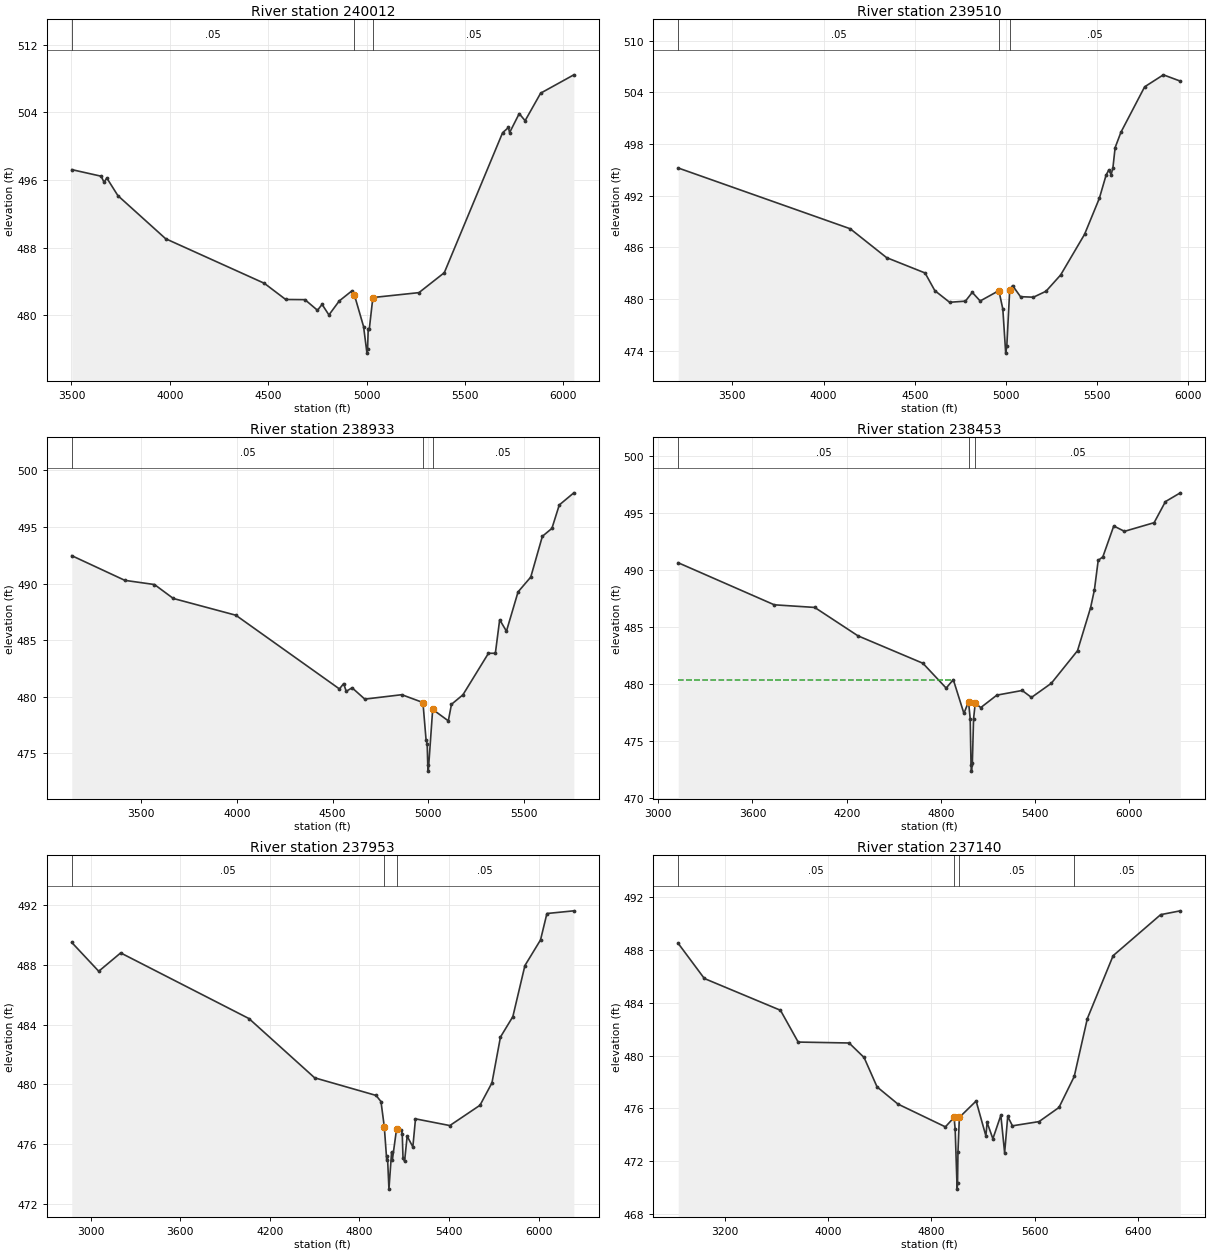
Type RM Length L Ch R = 1 ,240012  ,502,502,502
BEGIN DESCRIPTION:
STEELE CREEK 149.0
END DESCRIPTION:
XS GIS Cut Line= 4
       3451656.9     10510086.69      3451229.81     10509534.59
      3450120.43     10509060.63      3449517.22     10508826.63
#Sta/Elev= 30
  3501.4  497.23  3650.7  496.45  3665.2  495.74  3679.6  496.23  3735.8  494.15
  3978.5  489.05  4479.6  483.78  4588.4  481.86  4686.3  481.84  4750.1  480.58
  4773.3  481.28  4808.2  480.03  4860.8  481.69  4925.5  482.89  4937.1  482.44
  4984.3  478.65  5001.4  475.51  5004.6  476.01  5007.9  478.39  5013.3  478.36
  5031.5  482.09  5265.6  482.67  5394.5  485.03  5690.8   501.6  5720.7  502.22
  5726.1   501.6  5775.2  503.86  5805.1  503.02  5884.1  506.28  6052.8  508.45
#Mann= 3 , 0 , 0
  3501.4     .05       0  4937.1    .035       0  5031.5     .05       0
Bank Sta=4937.1,5031.5
XS Rating Curve= 0 ,0
Exp/Cntr=0.3,0.1

Type RM Length L Ch R = 1 ,239510  ,577,577,577
BEGIN DESCRIPTION:
STEELE CREEK 146.0
END DESCRIPTION:
XS GIS Cut Line= 2
      3452130.85     10509617.93      3449729.84     10508268.98
#Sta/Elev= 30
  3202.9  495.22  4146.2  488.17  4345.8  484.82  4556.8  483.04  4610.4  480.99
  4691.4  479.64  4778.1  479.77  4815.7  480.79  4859.1  479.79  4961.7  480.99
  4983.4  478.85  4999.1  473.74  5005.1  474.53    5021  481.03  5036.7  481.58
  5080.3  480.29  5151.4  480.23  5220.2  480.92  5300.5  482.81  5431.6  487.52
  5512.6  491.69  5550.2  494.42  5564.3  494.97  5577.6  494.46  5587.3  495.25
  5599.3  497.58  5631.2  499.37  5761.3  504.64  5863.9  506.03  5956.9   505.3
#Mann= 3 , 0 , 0
  3202.9     .05       0  4961.7    .035       0    5021     .05       0
Bank Sta=4961.7,5021
XS Rating Curve= 0 ,0
Exp/Cntr=0.3,0.1

Type RM Length L Ch R = 1 ,238933  ,480,480,480
BEGIN DESCRIPTION:
STEELE CREEK 145.0
END DESCRIPTION:
XS GIS Cut Line= 2
      3452281.86     10509055.41      3449958.95     10507841.87
#Sta/Elev= 30
  3138.6  492.47  3415.7  490.29  3570.3  489.92  3668.6  488.69    3995  487.21
  4535.7   480.7  4557.8  481.17  4571.2  480.49  4601.9   480.8  4668.2   479.8
  4861.3  480.19  4971.7   479.5  4988.1  476.18  4993.8  475.84  4996.9  473.94
  4999.7  473.44  5022.5  478.89  5104.2  477.88  5120.6  479.34  5180.4  480.18
  5313.7  483.85  5349.7  483.85  5372.2  486.81  5407.6   485.8  5468.2  489.27
  5534.5  490.58  5595.1  494.18  5644.9  494.88  5683.4  496.95  5759.4  498.02
#Mann= 3 , 0 , 0
  3138.6     .05       0  4971.7    .035       0  5022.5     .05       0
Bank Sta=4971.7,5022.5
XS Rating Curve= 0 ,0
Exp/Cntr=0.3,0.1

Type RM Length L Ch R = 1 ,238453  ,500,500,500
BEGIN DESCRIPTION:
STEELE CREEK 143.0
END DESCRIPTION:
XS GIS Cut Line= 3
      3452599.58      10508482.5       3450037.1     10507456.47
      3449609.98     10507560.64
#Sta/Elev= 30
  3126.7  490.66  3738.8  486.97  3996.5  486.74  4271.8  484.25  4685.9  481.84
  4834.3  479.66  4879.8   480.4  4947.4  477.44    4977  478.46  4987.5  476.96
  4992.8  472.87  4995.6  472.37  5001.2   473.1    5009  476.98  5019.8  478.33
    5055  477.95  5157.3  479.04  5318.8  479.45    5378  478.84  5504.5  480.08
  5671.4  482.94  5754.8  486.72  5779.1  488.28  5803.3  490.87  5832.9  491.18
  5902.4  493.89  5970.7  493.42  6159.7  494.18  6231.8  496.03  6326.6   496.8
#Mann= 3 , 0 , 0
  3126.7     .05       0    4977    .035       0  5019.8     .05       0
#XS Ineff= 2 , 0
         4879.72   480.4
Permanent Ineff=
       F       F
Bank Sta=4977,5019.8
XS Rating Curve= 0 ,0
Exp/Cntr=0.3,0.1

Type RM Length L Ch R = 1 ,237953  ,813,813,813
BEGIN DESCRIPTION:
STEELE CREEK 142.0
END DESCRIPTION:
XS GIS Cut Line= 4
      3452964.16     10508268.95      3451891.27     10507612.72
      3450339.18     10507143.97      3449880.83     10507295.02
#Sta/Elev= 30
  2873.7  489.51  3054.2  487.58  3201.2  488.81  4060.1  484.41  4499.8  480.44
    4911  479.26    4944  478.85  4966.2  477.16  4982.2  474.95  4987.4  475.19
  4997.3  472.98  5015.1  475.47  5020.4  474.95  5048.1  476.99  5081.1  476.92
  5086.3   476.7  5091.5  475.06    5102  474.85  5119.3  476.53  5157.4  475.81
  5175.1  477.69  5404.9  477.24  5606.9   478.6    5687   480.1  5743.9  483.17
  5826.9  484.54  5907.6  487.96  6012.2  489.68    6055  491.45  6235.3  491.63
#Mann= 3 , 0 , 0
  2873.7     .05       0  4966.2    .035       0  5048.1     .05       0
Bank Sta=4966.2,5048.1
XS Rating Curve= 0 ,0
Exp/Cntr=0.3,0.1

Type RM Length L Ch R = 1 ,237140  ,861,861,861
BEGIN DESCRIPTION:
STEELE CREEK 140.0
END DESCRIPTION:
XS GIS Cut Line= 4
      3453172.51     10507680.42       3451849.6     10506867.93
      3450485.02     10506305.43      3449667.35     10506571.04
#Sta/Elev= 30
  2840.2   488.5  3042.3  485.84  3631.8  483.43  3769.1  481.02  4163.4  480.95
  4279.4  479.85    4380  477.62  4541.4  476.32  4909.2  474.59  4976.4  475.31
  4984.9   474.4  5000.1  469.87  5003.3  470.37  5006.5  472.69  5017.3  475.31
  5147.1  476.55  5222.8   473.9    5232  474.93  5276.9  473.69  5338.6  475.47
  5367.9  472.62  5391.8  475.38  5428.4  474.67  5634.3  474.99  5788.7  476.06
  5906.8  478.41  6008.4   482.8  6208.2  487.57  6576.2  490.68  6728.4  490.97
#Mann= 4 ,-1 , 0
  2840.2     .05       0  4976.4    .035       0  5017.3     .05       0
  5906.8     .05       0
Bank Sta=4976.4,5017.3
XS Rating Curve= 0 ,0
Exp/Cntr=0.3,0.1

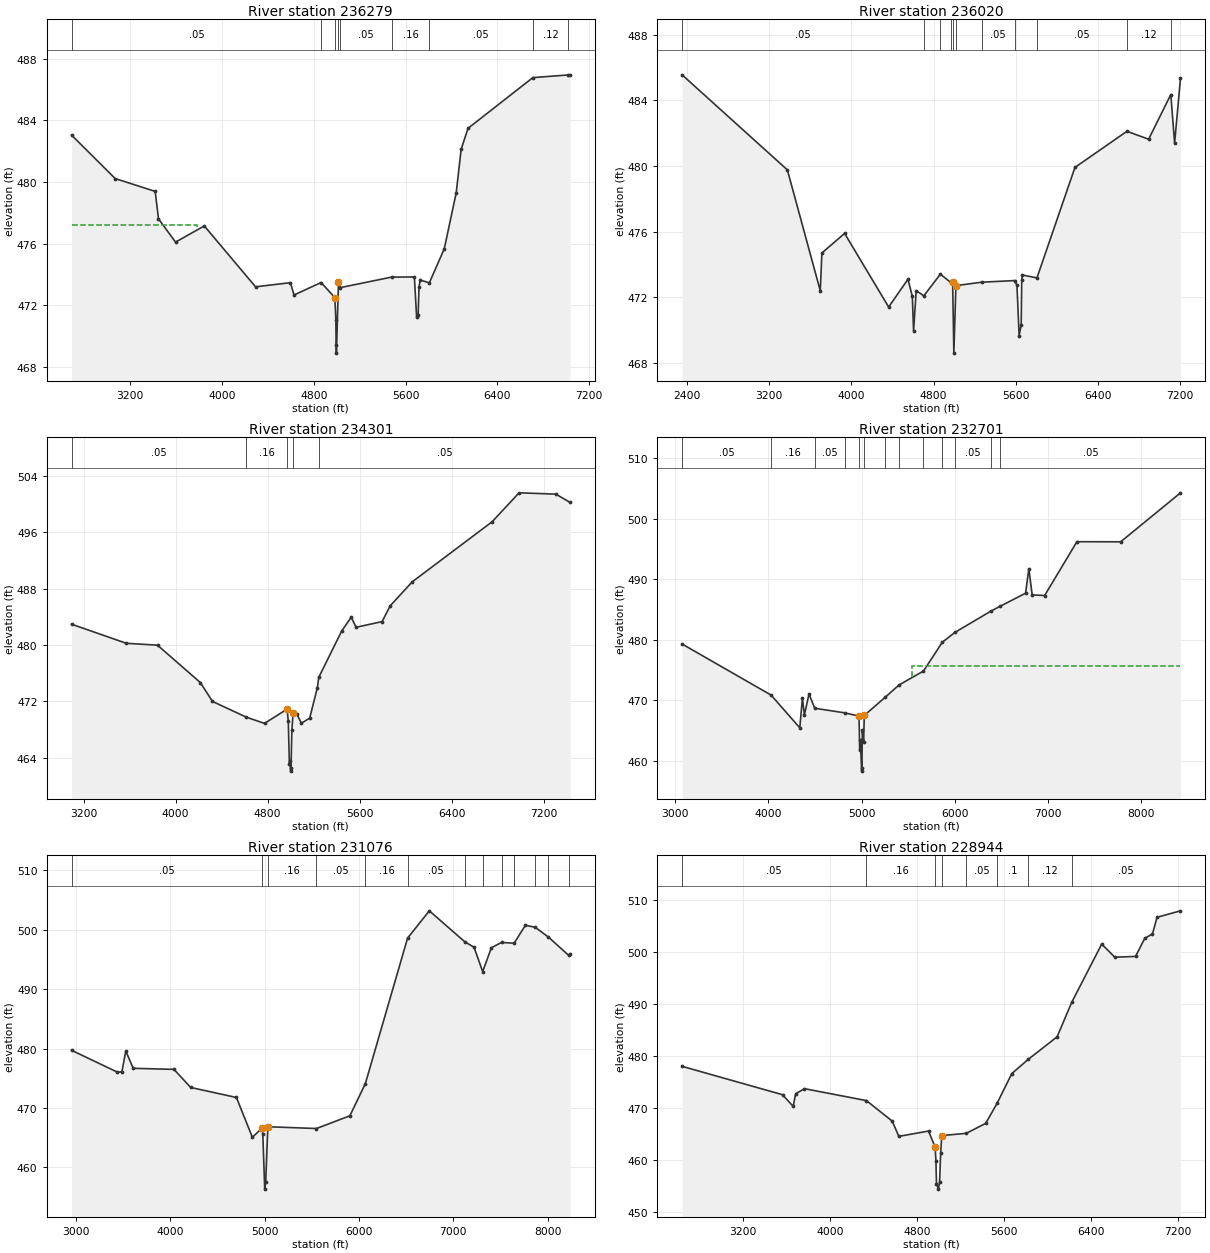
Type RM Length L Ch R = 1 ,236279  ,259,259,259
BEGIN DESCRIPTION:
STEELE CREEK 139.0
END DESCRIPTION:
XS GIS Cut Line= 4
      3453438.11     10507071.02      3452714.18     10506190.84
      3450490.22     10505503.34       3449672.5     10505810.64
#Sta/Elev= 30
  2690.9  483.05  3071.2  480.23  3419.1   479.4  3447.8  477.62  3596.4  476.11
  3846.6  477.16  4293.3  473.21  4596.8  473.48  4628.5  472.68    4864  473.49
  4984.1  472.51  4992.6  471.09  4994.9  469.41  4997.6  468.91  5015.5   473.5
  5032.7  473.16  5477.4  473.84  5676.6  473.85  5695.8  471.27  5709.3  471.38
  5716.8   473.2  5727.2  473.65  5806.8  473.47  5936.6  475.67  6040.8   479.3
  6083.9  482.13  6143.9  483.49  6708.5  486.78  7014.5  486.95  7031.9  486.96
#Mann= 9 ,-1 , 0
  2690.9     .05       0    4864     .16       0  4984.1     .07       0
  5015.5     .16       0  5032.7     .05       0  5477.4     .16       0
  5806.8     .05       0  6708.5     .12       0  7014.5     .16       0
#XS Ineff= 2 , 0
         3780.95  477.25
Permanent Ineff=
       F       F
Bank Sta=4984.1,5015.5
XS Rating Curve= 0 ,0
Exp/Cntr=0.3,0.1

Type RM Length L Ch R = 1 ,236020  ,1719,1719,1719
BEGIN DESCRIPTION:
STEELE CREEK 138.0
END DESCRIPTION:
XS GIS Cut Line= 4
      3453776.68     10507097.09      3452932.93     10506045.01
      3450755.85     10505279.38      3449575.33      10505445.8
#Sta/Elev= 30
  2353.7  485.55  3377.9  479.76  3697.9   472.4  3713.8   474.7  3934.8  475.89
  4363.1  471.41  4551.2   473.1  4593.6  472.06  4605.6  469.96  4631.3  472.41
  4705.1  472.09  4866.4  473.41  4969.8  472.89  4985.8  472.93  4997.4   468.6
  5017.6  472.71    5268  472.92  5589.9  473.02  5611.3  472.73  5632.5  469.67
  5652.5  470.32  5657.8  473.06  5664.3  473.36  5805.8  473.18  6175.5  479.91
  6680.8  482.11  6892.5  481.63  7108.1  484.35    7145  481.39  7202.3  485.35
#Mann= 11 ,-1 , 0
  2353.7     .05       0  4705.1     .16       0  4866.4     .05       0
  4969.8     .16       0  4985.8     .07       0  5017.6     .16       0
    5268     .05       0  5589.9     .16       0  5805.8     .05       0
  6680.8     .12       0  7108.1     .16       0
#XS Ineff= 2 , 0
         3934.59  475.88
Permanent Ineff=
       F       F
Bank Sta=4985.8,5017.6
XS Rating Curve= 0 ,0
Exp/Cntr=0.3,0.1

Type RM Length L Ch R = 1 ,234301  ,1600,1600,1600
BEGIN DESCRIPTION:
STEELE CREEK 137.0
END DESCRIPTION:
XS GIS Cut Line= 4
      3453735.04     10506633.58      3453141.27     10505821.05
      3452761.06     10504357.51      3451390.85     10503168.29
#Sta/Elev= 30
    3096  482.96  3571.2  480.25    3843  479.98  4215.4  474.67  4320.8  471.99
  4615.6  469.75  4773.3  468.87  4969.6   470.9    4980  469.17  4989.5  463.04
  4994.7  463.47  5000.4  462.09  5003.6  462.59    5011  467.94  5021.3  470.28
  5052.3  470.26  5093.6   468.9  5165.9  469.62  5232.8  473.95  5244.5   475.4
  5444.9  482.02  5527.6  483.96  5568.9  482.52  5795.4  483.33  5865.6  485.57
  6057.5  488.98  6751.8  497.51  6986.2  501.62  7305.3  501.44  7428.8  500.27
#Mann= 5 ,-1 , 0
    3096     .05       0  4615.6     .16       0  4969.6     .07       0
  5021.3     .16       0  5244.5     .05       0
Bank Sta=4969.6,5021.3
XS Rating Curve= 0 ,0
Exp/Cntr=0.3,0.1

Type RM Length L Ch R = 1 ,232701  ,1625,1625,1625
BEGIN DESCRIPTION:
STEELE CREEK 134.0
END DESCRIPTION:
XS GIS Cut Line= 4
      3454059.67     10505812.35      3453976.34     10504777.65
      3451445.09     10502118.36      3450827.04     10501930.86
#Sta/Elev= 30
    3072  479.29  4028.7  470.84  4336.7  465.43    4365  470.36    4386  467.56
  4435.8  471.02  4497.2  468.67  4818.5  467.91  4973.3  467.37  4980.2  461.72
  4987.5  463.39  5001.4  458.27  5004.6  458.77  5008.5  465.01  5022.7  463.12
  5029.6  467.48  5252.9  470.46  5402.2  472.51  5665.7  474.82  5868.1  479.58
  6003.6  481.21  6387.8  484.71  6491.5  485.55  6762.7  487.69  6797.9  491.75
  6833.5  487.41  6967.8  487.31  7314.4  496.21  7784.4  496.19  8427.3  504.29
#Mann= 13 ,-1 , 0
    3072     .05       0  4028.7     .16       0  4497.2     .05       0
  4818.5     .16       0  4973.3     .07       0  5029.6     .16       0
  5252.9     .05       0  5402.2     .16       0  5665.7     .12       0
  5868.1     .16       0  6003.6     .05       0  6387.8     .16       0
  6491.5     .05       0
#XS Ineff= 2 , 0
                         5546.27          475.59
Permanent Ineff=
       F       F
Bank Sta=4973.3,5029.6
XS Rating Curve= 0 ,0
Exp/Cntr=0.3,0.1

Type RM Length L Ch R = 1 ,231076  ,2132,2132,2132
BEGIN DESCRIPTION:
STEELE CREEK 133.0
END DESCRIPTION:
XS GIS Cut Line= 4
      3454483.28     10505880.95      3454309.67      10504394.4
      3453984.15     10503114.02      3452270.34     10501345.98
#Sta/Elev= 30
  2955.1   479.7    3441  476.02    3488  476.07  3529.4  479.59  3607.8  476.67
  4039.8  476.49  4216.6  473.45  4701.4  471.76  4870.2  465.07  4970.5  466.56
  4980.8  465.68  5001.2  456.34  5011.8  457.62    5034  466.84  5549.5  466.54
  5903.2  468.68  6067.1  474.09  6514.6  498.58  6744.9  503.17  7120.7  497.96
  7218.7  497.04  7310.2  492.95  7402.6  496.96  7509.6  497.85  7643.3  497.72
  7763.2  500.74  7866.2   500.4  8007.1  498.75  8220.3  495.69  8235.2  495.93
#Mann= 13 ,-1 , 0
  2955.1     .05       0  4970.5     .07       0    5034     .16       0
  5549.5     .05       0  6067.1     .16       0  6514.6     .05       0
  7120.7      .1       0  7310.2     .16       0  7509.6     .12       0
  7643.3     .16       0  7866.2     .05       0  8007.1      .1       0
  8220.3     .05       0
Bank Sta=4970.5,5034
XS Rating Curve= 0 ,0
Exp/Cntr=0.3,0.1

Type RM Length L Ch R = 1 ,228944  ,87,87,87
BEGIN DESCRIPTION:
Mapping XS 55b0ddf4
END DESCRIPTION:
XS GIS Cut Line= 4
      3454912.82     10505627.03      3455199.28     10503613.12
      3455095.12     10503014.17      3453776.37     10501582.63
#Sta/Elev= 30
  2638.7  478.01  3563.3  472.56  3661.3  470.32  3684.5  472.75  3765.3  473.72
  4335.7  471.43  4573.4  467.49    4634  464.56  4907.8  465.58  4968.7  462.45
  4975.6   459.8  4980.7   455.5  4998.9  454.42  5009.3   455.8  5019.5  461.43
  5029.6  464.71  5255.1  465.14  5433.6  467.05  5538.3  470.89  5674.1  476.62
  5827.1  479.38  6091.4  483.69  6225.8  490.31    6502   501.5  6622.2  498.98
  6813.4  499.13  6898.4  502.61  6969.3  503.45  7011.3  506.65  7227.2  507.89
#Mann= 8 ,-1 , 0
  2638.7     .05       0  4335.7     .16       0  4968.7     .07       0
  5029.6     .16       0  5255.1     .05       0  5538.3      .1       0
  5827.1     .12       0  6225.8     .05       0
Bank Sta=4968.7,5029.6
XS Rating Curve= 0 ,0
Exp/Cntr=0.3,0.1

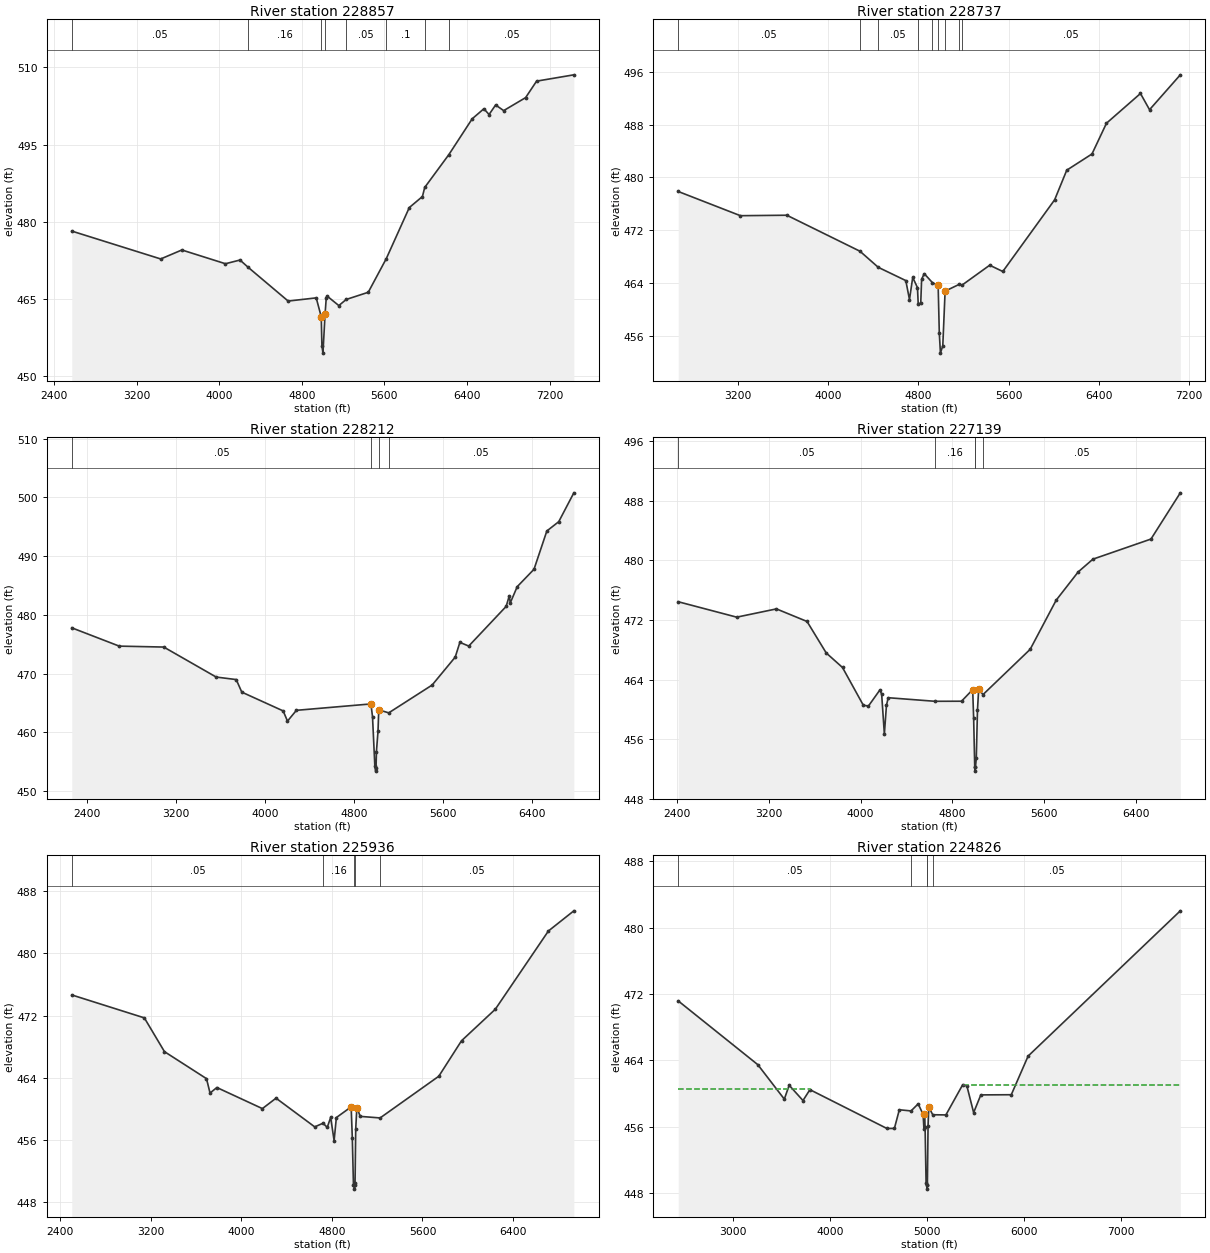
Type RM Length L Ch R = 1 ,228857  ,120,120,120
BEGIN DESCRIPTION:
STEELE CREEK 131.0
END DESCRIPTION:
XS GIS Cut Line= 4
      3455014.96     10505663.96      3455307.28     10503640.85
      3455145.59     10502911.33      3453778.16     10501356.41
#Sta/Elev= 30
  2572.9  478.14  3434.1  472.71    3639  474.46    4061  471.78    4202   472.5
    4283  471.05  4668.3  464.51  4940.1  465.13  4988.8  461.45  4995.2  455.83
  5005.2  454.37  5025.9  461.98  5037.5  465.19  5046.4  465.47  5159.1  463.63
  5230.4  464.82    5444  466.22  5618.8  472.78  5841.5  482.72  5968.7  484.87
  5990.8  486.64  6225.2  493.05  6450.7  500.01  6563.6  501.96  6613.9  500.84
  6677.4   502.7  6755.3   501.6  6967.8  504.13  7074.1  507.34  7434.9  508.57
#Mann= 8 ,-1 , 0
  2572.9     .05       0    4283     .16       0  4988.8     .07       0
  5025.9     .16       0  5230.4     .05       0  5618.8      .1       0
  5990.8     .12       0  6225.2     .05       0
Bank Sta=4988.8,5025.9
XS Rating Curve= 0 ,0
Exp/Cntr=0.3,0.1

Type RM Length L Ch R = 1 ,228737  ,525,525,525
BEGIN DESCRIPTION:
Mapping XS b8211c26
END DESCRIPTION:
XS GIS Cut Line= 4
      3455199.28     10505540.24      3455398.94     10503482.92
      3455210.86     10502698.48      3454313.85     10501399.56
#Sta/Elev= 30
    2670  477.86  3221.2  474.19  3633.1  474.26  4281.7   468.8  4443.8  466.36
    4688  464.35  4720.6  461.47  4749.3  464.83  4791.3  463.29  4798.2  460.75
  4820.6  460.99  4828.2  464.55  4851.4   465.4  4923.4  464.05  4974.8  463.62
  4985.1  456.37  4995.1  453.35    5016  454.48  5036.5  462.75  5161.7  463.78
  5185.5  463.65  5431.8  466.68  5548.1  465.73  6007.8   476.6  6115.2  481.09
    6339  483.55  6467.4  488.21  6768.9  492.72  6849.4  490.26  7122.2  495.55
#Mann= 9 ,-1 , 0
    2670     .05       0  4281.7     .16       0  4443.8     .05       0
  4798.2     .16       0  4923.4     .05       0  4974.8     .04       0
  5036.5     .05       0  5161.7     .16       0  5185.5     .05       0
#XS Ineff= 2 , 0
                         5431.75          466.67
Permanent Ineff=
       F       F
Bank Sta=4974.8,5036.5
XS Rating Curve= 0 ,0
Exp/Cntr=0.3,0.1

Type RM Length L Ch R = 1 ,228212  ,1073,1073,1073
BEGIN DESCRIPTION:
Mapping XS 0e692635
END DESCRIPTION:
XS GIS Cut Line= 4
      3455312.13     10505427.35      3455510.34     10502839.11
      3455354.09     10502652.48      3454378.03       10501286.
#Sta/Elev= 30
  2262.3  477.79  2689.3  474.67  3090.4  474.51  3561.8   469.4  3742.3  468.97
  3792.5  466.83  4164.8  463.63  4203.7  461.89  4283.9  463.73  4954.6  464.82
  4968.9  462.64  4989.8  454.28  4997.3  453.37  5000.6  453.87  5004.1  456.69
  5018.4  460.17  5024.9  463.81  5114.9   463.3  5505.6  468.04  5713.3   472.8
  5755.1  475.31  5834.9  474.68  6171.7  481.44  6199.9  483.25  6208.5  482.03
  6271.2   484.8  6422.4  487.77  6537.9  494.29  6644.8  495.87  6780.8  500.79
#Mann= 4 ,-1 , 0
  2262.3     .05       0  4954.6     .07       0  5024.9     .05       0
  5114.9     .05       0
Bank Sta=4954.6,5024.9
XS Rating Curve= 0 ,0
Exp/Cntr=0.3,0.1

Type RM Length L Ch R = 1 ,227139  ,1203,1203,1203
BEGIN DESCRIPTION:
STEELE CREEK 129.0
END DESCRIPTION:
XS GIS Cut Line= 4
      3456110.89     10504784.98      3456338.75     10503265.93
      3455909.64     10501801.78       3454895.6     10500978.41
#Sta/Elev= 30
  2414.3  474.45  2923.1  472.38  3268.6  473.49  3534.9   471.8  3701.9  467.57
  3843.4  465.62  4024.9  460.54  4069.4  460.45    4169  462.61  4184.1  462.03
  4207.6  456.68  4225.7  460.52    4241  461.56  4647.9  461.08  4878.8  461.09
    4976  462.65  4984.3  458.83  4993.9   452.2  4996.6   451.7  4999.9   452.2
  5007.3   453.4  5017.7  459.93  5028.1  462.72  5065.7  461.98  5476.1  468.06
  5702.3  474.66  5894.1  478.46    6022  480.17    6527  482.87  6782.3  489.08
#Mann= 5 ,-1 , 0
  2414.3     .05       0  4647.9     .16       0  4993.9     .07       0
  4999.9     .16       0  5065.7     .05       0
Bank Sta=4976,5028.1
XS Rating Curve= 0 ,0
Exp/Cntr=0.3,0.1

Type RM Length L Ch R = 1 ,225936  ,1110,1110,1110
BEGIN DESCRIPTION:
STEELE CREEK 127.0
END DESCRIPTION:
XS GIS Cut Line= 4
      3456642.58     10504578.84      3457033.19     10503428.69
      3456794.48      10501182.6      3456262.82     10500379.68
#Sta/Elev= 30
  2501.2  474.66  3142.5  471.71  3320.3  467.37  3691.6   463.9    3723  462.05
  3783.3  462.76  4185.6  460.05  4306.2  461.39  4648.1   457.7  4720.9  458.17
  4758.8  457.64  4788.9  458.92  4819.2  455.93  4839.2   458.9  4969.9  460.27
    4980  456.32  4990.1  450.29  4996.3   450.2  4999.1   449.7  5002.3   450.2
  5004.3  450.47  5010.2  457.44  5020.2  460.18  5050.4  459.05  5225.7  458.85
  5744.3  464.21  5945.1  468.77  6243.6  472.82  6712.9  482.88  6937.6  485.47
#Mann= 5 ,-1 , 0
  2501.2     .05       0  4720.9     .16       0  4996.3     .07       0
  5002.3     .16       0  5225.7     .05       0
Bank Sta=4969.9,5020.2
XS Rating Curve= 0 ,0
Exp/Cntr=0.3,0.1

Type RM Length L Ch R = 1 ,224826  ,3514,3514,3514
BEGIN DESCRIPTION:
STEELE CREEK 124.0
END DESCRIPTION:
XS GIS Cut Line= 4
      3457119.99     10504568.02       3457933.8     10503038.07
      3457488.92     10500933.03        3456546.      10500044.3
#Sta/Elev= 30
  2436.7  471.17  3257.4   463.5  3531.3  459.35  3581.3  461.02  3723.8  459.18
  3795.4  460.49  4589.5  455.82  4666.8  455.82  4717.9  458.07  4838.7  457.93
  4912.1  458.78  4963.2  457.52  4972.1   455.7  4977.2  457.56  4983.6  456.03
  4993.9  449.26  5001.1  449.02  5003.8  448.52  5007.1  449.02  5014.3  456.14
  5021.8   458.4  5062.5  457.47  5198.3  457.45    5372  461.09  5414.6  460.95
  5484.5  457.73  5558.6  459.86  5872.9  459.88  6046.6  464.53  7616.9  482.01
#Mann= 5 ,-1 , 0
  2436.7     .05       0  4838.7     .16       0  5001.1     .07       0
  5007.1     .16       0  5062.5     .05       0
#XS Ineff= 2 , 0
         3795.45  460.51 5371.36           461.1
Permanent Ineff=
       F       F
Bank Sta=4977.2,5021.8
XS Rating Curve= 0 ,0
Exp/Cntr=0.3,0.1