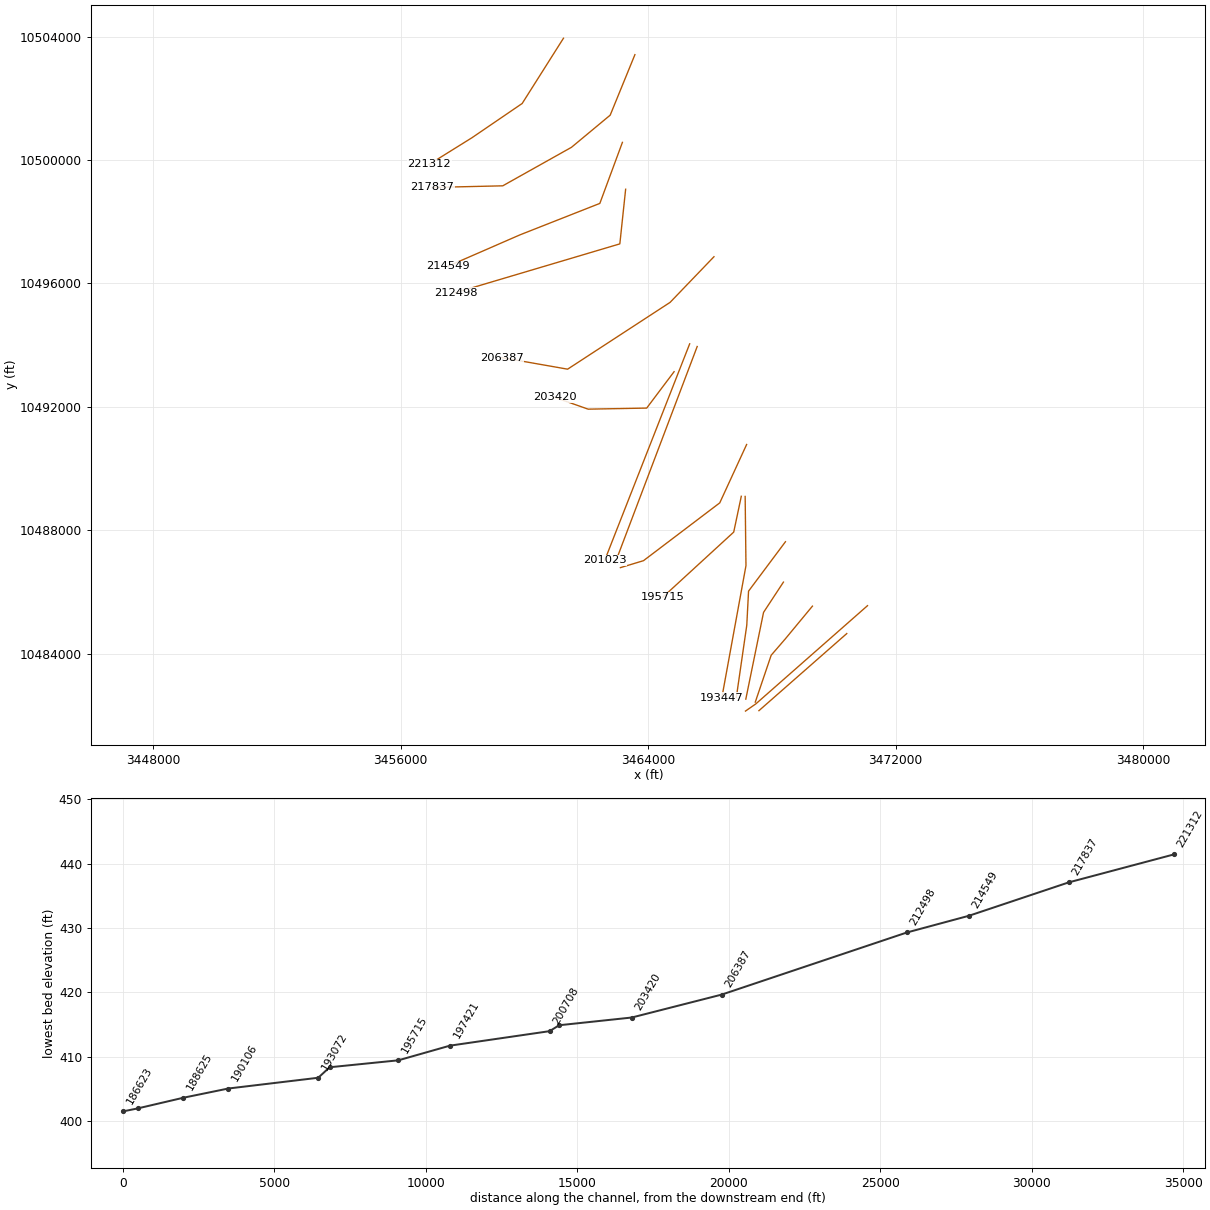
HEC-RAS study STEELE CREEK.prj: STEELE CREEK Base Level Engineering

--- STEELE CREEK.g01 (geometry) --- (continued)

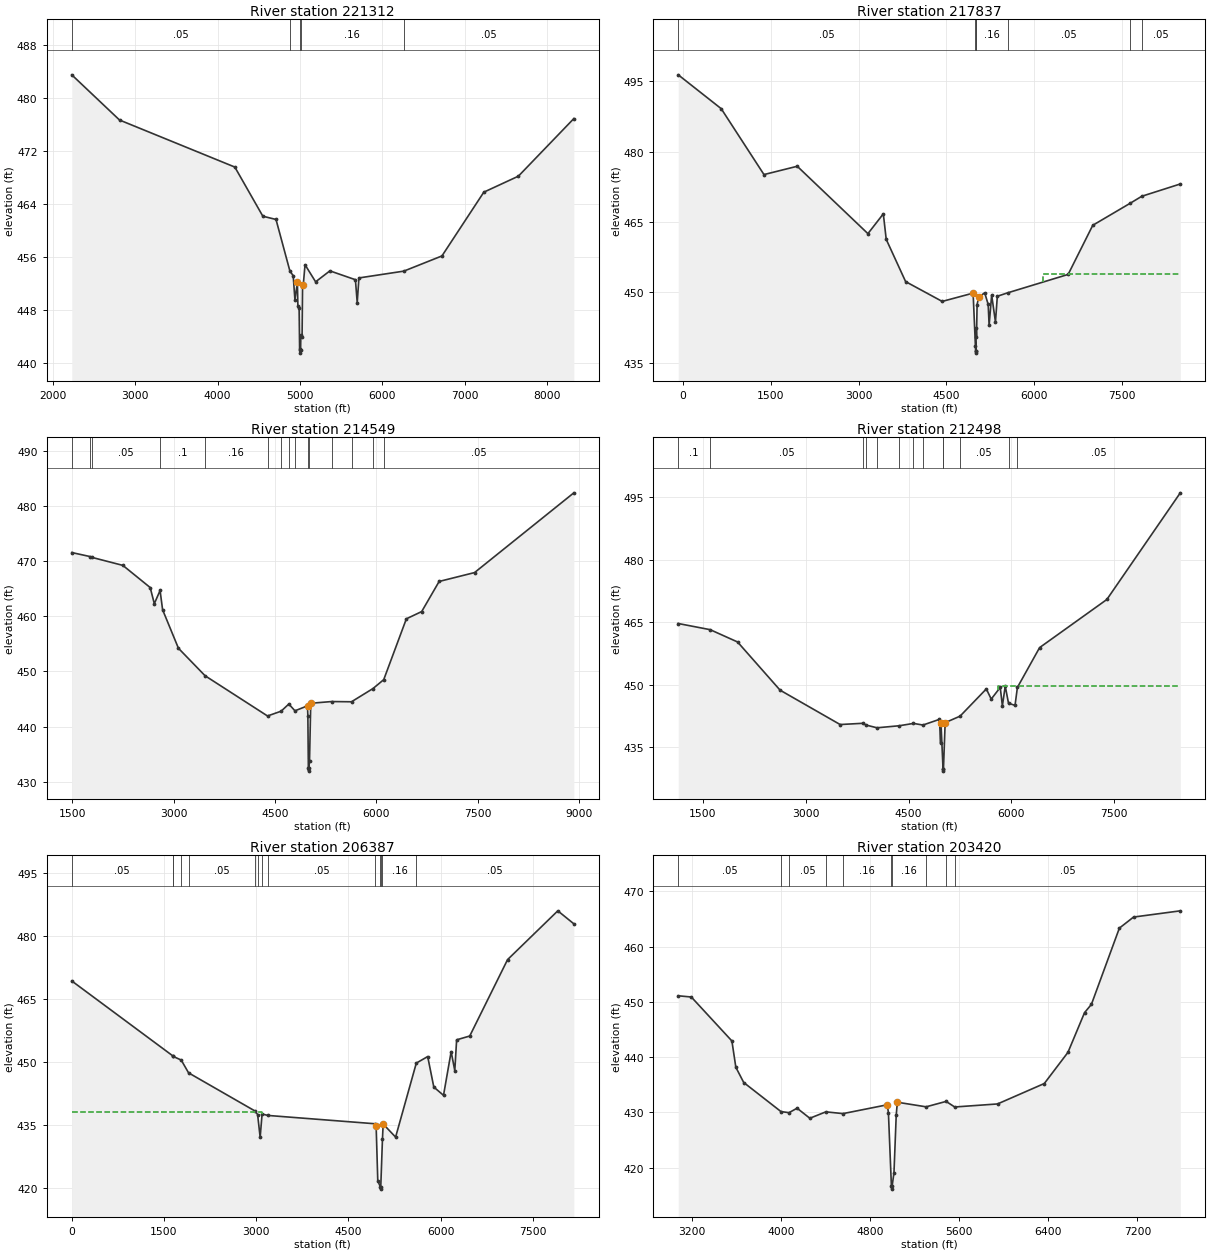
Type RM Length L Ch R = 1 ,221312  ,3475,3475,3475
BEGIN DESCRIPTION:
STEELE CREEK 123.0
END DESCRIPTION:
XS GIS Cut Line= 4
      3461264.95      10503949.5      3459930.33     10501833.64
      3458313.58     10500726.87      3456925.92     10499859.58
#Sta/Elev= 30
  2229.3  483.55  2809.2  476.71  4209.6  469.59  4549.8  462.15  4709.6  461.66
  4878.4  453.85  4918.5  453.15  4939.4  449.49  4969.3  452.15  4975.3   448.5
  4990.2  448.23  4996.3   442.1  5002.1  441.93  5004.9  441.43  5008.1  441.93
  5011.2  444.18  5026.1  443.81  5032.2  451.84    5041   451.8    5062  454.81
  5190.6  452.22  5363.9  453.88    5674  452.54  5695.7  449.08  5716.7  452.81
  6261.7  453.84  6724.9  456.14  7233.2  465.79    7653  468.21  8326.6  476.93
#Mann= 5 ,-1 , 0
  2229.3     .05       0  4878.4     .16       0  5002.1     .07       0
  5008.1     .16       0  6261.7     .05       0
Bank Sta=4969.3,5041
XS Rating Curve= 0 ,0
Exp/Cntr=0.3,0.1

Type RM Length L Ch R = 1 ,217837  ,3288,3288,3288
BEGIN DESCRIPTION:
STEELE CREEK 121.0
END DESCRIPTION:
XS GIS Cut Line= 5
      3463573.36     10503417.13      3462774.76     10501455.34
      3461524.76     10500413.67      3459302.54     10499163.67
      3457028.24     10499111.59
#Sta/Elev= 30
   -78.6  496.34   655.1  489.13  1384.9   475.1  1952.7  476.87    3159  462.52
    3422  466.74  3471.4  461.31  3802.5  452.31  4426.9  448.09  4954.7  449.86
  4993.6  438.69  4997.6  437.58  5000.4  437.08  5003.6  437.58  5006.6   442.4
  5012.3  440.43  5022.5  447.42  5049.9  449.01  5152.5  449.92  5211.8  447.44
  5227.8     443  5271.1  449.46  5336.1   443.7  5367.8  449.19    5547  449.93
  6576.8  453.84  6996.9   464.3    7638  469.01  7833.4  470.48  8491.2   473.1
#Mann= 7 ,-1 , 0
   -78.6     .05       0  4993.6     .16       0  4997.6     .07       0
  5003.6     .16       0    5547     .05       0    7638      .1       0
  7833.4     .05       0
#XS Ineff= 2 , 0
                         6145.59          453.83
Permanent Ineff=
       F       F
Bank Sta=4954.7,5049.9
XS Rating Curve= 0 ,0
Exp/Cntr=0.3,0.1

Type RM Length L Ch R = 1 ,214549  ,2051,2051,2051
BEGIN DESCRIPTION:
STEELE CREEK 119.0
END DESCRIPTION:
XS GIS Cut Line= 4
      3463169.49     10500573.24      3462440.31     10498594.05
      3459856.98     10497573.22      3457525.41     10496553.16
#Sta/Elev= 30
  1493.1  471.61  1760.7  470.89  1792.3  470.73  2249.1  469.28  2654.1  465.25
    2715  462.32  2800.3  464.72  2837.6  461.22  3072.1  454.22  3466.2  449.23
  4390.7  441.92    4592  442.79    4706  444.09  4796.6  442.86  4982.6  443.76
  4987.9  441.93  4995.2   432.4    4998   431.9  5001.2   432.4  5012.3  433.75
  5030.5  444.23  5339.4  444.54  5633.8   444.5  5951.5   446.9  6110.9  448.52
  6445.9  459.57  6672.8  460.89  6931.1  466.36  7455.1  467.97    8925  482.46
#Mann= 15 ,-1 , 0
  1493.1     .05       0  1760.7      .1       0  1792.3     .05       0
  2800.3      .1       0  3466.2     .16       0  4390.7     .12       0
    4592     .16       0    4706     .12       0  4796.6     .16       0
  4995.2     .07       0  5001.2     .16       0  5339.4      .1       0
  5633.8     .05       0  5951.5     .16       0  6110.9     .05       0
Bank Sta=4982.6,5030.5
XS Rating Curve= 0 ,0
Exp/Cntr=0.3,0.1

Type RM Length L Ch R = 1 ,212498  ,6111,6111,6111
BEGIN DESCRIPTION:
STEELE CREEK 118.0
END DESCRIPTION:
XS GIS Cut Line= 3
      3463273.65     10499052.41      3463086.14     10497281.55
      3457775.35     10495698.73
#Sta/Elev= 30
  1139.9  464.69    1606  463.21  2005.5  460.26  2625.3  448.71    3501  440.47
  3834.7  440.77  3880.3  440.34  4039.2  439.69  4364.1  440.18  4570.8  440.74
  4708.7  440.35  4949.2  441.71  4966.7  435.96  4971.9  440.81    5002   429.8
  5004.8   429.3    5008   429.8  5032.7  440.92  5250.3  442.48  5633.2  449.01
  5704.7  446.57  5836.1  449.37  5867.4  444.96  5908.9  449.68    5957  445.56
  6051.9  445.07  6086.2  449.36  6410.1  458.91  7390.9  470.45  8462.3  496.02
#Mann= 13 ,-1 , 0
  1139.9      .1       0    1606     .05       0  3834.7      .1       0
  3880.3     .12       0  4039.2     .16       0  4364.1      .1       0
  4570.8     .05       0  4708.7     .16       0    5002     .07       0
    5008     .16       0  5250.3     .05       0    5957     .16       0
  6086.2     .05       0
#XS Ineff= 2 , 0
                         5803.51          449.74
Permanent Ineff=
       F       F
Bank Sta=4971.9,5032.7
XS Rating Curve= 0 ,0
Exp/Cntr=0.3,0.1

Type RM Length L Ch R = 1 ,206387  ,2967,2967,2967
BEGIN DESCRIPTION:
STEELE CREEK 117.0
END DESCRIPTION:
XS GIS Cut Line= 4
      3466127.84     10496864.92      3464711.14     10495385.72
      3461398.64     10493219.05      3459275.41     10493593.74
#Sta/Elev= 30
       3  469.32  1641.2  451.49    1651  451.32  1782.5  450.44    1902  447.39
  2981.9  438.29  3024.2  437.45  3065.7     432    3097  437.58  3192.1  437.23
  4939.1  435.24    4951  434.81    4978  421.65  5020.3  420.15  5023.1  419.65
  5026.3  420.15  5054.2  431.67  5065.5  435.19  5267.6  432.06  5604.3  449.72
  5789.4  451.28  5888.8     444  6046.5  442.03  6170.7  452.45    6230  447.92
  6259.7  455.27  6472.9  456.18    7088  474.41  7904.7  486.05  8165.4  482.95
#Mann= 14 ,-1 , 0
       3     .05       0  1641.2      .1       0    1651     .05       0
  1782.5      .1       0    1902     .05       0  2981.9      .1       0
  3024.2     .05       0    3097      .1       0  3192.1     .05       0
  4939.1     .12       0  5020.3     .07       0  5026.3     .12       0
  5054.2     .16       0  5604.3     .05       0
#XS Ineff= 2 , 0
         3102.87  438.03
Permanent Ineff=
       F       F
Bank Sta=4951,5065.5
XS Rating Curve= 0 ,0
Exp/Cntr=0.3,0.1

Type RM Length L Ch R = 1 ,203420  ,2397,2397,2397
BEGIN DESCRIPTION:
STEELE CREEK 116.0
END DESCRIPTION:
XS GIS Cut Line= 4
      3464839.58     10493137.86      3463954.15     10491957.29
      3462061.79     10491922.57      3460986.28      10492304.2
#Sta/Elev= 30
  3076.3  451.09  3193.7  450.87  3558.3  442.91  3593.7  438.15  3664.5  435.39
    3999  430.13  4071.3  429.93  4143.7  430.74  4258.3  428.92  4402.2  430.08
  4556.2  429.76  4954.1  431.36  4964.1  429.94  4991.1  416.59  4993.9  416.09
  4997.1  416.59  5014.1  419.07  5034.1  429.42  5044.1  431.82  5302.7  430.99
  5482.3  431.97  5559.5  430.96  5944.3  431.51  6364.4  435.21  6576.7  440.85
  6725.8  448.04  6787.5  449.54  7038.6  463.34  7165.9  465.34  7585.9  466.47
#Mann= 10 ,-1 , 0
  3076.3     .05       0    3999      .1       0  4071.3     .05       0
  4402.2      .1       0  4556.2     .16       0  4991.1     .07       0
  4997.1     .16       0  5302.7     .05       0  5482.3      .1       0
  5559.5     .05       0
Bank Sta=4954.1,5044.1
XS Rating Curve= 0 ,0
Exp/Cntr=0.3,0.1

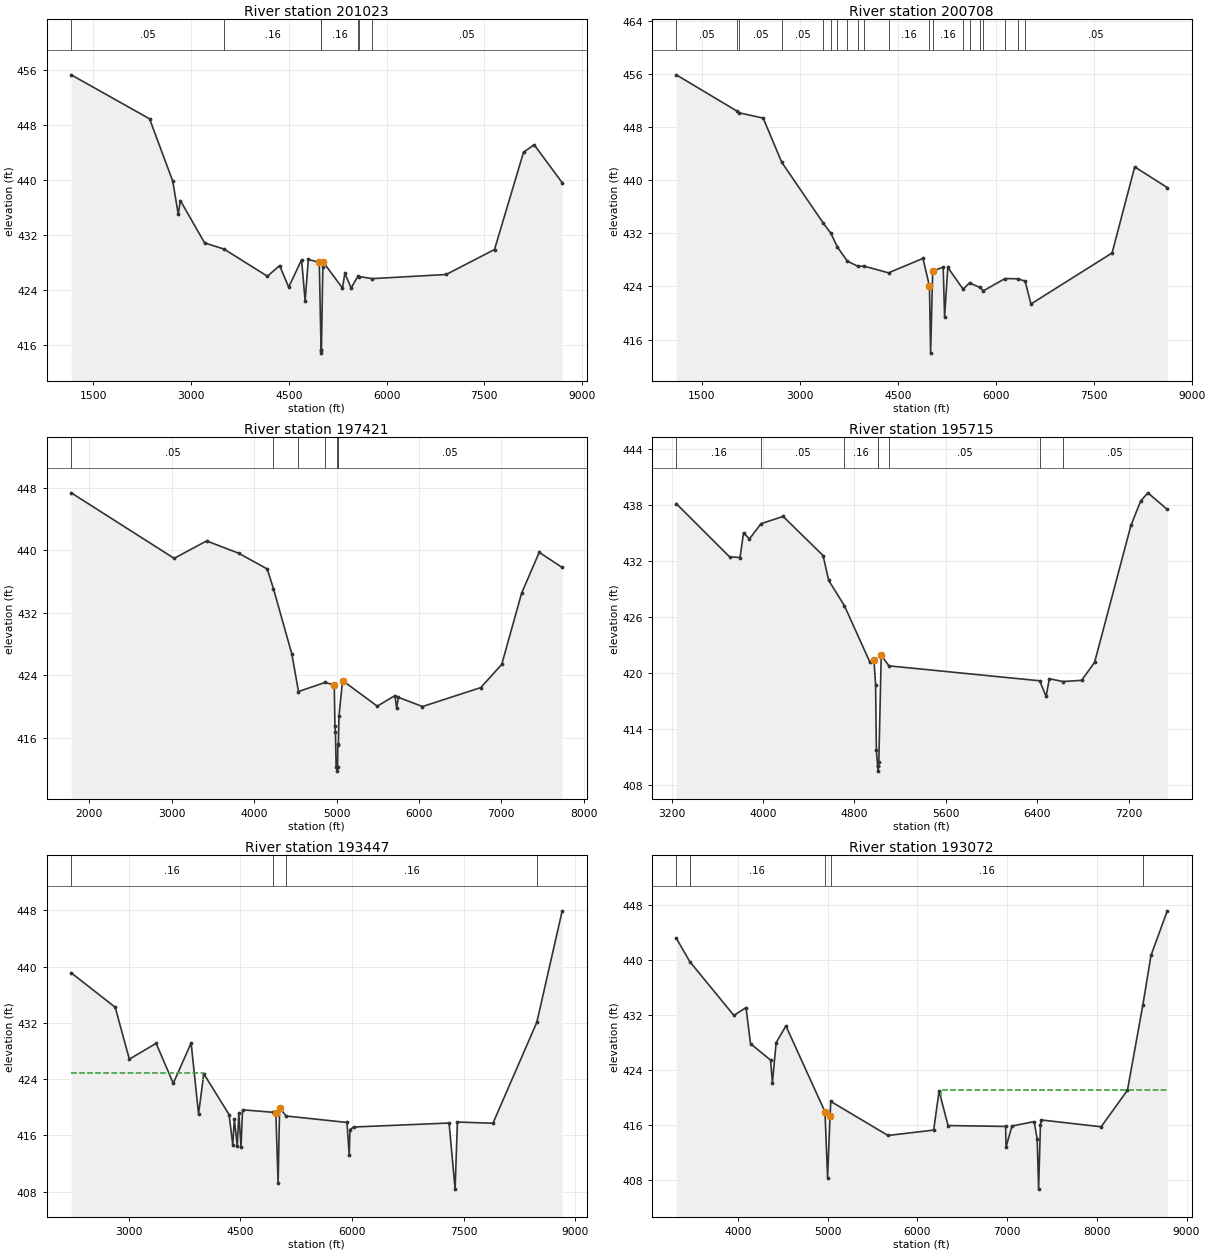
Type RM Length L Ch R = 1 ,201023  ,315,315,315
BEGIN DESCRIPTION:
STEELE CREEK 115.0
END DESCRIPTION:
XS GIS Cut Line= 2
      3465343.04      10494040.6      3462599.98     10487026.71
#Sta/Elev= 30
  1163.4  455.31  2365.3  448.92  2720.9  439.86  2805.1  435.08  2837.3  437.05
  3209.6   430.9  3507.5     430  4173.2  426.06  4360.6  427.61    4499  424.47
  4697.1  428.46  4751.4  422.49  4800.4  428.49  4968.6  428.08  4995.5  415.39
  4998.2  414.89  5001.5  415.39  5022.9  427.47  5028.3  428.12  5324.3  424.34
  5360.7  426.49  5457.3  424.36  5565.7  426.12  5579.9  426.01  5779.8  425.71
  6915.1  426.31  7656.2  429.94  8101.3  444.06  8264.2  445.16  8694.6  439.64
#Mann= 7 ,-1 , 0
  1163.4     .05       0  3507.5     .16       0  4995.5     .07       0
  5001.5     .16       0  5565.7     .05       0  5579.9     .16       0
  5779.8     .05       0
Bank Sta=4968.6,5028.3
XS Rating Curve= 0 ,0
Exp/Cntr=0.3,0.1

Type RM Length L Ch R = 1 ,200708  ,3287,3287,3287
BEGIN DESCRIPTION:
STEELE CREEK 114.0
END DESCRIPTION:
XS GIS Cut Line= 2
      3465586.09      10493953.8      3462929.86     10486922.61
#Sta/Elev= 30
  1109.6  455.84  2039.2  450.38  2073.9  450.12  2439.7  449.33  2722.9   442.7
  3361.9   433.5  3476.6  431.99  3574.9  429.94  3729.6   427.8  3894.3  427.02
  3982.6  427.06  4358.1  426.05  4885.4  428.22  4985.2  424.05  5002.7  413.97
  5034.8  426.31  5195.4  426.91  5216.8   419.4  5265.6  426.87  5500.7  423.58
  5598.3  424.54  5753.7  423.86  5811.3  423.35  6142.1  425.19  6343.7  425.15
  6450.2  424.79  6538.3  421.36  7780.9  429.04    8127  441.99  8625.8  438.88
#Mann= 20 ,-1 , 0
  1109.6     .05       0  2039.2     .08       0  2073.9     .05       0
  2722.9     .05       0  3361.9     .12       0  3476.6     .05       0
  3574.9     .16       0  3729.6     .05       0  3894.3     .16       0
  3982.6     .05       0  4358.1     .16       0  4985.2     .07       0
  5034.8     .16       0  5500.7     .05       0  5598.3     .16       0
  5753.7     .05       0  5811.3     .16       0  6142.1     .05       0
  6343.7     .16       0  6450.2     .05       0
Bank Sta=4985.2,5034.8
XS Rating Curve= 0 ,0
Exp/Cntr=0.3,0.1

Type RM Length L Ch R = 1 ,197421  ,1706,1706,1706
BEGIN DESCRIPTION:
STEELE CREEK 110.0
END DESCRIPTION:
XS GIS Cut Line= 4
      3467183.33     10490776.76      3466315.27     10488884.37
      3463849.99     10487009.37      3463105.26     10486784.22
#Sta/Elev= 30
  1780.5  447.36  3029.3  438.97  3423.1   441.2    3813  439.62  4158.9  437.61
  4234.2  435.09  4458.3  426.68    4538  421.91  4858.4  423.07  4972.1  422.77
  4980.2  417.49  4986.5  416.72  4994.7  412.26  5006.3  412.22    5009  411.72
  5012.3  412.22  5015.5  415.22  5021.8  415.13  5030.1  418.82  5072.6  423.32
  5493.8  420.04  5707.9  421.39  5728.8  419.81    5751  421.17  6042.7  419.99
  6749.7  422.42  7004.2  425.39  7245.3  434.51    7459  439.74  7737.8   437.8
#Mann= 7 ,-1 , 0
  1780.5     .05       0  4234.2     .16       0    4538     .05       0
  4858.4     .16       0  5006.3     .07       0  5012.3     .16       0
  5021.8     .05       0
Bank Sta=4972.1,5072.6
XS Rating Curve= 0 ,0
Exp/Cntr=0.3,0.1

Type RM Length L Ch R = 1 ,195715  ,2268,2268,2268
BEGIN DESCRIPTION:
Mapping XS 4bc9a733
END DESCRIPTION:
XS GIS Cut Line= 3
      3467011.01     10489097.87      3466766.22      10487936.4
      3464475.84     10485828.22
#Sta/Elev= 30
  3239.7  438.13  3705.9  432.43  3797.9  432.35  3828.6  435.01  3879.7  434.34
    3982  435.98  4175.4  436.76  4525.2  432.56  4574.5  429.89  4711.4   427.2
  4935.2  421.13  4970.9  421.36  4985.1  418.69  4991.9   411.7    5003  409.94
  5005.8  409.44    5009  409.94  5013.4  410.43  5034.4  421.85  5102.6  420.73
    6422  419.13  6478.3  417.46  6506.6  419.35  6626.3  419.05  6789.6  419.18
    6903  421.11  7221.2  435.79  7306.3  438.41  7369.8  439.29  7539.6  437.51
#Mann= 8 ,-1 , 0
  3239.7     .16       0    3982     .05       0  4711.4     .16       0
    5003     .07       0    5009     .16       0  5102.6     .05       0
    6422      .1       0  6626.3     .05       0
Bank Sta=4970.9,5034.4
XS Rating Curve= 0 ,0
Exp/Cntr=0.3,0.1

Type RM Length L Ch R = 1 ,193447  ,375,375,375
BEGIN DESCRIPTION:
Mapping XS d642cd1c
END DESCRIPTION:
XS GIS Cut Line= 3
      3467136.01     10489092.62      3467162.05     10486847.86
      3466382.11     10482566.33
#Sta/Elev= 30
  2225.8  439.11  2816.8  434.22  3006.8  426.84  3366.9  429.09  3596.9   423.4
  3836.9  429.14  3936.9  419.04  4006.9  424.77  4346.9  418.96  4396.9  414.63
  4416.9  418.34  4456.9  414.48    4477  419.15  4507.5  414.41  4527.9  419.64
  4942.1  419.28  4975.1  419.22  5005.6   409.2  5025.9  419.93  5112.2  418.76
  5930.6  417.84  5961.1  413.21  5971.2  416.83    6022  417.19  7302.8  417.76
  7383.8  408.36  7414.6   417.9  7892.3  417.73  8481.9  432.09  8822.7  447.93
#Mann= 4 ,-1 , 0
  2225.8     .16       0  4942.1     .12       0  5112.2     .16       0
  8481.9     .05       0
#XS Ineff= 2 , 0
         3996.59  424.91
Permanent Ineff=
       F       F
Bank Sta=4975.1,5025.9
XS Rating Curve= 0 ,0
Exp/Cntr=0.3,0.1

Type RM Length L Ch R = 1 ,193072  ,2966,2966,2966
BEGIN DESCRIPTION:
STEELE CREEK 106.0
END DESCRIPTION:
XS GIS Cut Line= 4
      3468438.37      10487624.3      3467245.68     10486022.76
      3467188.39     10484918.59      3466849.84     10482572.21
#Sta/Elev= 30
  3312.1  443.16  3461.9  439.77    3954  431.95  4089.5  433.08  4139.6  427.85
  4362.8  425.46  4383.6   422.2  4425.3  427.99  4533.8  430.43  4969.6  417.95
  4998.6  408.41  5025.9  417.32  5034.3  419.46  5671.5  414.52  6181.3   415.3
  6241.3  420.98  6341.5  415.96  6983.1  415.83  6988.1  412.84  7053.5  415.89
  7300.6  416.53    7335  414.03  7350.9  406.73  7371.4  416.09  7381.5  416.77
  8048.3  415.78  8341.3  421.09  8513.1  433.48    8604  440.67  8785.3  447.13
#Mann= 5 ,-1 , 0
  3312.1     .05       0  3461.9     .16       0  4969.6     .12       0
  5034.3     .16       0  8513.1     .05       0
#XS Ineff= 2 , 0
                         6259.09          421.09
Permanent Ineff=
       F       F
Bank Sta=4969.6,5025.9
XS Rating Curve= 0 ,0
Exp/Cntr=0.3,0.1

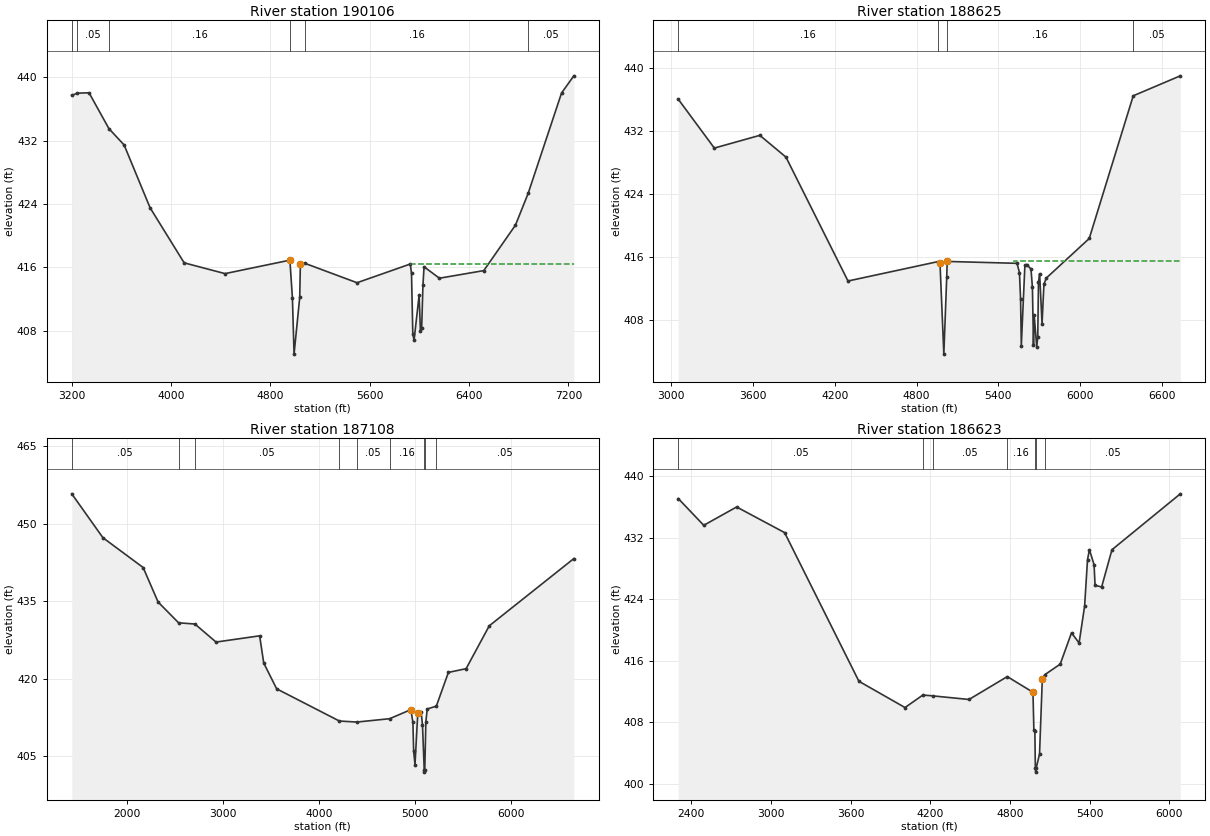
Type RM Length L Ch R = 1 ,190106  ,1481,1481,1481
BEGIN DESCRIPTION:
STEELE CREEK 105.0
END DESCRIPTION:
XS GIS Cut Line= 4
      3468372.42     10486314.43      3467730.05     10485333.52
      3467308.92     10483266.13      3467157.13     10482521.01
#Sta/Elev= 30
  3201.5  437.71  3246.5  437.99  3340.6  438.04  3500.5  433.52  3623.2  431.45
  3832.1  423.53  4106.5  416.58  4435.5  415.22  4957.7  416.92  4978.1  412.19
  4991.4  405.06  5037.1  412.24  5042.2  416.42  5080.1  416.51  5498.5  414.07
  5927.2  416.43  5937.1  415.27  5947.6  407.59  5957.8  406.82  5998.6  412.53
  6008.8     408    6019  408.37  6029.2  413.75  6038.2  416.08  6161.9  414.64
  6519.1   415.6  6774.2  421.34  6876.3  425.34  7145.5  438.02  7244.3  440.18
#Mann= 6 ,-1 , 0
  3201.5     .16       0  3246.5     .05       0  3500.5     .16       0
  4957.7     .12       0  5080.1     .16       0  6876.3     .05       0
#XS Ineff= 2 , 0
       0                 5924.27       0  416.49
Permanent Ineff=
       F       T
Bank Sta=4957.7,5042.2
XS Rating Curve= 0 ,0
Exp/Cntr=0.3,0.1

Type RM Length L Ch R = 1 ,188625  ,1517,1517,1517
BEGIN DESCRIPTION:
STEELE CREEK 101.0
END DESCRIPTION:
XS GIS Cut Line= 4
      3469309.59     10485535.63      3468432.88     10484473.62
      3467976.58     10483943.77      3467463.33     10482424.82
#Sta/Elev= 30
  3053.7  436.06  3318.2  429.84  3651.7  431.46  3843.2  428.69  4297.9  412.93
  4957.7   415.4    4972  415.27  5000.3  403.63  5021.4  413.38    5025  415.42
  5536.6  415.18  5554.5     414  5562.8  410.59  5568.1  404.71  5594.3  414.91
  5607.3  415.03    5639  414.46  5649.5  412.11  5657.2  404.79  5662.4  408.57
  5681.2  404.57  5688.6  405.84  5693.9  412.77  5702.3  413.86  5720.1  407.52
    5734  412.54  5751.5  413.31    6066  418.34  6388.4  436.49  6733.4  439.03
#Mann= 4 ,-1 , 0
  3053.7     .16       0  4957.7     .12       0  5021.4     .16       0
  6388.4     .05       0
#XS Ineff= 2 , 0
       0                 5515.91       0  415.52
Permanent Ineff=
       F       T
Bank Sta=4972,5025
XS Rating Curve= 0 ,0
Exp/Cntr=0.3,0.1

Type RM Length L Ch R = 1 ,187108  ,485,485,485
BEGIN DESCRIPTION:
STEELE CREEK 100.0
END DESCRIPTION:
XS GIS Cut Line= 3
      3471089.55     10485551.02      3467479.59     10482365.79
      3467146.66     10482133.43
#Sta/Elev= 30
  1430.1  455.82  1753.8  447.33  2172.1  441.56  2327.7  434.88  2540.8  430.86
  2710.7  430.62    2930  427.13  3383.5  428.34  3426.1  423.07  3560.5  418.08
  4212.5  411.85  4393.5  411.65  4735.7   412.3  4956.2  414.06  4977.1  411.57
  4984.7  406.03  4998.9  403.42  5027.4  413.31  5062.5  413.64  5076.7   411.1
  5094.6  402.46  5097.4  401.96  5100.6  402.46  5111.8  411.74  5126.1  414.18
  5220.5  414.73  5346.1  421.26  5530.1  421.98  5771.1  430.28  6650.4  443.29
#Mann= 9 ,-1 , 0
  1430.1     .05       0  2540.8     .16       0  2710.7     .05       0
  4212.5     .16       0  4393.5     .05       0  4735.7     .16       0
  5094.6     .07       0  5100.6     .16       0  5220.5     .05       0
Bank Sta=4956.2,5027.4
XS Rating Curve= 0 ,0
Exp/Cntr=0.3,0.1

Type RM Length L Ch R = 1 ,186623  ,1227,1227,1227
BEGIN DESCRIPTION:
Mapping XS c2d08c80
END DESCRIPTION:
XS GIS Cut Line= 2
      3470418.82     10484645.88      3467580.73     10482146.28
#Sta/Elev= 30
  2302.1  437.13  2494.3  433.64  2741.9  436.03  3103.4  432.69  3663.1  413.33
  4010.3  409.91  4144.9  411.54  4219.4  411.43  4492.3  410.96  4780.6  413.94
  4974.2   411.9  4980.9  406.99  4988.5  406.83  4992.1     402  4994.9   401.5
  4998.1     402  5023.6  403.86  5044.5  413.63  5064.2   414.2  5179.2  415.56
  5264.5  419.64  5321.5  418.31  5363.2  423.13    5385  429.17  5399.3  430.47
  5434.4  428.51  5441.9  425.83  5491.3  425.61  5569.1  430.46    6084  437.74
#Mann= 7 ,-1 , 0
  2302.1     .05       0  4144.9     .16       0  4219.4     .05       0
  4780.6     .16       0  4992.1     .07       0  4998.1     .16       0
  5064.2     .05       0
Bank Sta=4974.2,5044.5
XS Rating Curve= 0 ,0
Exp/Cntr=0.3,0.1