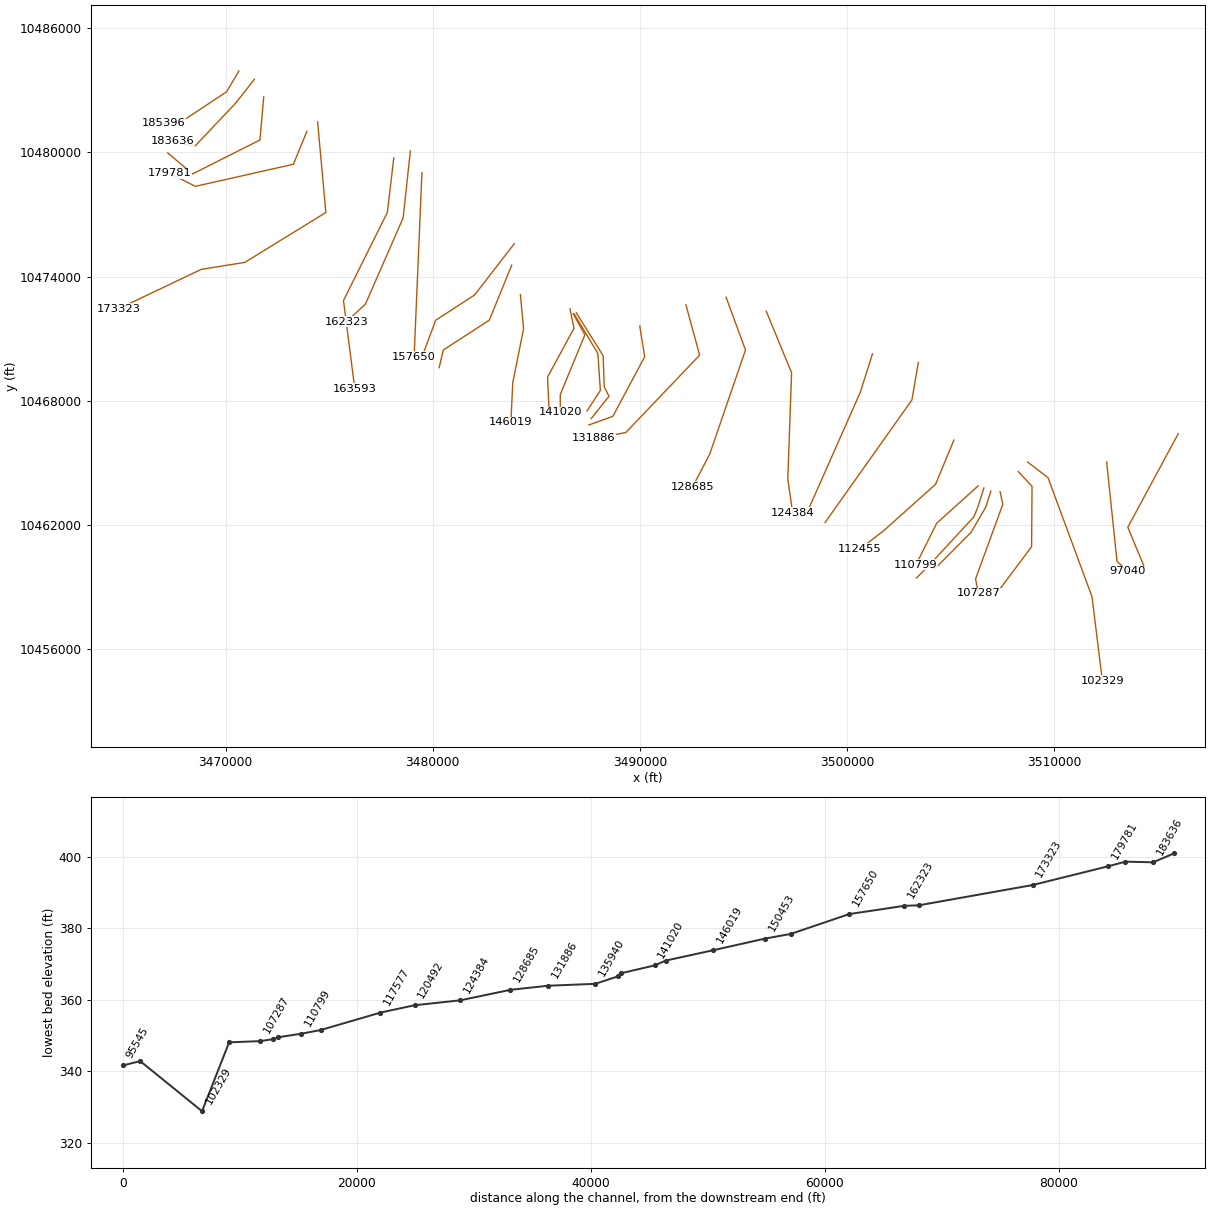
HEC-RAS study STEELE CREEK.prj: STEELE CREEK Base Level Engineering

--- STEELE CREEK.g01 (geometry) --- (continued)

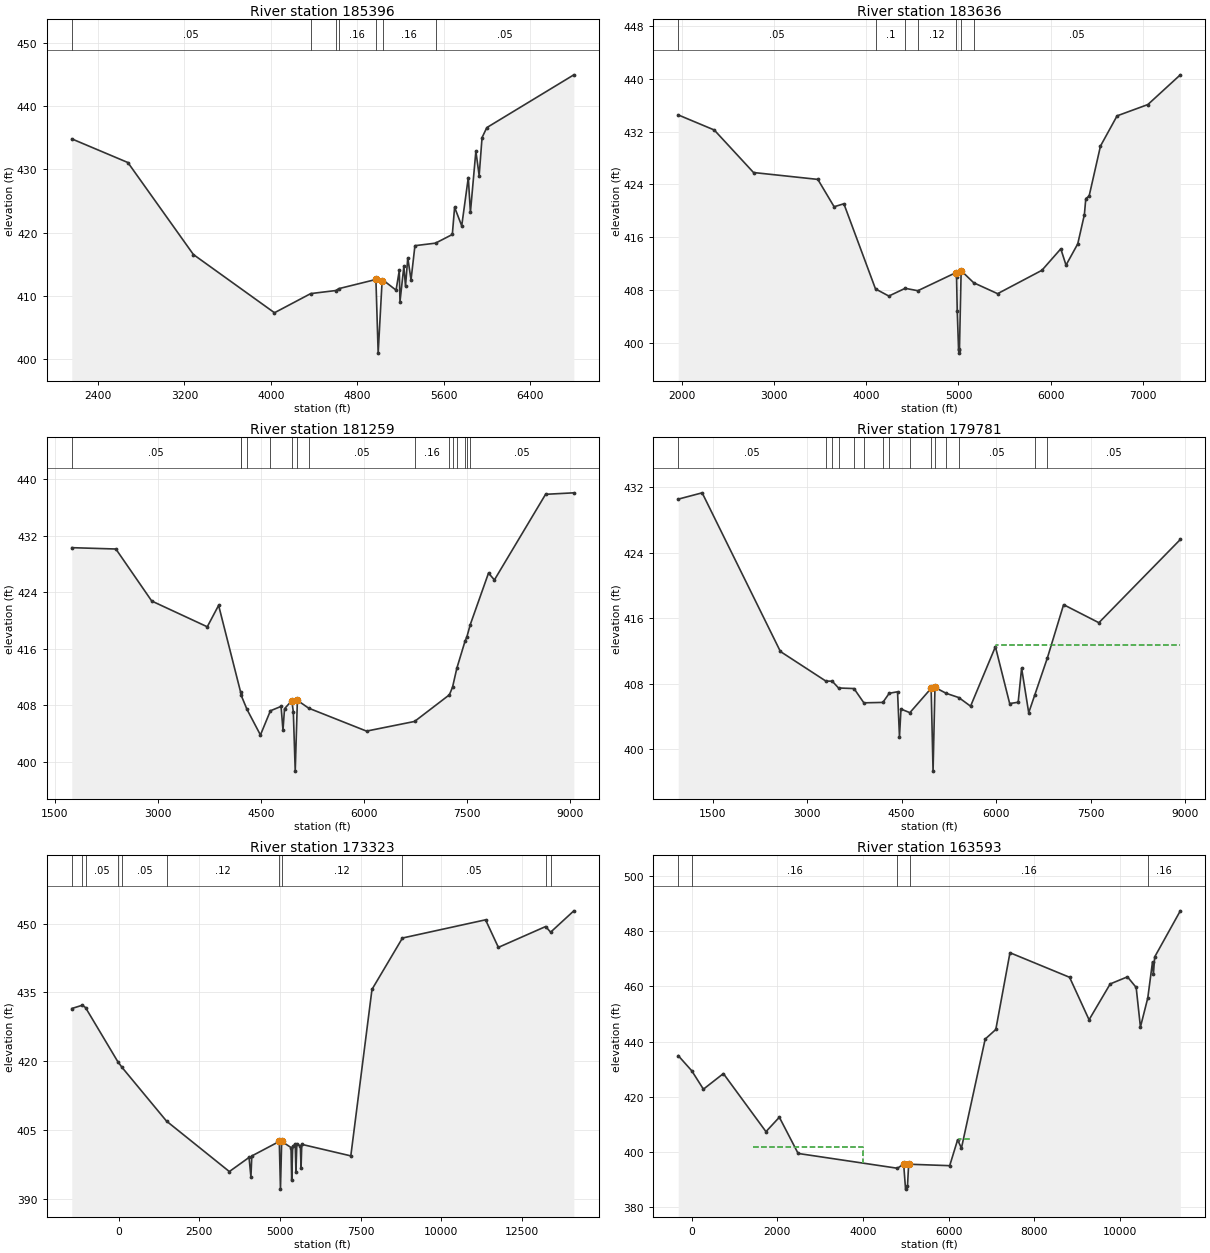
Type RM Length L Ch R = 1 ,185396  ,1760,1760,1760
BEGIN DESCRIPTION:
STEELE CREEK 97.0
END DESCRIPTION:
XS GIS Cut Line= 4
      3470641.44     10483933.78      3470044.65     10482924.67
      3467961.32     10481546.63      3466996.31     10481394.83
#Sta/Elev= 30
  2157.9  434.82  2677.3  431.08  3283.8  416.54  4034.2  407.34  4369.7  410.37
  4600.7  410.85  4629.7  411.15    4973   412.6  4993.8  400.96  5030.2  412.35
  5036.2  412.54  5159.6  410.91  5189.7  414.06  5195.7  409.08  5231.8   414.7
  5246.9  411.54  5267.9  416.03    5298  412.54  5334.2  417.94  5524.5  418.34
  5680.2  419.71  5701.3  424.01  5767.2  421.07  5828.1  428.71  5847.6  423.21
  5898.2  432.88  5928.6  429.02  5955.3  435.02  5999.4   436.6    6805  444.94
#Mann= 7 ,-1 , 0
  2157.9     .05       0  4369.7     .16       0  4600.7     .05       0
  4629.7     .16       0    4973     .07       0  5036.2     .16       0
  5524.5     .05       0
Bank Sta=4973,5030.2
XS Rating Curve= 0 ,0
Exp/Cntr=0.3,0.1

Type RM Length L Ch R = 1 ,183636  ,2377,2377,2377
BEGIN DESCRIPTION:
STEELE CREEK 96.0
END DESCRIPTION:
XS GIS Cut Line= 4
      3471390.11     10483532.27      3470467.83     10482360.43
      3468503.85     10480287.95      3467429.64     10480548.36
#Sta/Elev= 30
  1956.9  434.53  2347.8  432.25  2774.4  425.81  3472.7  424.77  3649.5  420.63
  3755.5  421.08  4098.9  408.19  4243.7  407.11    4421  408.28  4558.9  407.92
  4972.3  410.66  4979.1  409.96  4986.4  404.88  5000.6  399.11  5007.2  398.47
  5010.5  398.97  5028.9  410.95  5165.3  409.12  5424.9  407.47  5905.9  411.01
    6111  414.26  6167.6  411.79    6295  415.01  6366.9  419.42  6382.5  421.87
  6418.4  422.24  6541.8  429.82  6722.1  434.39  7056.3   436.1  7408.7   440.6
#Mann= 7 ,-1 , 0
  1956.9     .05       0  4098.9      .1       0    4421     .16       0
  4558.9     .12       0  4972.3     .07       0  5028.9     .12       0
  5165.3     .05       0
Bank Sta=4972.3,5028.9
XS Rating Curve= 0 ,0
Exp/Cntr=0.3,0.1

Type RM Length L Ch R = 1 ,181259  ,1478,1478,1478
BEGIN DESCRIPTION:
STEELE CREEK 94.0
END DESCRIPTION:
XS GIS Cut Line= 4
      3471838.99     10482681.25       3471656.7     10480597.92
      3468401.49     10478957.29      3467203.56     10479972.93
#Sta/Elev= 30
  1749.9  430.32  2391.9  430.13  2913.8  422.76  3721.9  419.11    3887  422.15
  4206.7  409.88  4214.3  409.43  4299.9  407.41  4495.8  403.78  4640.8  407.21
    4796  407.83  4823.9  404.47  4846.2   407.5  4952.2  408.65  4974.5  407.05
  5002.1  398.66  5033.4  408.69  5197.8  407.58  6039.6  404.33  6739.3   405.7
  7245.4  409.47  7291.7  410.56  7353.9  413.23  7475.1  417.13  7499.3  417.65
  7549.3  419.41  7815.1  426.72  7900.8  425.75  8645.6  437.88    9057  438.09
#Mann= 15 ,-1 , 0
  1749.9     .05       0  4206.7      .1       0  4214.3     .05       0
  4299.9      .1       0  4640.8     .12       0  4952.2     .07       0
  5033.4     .12       0  5197.8     .05       0  6739.3     .16       0
  7245.4      .1       0  7291.7     .05       0  7353.9     .16       0
  7475.1     .05       0  7499.3     .16       0  7549.3     .05       0
Bank Sta=4952.2,5033.4
XS Rating Curve= 0 ,0
Exp/Cntr=0.3,0.1

Type RM Length L Ch R = 1 ,179781  ,6458,6458,6458
BEGIN DESCRIPTION:
STEELE CREEK 95.0
END DESCRIPTION:
XS GIS Cut Line= 4
      3473922.33     10481014.59      3473271.28     10479426.04
      3468538.21     10478358.33       3467291.4     10478987.16
#Sta/Elev= 30
   956.2  430.53  1335.7   431.3  2576.8  411.95  3298.5  408.34  3398.9  408.33
  3499.3   407.5  3744.5  407.43  3901.1  405.69  4202.4  405.74  4302.9  406.85
  4435.4  407.04  4466.1  401.55  4489.9  404.93  4631.1  404.49  4968.4  407.46
  4998.9  397.36    5029  407.57  5206.8  406.85  5407.7  406.33  5593.8  405.28
    5988  412.53  6214.4   405.6  6349.2  405.76  6403.6  409.92  6516.4  404.48
    6613  406.66  6813.8   411.2  7069.9  417.66  7629.6  415.46  8921.4  425.61
#Mann= 15 ,-1 , 0
   956.2     .05       0  3298.5     .16       0  3398.9     .05       0
  3499.3     .16       0  3744.5     .05       0  3901.1     .16       0
  4202.4     .05       0  4302.9     .16       0  4631.1     .12       0
  4968.4     .07       0    5029     .12       0  5206.8      .1       0
  5407.7     .05       0    6613      .1       0  6813.8     .05       0
#XS Ineff= 2 , 0
                         5994.32          412.72
Permanent Ineff=
       F       F
Bank Sta=4968.4,5029
XS Rating Curve= 0 ,0
Exp/Cntr=0.3,0.1

Type RM Length L Ch R = 1 ,173323  ,9730,9730,9730
BEGIN DESCRIPTION:
STEELE CREEK 93.0
END DESCRIPTION:
XS GIS Cut Line= 5
      3474440.27     10481471.17      3474839.57     10477096.18
      3470926.15     10474686.46      3468818.16     10474347.92
      3464816.05     10472440.53
#Sta/Elev= 30
   -1450   431.5 -1121.5  432.22 -1023.3   431.7     -26  419.94   110.3  418.64
  1486.2  406.95  3432.9  395.95  4043.4  399.03  4101.3  394.75  4128.5  399.35
  4980.4  402.52  5016.8  392.12  5053.7  402.53  5343.6  401.19  5364.9  394.04
  5394.6  401.42  5474.9  401.92  5496.2  395.93  5523.8  402.02  5633.4  401.51
  5654.7  396.69  5676.5  401.88  7196.3  399.37  7852.6  435.67  8796.5  446.87
 11371.9  450.84 11768.9  444.83 13234.6  449.38 13387.2  448.14 14107.4   452.8
#Mann= 11 ,-1 , 0
   -1450     .05       0 -1121.5      .1       0 -1023.3     .05       0
     -26      .1       0   110.3     .05       0  1486.2     .12       0
  4980.4     .07       0  5053.7     .12       0  8796.5     .05       0
 13234.6     .16       0 13387.2     .05       0
Bank Sta=4980.4,5053.7
XS Rating Curve= 0 ,0
Exp/Cntr=0.3,0.1

Type RM Length L Ch R = 1 ,163593  ,1270,1270,1270
BEGIN DESCRIPTION:
STEELE CREEK 92.0
END DESCRIPTION:
XS GIS Cut Line= 4
      3478120.82     10479735.04      3477808.32     10477096.18
      3475690.27     10472842.71      3476238.64     10468568.49
#Sta/Elev= 30
  -311.4  434.87     4.2  429.38   276.1   422.7   742.4  428.36  1736.2   407.3
  2048.4  412.53  2486.9  399.39  4805.8  394.02  4949.6  395.59  4994.1  386.45
  5039.2  387.51  5067.2  395.73  5099.1  395.47  6024.3  394.96  6208.9  404.33
  6298.5  401.33  6852.6  440.88  7100.6  444.36  7431.3   472.2  8822.6  463.29
  9277.2  447.88  9770.3  460.88 10173.6  463.46 10376.7   459.6 10476.1  445.25
 10647.5  455.79 10758.4  468.93 10778.5  464.35 10808.8  470.68 11406.8   487.4
#Mann= 5 ,-1 , 0
  -311.4     .05       0     4.2     .16       0  4805.8     .12       0
  5099.1     .16       0 10647.5     .16       0
#XS Ineff= 2 ,-1
 1433.48 4011.11   401.6 6230.06 6507.15  404.67
Permanent Ineff=
       T       T
Bank Sta=4949.6,5067.2
XS Rating Curve= 0 ,0
Exp/Cntr=0.3,0.1

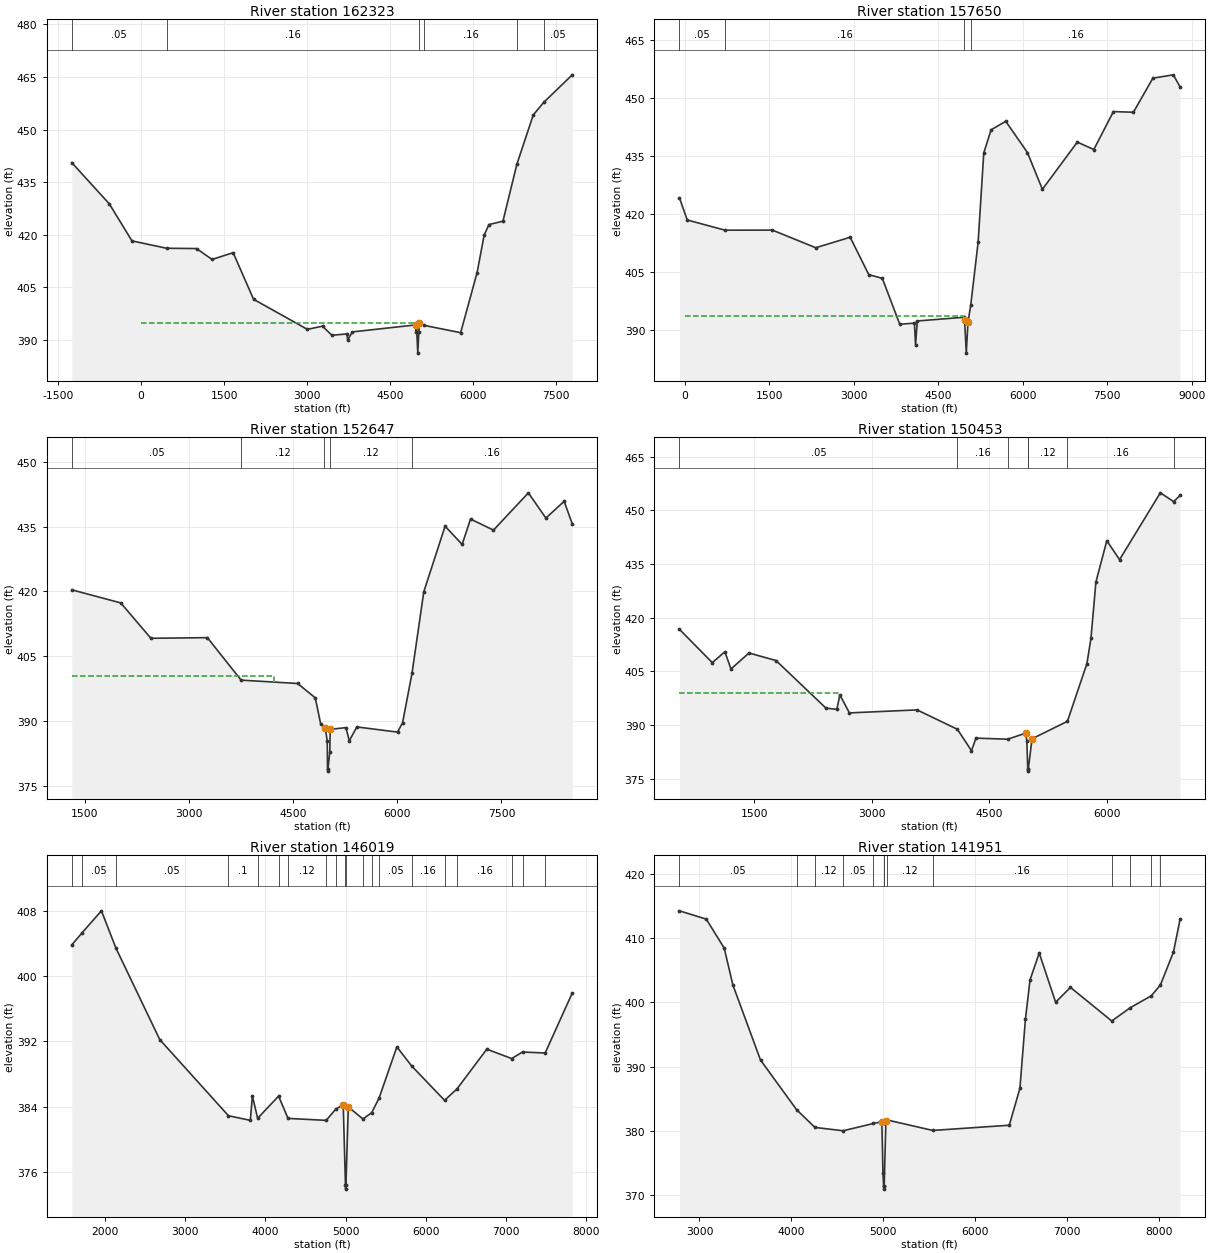
Type RM Length L Ch R = 1 ,162323  ,4673,4673,4673
BEGIN DESCRIPTION:
STEELE CREEK 91.0
END DESCRIPTION:
XS GIS Cut Line= 4
      3478919.43      10480064.9      3478572.21     10476835.76
      3476749.29      10472669.1      3475829.13     10471818.38
#Sta/Elev= 30
 -1254.3  440.62    -575  428.86  -164.8  418.29   460.3  416.19  1001.9   416.1
  1283.5  412.99  1663.9  414.93  2033.6  401.64  3005.9  393.07  3279.5  393.98
  3448.7  391.39  3722.4  391.76  3733.5  390.03  3820.8  392.34  4966.9  394.34
  4973.7  392.26  4979.2  393.79  5002.3  386.29  5020.5  392.29  5032.4  394.77
  5113.8  394.21  5776.8  392.12  6073.8  409.22  6201.7  419.91  6287.6  422.94
  6541.4   423.9  6792.5   440.1  7089.6   454.2  7279.5  457.79  7794.6  465.63
#Mann= 6 ,-1 , 0
 -1254.3     .05       0   460.3     .16       0  5020.5     .12       0
  5113.8     .16       0  6792.5     .16       0  7279.5     .05       0
#XS Ineff= 2 , 0
       0 4957.13  394.84               0
Permanent Ineff=
       T       F
Bank Sta=4966.9,5032.4
XS Rating Curve= 0 ,0
Exp/Cntr=0.3,0.1

Type RM Length L Ch R = 1 ,157650  ,5003,5003,5003
BEGIN DESCRIPTION:
STEELE CREEK 90.0
END DESCRIPTION:
XS GIS Cut Line= 2
      3479479.55     10479019.77      3479101.94     10470139.49
#Sta/Elev= 30
   -94.5  424.16    43.7  418.45   714.4  415.81  1555.1  415.83  2325.8  411.27
  2936.4  413.98  3266.7  404.31  3506.9  403.35  3817.2  391.47  4077.4  391.77
  4097.4     386  4127.4  392.32  4958.2  393.28  4968.2  392.58    4998     384
  5028.2  391.95  5078.3  396.53  5208.4  412.71  5308.5  435.79  5438.6  441.77
  5698.9  443.99  6083.6  435.91  6349.4  426.39    6970   438.6  7262.6  436.68
  7610.6   446.5    7966  446.33  8311.2  455.15  8674.4  456.01  8793.8  452.89
#Mann= 4 ,-1 , 0
   -94.5     .05       0   714.4     .16       0  4958.2     .12       0
  5078.3     .16       0
#XS Ineff= 2 , 0
       0 4961.36  393.52               0
Permanent Ineff=
       T       F
Bank Sta=4968.2,5028.2
XS Rating Curve= 0 ,0
Exp/Cntr=0.3,0.1

Type RM Length L Ch R = 1 ,152647  ,2194,2194,2194
BEGIN DESCRIPTION:
STEELE CREEK 86.0
END DESCRIPTION:
XS GIS Cut Line= 4
      3483942.12     10475591.67      3482018.61     10473108.26
      3480142.11     10471891.64      3479505.59     10470178.57
#Sta/Elev= 30
  1314.7  420.37  2020.9  417.34  2454.6  409.16  3267.6  409.31  3752.9  399.49
  4567.1  398.71  4820.9  395.39  4899.4   389.3  4950.8  388.75  4964.2  388.48
    4993  385.42    4997  378.95  4999.7  378.45  5029.2  382.77  5035.7  388.11
  5261.9  388.51  5310.1  385.46  5418.9  388.67    6005  387.47  6077.5  389.66
  6213.8  401.14  6382.4   419.9  6689.3  435.08  6934.3  430.86  7055.8  436.73
  7385.7  434.16  7888.1  442.79    8140  436.95  8402.6  440.83  8519.8  435.62
#Mann= 5 ,-1 , 0
  1314.7     .05       0  3752.9     .12       0  4950.8     .07       0
  5035.7     .12       0  6213.8     .16       0
#XS Ineff= 2 , 0
         4222.73  400.34
Permanent Ineff=
       F       F
Bank Sta=4964.2,5035.7
XS Rating Curve= 0 ,0
Exp/Cntr=0.3,0.1

Type RM Length L Ch R = 1 ,150453  ,4434,4434,4434
BEGIN DESCRIPTION:
STEELE CREEK 84.0
END DESCRIPTION:
XS GIS Cut Line= 4
      3483815.48     10474553.56      3482734.75     10471897.32
      3480508.19     10470452.01      3480312.99     10469606.15
#Sta/Elev= 30
     545  416.75     964  407.44  1124.6  410.49  1202.1  405.67  1432.3  410.14
  1777.8  408.03  2414.8  394.75  2553.5   394.4 2593.18  398.42  2714.1  393.41
    3578  394.25  4092.9  388.83  4272.7  382.85  4330.1  386.36    4737  386.07
  4965.7  387.77  4979.3  385.61  4991.5  377.65  4994.2  377.15  4997.5  377.65
  5045.9  386.19  5497.3  391.05  5746.5  407.19  5797.9  414.22  5861.2  429.96
  6000.3   441.5    6163  436.21  6683.4  454.87  6853.7  452.42  6935.3  454.15
#Mann= 7 ,-1 , 0
     545     .05       0  4092.9     .16       0    4737     .12       0
  4991.5     .07       0  4997.5     .12       0  5497.3     .16       0
  6853.7      .1       0
#XS Ineff= 2 , 0
         2585.23  398.92
Permanent Ineff=
       F       F
Bank Sta=4965.7,5045.9
XS Rating Curve= 0 ,0
Exp/Cntr=0.3,0.1

Type RM Length L Ch R = 1 ,146019  ,4068,4068,4068
BEGIN DESCRIPTION:
STEELE CREEK 83.0
END DESCRIPTION:
XS GIS Cut Line= 4
      3484232.15     10473134.27       3484388.4     10471480.66
      3483867.57     10468889.51      3483774.58      10466957.9
#Sta/Elev= 30
  1585.4  403.78  1717.4  405.31  1955.8  407.97  2136.4  403.41  2682.9   392.2
  3538.8  382.88  3811.3  382.31    3837  385.29  3902.9  382.57  4163.6  385.28
  4280.9  382.55  4756.9  382.31    4876  383.69  4969.2  384.21  4996.8  374.39
  4999.5  373.89  5002.8  374.39  5032.3  383.96  5214.6  382.48  5323.8  383.25
  5416.4  385.06  5637.6  391.31    5820  388.99  6232.3  384.76  6388.6  386.19
  6758.2  391.03  7067.6  389.88  7203.9  390.68  7485.5  390.56  7823.2  397.91
#Mann= 20 ,-1 , 0
  1585.4     .05       0  1717.4     .05       0  2136.4     .05       0
  3538.8      .1       0  3902.9     .12       0  4163.6     .05       0
  4280.9     .12       0  4756.9     .16       0    4876     .12       0
  4996.8     .07       0  5002.8     .12       0  5214.6     .05       0
  5323.8     .07       0  5416.4     .05       0    5820     .16       0
  6232.3      .1       0  6388.6     .16       0  7067.6     .16       0
  7203.9     .16       0  7485.5     .16       0
Bank Sta=4969.2,5032.3
XS Rating Curve= 0 ,0
Exp/Cntr=0.3,0.1

Type RM Length L Ch R = 1 ,141951  ,931,931,931
BEGIN DESCRIPTION:
STEELE CREEK 82.0
END DESCRIPTION:
XS GIS Cut Line= 4
      3486627.99     10472444.18       3486823.3      10471506.7
      3485547.25     10469149.93      3485625.38     10467340.07
#Sta/Elev= 30
  2782.3  414.24  3074.1  412.95  3269.2  408.45  3364.2   402.7  3664.5  391.05
  4057.6  383.33  4257.1  380.58  4563.5  380.06  4893.8  381.19  4985.2  381.48
  4997.2  373.56  5004.7  371.49  5007.4  370.99  5010.7  371.49  5029.5  381.53
  5038.6  381.75  5539.5  380.11  6372.5  380.92  6488.3  386.66  6548.4  397.41
  6598.4  403.51  6698.5  407.68    6877  400.04  7038.8  402.34    7488  397.12
  7689.1  399.18  7918.9  401.04    8017   402.7  8159.9  407.83  8231.5  412.92
#Mann= 13 ,-1 , 0
  2782.3     .05       0  4057.6      .1       0  4257.1     .12       0
  4563.5     .05       0  4893.8     .16       0  5004.7     .07       0
  5010.7     .16       0  5038.6     .12       0  5539.5     .16       0
    7488     .05       0  7689.1      .1       0  7918.9     .16       0
    8017     .05       0
Bank Sta=4985.2,5029.5
XS Rating Curve= 0 ,0
Exp/Cntr=0.3,0.1

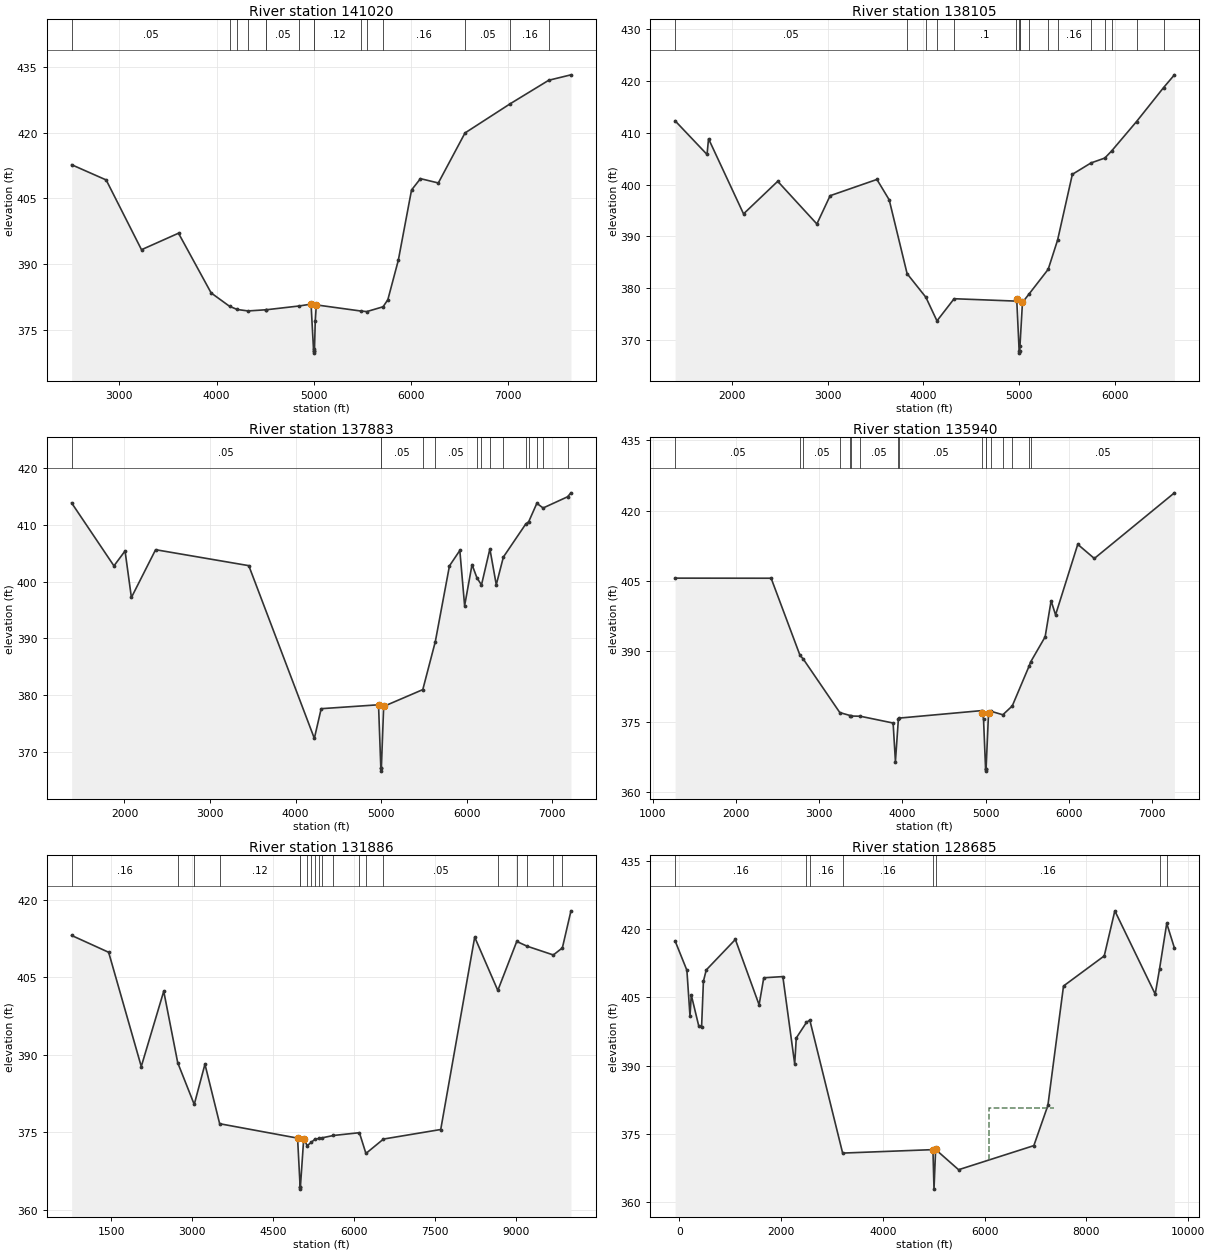
Type RM Length L Ch R = 1 ,141020  ,2915,2915,2915
BEGIN DESCRIPTION:
STEELE CREEK 81.0
END DESCRIPTION:
XS GIS Cut Line= 4
      3486787.77     10472201.62      3487347.68     10471185.97
      3486159.23     10468303.57      3486159.23     10467445.42
#Sta/Elev= 30
  2508.6   412.7  2863.8  409.22  3227.2  393.28  3607.8  397.05  3943.5   383.4
  4132.9  380.35  4211.9  379.62  4323.1  379.29  4509.7  379.56  4511.3  379.56
  4851.2  380.43    4971  380.85  4996.3  370.52  4999.9  370.15  5002.7  369.65
  5005.9  370.15  5014.3  376.97  5025.1  380.67  5479.8  379.28  5543.7  379.14
  5711.8  380.24  5760.7  381.85  5868.5  390.87  6004.4  406.92    6096  409.52
  6279.9  408.53  6554.6  419.96  7021.5  426.66  7415.6     432  7644.3  433.24
#Mann= 16 ,-1 , 0
  2508.6     .05       0  4132.9      .1       0  4211.9     .12       0
  4323.1     .05       0  4509.7      .1       0  4511.3     .05       0
  4851.2     .16       0  4996.3     .12       0  4999.9     .07       0
  5005.9     .12       0  5479.8     .16       0  5543.7     .12       0
  5711.8     .16       0  6554.6     .05       0  7021.5     .16       0
  7415.6     .05       0
Bank Sta=4971,5025.1
XS Rating Curve= 0 ,0
Exp/Cntr=0.3,0.1

Type RM Length L Ch R = 1 ,138105  ,222,222,222
BEGIN DESCRIPTION:
Mapping XS d1f2cbd6
END DESCRIPTION:
XS GIS Cut Line= 4
      3486826.86     10472204.18      3487973.84     10470288.18
      3488096.47     10468502.29      3487450.62      10467509.2
#Sta/Elev= 30
    1410  412.31  1743.3   405.8  1758.9  408.84  2123.9  394.33  2480.3  400.62
  2888.7  392.38  3026.8  397.84  3514.9  400.98  3643.1  397.04  3829.7  382.78
  4025.9  378.21  4141.2  373.66  4320.2  377.94  4964.7  377.48  4972.7  377.94
  4998.2  367.93  5000.9  367.43  5004.2  367.93  5006.9  368.84  5032.9  377.23
    5105  378.93  5301.2  383.62  5399.3  389.27  5553.2  401.97  5747.7  404.17
  5891.5  405.11  5963.6   406.5  6222.5  412.16  6504.8  418.73  6617.8  421.19
#Mann= 17 ,-1 , 0
    1410     .05       0  3829.7     .16       0  4025.9     .05       0
  4141.2     .16       0  4320.2      .1       0  4964.7     .05       0
  4998.2     .03       0  5004.2     .05       0  5006.9     .16       0
    5105     .12       0  5301.2     .05       0  5399.3     .16       0
  5747.7      .1       0  5891.5     .16       0  5963.6      .1       0
  6222.5     .05       0  6504.8      .1       0
Bank Sta=4972.7,5032.9
XS Rating Curve= 0 ,0
Exp/Cntr=0.3,0.1

Type RM Length L Ch R = 1 ,137883  ,1943,1943,1943
BEGIN DESCRIPTION:
Mapping XS 39499460
END DESCRIPTION:
XS GIS Cut Line= 5
      3486936.22     10472248.26      3488229.63     10470177.94
      3488282.58     10468677.94      3488511.75      10468219.6
      3487650.81     10467136.49
#Sta/Elev= 30
  1382.2  413.85    1877  402.76  2006.7  405.39    2081  397.19    2364  405.61
  3453.4   402.8  4219.9  372.37  4299.9   377.6  4970.3  378.29  4997.4   367.1
  5000.1   366.6  5003.4   367.1  5030.4     378  5487.8  380.96  5634.3  389.42
  5799.6  402.76  5920.8  405.48  5976.9  395.74  6063.4  402.98    6121  400.65
    6174   399.4  6272.3  405.75  6346.9  399.44  6430.1  404.32  6691.8  410.14
  6726.2  410.55  6821.3  413.78  6894.8  412.96    7180  414.93  7220.3  415.63
#Mann= 14 ,-1 , 0
  1382.2     .05       0  4997.4     .04       0  5003.4     .05       0
  5487.8     .12       0  5634.3     .05       0    6121     .16       0
    6174     .05       0  6272.3      .1       0  6430.1     .16       0
  6691.8     .05       0  6726.2     .16       0  6821.3     .05       0
  6894.8     .16       0    7180     .05       0
Bank Sta=4970.3,5030.4
XS Rating Curve= 0 ,0
Exp/Cntr=0.3,0.1

Type RM Length L Ch R = 1 ,135940  ,4054,4054,4054
BEGIN DESCRIPTION:
STEELE CREEK 80.0
END DESCRIPTION:
XS GIS Cut Line= 4
      3490000.38     10471610.82      3490234.75     10470126.49
       3488698.3     10467248.88      3487539.45     10466832.22
#Sta/Elev= 30
  1270.7  405.63    2424  405.61  2770.5  389.18  2809.2  388.41  3248.7  376.98
  3374.4  376.34  3380.3  376.24    3494   376.2  3888.9  374.75  3916.6  366.55
  3952.1  375.61  3960.4   375.8    4954   377.4  4958.2  376.98  4974.5  375.64
  4999.1     365  5001.8   364.5  5005.1     365  5034.7  376.85  5065.5  377.25
  5206.3  376.51  5319.5  378.39  5522.9  386.93  5539.8  387.75  5714.4  393.12
    5786  400.79  5839.7   397.8  6106.2  412.83  6305.3  409.82    7267  423.81
#Mann= 17 ,-1 , 0
  1270.7     .05       0  2770.5      .1       0  2809.2     .05       0
  3248.7     .16       0  3374.4     .05       0  3380.3     .16       0
    3494     .05       0  3952.1     .16       0  3960.4     .05       0
    4954     .12       0  4999.1     .07       0  5005.1     .12       0
  5065.5     .05       0  5206.3     .16       0  5319.5     .05       0
  5522.9     .12       0  5539.8     .05       0
Bank Sta=4958.2,5034.7
XS Rating Curve= 0 ,0
Exp/Cntr=0.3,0.1

Type RM Length L Ch R = 1 ,131886  ,3201,3201,3201
BEGIN DESCRIPTION:
STEELE CREEK 79.0
END DESCRIPTION:
XS GIS Cut Line= 4
      3492226.95     10472639.47        3492891.     10470204.61
       3489323.3     10466467.63      3487786.94      10466181.2
#Sta/Elev= 30
   766.6   413.1  1452.5  409.84  2057.1  387.71  2473.4  402.29  2732.7  388.44
  3038.6  380.36    3237  388.16  3509.6  376.63  4953.7  373.84  5000.4  364.46
  5003.2  363.96  5006.4  364.46  5066.9  373.68  5132.3  372.38  5211.5  373.06
  5273.3  373.61  5348.9  373.77  5414.3  373.91  5616.6  374.35  6099.1  374.89
  6220.1  370.87  6545.6  373.66  7606.3  375.51  8235.7  412.77  8664.1  402.45
  9015.3  411.94    9206  411.02    9693  409.32  9860.4  410.69 10019.8  417.87
#Mann= 20 ,-1 , 0
   766.6     .16       0  2732.7     .12       0  3038.6     .16       0
  3509.6     .12       0  5000.4     .07       0  5006.4     .12       0
  5132.3      .1       0  5211.5     .12       0  5273.3      .1       0
  5348.9     .16       0  5414.3      .1       0  5616.6     .05       0
  6099.1     .16       0  6220.1     .12       0  6545.6     .05       0
  8664.1     .16       0  9015.3     .05       0    9206     .16       0
    9693      .1       0  9860.4     .05       0
#XS Ineff= 2 , 0
         3238.64  388.01
Permanent Ineff=
       F       F
Bank Sta=4953.7,5066.9
XS Rating Curve= 0 ,0
Exp/Cntr=0.3,0.1

Type RM Length L Ch R = 1 ,128685  ,4301,4301,4301
BEGIN DESCRIPTION:
STEELE CREEK 78.0
END DESCRIPTION:
XS GIS Cut Line= 4
      3494167.04     10473004.11      3495104.55     10470452.01
      3493372.77     10465412.95      3492552.47     10463850.47
#Sta/Elev= 30
   -82.5  417.43   149.4  410.97   210.4  400.89   235.6  405.53   382.6  398.71
   438.3  398.52   474.1  408.55   529.7  411.04    1102  417.75  1568.4  403.36
  1659.8  409.32  2034.8  409.58    2268  390.34  2298.5  396.07  2498.2  399.49
  2564.5  400.01  3209.7  370.75  4984.2  371.51  5005.1  362.82    5037  371.54
  5488.2  367.09  6966.8  372.39  7242.7  381.23  7549.9  407.51  8350.2  414.13
  8558.4  424.05  9351.7  405.72  9436.9  411.27  9578.2  421.28  9729.4  415.87
#Mann= 8 ,-1 , 0
   -82.5     .16       0  2498.2      .1       0  2564.5     .16       0
  3209.7     .16       0  4984.2     .12       0    5037     .16       0
  9436.9     .05       0  9578.2     .16       0
#XS Ineff= 1 ,-1
 6085.49 7360.79  380.59
Permanent Ineff=
       T
Bank Sta=4984.2,5037
XS Rating Curve= 0 ,0
Exp/Cntr=0.3,0.1

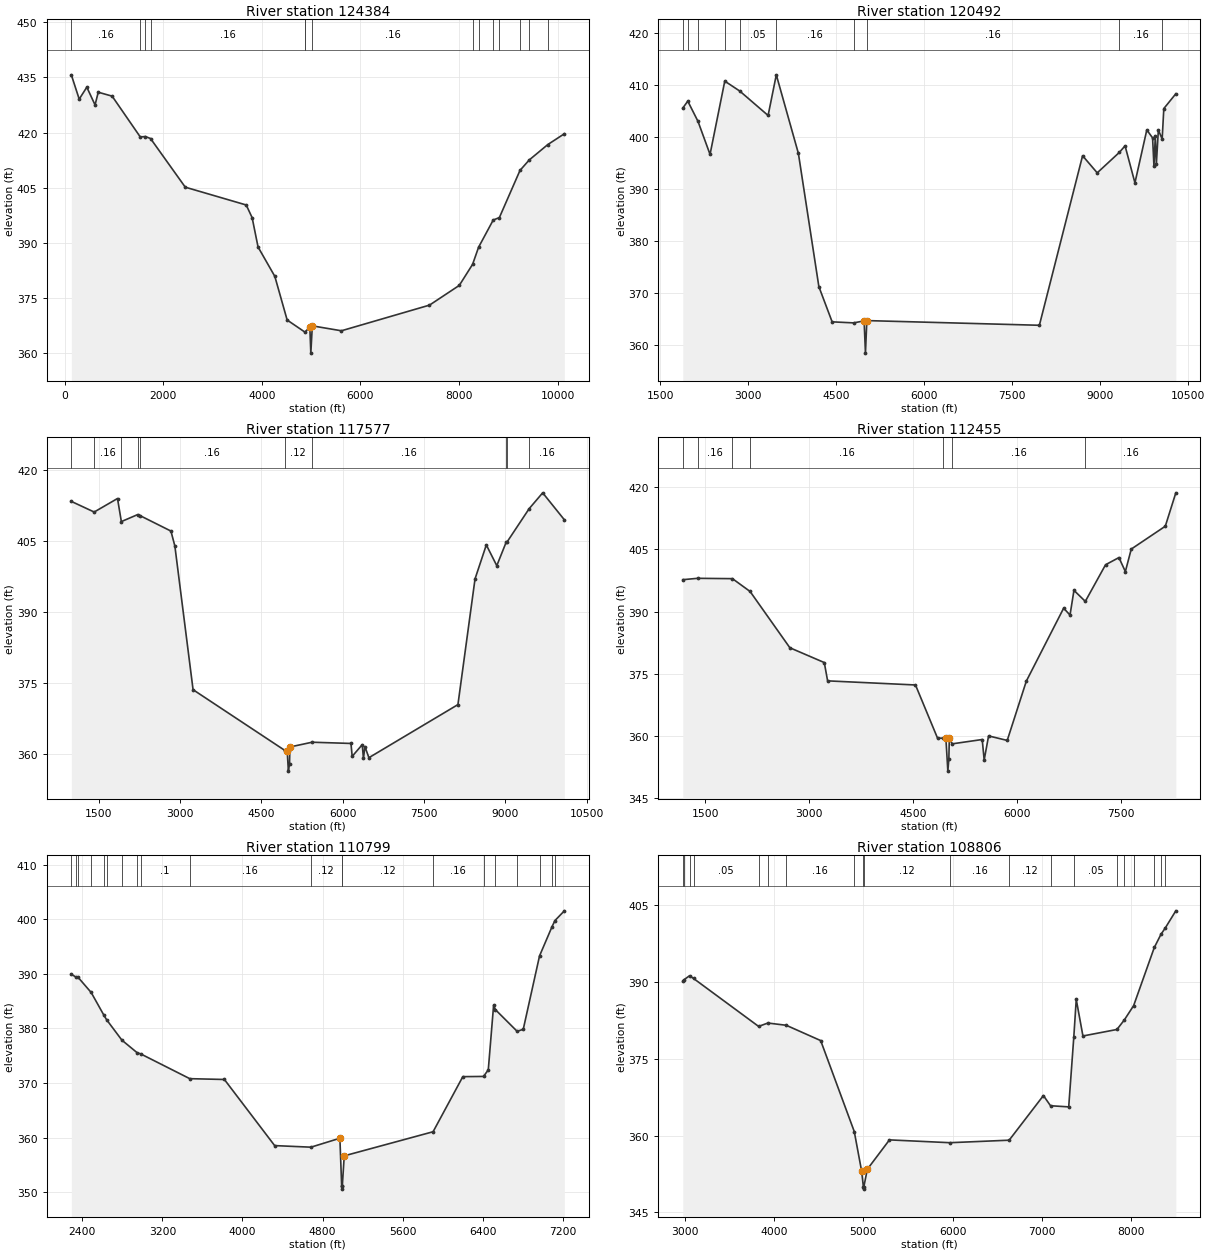
Type RM Length L Ch R = 1 ,124384  ,3892,3892,3892
BEGIN DESCRIPTION:
STEELE CREEK 77.0
END DESCRIPTION:
XS GIS Cut Line= 4
      3496107.15       10472327.      3497331.11     10469358.26
      3497148.82     10464228.05      3497383.19     10462587.41
#Sta/Elev= 30
   136.1  435.72   296.1   429.1   450.5  432.35   617.8  427.51   682.1  430.98
     964  429.91  1534.3   418.8  1638.7   418.9  1743.2  418.36    2448   405.1
  3684.1  400.25  3804.2   396.8  3924.2   388.8  4264.4   380.8  4514.6   368.9
  4874.8  365.61  4974.9  366.96  4994.7  359.88  5024.9  367.31  5615.3  365.97
  7401.9  372.96  8006.8  378.34    8277  384.09  8397.9  388.74  8694.8  396.15
  8819.7  396.82  9237.9  409.67  9425.1  412.52  9803.4  416.73   10138  419.66
#Mann= 14 ,-1 , 0
   136.1     .16       0  1534.3     .16       0  1638.7     .05       0
  1743.2     .16       0  4874.8     .05       0  4874.8     .12       0
  5024.9     .16       0    8277     .12       0  8397.9     .16       0
  8694.8     .12       0  8819.7     .16       0  9237.9     .05       0
  9425.1     .16       0  9803.4     .05       0
Bank Sta=4974.9,5024.9
XS Rating Curve= 0 ,0
Exp/Cntr=0.3,0.1

Type RM Length L Ch R = 1 ,120492  ,2915,2915,2915
BEGIN DESCRIPTION:
STEELE CREEK 73.0
END DESCRIPTION:
XS GIS Cut Line= 4
      3501237.36     10470269.71      3500649.13     10468411.87
      3498659.23     10463915.55      3498034.23     10462509.29
#Sta/Elev= 30
  1884.5  405.58  1969.7  406.92  2144.3  403.02  2349.2  396.68  2600.4  410.76
    2855  408.86  3339.1  404.16  3478.8  411.97  3855.4  396.87  4204.4  371.28
  4430.4  364.52  4795.8  364.32  4975.6   364.7  4998.6  358.51  5022.1  364.76
  7963.2  363.86  8699.8  396.43  8949.2  393.14  9325.4  397.06  9423.9  398.33
  9592.1  391.22  9794.6  401.39  9893.1  399.85  9916.3  394.44  9939.6  400.21
  9957.3   394.8  9991.5  401.38 10056.3  399.64 10084.6  405.49 10289.1  408.33
#Mann= 10 ,-1 , 0
  1884.5     .16       0  1969.7     .05       0  2144.3     .16       0
  2600.4     .05       0    2855     .05       0  3478.8     .16       0
  4795.8     .12       0  5022.1     .16       0  9325.4     .16       0
 10056.3     .05       0
Bank Sta=4975.6,5022.1
XS Rating Curve= 0 ,0
Exp/Cntr=0.3,0.1

Type RM Length L Ch R = 1 ,117577  ,5122,5122,5122
BEGIN DESCRIPTION:
STEELE CREEK 71.0
END DESCRIPTION:
XS GIS Cut Line= 3
      3503450.89     10469853.03      3503142.11     10468041.64
      3498946.38     10462119.66
#Sta/Elev= 30
   991.9  413.47  1413.7  411.22  1843.9  414.08  1914.9   409.2  2215.5  410.68
  2260.2  410.46  2829.4   407.2    2902  404.04  3237.9  373.67    4925  360.88
  4974.1  360.79  4996.2  356.46  5017.3  358.02  5023.4  361.56  5433.2  362.57
  6150.7  362.31  6172.8  359.58    6359  362.06  6380.7  359.15    6408  361.64
  6481.6   359.3  8123.8  370.52  8439.4   397.1  8647.4  404.27  8840.6  399.88
  9012.8  404.82  9032.3  404.93  9436.9  411.92  9687.2  415.28 10087.1  409.58
#Mann= 10 ,-1 , 0
   991.9     .05       0  1413.7     .16       0  1914.9      .1       0
  2215.5     .16       0  2260.2     .16       0    4925     .12       0
  5433.2     .16       0  9012.8     .16       0  9032.3     .05       0
  9436.9     .16       0
Bank Sta=4974.1,5023.4
XS Rating Curve= 0 ,0
Exp/Cntr=0.3,0.1

Type RM Length L Ch R = 1 ,112455  ,1656,1656,1656
BEGIN DESCRIPTION:
STEELE CREEK 68.0
END DESCRIPTION:
XS GIS Cut Line= 4
      3505169.64     10466103.04      3504284.23     10463967.63
      3501810.27     10461754.09      3500638.37     10460842.61
#Sta/Elev= 30
  1175.7  397.72  1388.5  398.05  1892.4  397.97  2147.2  394.88  2721.3  381.31
  3218.3  377.74  3266.1  373.33  4534.4  372.34  4852.9  359.51  4930.7  359.52
  4973.3  359.48  5001.5  351.57  5015.9  354.53  5022.6  359.46  5065.2  358.15
  5497.4  359.19  5525.8  354.26  5589.4  360.06  5858.5  358.97  6134.4  373.28
  6672.7  390.85  6764.7  389.19  6821.5  395.15  6985.3  392.49  7277.5  401.32
  7470.3  403.05  7563.5  399.68  7648.6   405.1  8139.9  410.61  8291.7  418.66
#Mann= 7 ,-1 , 0
  1175.7     .05       0  1388.5     .16       0  1892.4     .05       0
  2147.2     .16       0  4930.7     .12       0  5065.2     .16       0
  6985.3     .16       0
Bank Sta=4973.3,5022.6
XS Rating Curve= 0 ,0
Exp/Cntr=0.3,0.1

Type RM Length L Ch R = 1 ,110799  ,1993,1993,1993
BEGIN DESCRIPTION:
STEELE CREEK 67.0
END DESCRIPTION:
XS GIS Cut Line= 3
      3506342.13     10463891.67      3504342.11     10462091.64
      3503342.12     10460091.67
#Sta/Elev= 30
  2289.7  389.94  2334.8  389.44  2355.8  389.41  2488.2   386.6  2612.6  382.52
  2641.7  381.62  2795.2  377.86  2948.6  375.54    2981  375.36  3473.5   370.8
  3819.3  370.65  4321.6  358.53  4684.3  358.24  4973.4  359.88  4991.4  351.05
  4994.2  350.55  4997.4  351.05  5016.8  356.65  5904.7  361.07  6201.9  371.17
  6408.8  371.21  6456.3  372.42  6509.4  384.24  6528.1  383.44  6744.6  379.48
  6805.7  379.85  6968.5  393.31  7093.7  398.68  7122.6  399.79  7216.5  401.57
#Mann= 20 ,-1 , 0
  2289.7      .1       0  2334.8     .05       0  2355.8     .16       0
  2488.2     .05       0  2612.6     .16       0  2641.7     .05       0
  2795.2      .1       0  2948.6     .05       0    2981      .1       0
  3473.5     .16       0  4684.3     .12       0  4991.4     .07       0
  4997.4     .12       0  5904.7     .16       0  6408.8     .05       0
  6528.1      .1       0  6744.6      .1       0  6968.5     .05       0
  7093.7     .16       0  7122.6     .05       0
Bank Sta=4973.4,5016.8
XS Rating Curve= 0 ,0
Exp/Cntr=0.3,0.1

Type RM Length L Ch R = 1 ,108806  ,391,391,391
BEGIN DESCRIPTION:
STEELE CREEK 65.0
END DESCRIPTION:
XS GIS Cut Line= 5
      3506617.57     10463791.61      3506331.11     10462880.13
       3506135.8     10462398.36      3504091.52     10460184.82
      3503362.38     10459442.66
#Sta/Elev= 30
    2975  390.18    2992   390.5  3051.3  391.24  3096.1   390.7  3825.3  381.34
  3929.5     382  4135.3  381.56  4521.4  378.57    4898   360.8  4981.2  353.01
  4999.8  350.05  5002.5  349.55  5005.8  350.05  5044.8  353.44  5292.5  359.17
  5970.4  358.62  6634.9  359.11  7019.2  367.83  7098.7  365.84  7302.7  365.62
  7359.6  379.21  7387.2  386.61  7462.2  379.47  7843.6  380.74    7927  382.62
  8030.8   385.4  8262.6  396.76  8337.2  399.33  8385.9  400.58  8503.8  403.92
#Mann= 20 ,-1 , 0
    2975      .1       0    2992     .05       0  3051.3      .1       0
  3096.1     .05       0  3825.3      .1       0  3929.5     .12       0
  4135.3     .16       0    4898     .12       0  4999.8     .07       0
  5005.8     .12       0  5970.4     .16       0  6634.9     .12       0
  7098.7     .16       0  7359.6     .05       0  7843.6      .1       0
    7927     .16       0  8030.8      .1       0  8262.6     .16       0
  8337.2      .1       0  8385.9     .16       0
Bank Sta=4981.2,5044.8
XS Rating Curve= 0 ,0
Exp/Cntr=0.3,0.1

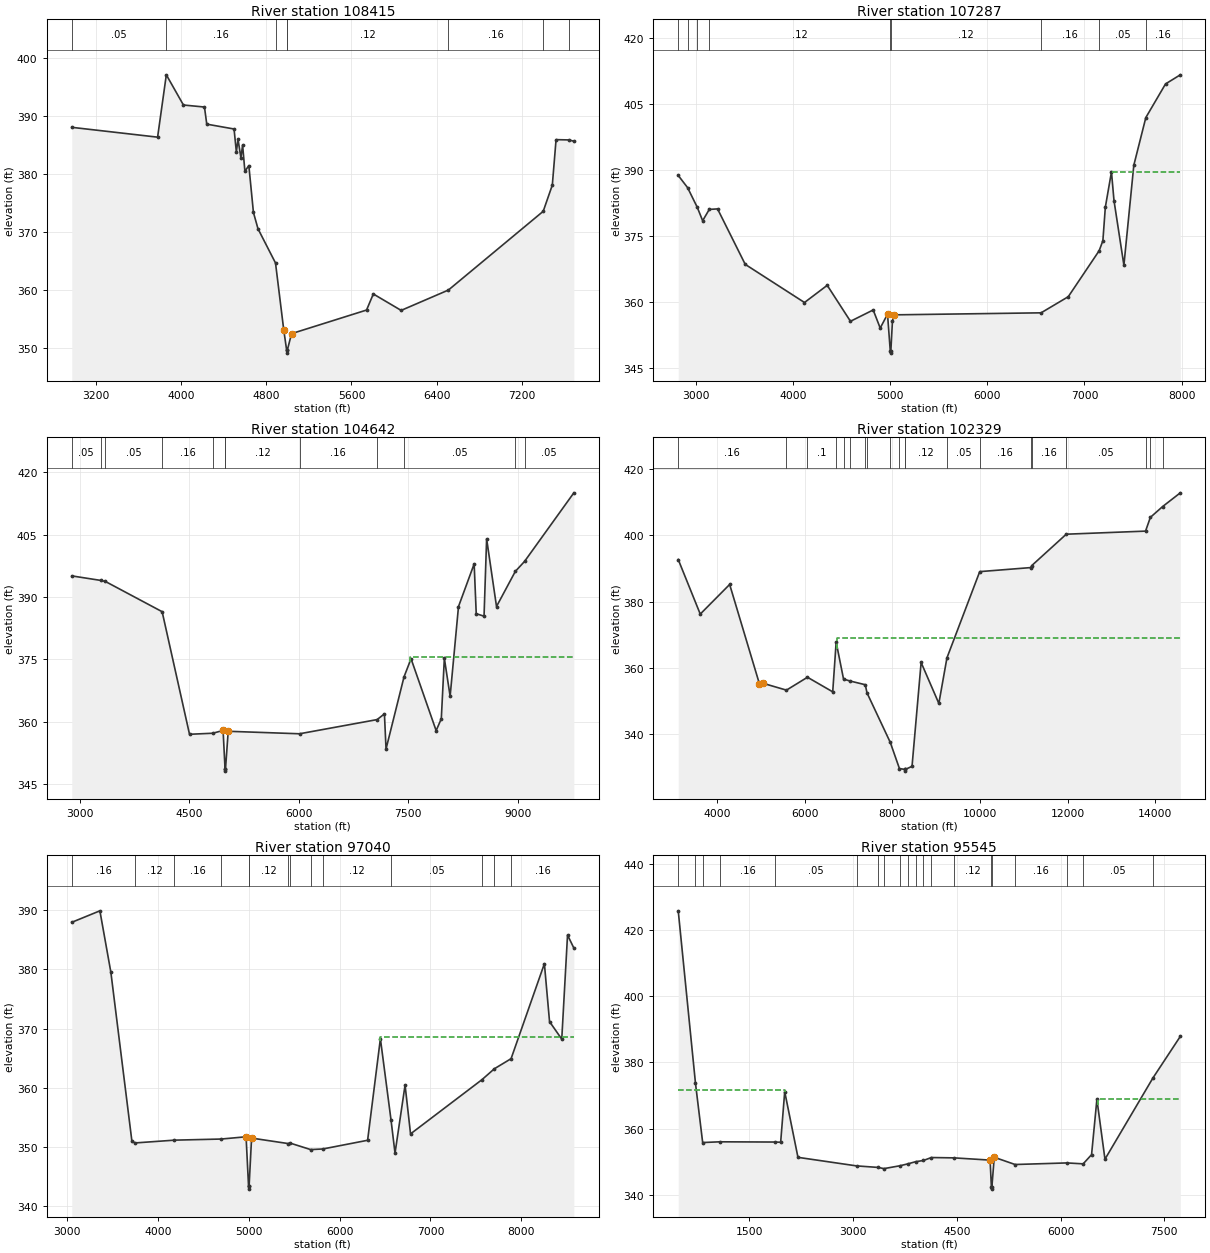
Type RM Length L Ch R = 1 ,108415  ,1128,1128,1128
BEGIN DESCRIPTION:
STEELE CREEK 64.0
END DESCRIPTION:
XS GIS Cut Line= 5
       3506956.1     10463635.31      3506708.71     10462867.11
      3506005.59     10461656.18        3504391.     10460028.57
      3504222.53     10459886.02
#Sta/Elev= 30
  2970.3  388.09  3777.3  386.39  3859.3  397.17  4020.1  391.95    4218   391.6
  4239.5  388.64  4496.2   387.8  4517.7  383.85  4533.4  386.01  4560.7  382.82
  4576.5  385.02    4598   380.5  4635.2  381.47  4678.3  373.37  4721.3  370.54
  4885.9  364.63  4963.2  353.08  4990.7  349.54  4993.5  349.04  4996.7  349.54
  5036.8  352.41  5741.9  356.49  5805.5  359.27  6067.2  356.43  6511.6  359.95
  7402.9  373.57  7488.5   378.1  7523.7  385.96  7647.8  385.91  7690.9  385.68
#Mann= 8 ,-1 , 0
  2970.3     .05       0  3859.3     .16       0  4885.9     .12       0
  4990.7     .07       0  4996.7     .12       0  6511.6     .16       0
  7402.9     .05       0  7647.8      .1       0
Bank Sta=4963.2,5036.8
XS Rating Curve= 0 ,0
Exp/Cntr=0.3,0.1

Type RM Length L Ch R = 1 ,107287  ,2645,2645,2645
BEGIN DESCRIPTION:
STEELE CREEK 57.0
END DESCRIPTION:
XS GIS Cut Line= 4
      3507400.44     10463607.16      3507530.65     10462999.49
      3506215.55     10459397.06      3506354.43     10458702.65
#Sta/Elev= 30
  2821.4  388.78  2917.7  386.01  3017.2  381.55  3072.5  378.51  3140.7  381.08
  3225.9  381.19  3510.6  368.61  4120.2  359.96    4354  363.86    4593   355.7
  4826.8  358.27    4899  354.16  4974.2  357.31  5002.5  348.98  5005.2  348.48
  5008.5  348.98  5024.7  355.69  5037.4  357.16  6553.8  357.62  6833.5  361.28
  7151.3  371.71  7189.5  373.97  7214.7  381.57  7277.8  389.58  7303.8  383.09
  7405.7  368.42  7507.7  391.09  7631.4  401.91  7834.1  409.54    7986   411.6
#Mann= 9 ,-1 , 0
  2821.4     .05       0  2917.7      .1       0  3017.2     .16       0
  3140.7     .12       0  5002.5     .07       0  5008.5     .12       0
  6553.8     .16       0  7151.3     .05       0  7631.4     .16       0
#XS Ineff= 2 , 0
                         7278.31          389.48
Permanent Ineff=
       F       F
Bank Sta=4974.2,5037.4
XS Rating Curve= 0 ,0
Exp/Cntr=0.3,0.1

Type RM Length L Ch R = 1 ,104642  ,2313,2313,2313
BEGIN DESCRIPTION:
STEELE CREEK 63.0
END DESCRIPTION:
XS GIS Cut Line= 4
      3508276.32     10464581.08      3508942.98     10463872.76
      3508922.14     10460956.09      3507130.49     10458560.27
#Sta/Elev= 30
    2888  395.08  3285.8  393.99  3347.6  393.75  4126.6  386.47  4501.8     357
  4820.9  357.25  4961.9  357.92  4988.9  348.64  4991.6  348.14  4994.9  348.64
  5031.9  357.72  6009.8  357.12  7072.8  360.53  7173.1   361.9  7195.1  353.47
  7441.9  370.82  7537.9  375.16  7881.8  357.88  7952.6  360.73  7994.3  375.26
  8073.5  366.15  8188.1   387.7  8402.8  397.96  8431.3  385.99  8538.3  385.39
  8573.7     404  8709.2  387.72  8967.1  396.16  9093.4  398.56  9769.1  415.05
#Mann= 12 ,-1 , 0
    2888     .05       0  3285.8     .16       0  3347.6     .05       0
  4126.6     .16       0  4820.9     .12       0  4988.9     .07       0
  4994.9     .12       0  6009.8     .16       0  7072.8     .12       0
  7441.9     .05       0  8967.1     .08       0  9093.4     .05       0
#XS Ineff= 2 , 0
                         7518.18          375.54
Permanent Ineff=
       F       F
Bank Sta=4961.9,5031.9
XS Rating Curve= 0 ,0
Exp/Cntr=0.3,0.1

Type RM Length L Ch R = 1 ,102329  ,5289,5289,5289
BEGIN DESCRIPTION:
STEELE CREEK 62.0
END DESCRIPTION:
XS GIS Cut Line= 4
      3508734.67     10465039.41      3509713.81     10464289.42
      3511838.81     10458539.42      3512338.81     10454476.94
#Sta/Elev= 30
  3115.6  392.71    3618  376.25  4288.9  385.19  4967.3  355.25 5038.64  355.42
  5584.8  353.31  6064.6   357.2  6640.7   352.8    6719   367.8  6887.6  356.65
  7028.4  356.09  7383.7  354.94  7422.5   352.5    7953  337.58  8162.7  329.67
  8288.2  329.38  8290.9  328.88  8294.2  329.38  8450.3  330.32  8657.9  361.65
  9062.4   349.3    9247  363.04  9995.2  389.06 11159.6  390.28 11182.9  390.89
 11970.1  400.35   13779  401.28 13889.1  405.43 14169.5   408.7 14572.2  412.83
#Mann= 20 ,-1 , 0
  3115.6     .16       0  5584.8     .12       0  6064.6      .1       0
    6719     .16       0  6887.6      .1       0  7028.4     .05       0
  7383.7     .16       0  7422.5     .05       0    7953      .1       0
  8162.7     .16       0  8288.2     .07       0  8294.2     .12       0
    9247     .05       0  9995.2     .16       0 11159.6     .05       0
 11182.9     .16       0 11970.1     .05       0   13779     .16       0
 13889.1      .1       0 14169.5     .05       0
#XS Ineff= 2 , 0
                         6748.86          368.94
Permanent Ineff=
       F       F
Bank Sta=4967.3,5038.64
XS Rating Curve= 0 ,0
Exp/Cntr=0.3,0.1

Type RM Length L Ch R = 1 ,97040   ,1495,1495,1495
BEGIN DESCRIPTION:
STEELE CREEK 60.0
END DESCRIPTION:
XS GIS Cut Line= 3
      3512547.15     10465039.42      3513047.14     10460247.76
      3513567.54     10459768.99
#Sta/Elev= 30
  3053.6  387.96    3363   389.9  3483.7  379.54  3714.9  351.04  3749.3   350.7
  4182.3  351.17  4698.4  351.36  4971.7  351.74  4998.9   343.4  5001.6   342.9
  5004.9   343.4  5032.1  351.52    5437  350.59  5453.3  350.69  5681.9  349.58
  5816.3  349.68    6309  351.15  6449.7  368.31  6566.8  354.56  6610.6  348.97
  6721.2  360.47  6781.5  352.23  7565.3  361.36  7704.1  363.23  7887.7  364.93
  8254.3  380.97    8311  371.19  8445.4  368.23  8508.9  385.81  8578.4  383.62
#Mann= 14 ,-1 , 0
  3053.6     .16       0  3749.3     .12       0  4182.3     .16       0
  4698.4     .12       0  4998.9     .07       0  5004.9     .12       0
    5437     .16       0  5453.3     .12       0  5681.9     .16       0
  5816.3     .12       0  6566.8     .05       0  7565.3      .1       0
  7704.1     .05       0  7887.7     .16       0
#XS Ineff= 2 , 0
                         6446.59          368.54
Permanent Ineff=
       F       F
Bank Sta=4971.7,5032.1
XS Rating Curve= 0 ,0
Exp/Cntr=0.3,0.1

Type RM Length L Ch R = 1 ,95545   ,4002,4002,4002
BEGIN DESCRIPTION:
STEELE CREEK 58.0
END DESCRIPTION:
XS GIS Cut Line= 3
      3516005.48     10466414.43      3513567.98     10461893.59
      3514380.18     10459935.98
#Sta/Elev= 30
   475.4  425.89   724.7  373.68   828.5  355.77  1076.1  355.99  1873.9  355.92
  1955.5  355.86  2014.1  371.16  2205.5  351.29  3052.8   348.7  3363.8  348.24
  3448.7  347.88  3676.6  348.73  3790.5   349.3  3904.4  349.96  4018.3  350.34
  4133.5  351.23  4459.6  351.13  4982.2  350.45  5001.1  342.17  5003.8  341.67
  5007.1  342.17  5042.2  351.31  5343.4  349.12  6092.4   349.6    6327  349.32
  6448.4   352.1  6525.5  368.83  6642.1  350.73  7334.3  375.28  7730.9  387.89
#Mann= 20 ,-1 , 0
   475.4     .05       0   724.7      .1       0   828.5     .05       0
  1076.1     .16       0  1873.9     .05       0  3052.8     .16       0
  3363.8     .16       0  3448.7     .05       0  3676.6     .16       0
  3790.5     .05       0  3904.4     .16       0  4018.3      .1       0
  4133.5      .1       0  4459.6     .12       0  5001.1     .07       0
  5007.1     .12       0  5343.4     .16       0  6092.4     .12       0
    6327     .05       0  7334.3     .05       0
#XS Ineff= 2 , 0
         2013.64  371.54 6536.36          368.91
Permanent Ineff=
       F       F
Bank Sta=4982.2,5042.2
XS Rating Curve= 0 ,0
Exp/Cntr=0.3,0.1