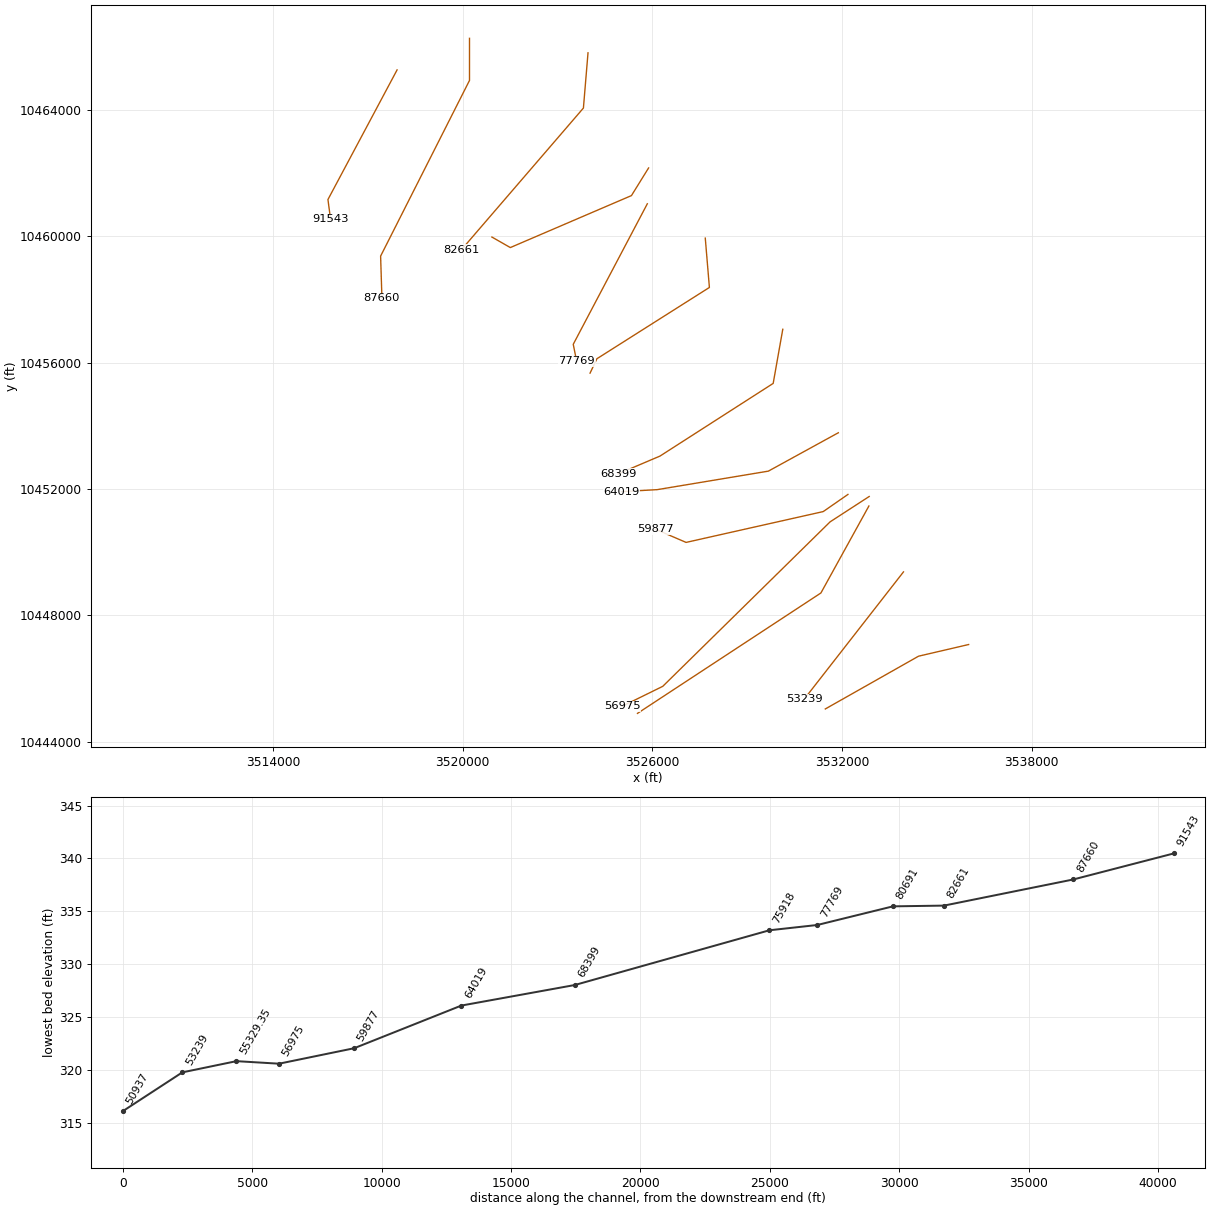
HEC-RAS study STEELE CREEK.prj: STEELE CREEK Base Level Engineering

--- STEELE CREEK.g01 (geometry) --- (continued)

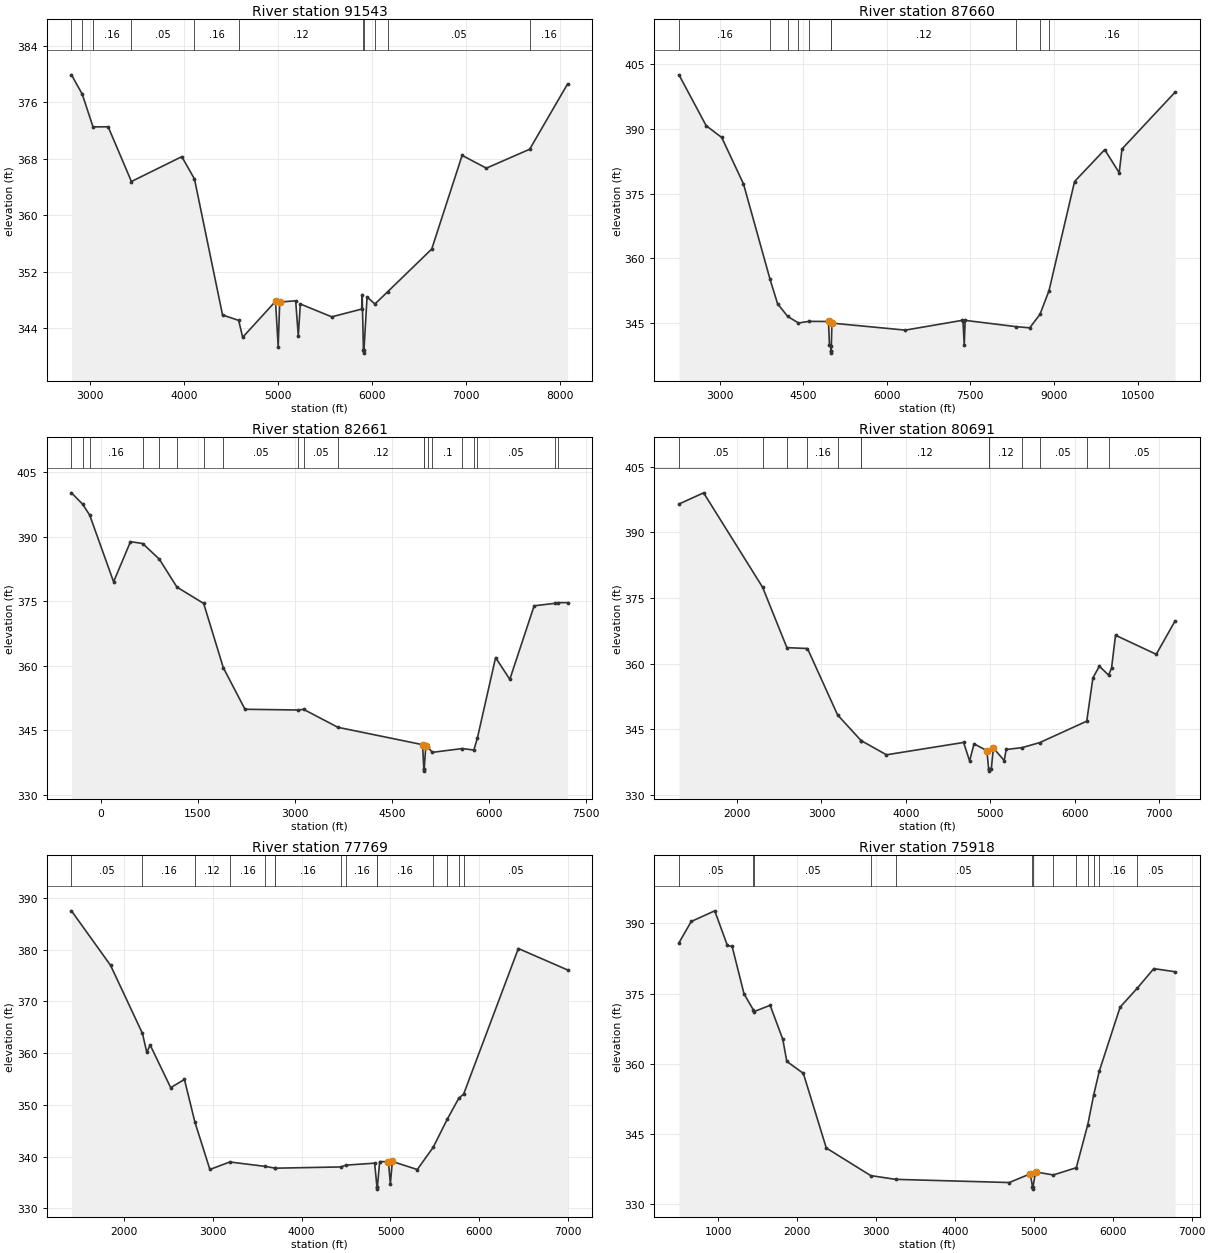
Type RM Length L Ch R = 1 ,91543   ,3883,3883,3883
BEGIN DESCRIPTION:
STEELE CREEK 55.0
END DESCRIPTION:
XS GIS Cut Line= 3
      3517922.16     10465268.62      3515734.64     10461164.42
      3515817.98     10460539.42
#Sta/Elev= 30
  2803.5   379.9  2918.3  377.16  3032.7  372.53    3194  372.54  3441.6  364.79
  3978.2  368.31  4112.9  365.15  4411.8  345.88  4583.5  345.12  4625.8  342.72
  4975.8  347.82  5004.1  341.39  5020.4  347.72  5190.4  347.89    5218  342.93
    5240  347.44  5574.4  345.62  5892.5  346.72  5898.2  348.77  5911.5  340.98
  5914.2  340.48  5917.5  340.98  5950.3  348.43  6033.8  347.44  6171.6   349.2
  6638.5  355.22  6962.3  368.49  7220.1  366.68  7681.3  369.36  8084.8  378.61
#Mann= 11 ,-1 , 0
  2803.5     .05       0  2918.3      .1       0  3032.7     .16       0
  3441.6     .05       0  4112.9     .16       0  4583.5     .12       0
  5911.5     .07       0  5917.5     .12       0  6033.8     .16       0
  6171.6     .05       0  7681.3     .16       0
Bank Sta=4975.8,5020.4
XS Rating Curve= 0 ,0
Exp/Cntr=0.3,0.1

Type RM Length L Ch R = 1 ,87660   ,4999,4999,4999
BEGIN DESCRIPTION:
STEELE CREEK 49.0
END DESCRIPTION:
XS GIS Cut Line= 4
      3520213.81     10466268.54      3520213.81     10464935.26
      3517401.31     10459372.76      3517442.98      10458039.4
#Sta/Elev= 30
  2271.9  402.59  2758.8   390.8  3038.8  388.05  3428.8  377.29  3905.8  355.14
  4040.9  349.46  4223.1  346.53  4415.4  345.01  4601.7  345.39  4954.6  345.36
  4971.3  339.84  4992.9  339.78  4996.2  338.52    4999  338.02  5002.2  338.52
  5015.9  344.98  6332.2  343.36  7351.9  345.62  7367.1  345.42  7389.4  339.87
  7406.1  345.62  8321.9  344.16    8565  343.89  8748.6  347.03  8909.9   352.5
  9368.9  377.84  9909.4  385.23 10169.6  379.87 10219.6  385.39 11172.3  398.57
#Mann= 11 ,-1 , 0
  2271.9     .16       0  3905.8     .05       0  4223.1      .1       0
  4415.4     .05       0  4601.7      .1       0  4992.9     .12       0
  4996.2     .07       0  5002.2     .12       0  8321.9     .16       0
  8748.6     .12       0  8909.9     .16       0
Bank Sta=4954.6,5015.9
XS Rating Curve= 0 ,0
Exp/Cntr=0.3,0.1

Type RM Length L Ch R = 1 ,82661   ,1970,1970,1970
BEGIN DESCRIPTION:
STEELE CREEK 47.0
END DESCRIPTION:
XS GIS Cut Line= 3
      3523963.81     10465810.23      3523817.98     10464060.26
      3519963.84     10459581.12
#Sta/Elev= 30
  -453.3  400.24  -282.1  397.62  -172.2  395.08   197.5  379.55   458.4  388.89
   647.8  388.45   903.5  384.83  1176.5  378.32  1589.1  374.53  1892.6   359.6
  2227.5  349.93  3041.4  349.76  3134.4   349.9  3662.3  345.74  4971.7   341.7
  4990.6  336.05  4993.4  335.55  4996.6  336.05  5021.2  341.33  5050.1  341.13
  5123.9  339.92  5586.2   340.8  5763.7  340.45  5817.6  343.19  6099.6  361.94
  6319.1  356.88  6695.4  373.98  7013.3  374.55  7060.6  374.71  7211.8  374.71
#Mann= 20 ,-1 , 0
  -453.3     .16       0  -282.1      .1       0  -172.2     .16       0
   647.8      .1       0   903.5     .16       0  1176.5     .05       0
  1589.1     .16       0  1892.6     .05       0  3041.4     .16       0
  3134.4     .05       0  3662.3     .12       0  4990.6     .07       0
  4996.6     .12       0  5050.1     .16       0  5123.9      .1       0
  5586.2     .05       0  5763.7     .16       0  5817.6     .05       0
  7013.3      .1       0  7060.6     .05       0
Bank Sta=4971.7,5021.2
XS Rating Curve= 0 ,0
Exp/Cntr=0.3,0.1

Type RM Length L Ch R = 1 ,80691   ,2922,2922,2922
BEGIN DESCRIPTION:
STEELE CREEK 43.0
END DESCRIPTION:
XS GIS Cut Line= 4
      3525880.49     10462164.44      3525338.81     10461289.42
      3521505.48     10459643.59      3520922.39     10459976.78
#Sta/Elev= 30
  1313.8  396.47  1605.2  399.03  2303.4  377.47  2591.1  363.68  2834.7  363.48
  3191.1  348.32  3469.4  342.45  3469.5  342.45  3769.9  339.21  4683.2  342.03
  4753.9   337.8  4806.4  341.71  4958.7  340.15  4979.2  335.98    4982  335.48
  4985.2  335.98  5011.2  336.07  5034.8  340.76  5163.4   337.9    5187  340.42
  5373.3  340.84  5584.8     342  6140.3  346.89  6213.6  356.79  6289.8  359.44
  6398.8  357.41  6433.8  358.98  6480.9  366.51  6963.1  362.16  7186.2  369.78
#Mann= 13 ,-1 , 0
  1313.8     .05       0  2303.4     .16       0  2591.1     .05       0
  2834.7     .16       0  3191.1     .12       0  3469.4     .16       0
  3469.5     .12       0  4979.2     .07       0  4985.2     .12       0
  5373.3     .16       0  5584.8     .05       0  6140.3      .1       0
  6398.8     .05       0
Bank Sta=4958.7,5034.8
XS Rating Curve= 0 ,0
Exp/Cntr=0.3,0.1

Type RM Length L Ch R = 1 ,77769   ,1851,1851,1851
BEGIN DESCRIPTION:
STEELE CREEK 42.0
END DESCRIPTION:
XS GIS Cut Line= 3
      3525840.27     10461029.48      3523496.51     10456580.67
      3523605.01     10456038.14
#Sta/Elev= 30
  1411.1  387.53    1851  376.98  2209.9  363.82  2258.3  360.17  2296.7  361.58
  2527.6  353.34    2682  354.93  2800.1  346.66  2968.4  337.52  3192.1  338.97
  3593.1  338.11  3702.7  337.78  3705.9  337.77    4442  338.01  4498.6  338.36
  4822.1  338.74  4847.5  334.22  4850.2  333.72  4853.5  334.22  4878.6  339.04
    4977  339.03  4999.1  334.74  5021.1  339.07  5301.8  337.51  5480.2  341.79
  5640.7  347.29  5768.5  351.28  5823.4   352.1  6438.9  380.24  6992.8   376.1
#Mann= 15 ,-1 , 0
  1411.1     .05       0  2209.9     .16       0  2800.1     .12       0
  3192.1     .16       0  3593.1      .1       0  3702.7     .05       0
  3705.9     .16       0    4442     .05       0  4498.6     .16       0
  4847.5     .07       0  4853.5     .16       0  5480.2     .16       0
  5640.7     .05       0  5768.5     .16       0  5823.4     .05       0
Bank Sta=4977,5021.1
XS Rating Curve= 0 ,0
Exp/Cntr=0.3,0.1

Type RM Length L Ch R = 1 ,75918   ,7519,7519,7519
BEGIN DESCRIPTION:
STEELE CREEK 41.0
END DESCRIPTION:
XS GIS Cut Line= 4
      3527674.39     10459942.94       3527804.6     10458380.44
      3524245.57     10456123.49      3524028.55     10455667.76
#Sta/Elev= 30
   503.3  385.88   658.3  390.42   956.2   392.7  1116.7   385.3  1176.9  385.09
  1327.4  374.96  1444.3  371.56  1457.4  371.18  1658.6  372.51  1819.1  365.22
  1869.3  360.52  2079.2  357.96  2370.2  342.01    2933  336.11  3248.8  335.31
  4688.8  334.63  4955.7   336.5  4983.2  333.72    4986  333.22  4989.2  333.72
  5022.6   336.9  5246.8  336.25  5538.1   337.8    5684  347.02    5759  353.37
  5829.5  358.44  6093.6  372.12  6311.8  376.18  6520.2  380.35  6790.3  379.68
#Mann= 13 ,-1 , 0
   503.3     .05       0  1444.3      .1       0  1457.4     .05       0
    2933     .12       0  3248.8     .05       0  4983.2     .07       0
  4989.2     .05       0  5246.8     .12       0  5538.1     .05       0
    5684     .16       0    5759     .05       0  5829.5     .16       0
  6311.8     .05       0
Bank Sta=4955.7,5022.6
XS Rating Curve= 0 ,0
Exp/Cntr=0.3,0.1

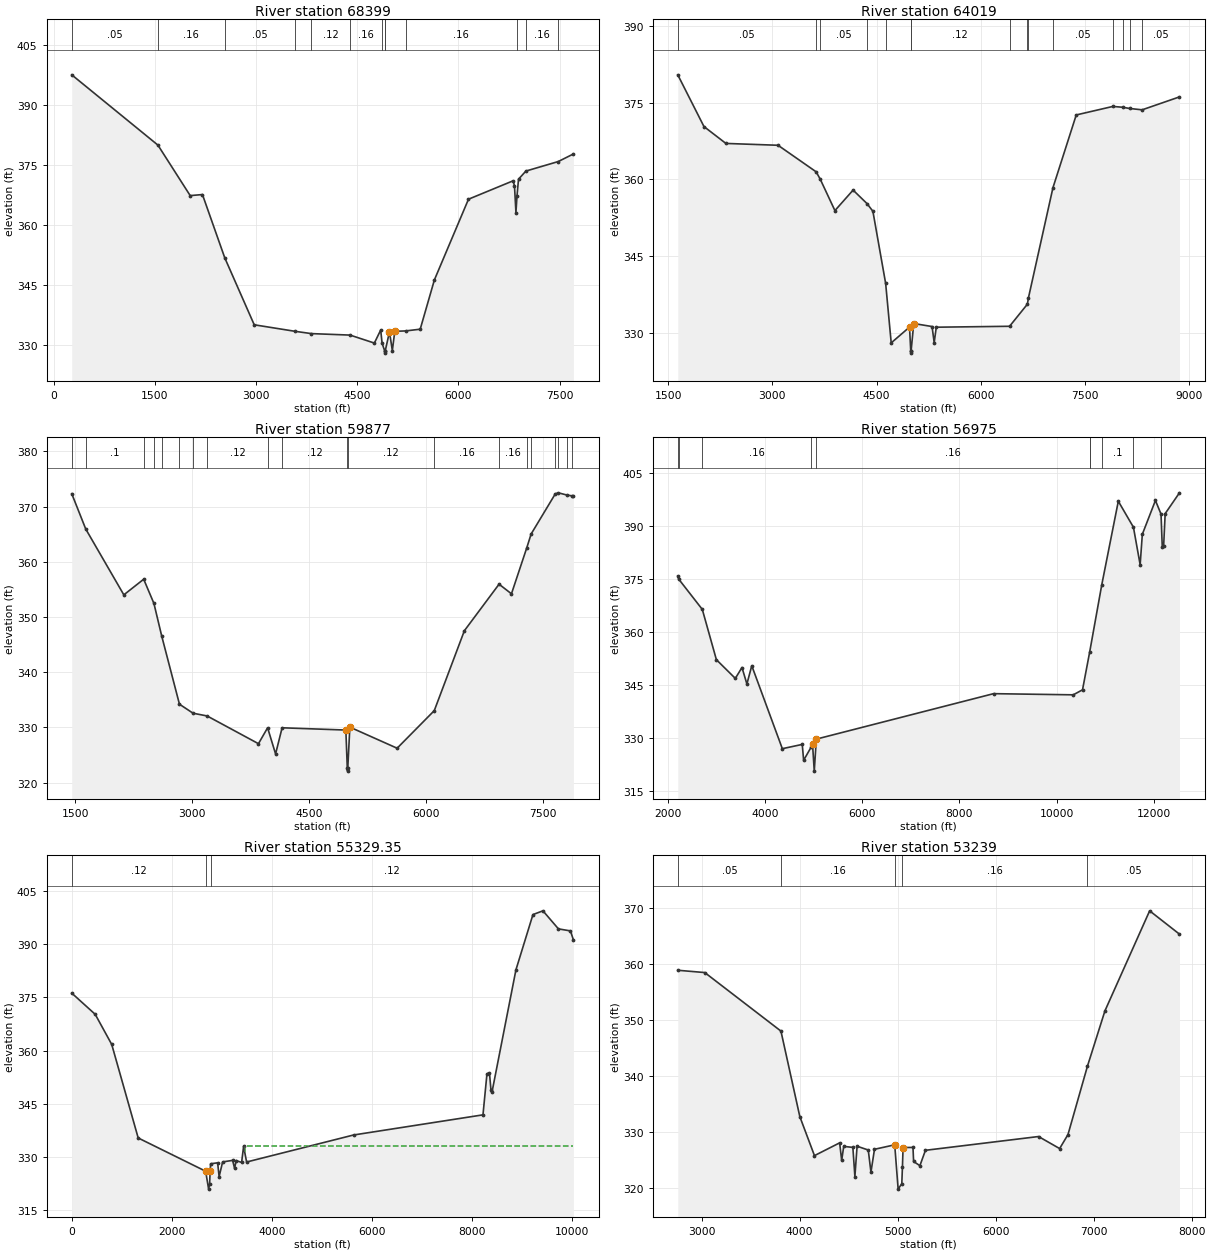
Type RM Length L Ch R = 1 ,68399   ,4380,4380,4380
BEGIN DESCRIPTION:
STEELE CREEK 40.0
END DESCRIPTION:
XS GIS Cut Line= 4
      3530126.64     10457056.62      3529822.82     10455342.24
       3526242.1      10453041.9      3524918.28     10452477.65
#Sta/Elev= 30
   269.4  397.48  1546.3  379.95    2025  367.35  2206.7  367.61  2537.8  351.81
  2974.1  335.12  3580.5  333.49  3821.3  332.92  4394.8  332.55    4755  330.56
  4848.8  333.81  4869.6   330.5  4909.2  328.55    4912  328.05  4915.2  328.55
    4979  333.38  5021.2  328.69  5057.6  333.49  5219.1  333.59  5434.4  334.02
  5644.8  346.32  6150.1  366.45    6810  371.03  6831.7  369.86  6853.4  363.13
  6869.2  367.26  6891.7  371.45  7001.1  373.47  7479.7  375.84  7705.5  377.74
#Mann= 13 ,-1 , 0
   269.4     .05       0  1546.3     .16       0  2537.8     .05       0
  3580.5      .1       0  3821.3     .12       0  4394.8     .16       0
  4869.6     .12       0  4909.2     .07       0  4915.2     .12       0
  5219.1     .16       0  6869.2     .05       0  7001.1     .16       0
  7479.7     .05       0
Bank Sta=4979,5057.6
XS Rating Curve= 0 ,0
Exp/Cntr=0.3,0.1

Type RM Length L Ch R = 1 ,64019   ,4142,4142,4142
BEGIN DESCRIPTION:
STEELE CREEK 39.0
END DESCRIPTION:
XS GIS Cut Line= 4
      3531884.47     10453779.75      3529670.92     10452564.47
      3526155.29     10451978.53      3525027.01     10451913.44
#Sta/Elev= 30
  1639.1  380.43  2016.1  370.33  2331.6  367.04  3082.1  366.68  3630.2   361.5
  3688.9  360.07  3900.6  353.93  4162.1  357.93  4361.5  355.31    4447   353.8
  4630.7  339.71  4710.6  328.11  4974.1  331.19  4991.4  326.61  4994.2  326.11
  4997.4  326.61    5035  331.89  5298.6   331.3    5329  328.16  5359.4  331.17
  6414.2  331.35  6670.1  335.66  6686.2  336.94  7038.3   358.4  7373.4   372.6
  7900.3  374.26  8042.4   374.1  8142.7  373.86  8321.8   373.6  8858.6  376.12
#Mann= 15 ,-1 , 0
  1639.1     .05       0  3630.2     .16       0  3688.9     .05       0
  4361.5     .16       0  4630.7     .12       0  4991.4     .07       0
  4997.4     .12       0  6414.2     .16       0  6670.1     .05       0
  6686.2     .16       0  7038.3     .05       0  7900.3      .1       0
  8042.4     .16       0  8142.7      .1       0  8321.8     .05       0
Bank Sta=4974.1,5035
XS Rating Curve= 0 ,0
Exp/Cntr=0.3,0.1

Type RM Length L Ch R = 1 ,59877   ,2902,2902,2902
BEGIN DESCRIPTION:
STEELE CREEK 36.0
END DESCRIPTION:
XS GIS Cut Line= 4
      3532188.31     10451826.64      3531407.03     10451284.08
      3527066.75     10450307.52      3526111.85     10450719.86
#Sta/Elev= 30
    1454  372.33  1633.7  365.93  2122.6  354.01  2377.5  356.84  2508.8  352.46
  2609.2  346.53  2836.7   334.2  3011.3  332.57  3192.3  332.07  3850.8  327.05
  3968.2  329.93  4070.7  325.19  4154.4  329.93  4972.7  329.52  4991.3  322.58
    4994  322.08  4997.3  322.58    5024  330.05  5630.9  326.23  6107.9  333.04
  6494.2  347.51  6939.4  355.94  7098.6   354.2    7295  362.52  7351.1  365.03
  7661.7  372.31  7700.7  372.49  7810.2  372.09  7871.2  371.95  7894.1  371.95
#Mann= 20 ,-1 , 0
    1454     .05       0  1633.7      .1       0  2377.5     .05       0
  2508.8      .1       0  2609.2     .16       0  2836.7     .12       0
  3011.3     .16       0  3192.3     .12       0  3968.2     .16       0
  4154.4     .12       0  4991.3     .07       0  4997.3     .12       0
  6107.9     .16       0  6939.4     .16       0    7295     .05       0
  7351.1     .16       0  7661.7     .05       0  7700.7     .16       0
  7810.2      .1       0  7871.2     .16       0
Bank Sta=4972.7,5024
XS Rating Curve= 0 ,0
Exp/Cntr=0.3,0.1

Type RM Length L Ch R = 1 ,56975   ,1646,1646,1646
BEGIN DESCRIPTION:
STEELE CREEK 35.0
END DESCRIPTION:
XS GIS Cut Line= 4
        3532861.      10451761.5      3531624.04     10450958.56
       3526328.9     10445750.23      3525048.55      10445120.9
#Sta/Elev= 30
  2201.7  375.82  2218.9  374.99  2706.8  366.38  2996.8  352.15  3386.4  346.86
  3523.7  349.94    3625  345.27  3725.1  350.45  4354.4  326.97  4764.6  328.18
  4792.9  323.69  4948.4  327.43  4976.7  328.18  5011.8  320.62  5054.5  329.68
  8703.3  342.54 10343.8  342.21 10534.8  343.63 10682.8  354.37 10931.6  373.39
 11271.7  396.99 11583.2  389.63 11721.3  379.03 11766.2  387.64   12036  397.21
 12151.1  393.36 12176.4  384.16 12204.4  384.21 12236.7  393.49 12530.4  399.37
#Mann= 10 ,-1 , 0
  2201.7      .1       0  2218.9     .05       0  2706.8     .16       0
  4948.4     .12       0  5054.5     .16       0 10682.8     .12       0
 10682.8     .05       0 10931.6      .1       0 11583.2     .05       0
 12151.1      .1       0
Bank Sta=4976.7,5054.5
XS Rating Curve= 0 ,0
Exp/Cntr=0.3,0.1

Type RM Length L Ch R = 1 ,55329.35,2090,2090,2090
XS GIS Cut Line= 3
     3532851.688    10451460.606     3531333.459    10448706.613
     3525528.771    10444894.113
#Sta/Elev= 30
       0  376.23  469.56  370.23  799.25  361.74 1328.75  335.31 2677.48  325.92
 2737.42  320.86  2757.4  322.44 2767.39     326 2777.38  328.01 2917.25   328.3
 2947.22  324.39 3017.16  328.55 3216.99  328.98 3256.97  326.71 3286.95  328.94
 3396.87   328.4 3436.84  332.95  3496.8  328.52 5635.36  336.15 8223.62  341.84
 8303.57  353.46 8353.54  353.65 8383.52  348.87  8403.5  348.23 8883.18  382.82
 9222.95  398.41 9422.82  399.47 9732.61  394.37 9972.45   393.810032.41  391.26
#Mann= 3 ,-1 , 0
       0     .12       0 2677.48     .07       0 2777.38     .12       0
#XS Ineff= 2 , 0
       0                 3456.82       0  332.92
Permanent Ineff=
       F       T
Bank Sta=2677.48,2767.39
XS Rating Curve= 0 ,0
Exp/Cntr=0.3,0.1

Type RM Length L Ch R = 1 ,53239   ,2302,2302,2302
BEGIN DESCRIPTION:
STEELE CREEK 34.0
END DESCRIPTION:
XS GIS Cut Line= 2
      3533946.09     10449374.37      3530799.38     10445337.89
#Sta/Elev= 30
  2757.6  358.87  3033.1  358.46  3810.1  348.01  4002.8  332.74  4152.1  325.78
    4409  328.06  4429.8  324.92  4450.6  327.43  4543.8  327.25  4564.6  322.05
  4586.9  327.46    4701  326.78  4728.4  322.83  4764.4  326.91  4970.8  327.71
  5005.8   319.8  5043.2  320.78  5049.5   323.7  5056.1  327.23  5157.2  327.24
  5163.5  324.74  5227.7  323.98  5284.3  326.73  6438.2  329.19  6653.4  327.04
  6738.5  329.54  6937.5  341.77  7115.7  351.63  7571.7  369.48  7875.7  365.32
#Mann= 5 ,-1 , 0
  2757.6     .05       0  3810.1     .16       0  4970.8     .12       0
  5049.5     .16       0  6937.5     .05       0
Bank Sta=4970.8,5056.1
XS Rating Curve= 0 ,0
Exp/Cntr=0.3,0.1

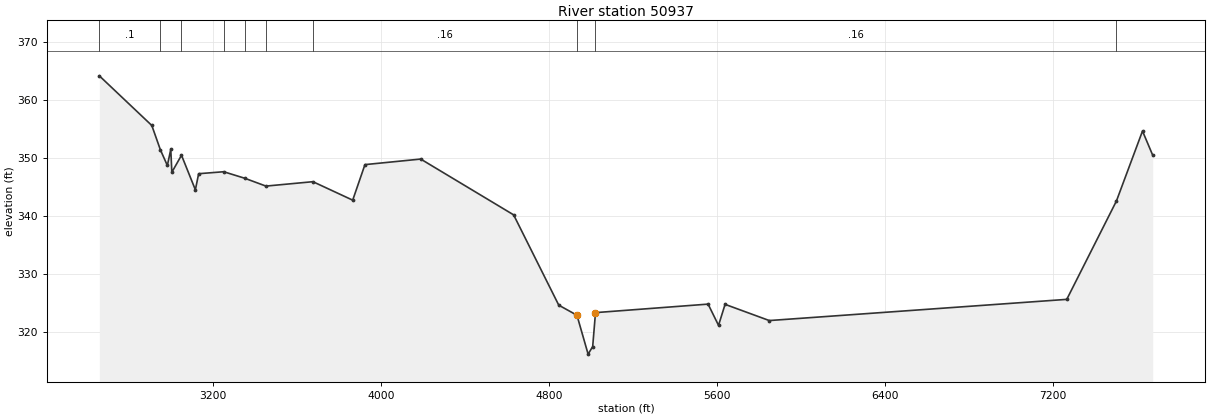
Type RM Length L Ch R = 1 ,50937   ,2798,2798,2798
BEGIN DESCRIPTION:
STEELE CREEK 32.0
END DESCRIPTION:
XS GIS Cut Line= 3
      3536007.68     10447074.01      3534423.52     10446705.09
      3531472.09     10445034.06
#Sta/Elev= 30
  2658.5  364.21  2908.5  355.63  2949.3  351.43  2982.5  348.72  2998.8  351.49
  3003.9  347.55  3049.9  350.49    3116  344.52  3131.6   347.3    3251  347.64
  3351.6  346.51  3452.1  345.16    3676  345.92  3865.5  342.73  3923.8  348.87
  4189.5  349.83  4632.1  340.19  4847.1  324.59  4933.7  322.85  4986.9  316.13
  5008.7  317.43  5022.1   323.3  5558.5  324.77  5608.2   321.1  5639.4  324.73
    5850  321.93  7267.1  325.59  7503.8  342.59  7627.9  354.67  7676.7  350.48
#Mann= 10 ,-1 , 0
  2658.5      .1       0  2949.3     .16       0  3049.9     .05       0
    3251      .1       0  3351.6     .05       0  3452.1      .1       0
    3676     .16       0  4933.7     .12       0  5022.1     .16       0
  7503.8     .05       0
Bank Sta=4933.7,5022.1
XS Rating Curve= 0 ,0
Exp/Cntr=0.3,0.1