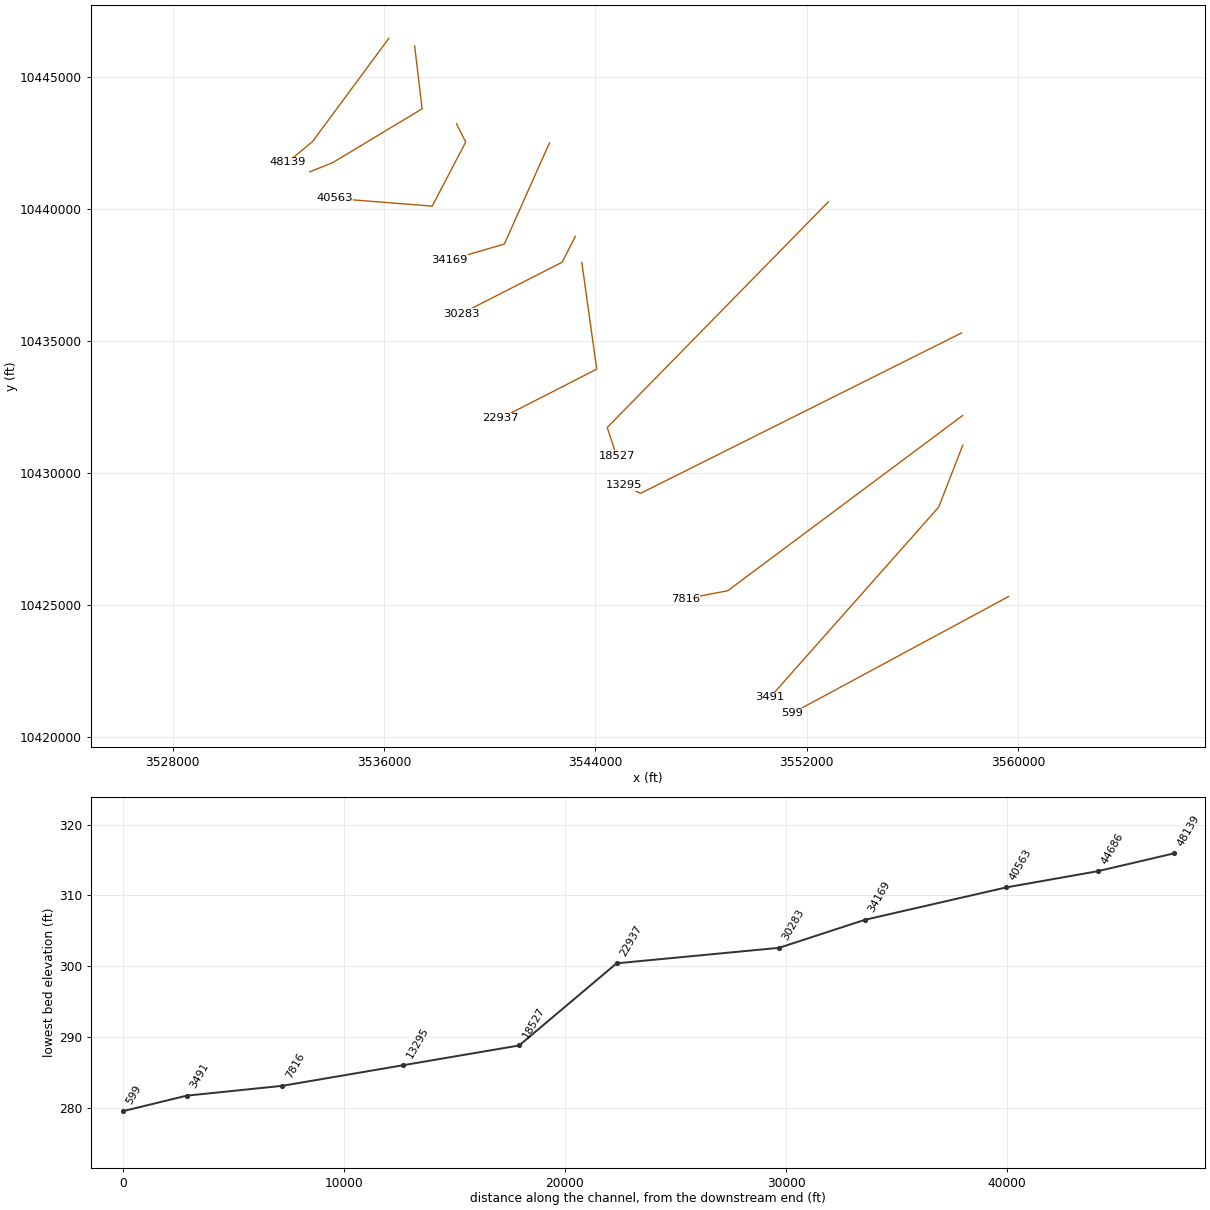
HEC-RAS study STEELE CREEK.prj: STEELE CREEK Base Level Engineering

--- STEELE CREEK.g01 (geometry) --- (continued)

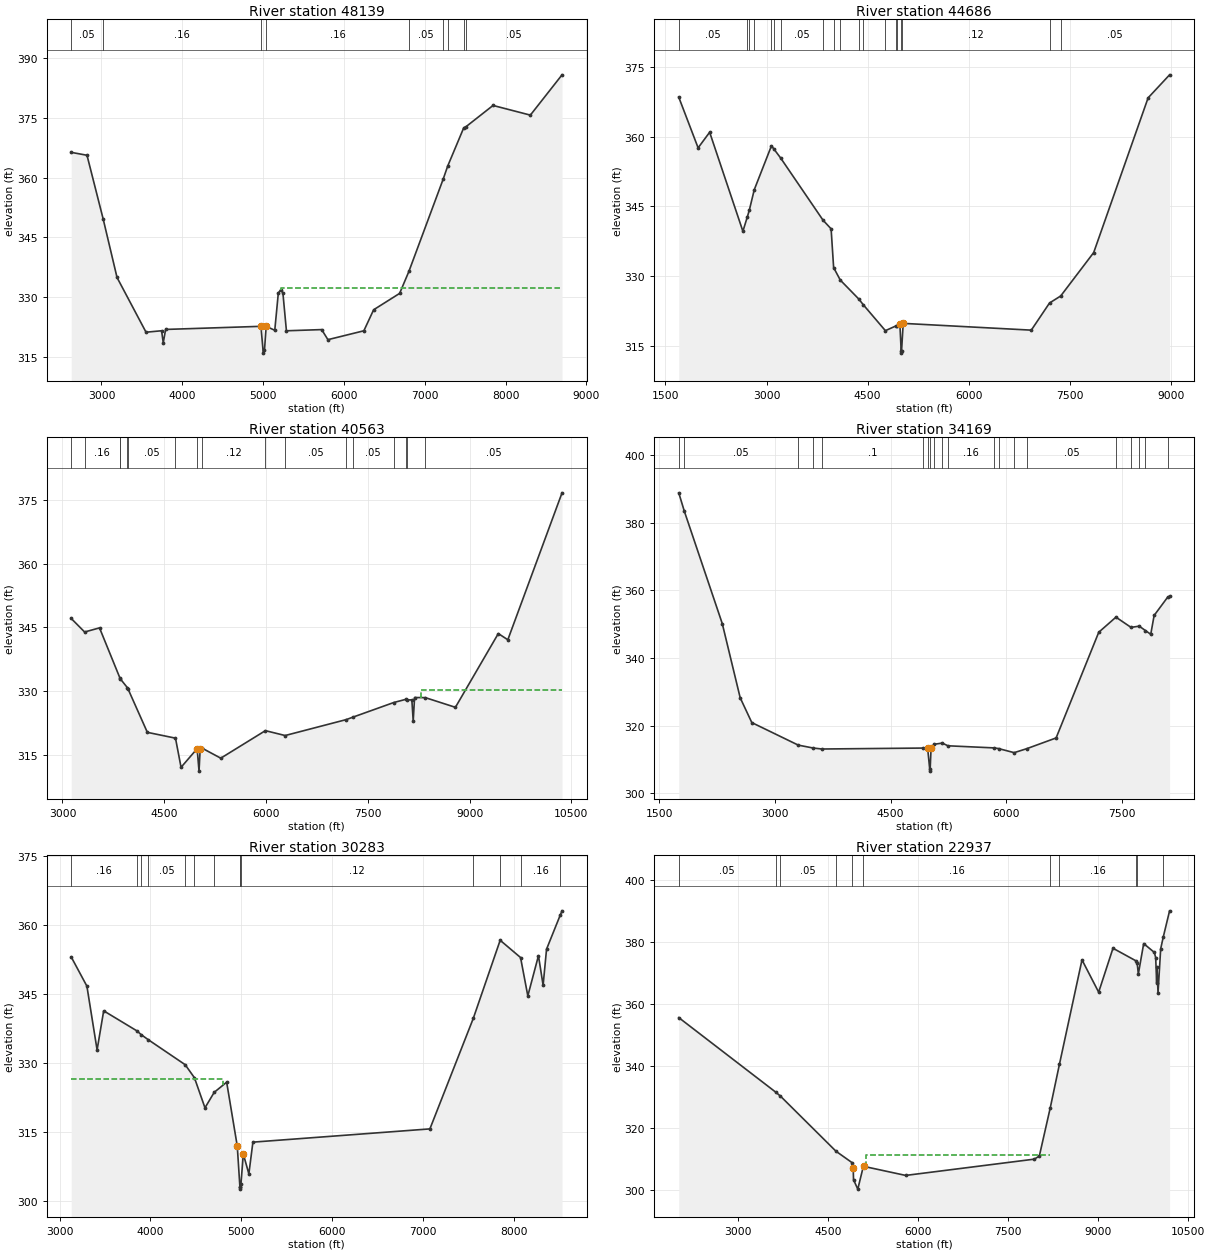
Type RM Length L Ch R = 1 ,48139   ,3453,3453,3453
BEGIN DESCRIPTION:
STEELE CREEK 29.0
END DESCRIPTION:
XS GIS Cut Line= 3
      3536181.33     10446466.38      3533295.05     10442560.13
       3532361.9     10441778.89
#Sta/Elev= 30
  2625.4  366.34  2820.8  365.61  3021.2  349.58  3192.4  334.92  3551.4  321.17
  3743.6  321.54  3764.5  318.52  3793.7  321.87  4973.3  322.65  5002.3  315.92
  5017.2  316.68    5038  322.64  5144.5  321.66  5188.3  331.01  5217.5  331.79
  5244.7   331.1  5288.6  321.53  5724.9  321.83  5802.1   319.3  6246.8  321.53
  6367.9  326.81  6689.4  330.92  6804.3  336.45  7226.9  359.53  7284.5   362.9
  7483.1  372.52  7508.7  372.75  7845.4  378.12  8307.3  375.69  8699.3  385.81
#Mann= 9 ,-1 , 0
  2625.4     .05       0  3021.2     .16       0  4973.3     .12       0
    5038     .16       0  6804.3     .05       0  7226.9     .16       0
  7284.5     .05       0  7483.1     .16       0  7508.7     .05       0
#XS Ineff= 2 , 0
                         5221.59          332.23
Permanent Ineff=
       F       F
Bank Sta=4973.3,5038
XS Rating Curve= 0 ,0
Exp/Cntr=0.3,0.1

Type RM Length L Ch R = 1 ,44686   ,4123,4123,4123
BEGIN DESCRIPTION:
STEELE CREEK 24.0
END DESCRIPTION:
XS GIS Cut Line= 4
       3537157.4      10446176.9      3537440.01      10443797.1
       3534054.6     10441757.17      3533186.78     10441410.05
#Sta/Elev= 30
  1697.7  368.54    1985  357.62  2156.2  360.98  2649.6  339.65  2715.3  342.73
  2746.7   344.3  2818.3   348.6  3073.6  358.07  3113.7  357.29    3209  355.45
  3838.6  342.04  3958.7  340.17    3996  331.83  4094.5  329.14  4370.3  325.04
  4433.8  323.86    4764  318.24  4925.6  319.29  4938.2  319.35  4979.1  319.71
  4998.2   313.9  5000.9   313.4  5004.2   313.9  5028.4  319.81  6929.3  318.35
  7199.9   324.2  7365.6  325.71  7855.5  335.07  8662.7  368.39  8981.4  373.35
#Mann= 19 ,-1 , 0
  1697.7     .05       0  2715.3     .16       0  2746.7     .05       0
  2818.3     .16       0  3073.6     .05       0  3113.7     .16       0
    3209     .05       0  3838.6      .1       0    3996     .08       0
  4094.5     .05       0  4370.3      .1       0  4433.8     .05       0
    4764     .12       0  4925.6     .05       0  4938.2     .12       0
  4998.2     .07       0  5004.2     .12       0  7199.9     .16       0
  7365.6     .05       0
Bank Sta=4979.1,5028.4
XS Rating Curve= 0 ,0
Exp/Cntr=0.3,0.1

Type RM Length L Ch R = 1 ,40563   ,6394,6394,6394
BEGIN DESCRIPTION:
STEELE CREEK 23.0
END DESCRIPTION:
XS GIS Cut Line= 4
      3538742.08     10443232.91      3539089.32     10442538.42
      3537822.82     10440111.34      3534115.78     10440402.91
#Sta/Elev= 30
  3129.2   347.1  3326.9  343.91  3546.4  344.88  3844.3  333.17  3853.3  332.86
  3956.4   330.8  3963.7  330.59  4251.2  320.26  4665.8  318.89  4747.9  312.02
  4984.9  316.41  5012.7  311.12  5029.4  316.36  5051.5  316.59    5333  314.17
  5990.8  320.66  6281.6  319.51  7183.4  323.27  7274.9  323.81  7882.4  327.29
  8065.1  328.06  8083.5  327.91  8148.7  327.91  8168.7  322.92  8188.8  328.47
  8347.4  328.44  8790.6  326.16  9422.6  343.54    9563  342.08 10361.8  376.71
#Mann= 17 ,-1 , 0
  3129.2     .05       0  3326.9     .16       0  3844.3      .1       0
  3853.3     .05       0  3956.4      .1       0  3963.7     .05       0
  4665.8     .12       0  4984.9     .07       0  5051.5     .12       0
  5990.8     .16       0  6281.6     .05       0  7183.4     .16       0
  7274.9     .05       0  7882.4     .16       0  8065.1      .1       0
  8083.5     .16       0  8347.4     .05       0
#XS Ineff= 2 , 0
                         8277.27          330.15
Permanent Ineff=
       F       F
Bank Sta=4984.9,5029.4
XS Rating Curve= 0 ,0
Exp/Cntr=0.3,0.1

Type RM Length L Ch R = 1 ,34169   ,3886,3886,3886
BEGIN DESCRIPTION:
STEELE CREEK 20.0
END DESCRIPTION:
XS GIS Cut Line= 3
      3542260.32     10442507.17      3540551.99     10438673.84
      3538468.69     10438069.68
#Sta/Elev= 30
  1752.4  388.82  1825.1  383.36  2316.8  350.16  2549.3  328.22    2700  320.89
  3302.3  314.23  3495.6  313.37  3609.3  313.08  4915.4  313.36  4980.6  313.32
  5009.8  306.54    5013  307.04  5024.8  313.37  5064.8  314.48  5170.4  314.83
  5243.6  314.03  5839.5  313.41  5899.8  313.21  6102.6     312  6266.4  313.18
  6646.6  316.35  7199.7   347.6  7422.7  352.06  7618.2  349.04  7724.9   349.4
  7804.9   348.1    7874     347    7918  352.57  8094.6  358.01  8118.3  358.22
#Mann= 20 ,-1 , 0
  1752.4      .1       0  1825.1     .05       0  3302.3      .1       0
  3495.6     .05       0  3609.3      .1       0  4915.4     .12       0
  4980.6     .07       0    5013     .12       0  5064.8     .05       0
  5170.4     .05       0  5243.6     .16       0  5839.5     .16       0
  5899.8      .1       0  6102.6     .16       0  6266.4     .05       0
  7422.7     .05       0  7618.2      .1       0  7724.9     .05       0
  7804.9      .1       0  8094.6      .1       0
Bank Sta=4980.6,5024.8
XS Rating Curve= 0 ,0
Exp/Cntr=0.3,0.1

Type RM Length L Ch R = 1 ,30283   ,7346,7346,7346
BEGIN DESCRIPTION:
STEELE CREEK 18.0
END DESCRIPTION:
XS GIS Cut Line= 3
      3543239.49     10438965.51      3542739.49     10437986.34
      3538906.63     10436028.25
#Sta/Elev= 30
  3128.7  353.04  3301.5  346.69  3413.7  332.83  3486.2  341.33    3853  336.96
  3898.5  336.16  3976.4  335.06  4383.5  329.62  4485.5  326.78  4601.3  320.25
  4703.1  323.62  4840.1  325.82  4956.8  311.94  4985.8  303.08  4988.5  302.58
  4991.8  303.08  4997.2  303.63  5023.4  310.21  5084.5  305.89  5128.9  312.79
  7077.5  315.67  7555.4   339.7  7851.1  356.66  8075.5  352.91  8155.5  344.58
  8272.7  353.31  8323.9  346.88  8361.6  354.72  8513.2  362.17  8532.2  363.06
#Mann= 14 ,-1 , 0
  3128.7     .16       0    3853     .05       0  3898.5     .16       0
  3976.4     .05       0  4383.5     .16       0  4485.5     .05       0
  4703.1     .16       0  4985.8     .07       0  4991.8     .16       0
  4997.2     .12       0  7555.4     .05       0  7851.1      .1       0
  8075.5     .16       0  8513.2      .1       0
#XS Ineff= 2 , 0
       0    4800  326.46               0
Permanent Ineff=
       T       F
Bank Sta=4956.8,5023.4
XS Rating Curve= 0 ,0
Exp/Cntr=0.3,0.1

Type RM Length L Ch R = 1 ,22937   ,4410,4410,4410
BEGIN DESCRIPTION:
STEELE CREEK 15.0
END DESCRIPTION:
XS GIS Cut Line= 3
      3543484.98     10437972.78      3544049.21     10433936.34
      3540403.42     10432070.04
#Sta/Elev= 30
  2018.3  355.72  3632.1  331.68  3711.8  330.38  4636.1  312.61  4907.3  308.88
  4922.7  307.29  4927.8  303.43    4999  300.39    5089  307.53  5099.1  307.73
  5795.8  304.81  7937.7  310.06    8021  311.04  8204.2  326.71  8356.3  340.69
  8731.6  374.34    9009  363.92  9247.5  378.09    9628  374.05  9649.9  373.36
  9669.6  369.79  9758.5  379.59  9936.1  376.74  9958.3  375.09  9974.9  366.84
  9980.5  372.05  9997.1  363.63 10041.5  377.91   10085  381.75 10189.7  390.16
#Mann= 11 ,-1 , 0
  2018.3     .05       0  3632.1      .1       0  3711.8     .05       0
  4636.1     .16       0  4907.3     .12       0    5089     .16       0
  8204.2     .12       0  8356.3     .16       0    9628      .1       0
  9649.9     .16       0   10085     .05       0
#XS Ineff= 1 ,-1
 5142.51 8200.46  311.34
Permanent Ineff=
       T
Bank Sta=4922.7,5099.1
XS Rating Curve= 0 ,0
Exp/Cntr=0.3,0.1

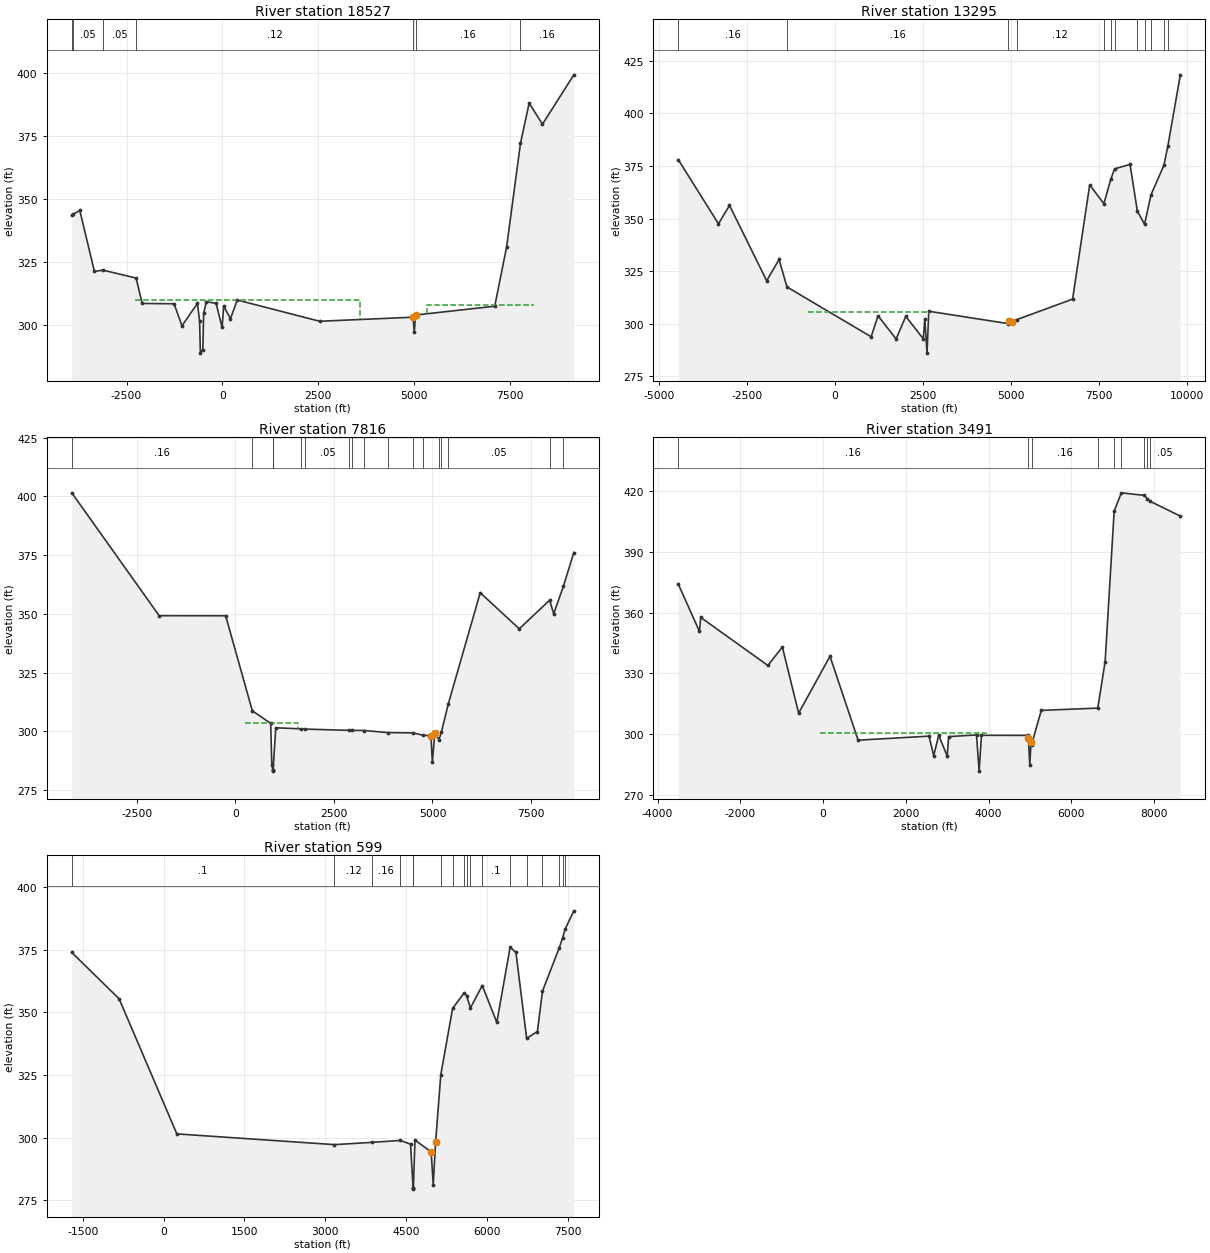
Type RM Length L Ch R = 1 ,18527   ,5232,5232,5232
BEGIN DESCRIPTION:
STEELE CREEK 13.0
END DESCRIPTION:
XS GIS Cut Line= 3
       3552816.6     10440273.17      3544446.78     10431728.01
      3544800.64     10430645.62
#Sta/Elev= 30
 -3929.4  343.52 -3897.1  343.88   -3720  345.45 -3338.3  321.21 -3114.9  321.75
 -2249.2  318.59 -2093.6  308.52 -1259.2  308.38 -1054.2  299.63  -651.1  308.54
  -594.5  301.54  -573.5  288.78  -509.7  290.18  -488.4  304.56  -417.7  309.25
  -163.1  308.51    -7.6  299.01    34.8  307.44   211.7  302.46   388.4  309.88
  2538.2  301.44  4977.8  303.05  5006.1  297.05  5041.5  303.92  7106.3  307.41
  7417.5  331.04  7778.1  372.07  8004.4  388.08  8351.9  379.72  9170.7  399.32
#Mann= 7 ,-1 , 0
 -3929.4     .16       0 -3897.1     .05       0 -3114.9     .05       0
 -2249.2     .12       0  4977.8     .12       0  5041.5     .16       0
  7778.1     .16       0
#XS Ineff= 2 ,-1
-2279.55  3599.8     310 5338.64 8130.68  307.93
Permanent Ineff=
       T       T
Bank Sta=4977.8,5041.5
XS Rating Curve= 0 ,0
Exp/Cntr=0.3,0.1

Type RM Length L Ch R = 1 ,13295   ,5479,5479,5479
BEGIN DESCRIPTION:
STEELE CREEK 11.0
END DESCRIPTION:
XS GIS Cut Line= 3
      3557859.98     10435307.87       3545707.2     10429231.48
      3545099.54     10429535.31
#Sta/Elev= 30
 -4455.5  377.99 -3312.1   347.5 -2999.1  356.23 -1942.3   320.4 -1590.4  330.51
 -1366.7  317.47  1025.8  293.77  1221.5  303.76  1735.8  292.75  2009.7  303.49
  2507.5   292.8  2552.2  302.04  2613.2     286    2664  305.91  4916.6  300.04
  4944.8  301.48  5028.4  300.86  5162.6  301.91  6750.2  311.67  7236.5  365.97
    7639  357.06  7835.4  368.62  7942.6   373.6  8382.5  375.72  8590.9  353.45
    8795  347.29  8978.7  361.28    9345  375.31  9457.8  384.45  9811.1   418.3
#Mann= 12 ,-1 , 0
 -4455.5     .16       0 -1366.7     .16       0  4916.6     .12       0
  5162.6     .12       0    7639     .05       0  7835.4      .1       0
  7942.6     .16       0  8590.9     .05       0    8795     .16       0
  8978.7     .16       0    9345     .05       0  9457.8     .16       0
#XS Ineff= 1 ,-1
 -781.76 2659.62   305.6
Permanent Ineff=
       T
Bank Sta=4944.8,5028.4
XS Rating Curve= 0 ,0
Exp/Cntr=0.3,0.1

Type RM Length L Ch R = 1 ,7816    ,4325,4325,4325
BEGIN DESCRIPTION:
STEELE CREEK 8.0
END DESCRIPTION:
XS GIS Cut Line= 3
      3557903.39     10432182.88      3549005.81     10425542.24
      3547399.88     10425238.42
#Sta/Elev= 30
 -4149.9  401.49   -1933  349.22  -246.4  349.19     431  308.72     896  303.42
   925.2  285.73   951.4  283.58   954.2  283.08   957.4  283.58  1025.3  301.52
  1657.2  301.08    1777  300.96  2890.8  300.43  2955.7  300.42  3273.3  300.36
  3867.9  299.48    4504  299.34  4762.4  298.38  4961.3  298.09  4998.1  286.95
  5061.4  299.32  5165.6  296.48    5228  299.74  5399.2   311.5  6212.2     359
  7201.8  343.63  7972.4  355.81  8075.9  350.01  8323.6  361.82    8587   376.1
#Mann= 17 ,-1 , 0
 -4149.9     .16       0     431     .12       0   951.4     .07       0
   957.4     .12       0  1657.2     .16       0    1777     .05       0
  2890.8      .1       0  2955.7     .05       0  3273.3     .07       0
  3867.9     .05       0    4504     .07       0  4762.4     .12       0
  5165.6     .16       0    5228     .12       0  5399.2     .05       0
  7972.4     .16       0  8323.6     .05       0
#XS Ineff= 1 ,-1
   235.5 1593.02   303.6
Permanent Ineff=
       T
Bank Sta=4961.3,5061.4
XS Rating Curve= 0 ,0
Exp/Cntr=0.3,0.1

Type RM Length L Ch R = 1 ,3491    ,2892,2892,2892
BEGIN DESCRIPTION:
STEELE CREEK 4.0
END DESCRIPTION:
XS GIS Cut Line= 3
      3557903.39     10431054.42      3556991.92     10428710.65
      3550612.07     10421506.19
#Sta/Elev= 30
   -3501  374.11 -2987.7  350.66 -2957.8   357.6 -1333.8  333.86  -983.6  342.98
  -590.2  310.31   167.6  338.41   847.6  296.97  2562.3  298.97  2675.2  289.32
  2795.6  299.39  3001.4  289.16  3036.5  298.73  3709.8  299.57  3773.1  281.69
  3830.3  299.37  4956.4  299.36  4963.6  298.13  4998.7   284.5  5027.1  295.94
  5041.4  294.82  5275.6  311.68  6641.5  312.81  6819.6  335.74  7037.8  410.08
    7212  419.11  7766.7  417.85  7842.8  416.23  7902.6  414.96    8637  407.63
#Mann= 9 ,-1 , 0
   -3501     .16       0  4956.4     .12       0  5041.4     .16       0
  6641.5     .16       0  7037.8     .05       0    7212      .1       0
  7766.7     .05       0  7842.8      .1       0  7902.6     .05       0
#XS Ineff= 1 ,-1
  -81.07 3948.31  300.73
Permanent Ineff=
       T
Bank Sta=4963.6,5027.1
XS Rating Curve= 0 ,0
Exp/Cntr=0.3,0.1

Type RM Length L Ch R = 1 ,599     ,0,0,0
BEGIN DESCRIPTION:
STEELE CREEK 1.0
END DESCRIPTION:
XS GIS Cut Line= 2
      3559639.53     10425325.25      3551436.75     10420898.35
#Sta/Elev= 30
 -1703.3  373.96  -823.7  355.45   247.3  301.54  3174.2  297.25  3877.9  298.17
  4396.5  298.93  4586.4  297.43  4632.9  279.99  4635.6  279.49  4638.9  279.99
  4668.3  299.04  4969.1  294.35  5007.2  281.27  5050.9  298.14  5147.8  325.18
  5367.7  351.69  5587.6  357.95  5626.8  356.73  5697.6  351.82  5917.5  360.77
  6187.6  346.06  6434.5  376.04  6542.7  373.99  6741.6  339.65  6941.3  342.41
  7035.3  358.51  7346.9   375.8  7410.5  379.88  7456.9  383.32  7617.8  390.58
#Mann= 18 ,-1 , 0
 -1703.3      .1       0  3174.2     .12       0  3877.9     .16       0
  4396.5     .12       0  4632.9     .07       0  4638.9     .12       0
  5147.8     .16       0  5367.7      .1       0  5587.6     .05       0
  5626.8      .1       0  5697.6     .05       0  5917.5      .1       0
  6434.5     .05       0  6741.6     .16       0  7035.3     .05       0
  7346.9      .1       0  7410.5     .05       0  7456.9      .1       0
Bank Sta=4969.1,5050.9
XS Rating Curve= 0 ,0
Exp/Cntr=0.3,0.1

Chan Stop Cuts=-1
Use User Specified Reach Order=0
Composite Channel Slope=5