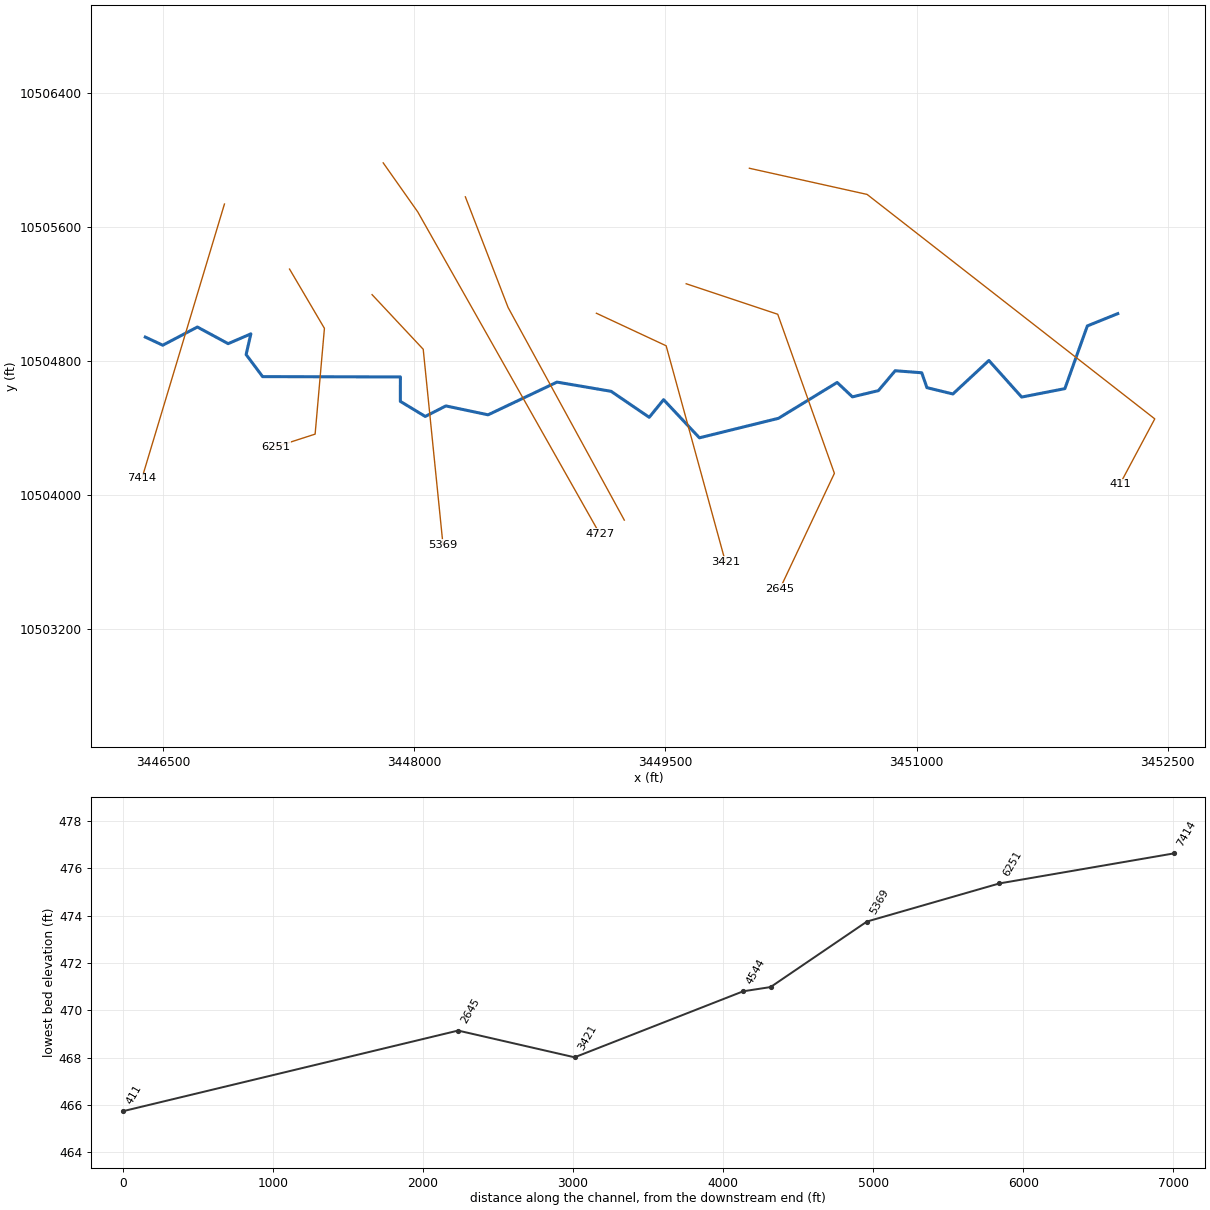
--- UNT004 IN STEL.prj (project) ---

Proj Title=UNT004 IN STEL Base Level Engineering
Current Plan=p01
Default Exp/Contr=0.3,0.1
English Units
Geom File=g01
Flow File=f01
Plan File=p01
BEGIN DESCRIPTION:
UNT004 IN STEL
END DESCRIPTION:

--- UNT004 IN STEL.p01 (plan) ---

Plan Title=Multiple Run
Short Identifier=Multiple
Geom File=g01
Flow File=f01
Subcritical Flow
K Sum by GR= 0
Std Step Tol= 0.01
Critical Tol= 0.01
Num of Std Step Trials= 20
Max Error Tol= 0.3
Flow Tol Ratio= 0.001
Split Flow NTrial= 30
Split Flow Tol= 0.02
Split Flow Ratio= 0.02
Log Output Level= 0
Friction Slope Method= 1
Unsteady Friction Slope Method= 2
Unsteady Bridges Friction Slope Method= 1
Parabolic Critical Depth
Global Vel Dist=  1 , 1 , 1
Global Log Level= 0
CheckData=True
Encroach Param= -1, 0, 0, 0
BEGIN DESCRIPTION:
Multiple Run
END DESCRIPTION:

--- UNT004 IN STEL.f01 (steady flow) ---

Flow Title=Multiple
Number of Profiles=7
Profile Names=10-year,25-year,50-year,1pct_min,100-year,1pct_plu,500-year
River Rch & RM= UNT004 IN STEL,Reach-1,7414
    1044    1434    1753    1563    2114    2858    3065
River Rch & RM= UNT004 IN STEL,Reach-1,5369
    2006    2833    3530    3198    4325    5849    6481
Boundary for River Rch & Prof#=UNT004 IN STEL,Reach-1,1
Up Type=0
Dn Type=3
Dn Slope=0.005
Boundary for River Rch & Prof#=UNT004 IN STEL,Reach-1,2
Up Type=0
Dn Type=3
Dn Slope=0.005
Boundary for River Rch & Prof#=UNT004 IN STEL,Reach-1,3
Up Type=0
Dn Type=3
Dn Slope=0.005
Boundary for River Rch & Prof#=UNT004 IN STEL,Reach-1,4
Up Type=0
Dn Type=3
Dn Slope=0.005
Boundary for River Rch & Prof#=UNT004 IN STEL,Reach-1,5
Up Type=0
Dn Type=3
Dn Slope=0.005
Boundary for River Rch & Prof#=UNT004 IN STEL,Reach-1,6
Up Type=0
Dn Type=3
Dn Slope=0.005
Boundary for River Rch & Prof#=UNT004 IN STEL,Reach-1,7
Up Type=0
Dn Type=3
Dn Slope=0.005

--- UNT004 IN STEL.g01 (geometry) ---

Geom Title=Existing Conditions

River Reach=UNT004 IN STEL,Reach-1
Reach XY= 30
      3446392.11     10504941.64      3446496.40     10504892.98
      3446703.37     10505001.67      3446886.98     10504902.26
      3447022.80     10504960.82      3446994.41     10504837.11
      3447093.08     10504705.20      3447916.20     10504703.37
      3447915.77     10504557.53      3448064.64     10504467.26
      3448187.90     10504530.19      3448440.09     10504477.10
      3448851.97     10504672.55      3449174.88     10504617.52
      3449402.78     10504462.14      3449488.68     10504567.52
      3449702.66     10504339.65      3450174.96     10504456.12
      3450525.58     10504670.38      3450616.75     10504584.36
      3450772.11     10504621.64      3450872.27     10504740.40
      3451030.93     10504728.28      3451061.95     10504639.33
      3451217.14     10504601.62      3451432.11     10504801.64
      3451627.89     10504583.08      3451886.03     10504633.54
      3452020.31     10505008.23      3452202.11     10505081.64

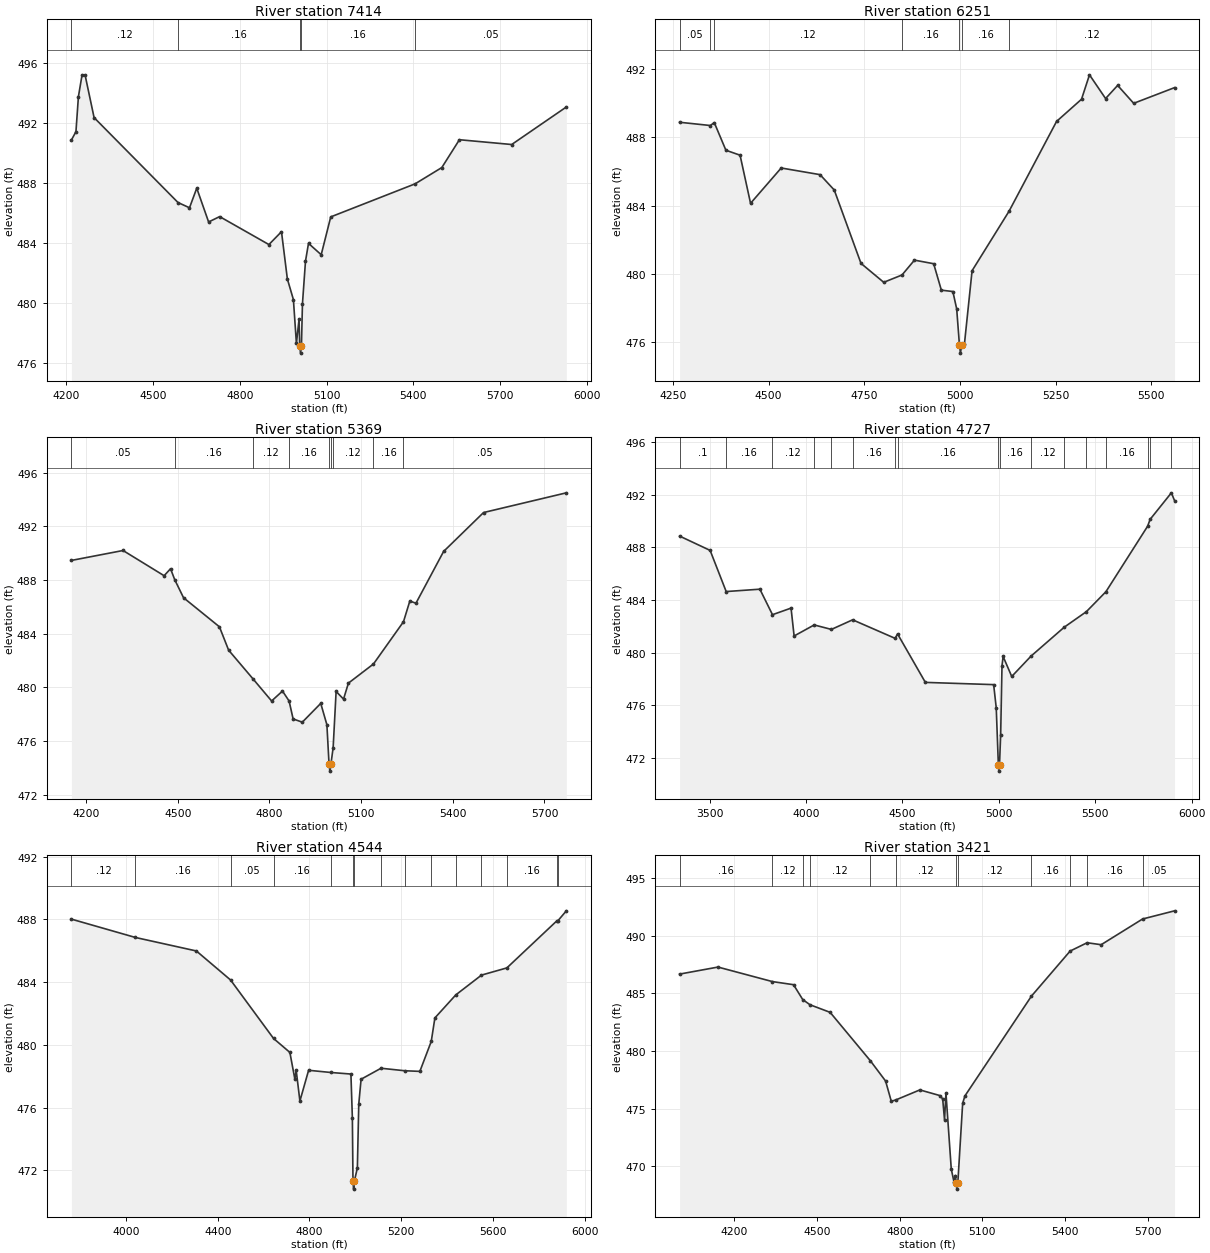
Type RM Length L Ch R = 1,7414,1163,1163,1163
BEGIN DESCRIPTION:
UNT004 IN STEL 10.0
END DESCRIPTION:
XS GIS Cut Line= 2
      3446865.03     10505736.70      3446371.99     10504097.86
#Sta/Elev= 30
  4217.5  490.88  4233.2  491.44  4241.7  493.78  4254.1  495.21  4264.6  495.24
  4295.9  492.38  4586.1  486.70  4625.8  486.35  4650.9  487.66  4691.9  485.40
  4730.1  485.76  4900.4  483.89  4943.9  484.75  4964.2  481.59  4985.1  480.21
  4995.5  477.28  5004.7  478.92  5006.9  477.13  5009.7  476.63  5012.9  477.13
  5016.4  479.93  5026.9  482.78  5037.3  483.97  5081.2  483.21  5114.2  485.74
  5405.9  487.95  5498.3  489.04  5559.1  490.90  5739.9  490.58  5928.9  493.09
#Mann=5,-1,0
  4217.5    0.12       0  4586.1    0.16       0  5006.9    0.07       0
  5012.9    0.16       0  5405.9    0.05       0
Bank Sta=5006.9,5012.9
Exp/Cntr=0.3,0.1

Type RM Length L Ch R = 1,6251,882,882,882
BEGIN DESCRIPTION:
Mapping XS c3a1ca87
END DESCRIPTION:
XS GIS Cut Line= 4
      3447253.93     10505347.84      3447462.26     10504993.68
      3447406.70     10504361.73      3447170.63     10504285.36
#Sta/Elev= 30
  4267.3  488.89  4347.5  488.70  4357.9  488.87  4388.3  487.25  4425.3  486.96
  4452.7  484.14  4532.8  486.21  4634.3  485.82  4671.4  484.92  4741.3  480.62
  4800.7  479.51  4848.5  479.94  4881.0  480.81  4931.2  480.60  4951.3  479.05
  4981.4  478.97  4991.4  477.95  4998.5  475.86  5001.2  475.36  5004.5  475.86
  5011.5  475.87  5031.6  480.19  5128.3  483.68  5252.4  488.94  5317.6  490.24
  5338.4  491.67  5380.5  490.28  5412.0  491.05  5453.9  490.00  5560.7  490.92
#Mann=7,-1,0
  4267.3    0.05       0  4347.5    0.16       0  4357.9    0.12       0
  4848.5    0.16       0  4998.5    0.07       0  5004.5    0.16       0
  5128.3    0.12       0
Bank Sta=4998.5,5004.5
Exp/Cntr=0.3,0.1

Type RM Length L Ch R = 1,5369,642,642,642
BEGIN DESCRIPTION:
Mapping XS b0d9c89a
END DESCRIPTION:
XS GIS Cut Line= 3
      3447746.95     10505195.10      3448052.54     10504868.68
      3448170.60     10503701.97
#Sta/Elev= 30
  4151.9  489.46  4320.9  490.20  4455.3  488.32  4476.3  488.84  4490.1  488.02
  4518.8  486.68  4636.3  484.51  4666.4  482.77  4747.6  480.59  4807.1  478.98
  4842.7  479.72  4864.3  478.98  4877.5  477.64  4907.6  477.40  4967.9  478.80
  4988.0  477.21  4995.1  474.25  4997.8  473.75  5001.1  474.25  5008.5  475.51
  5018.2  479.69  5042.5  479.12  5058.4  480.31  5140.5  481.74  5238.7  484.89
  5259.4  486.43  5279.5  486.27  5370.0  490.13  5500.7  493.03  5771.7  494.50
#Mann=9,-1,0
  4151.9    0.05       0  4490.1    0.16       0  4747.6    0.12       0
  4864.3    0.16       0  4995.1    0.07       0  5001.1    0.16       0
  5008.5    0.12       0  5140.5    0.16       0  5238.7    0.05       0
Bank Sta=4995.1,5001.1
Exp/Cntr=0.3,0.1

Type RM Length L Ch R = 1,4727,183,183,183
BEGIN DESCRIPTION:
UNT004 IN STEL 9.0
END DESCRIPTION:
XS GIS Cut Line= 3
      3447813.47     10505982.49      3448020.12     10505689.09
      3449107.02     10503766.42
#Sta/Elev= 30
  3343.8  488.86  3502.1  487.77  3585.4  484.64  3760.2  484.82  3825.6  482.88
  3921.9  483.38  3937.8  481.26  4041.9  482.10  4131.2  481.76  4241.4  482.49
  4461.8  481.08  4474.3  481.42  4618.7  477.73  4972.9  477.56  4986.3  475.80
  4997.3  471.48  5000.1  470.98  5003.3  471.48  5009.3  473.75  5016.2  479.00
  5022.0  479.70  5066.7  478.18  5166.9  479.73  5339.2  481.93  5453.9  483.11
  5555.4  484.63  5771.6  489.61  5784.5  490.13  5894.8  492.15  5911.3  491.56
#Mann=17,-1,0
  3343.8     0.1       0  3585.4    0.16       0  3825.6    0.12       0
  4041.9    0.16       0  4131.2    0.12       0  4241.4    0.16       0
  4461.8    0.12       0  4474.3    0.16       0  4997.3    0.07       0
  5003.3    0.16       0  5166.9    0.12       0  5339.2    0.16       0
  5453.9    0.12       0  5555.4    0.16       0  5771.6    0.05       0
  5784.5    0.16       0  5894.8    0.05       0
Bank Sta=4997.3,5003.3
Exp/Cntr=0.3,0.1

Type RM Length L Ch R = 1,4544,1123,1123,1123
BEGIN DESCRIPTION:
UNT004 IN STEL 8.0
END DESCRIPTION:
XS GIS Cut Line= 3
      3448304.29     10505779.57      3448559.48     10505118.68
      3449253.91     10503847.88
#Sta/Elev= 30
  3762.6  488.02  4041.7  486.85  4307.1  485.99  4456.0  484.14  4643.3  480.41
  4714.5  479.52  4736.3  477.81  4742.0  478.38  4758.2  476.42  4796.1  478.38
  4892.8  478.24  4980.5  478.14  4986.8  475.34  4989.5  471.30  4992.3  470.80
  4995.5  471.30  5008.6  472.16  5014.7  476.23  5024.8  477.81  5111.7  478.51
  5215.1  478.35  5280.9  478.31  5330.5  480.22  5346.4  481.72  5437.6  483.19
  5549.4  484.45  5660.1  484.91  5877.7  487.91  5882.5  487.92  5919.2  488.55
#Mann=15,-1,0
  3762.6    0.12       0  4041.7    0.16       0  4456.0    0.05       0
  4643.3    0.16       0  4892.8    0.05       0  4989.5    0.07       0
  4995.5    0.05       0  5111.7    0.05       0  5215.1    0.12       0
  5330.5    0.05       0  5437.6    0.16       0  5549.4    0.05       0
  5660.1    0.16       0  5877.7    0.05       0  5882.5    0.16       0
Bank Sta=4989.5,4995.5
Exp/Cntr=0.3,0.1

Type RM Length L Ch R = 1,3421,776,776,776
BEGIN DESCRIPTION:
UNT004 IN STEL 6.0
END DESCRIPTION:
XS GIS Cut Line= 3
      3449087.23     10505083.97      3449503.93     10504889.51
      3449857.60     10503599.66
#Sta/Elev= 30
  4000.8  486.67  4140.2  487.28  4337.7  486.02  4414.5  485.75  4447.9  484.46
  4474.2  484.01  4547.4  483.35  4693.5  479.15  4748.8  477.39  4769.5  475.63
  4786.9  475.76  4873.2  476.62  4945.8  476.13  4956.1  475.84  4962.8  474.03
  4968.0  476.34  4987.3  469.75  4997.3  468.62  5002.5  469.19  5005.0  468.51
  5007.7  468.01  5011.0  468.51  5028.7  475.46  5036.9  476.10  5278.5  484.76
  5419.0  488.67  5480.6  489.39  5531.6  489.22  5681.9  491.45  5798.1  492.16
#Mann=12,-1,0
  4000.8    0.16       0  4337.7    0.12       0  4447.9    0.16       0
  4474.2    0.12       0  4693.5    0.16       0  4786.9    0.12       0
  5005.0    0.07       0  5011.0    0.12       0  5278.5    0.16       0
  5419.0    0.12       0  5480.6    0.16       0  5681.9    0.05       0
Bank Sta=5005,5011
Exp/Cntr=0.3,0.1

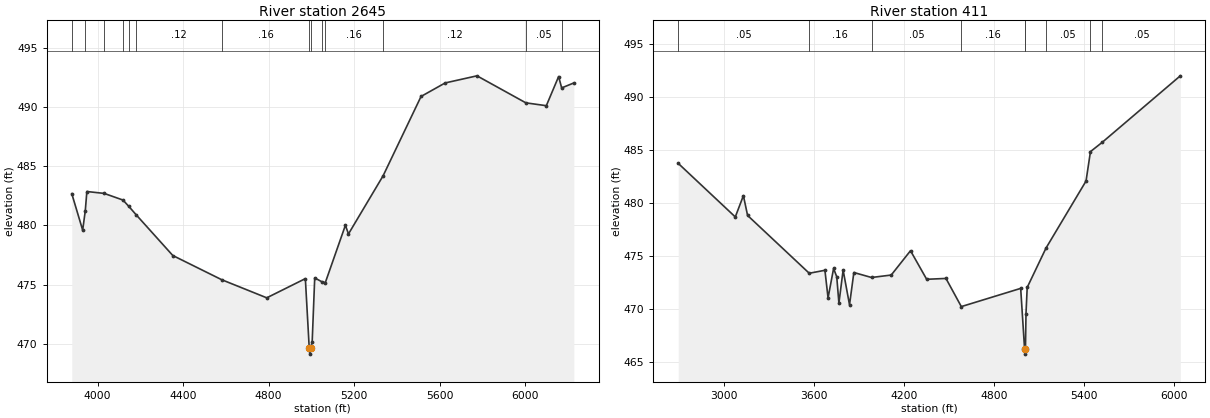
Type RM Length L Ch R = 1,2645,2234,2234,2234
BEGIN DESCRIPTION:
UNT004 IN STEL 4.0
END DESCRIPTION:
XS GIS Cut Line= 4
      3449623.73     10505260.17      3450170.59     10505077.88
      3450509.13     10504127.36      3450183.61     10503437.24
#Sta/Elev= 30
  3879.6  482.68  3930.6  479.60  3942.8  481.23  3950.2  482.86  4031.1  482.70
  4119.0  482.14  4146.2  481.61  4179.6  480.92  4352.2  477.46  4580.7  475.42
  4791.7  473.89  4972.2  475.51  4990.4  469.64  4993.2  469.14  4996.4  469.64
  5004.1  470.16  5016.0  475.57  5051.1  475.23  5065.7  475.18  5159.5  480.01
  5173.9  479.28  5336.0  484.19  5513.4  490.88  5626.2  492.02  5775.0  492.62
  6003.7  490.34  6099.4  490.10  6156.9  492.56  6171.1  491.60  6228.1  492.02
#Mann=14,-1,0
  3879.6    0.16       0  3942.8    0.12       0  4031.1    0.16       0
  4119.0    0.12       0  4146.2    0.16       0  4179.6    0.12       0
  4580.7    0.16       0  4990.4    0.07       0  4996.4    0.16       0
  5051.1    0.12       0  5065.7    0.16       0  5336.0    0.12       0
  6003.7    0.05       0  6171.1    0.12       0
Bank Sta=4990.4,4996.4
Exp/Cntr=0.3,0.1

Type RM Length L Ch R = 1,411,0,0,0
BEGIN DESCRIPTION:
UNT004 IN STEL 1.0
END DESCRIPTION:
XS GIS Cut Line= 4
      3450001.30     10505950.28      3450704.45     10505794.02
      3452423.20     10504452.88      3452214.86     10504062.25
#Sta/Elev= 30
  2696.1  483.75  3076.0  478.69  3130.0  480.70  3157.9  478.83  3568.4  473.37
  3672.8  473.65  3693.7  471.04  3730.5  473.82  3751.5  473.04  3766.0  470.55
  3794.0  473.67  3836.6  470.39  3865.5  473.44  3983.0  472.97  4114.3  473.20
  4242.7  475.50  4350.3  472.80  4478.8  472.88  4581.0  470.22  4976.3  471.94
  5002.2  466.23  5005.0  465.73  5008.2  466.23  5011.6  469.53  5019.7  472.03
  5145.0  475.75  5411.4  482.08  5440.9  484.86  5520.3  485.75  6039.2  492.02
#Mann=9,-1,0
  2696.1    0.05       0  3568.4    0.16       0  3983.0    0.05       0
  4581.0    0.16       0  5002.2    0.07       0  5008.2    0.16       0
  5145.0    0.05       0  5440.9    0.16       0  5520.3    0.05       0
Bank Sta=5002.2,5008.2
Exp/Cntr=0.3,0.1

Chan Stop Cuts=-1