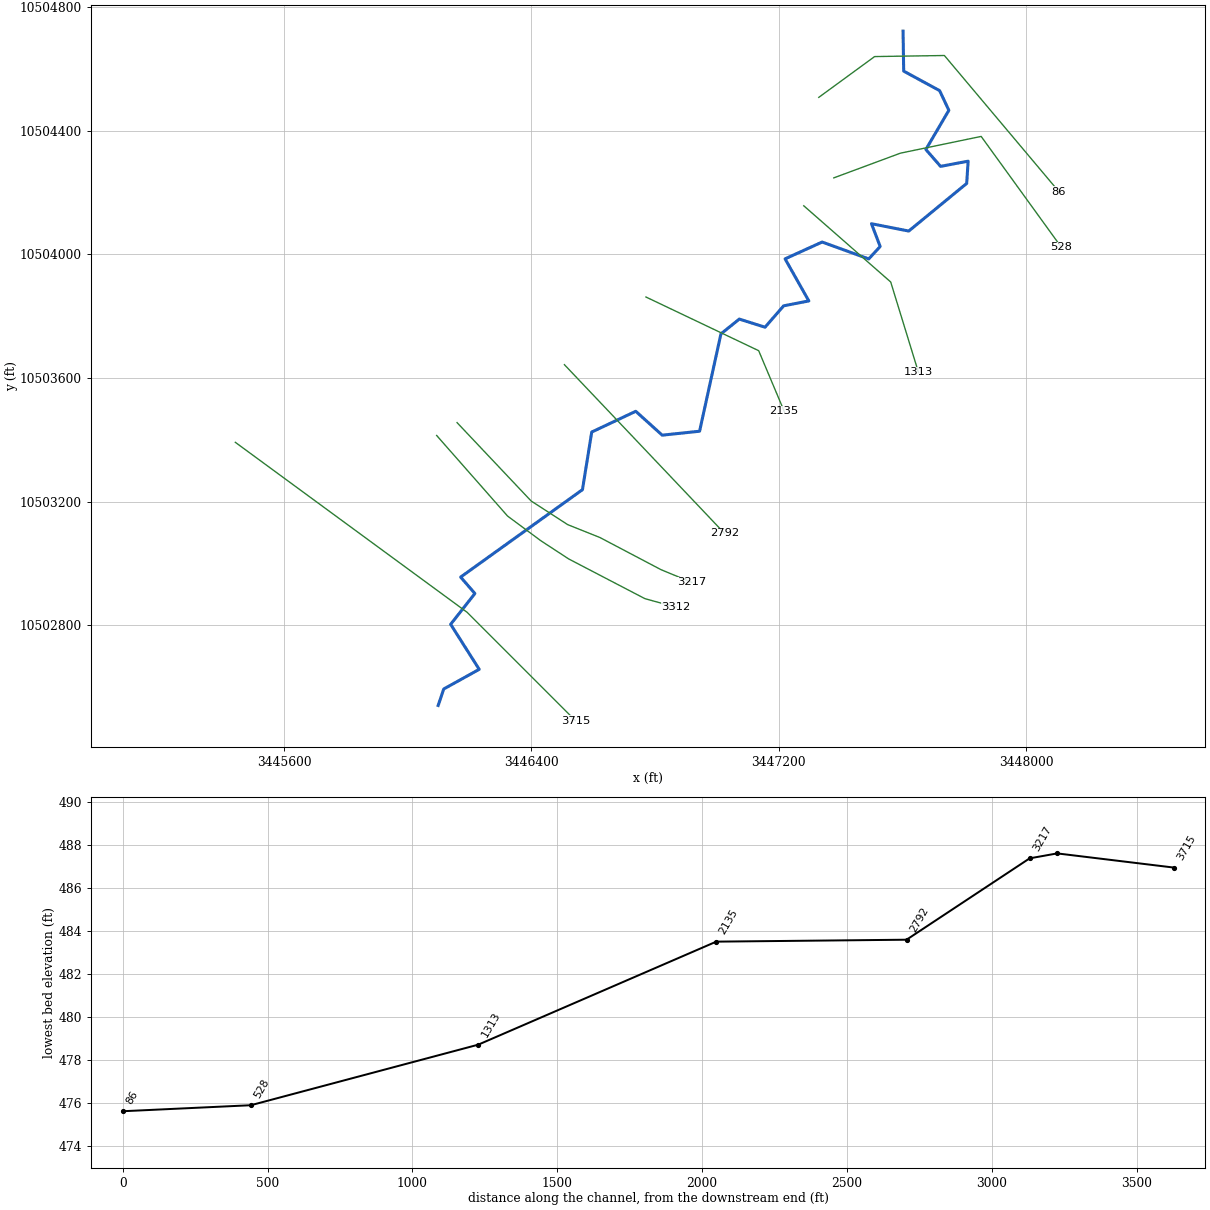
--- UNT005 IN STEL.prj (project) ---

Proj Title=UNT005 IN STEL Base Level Engineering
Current Plan=p01
Default Exp/Contr=0.3,0.1
English Units
Geom File=g01
Flow File=f01
Plan File=p01
BEGIN DESCRIPTION:
UNT005 IN STEL
END DESCRIPTION:

--- UNT005 IN STEL.p01 (plan) ---

Plan Title=Multiple Run
Short Identifier=Multiple
Geom File=g01
Flow File=f01
Subcritical Flow
K Sum by GR= 0
Std Step Tol= 0.01
Critical Tol= 0.01
Num of Std Step Trials= 20
Max Error Tol= 0.3
Flow Tol Ratio= 0.001
Split Flow NTrial= 30
Split Flow Tol= 0.02
Split Flow Ratio= 0.02
Log Output Level= 0
Friction Slope Method= 1
Unsteady Friction Slope Method= 2
Unsteady Bridges Friction Slope Method= 1
Parabolic Critical Depth
Global Vel Dist=  1 , 1 , 1
Global Log Level= 0
CheckData=True
Encroach Param= -1, 0, 0, 0
BEGIN DESCRIPTION:
Multiple Run
END DESCRIPTION:

--- UNT005 IN STEL.f01 (steady flow) ---

Flow Title=Multiple
Number of Profiles=7
Profile Names=10-year,25-year,50-year,1pct_min,100-year,1pct_plu,500-year
River Rch & RM= UNT005 IN STEL,Reach-1,3715
     920    1252    1521    1348    1823    2466    2613
Boundary for River Rch & Prof#=UNT005 IN STEL,Reach-1,1
Up Type=0
Dn Type=3
Dn Slope=0.005
Boundary for River Rch & Prof#=UNT005 IN STEL,Reach-1,2
Up Type=0
Dn Type=3
Dn Slope=0.005
Boundary for River Rch & Prof#=UNT005 IN STEL,Reach-1,3
Up Type=0
Dn Type=3
Dn Slope=0.005
Boundary for River Rch & Prof#=UNT005 IN STEL,Reach-1,4
Up Type=0
Dn Type=3
Dn Slope=0.005
Boundary for River Rch & Prof#=UNT005 IN STEL,Reach-1,5
Up Type=0
Dn Type=3
Dn Slope=0.005
Boundary for River Rch & Prof#=UNT005 IN STEL,Reach-1,6
Up Type=0
Dn Type=3
Dn Slope=0.005
Boundary for River Rch & Prof#=UNT005 IN STEL,Reach-1,7
Up Type=0
Dn Type=3
Dn Slope=0.005

--- UNT005 IN STEL.g01 (geometry) ---

Geom Title=Existing Conditions

River Reach=UNT005 IN STEL,Reach-1
Reach XY= 30
      3446098.29     10502540.42      3446116.29     10502593.69
      3446231.08     10502657.28      3446138.65     10502802.98
      3446217.10     10502902.57      3446171.02     10502955.70
      3446565.00     10503238.41      3446595.07     10503424.89
      3446737.44     10503492.01      3446822.95     10503414.78
      3446943.91     10503427.52      3447012.98     10503742.40
      3447072.42     10503790.26      3447155.68     10503763.99
      3447215.82     10503833.16      3447297.29     10503848.97
      3447220.46     10503985.08      3447340.33     10504039.49
      3447491.12     10503984.91      3447528.06     10504025.15
      3447499.87     10504098.77      3447620.55     10504075.05
      3447807.93     10504229.06      3447812.62     10504301.14
      3447723.45     10504284.23      3447675.88     10504338.82
      3447750.27     10504465.59      3447720.38     10504529.22
      3447604.14     10504592.38      3447602.11     10504721.64

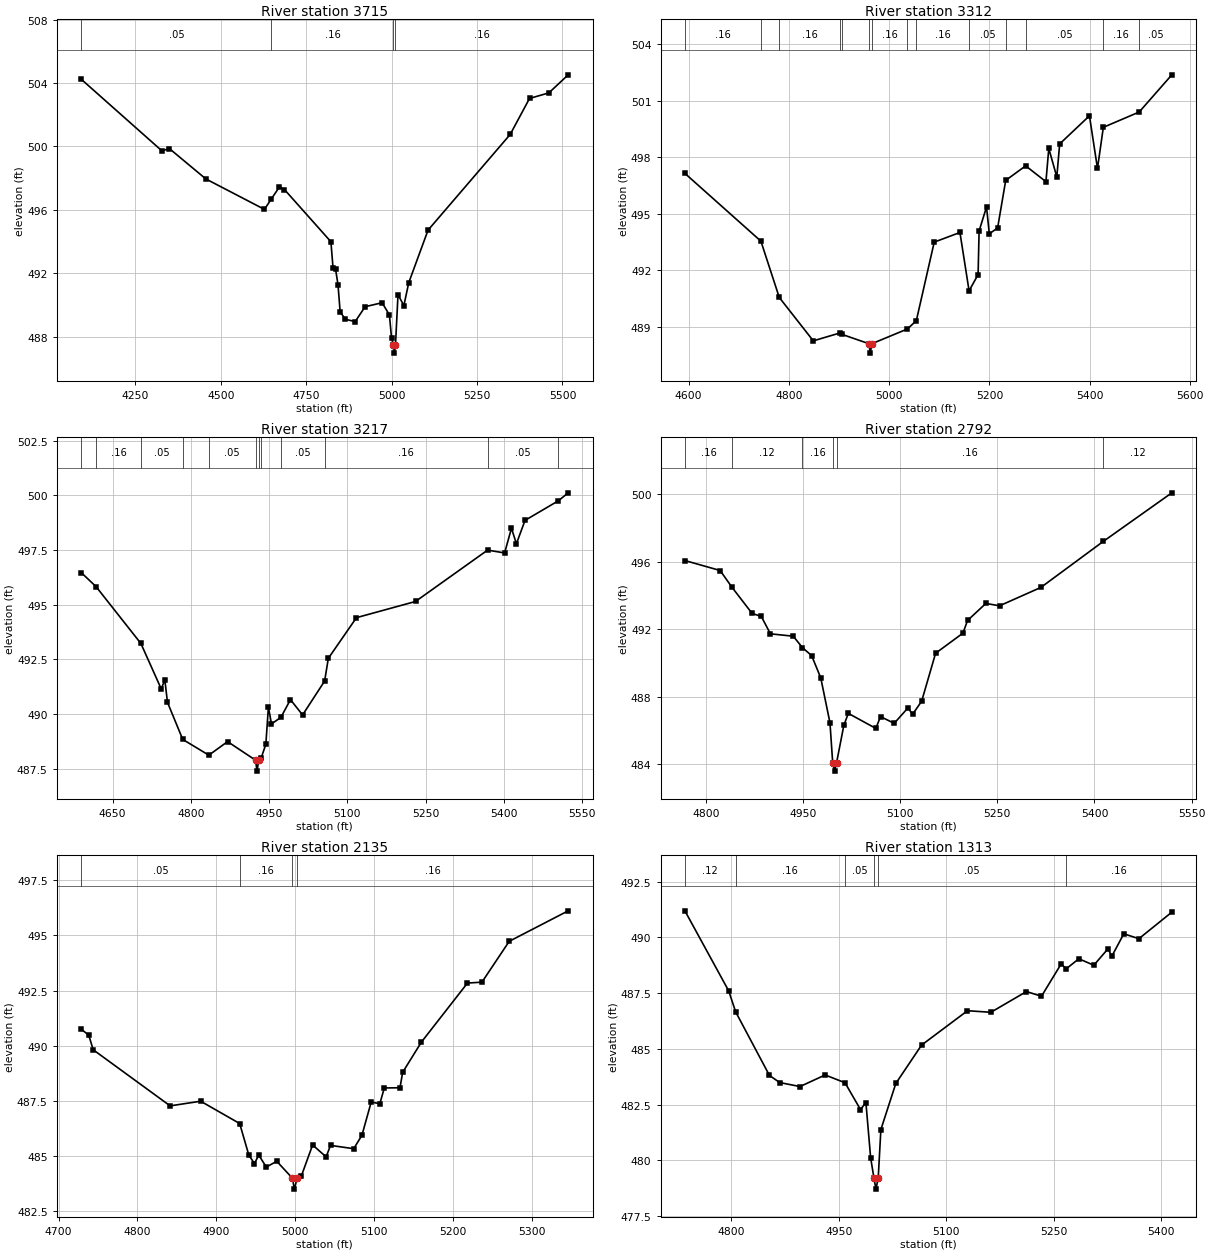
Type RM Length L Ch R = 1,3715,403,403,403
BEGIN DESCRIPTION:
UNT005 IN STEL 8.0
END DESCRIPTION:
XS GIS Cut Line= 3
      3445442.07     10503391.67      3446192.11     10502841.64
      3446542.13     10502491.62
#Sta/Elev= 30
  4091.6  504.24  4327.3  499.73  4349.8  499.86  4456.3  497.95  4627.7  496.03
  4648.0  496.69  4671.7  497.45  4686.3  497.28  4822.2  493.99  4828.4  492.35
  4835.7  492.28  4843.0  491.28  4849.2  489.58  4863.9  489.10  4893.2  488.95
  4922.5  489.89  4972.1  490.14  4993.5  489.37  4999.7  487.91  5005.2  487.46
  5007.9  486.96  5011.2  487.46  5018.6  490.65  5035.8  489.96  5050.0  491.40
  5106.5  494.72  5347.0  500.76  5403.5  503.03  5460.1  503.38  5516.7  504.52
#Mann=4,-1,0
  4091.6    0.05       0  4648.0    0.16       0  5005.2    0.07       0
  5011.2    0.16       0
Bank Sta=5005.2,5011.2
Exp/Cntr=0.3,0.1

Type RM Length L Ch R = 1,3312,95,95,95
BEGIN DESCRIPTION:
UNT005 IN STEL 6.0
END DESCRIPTION:
XS GIS Cut Line= 6
      3446093.38     10503413.75      3446322.57     10503153.31
      3446430.21     10503073.45      3446520.49     10503014.42
      3446767.01     10502885.95      3446867.45     10502858.24
#Sta/Elev= 30
  4592.5  497.14  4744.1  493.55  4780.7  490.57  4848.6  488.27  4902.0  488.69
  4906.1  488.61  4959.5  488.12  4962.2  487.62  4965.5  488.12  5036.4  488.90
  5054.1  489.34  5089.8  493.50  5141.1  494.01  5159.3  490.92  5177.3  491.78
  5179.3  494.09  5194.1  495.36  5199.7  493.94  5216.2  494.25  5232.4  496.77
  5272.2  497.54  5312.6  496.70  5318.3  498.46  5334.3  496.95  5340.0  498.70
  5399.4  500.19  5415.4  497.40  5427.1  499.58  5498.6  500.39  5563.7  502.36
#Mann=14,-1,0
  4592.5    0.16       0  4744.1    0.05       0  4780.7    0.16       0
  4902.0    0.05       0  4906.1    0.16       0  4959.5    0.07       0
  4965.5    0.16       0  5036.4    0.05       0  5054.1    0.16       0
  5159.3    0.05       0  5232.4    0.16       0  5272.2    0.05       0
  5427.1    0.16       0  5498.6    0.05       0
Bank Sta=4959.5,4965.5
Exp/Cntr=0.3,0.1

Type RM Length L Ch R = 1,3217,425,425,425
BEGIN DESCRIPTION:
UNT005 IN STEL 7.0
END DESCRIPTION:
XS GIS Cut Line= 6
      3446159.38     10503455.39      3446398.96     10503201.92
      3446517.01     10503125.53      3446621.18     10503083.87
      3446819.10     10502979.70      3446918.49     10502938.57
#Sta/Elev= 30
  4590.1  496.47  4618.4  495.83  4704.3  493.23  4743.3  491.15  4750.2  491.57
  4755.2  490.54  4784.5  488.84  4834.5  488.12  4870.4  488.74  4924.0  487.89
  4926.8  487.39  4930.0  487.89  4934.6  487.98  4943.7  488.62  4948.6  490.32
  4954.5  489.55  4972.6  489.85  4990.8  490.66  5014.1  489.96  5056.3  491.51
  5063.4  492.55  5117.3  494.41  5230.4  495.15  5368.5  497.50  5401.1  497.37
  5414.2  498.50  5423.7  497.79  5440.2  498.86  5503.7  499.75  5522.9  500.12
#Mann=12,-1,0
  4590.1    0.05       0  4618.4    0.16       0  4704.3    0.05       0
  4784.5    0.16       0  4834.5    0.05       0  4924.0    0.04       0
  4930.0    0.05       0  4934.6    0.16       0  4972.6    0.05       0
  5056.3    0.16       0  5368.5    0.05       0  5503.7    0.16       0
Bank Sta=4924,4930
Exp/Cntr=0.3,0.1

Type RM Length L Ch R = 1,2792,657,657,657
BEGIN DESCRIPTION:
UNT005 IN STEL 5.0
END DESCRIPTION:
XS GIS Cut Line= 2
      3446506.63     10503642.86      3447023.95     10503097.76
#Sta/Elev= 30
  4767.9  496.07  4822.3  495.48  4840.5  494.49  4871.6  492.94  4885.8  492.76
  4899.9  491.73  4935.1  491.59  4949.4  490.91  4963.5  490.44  4977.6  489.12
  4991.8  486.46  4996.0  484.10  4998.8  483.60  5002.0  484.10  5013.2  486.31
  5020.1  487.02  5062.6  486.13  5069.8  486.83  5090.9  486.43  5112.3  487.35
  5119.2  486.96  5133.3  487.74  5154.8  490.58  5197.0  491.77  5204.1  492.52
  5232.4  493.53  5253.5  493.39  5317.4  494.48  5413.5  497.20  5519.4  500.08
#Mann=6,-1,0
  4767.9    0.16       0  4840.5    0.12       0  4949.4    0.16       0
  4996.0    0.07       0  5002.0    0.16       0  5413.5    0.12       0
Bank Sta=4996,5002
Exp/Cntr=0.3,0.1

Type RM Length L Ch R = 1,2135,822,822,822
BEGIN DESCRIPTION:
UNT005 IN STEL 4.0
END DESCRIPTION:
XS GIS Cut Line= 3
      3446770.45     10503861.66      3447135.07     10503688.03
      3447217.75     10503491.67
#Sta/Elev= 30
  4728.8  490.75  4738.3  490.48  4743.9  489.82  4841.4  487.28  4880.1  487.49
  4929.5  486.48  4941.1  485.05  4948.2  484.67  4953.7  485.05  4963.2  484.51
  4976.5  484.77  4996.2  484.01  4998.9  483.51  5002.2  484.01  5007.5  484.09
  5021.9  485.51  5039.0  484.97  5044.6  485.49  5074.0  485.34  5084.4  485.95
  5096.1  487.45  5107.1  487.38  5112.7  488.09  5132.6  488.10  5136.0  488.80
  5159.8  490.17  5218.1  492.84  5236.4  492.88  5271.0  494.73  5345.7  496.11
#Mann=4,-1,0
  4728.8    0.05       0  4929.5    0.16       0  4996.2    0.07       0
  5002.2    0.16       0
Bank Sta=4996.2,5002.2
Exp/Cntr=0.3,0.1

Type RM Length L Ch R = 1,1313,785,785,785
BEGIN DESCRIPTION:
UNT005 IN STEL 3.0
END DESCRIPTION:
XS GIS Cut Line= 3
      3447280.88     10504156.80      3447562.15     10503910.26
      3447652.06     10503617.49
#Sta/Elev= 30
  4735.0  491.19  4796.2  487.60  4805.9  486.66  4853.1  483.81  4867.4  483.49
  4895.8  483.31  4931.0  483.83  4958.7  483.48  4980.3  482.28  4987.9  482.59
  4994.5  480.12  4999.1  479.21  5001.9  478.71  5005.1  479.21  5008.8  481.38
  5029.7  483.45  5065.7  485.17  5129.8  486.71  5162.5  486.64  5212.2  487.57
  5233.2  487.36  5260.7  488.81  5267.8  488.59  5285.4  489.04  5306.3  488.75
  5326.2  489.49  5331.4  489.15  5348.2  490.16  5369.3  489.94  5415.3  491.13
#Mann=6,-1,0
  4735.0    0.12       0  4805.9    0.16       0  4958.7    0.05       0
  4999.1   0.035       0  5005.1    0.05       0  5267.8    0.16       0
Bank Sta=4999.1,5005.1
Exp/Cntr=0.3,0.1

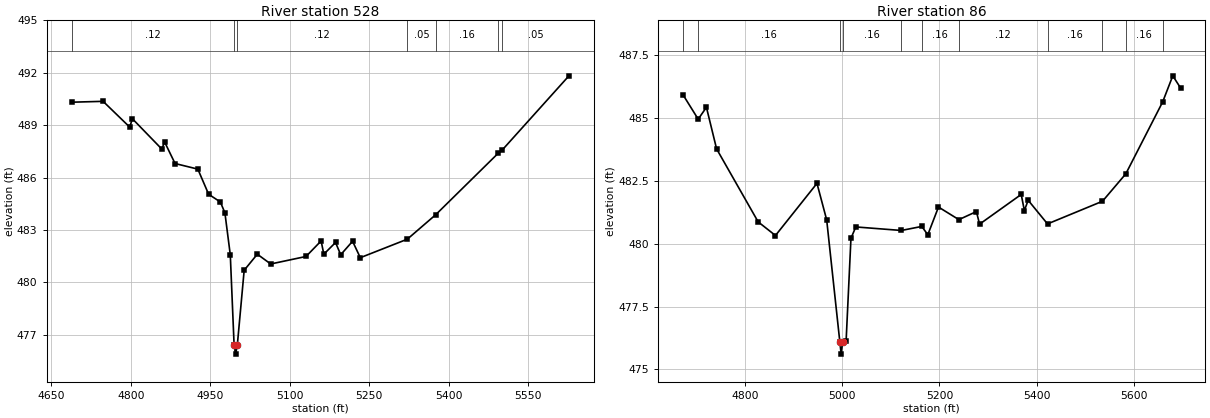
Type RM Length L Ch R = 1,528,442,442,442
BEGIN DESCRIPTION:
UNT005 IN STEL 2.0
END DESCRIPTION:
XS GIS Cut Line= 4
      3447378.13     10504247.06      3447593.40     10504326.92
      3447854.76     10504381.15      3448114.31     10504022.42
#Sta/Elev= 30
  4687.9  490.31  4747.5  490.36  4797.6  488.89  4802.9  489.36  4858.3  487.63
  4863.7  488.03  4883.4  486.80  4926.4  486.48  4946.8  485.04  4968.9  484.60
  4977.5  483.98  4987.7  481.57  4994.9  476.39  4997.6  475.89  5000.9  476.39
  5013.9  480.69  5038.7  481.61  5064.0  481.05  5130.7  481.48  5159.2  482.37
  5164.3  481.61  5186.4  482.28  5196.2  481.58  5218.6  482.35  5233.2  481.41
  5322.0  482.47  5375.6  483.87  5493.3  487.38  5500.5  487.55  5627.2  491.82
#Mann=7,-1,0
  4687.9    0.12       0  4994.9    0.07       0  5000.9    0.12       0
  5322.0    0.05       0  5375.6    0.16       0  5493.3    0.12       0
  5500.5    0.05       0
Bank Sta=4994.9,5000.9
Exp/Cntr=0.3,0.1

Type RM Length L Ch R = 1,86,0,0,0
BEGIN DESCRIPTION:
UNT005 IN STEL 1.0
END DESCRIPTION:
XS GIS Cut Line= 4
      3447329.47     10504507.45      3447510.07     10504639.42
      3447735.76     10504642.89      3448106.07     10504202.75
#Sta/Elev= 30
  4672.0  485.90  4703.0  484.94  4720.0  485.41  4740.9  483.76  4826.6  480.86
  4862.2  480.32  4947.7  482.39  4967.7  480.94  4994.7  476.11  4997.5  475.61
  5000.7  476.11  5007.7  476.12  5017.7  480.21  5027.7  480.66  5121.5  480.52
  5163.6  480.68  5176.0  480.35  5198.0  481.45  5240.0  480.95  5276.1  481.27
  5282.6  480.77  5368.4  481.95  5374.9  481.31  5382.7  481.72  5422.6  480.78
  5535.8  481.68  5583.9  482.77  5659.9  485.63  5680.6  486.66  5696.6  486.18
#Mann=11,-1,0
  4672.0    0.12       0  4703.0    0.16       0  4994.7    0.07       0
  5000.7    0.16       0  5121.5    0.12       0  5163.6    0.16       0
  5240.0    0.12       0  5422.6    0.16       0  5535.8    0.05       0
  5583.9    0.16       0  5659.9    0.05       0
Bank Sta=4994.7,5000.7
Exp/Cntr=0.3,0.1

Chan Stop Cuts=-1