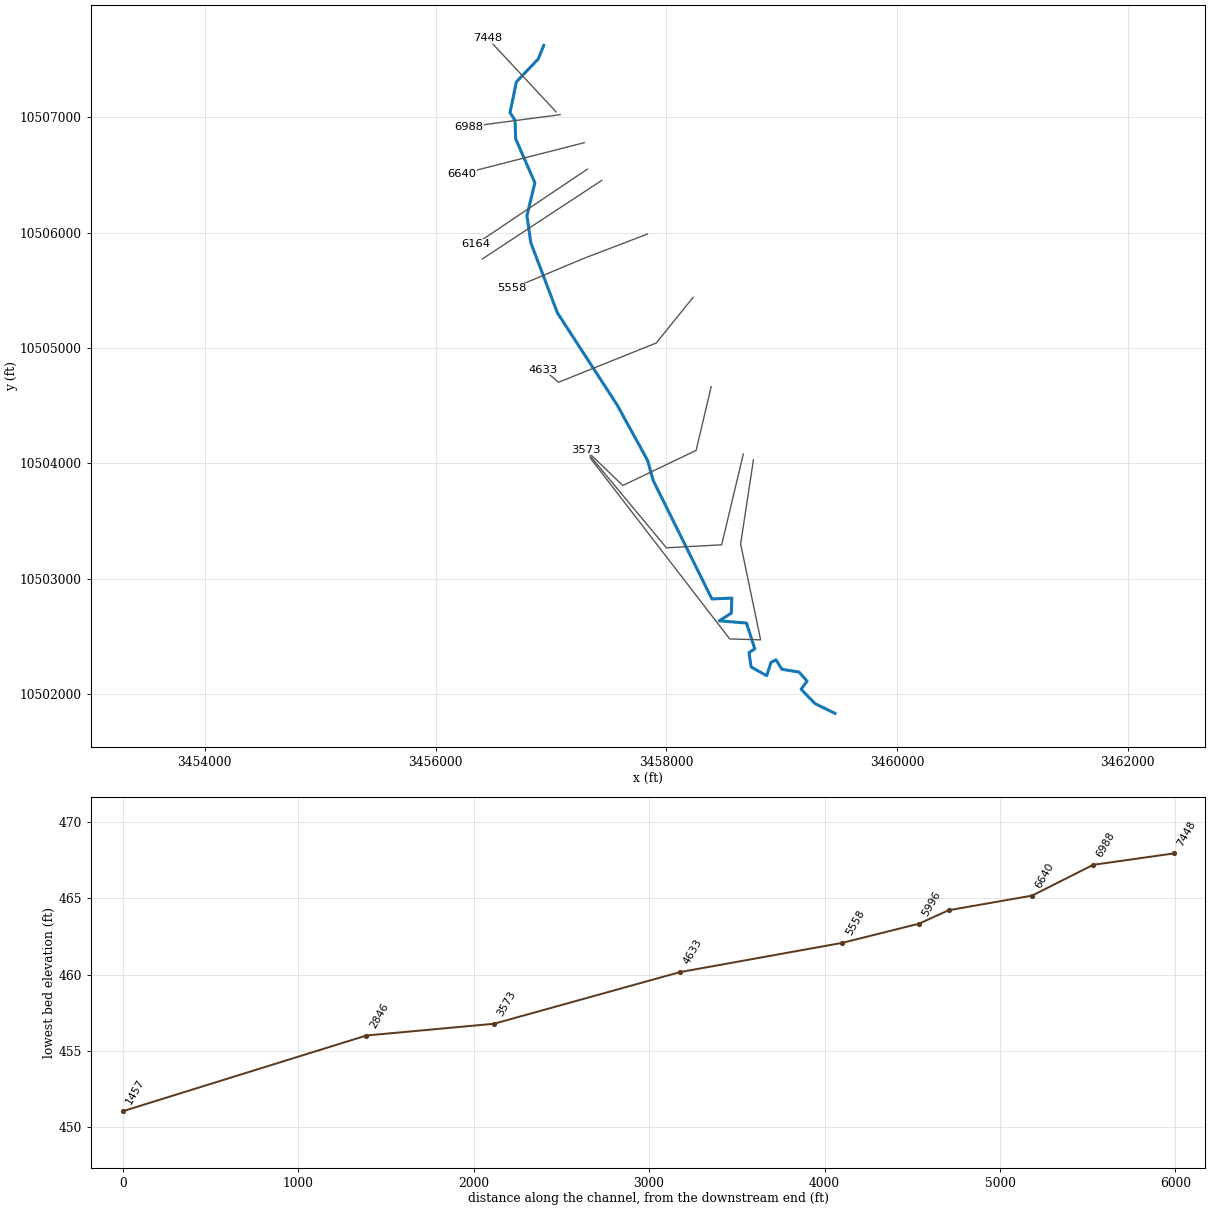
--- UNT007 IN STEL.prj (project) ---

Proj Title=UNT007 IN STEL Base Level Engineering
Current Plan=p01
Default Exp/Contr=0.3,0.1
English Units
Geom File=g01
Flow File=f01
Plan File=p01
BEGIN DESCRIPTION:
UNT007 IN STEL
END DESCRIPTION:

--- UNT007 IN STEL.p01 (plan) ---

Plan Title=Multiple Run
Short Identifier=Multiple
Geom File=g01
Flow File=f01
Subcritical Flow
K Sum by GR= 0
Std Step Tol= 0.01
Critical Tol= 0.01
Num of Std Step Trials= 20
Max Error Tol= 0.3
Flow Tol Ratio= 0.001
Split Flow NTrial= 30
Split Flow Tol= 0.02
Split Flow Ratio= 0.02
Log Output Level= 0
Friction Slope Method= 1
Unsteady Friction Slope Method= 2
Unsteady Bridges Friction Slope Method= 1
Parabolic Critical Depth
Global Vel Dist=  1 , 1 , 1
Global Log Level= 0
CheckData=True
Encroach Param= -1, 0, 0, 0
BEGIN DESCRIPTION:
Multiple Run
END DESCRIPTION:

--- UNT007 IN STEL.f01 (steady flow) ---

Flow Title=Multiple
Number of Profiles=7
Profile Names=10-year,25-year,50-year,1pct_min,100-year,1pct_plu,500-year
River Rch & RM= UNT007 IN STEL,Reach-1,7448
     773    1045    1264    1117    1510    2043    2149
River Rch & RM= UNT007 IN STEL,Reach-1,6640
    1006    1375    1677    1491    2017    2727    2908
Boundary for River Rch & Prof#=UNT007 IN STEL,Reach-1,1
Up Type=0
Dn Type=3
Dn Slope=0.005
Boundary for River Rch & Prof#=UNT007 IN STEL,Reach-1,2
Up Type=0
Dn Type=3
Dn Slope=0.005
Boundary for River Rch & Prof#=UNT007 IN STEL,Reach-1,3
Up Type=0
Dn Type=3
Dn Slope=0.005
Boundary for River Rch & Prof#=UNT007 IN STEL,Reach-1,4
Up Type=0
Dn Type=3
Dn Slope=0.005
Boundary for River Rch & Prof#=UNT007 IN STEL,Reach-1,5
Up Type=0
Dn Type=3
Dn Slope=0.005
Boundary for River Rch & Prof#=UNT007 IN STEL,Reach-1,6
Up Type=0
Dn Type=3
Dn Slope=0.005
Boundary for River Rch & Prof#=UNT007 IN STEL,Reach-1,7
Up Type=0
Dn Type=3
Dn Slope=0.005

--- UNT007 IN STEL.g01 (geometry) ---

Geom Title=Existing Conditions

River Reach=UNT007 IN STEL,Reach-1
Reach XY= 30
      3456937.86     10507621.05      3456890.13     10507504.11
      3456701.24     10507306.19      3456645.68     10507038.83
      3456689.67     10506972.45      3456694.49     10506812.76
      3456861.24     10506431.16      3456792.54     10506146.26
      3456825.58     10505912.71      3457056.36     10505304.01
      3457575.92     10504502.84      3457838.18     10504024.73
      3457887.49     10503849.16      3458395.77     10502823.43
      3458568.59     10502830.91      3458564.14     10502700.58
      3458459.81     10502634.07      3458695.52     10502614.40
      3458767.57     10502390.73      3458717.17     10502358.51
      3458735.77     10502233.88      3458870.97     10502158.24
      3458908.15     10502273.46      3458951.50     10502295.94
      3459002.72     10502213.63      3459151.28     10502189.42
      3459221.00     10502111.12      3459168.81     10502040.75
      3459289.25     10501916.59      3459462.11     10501831.64

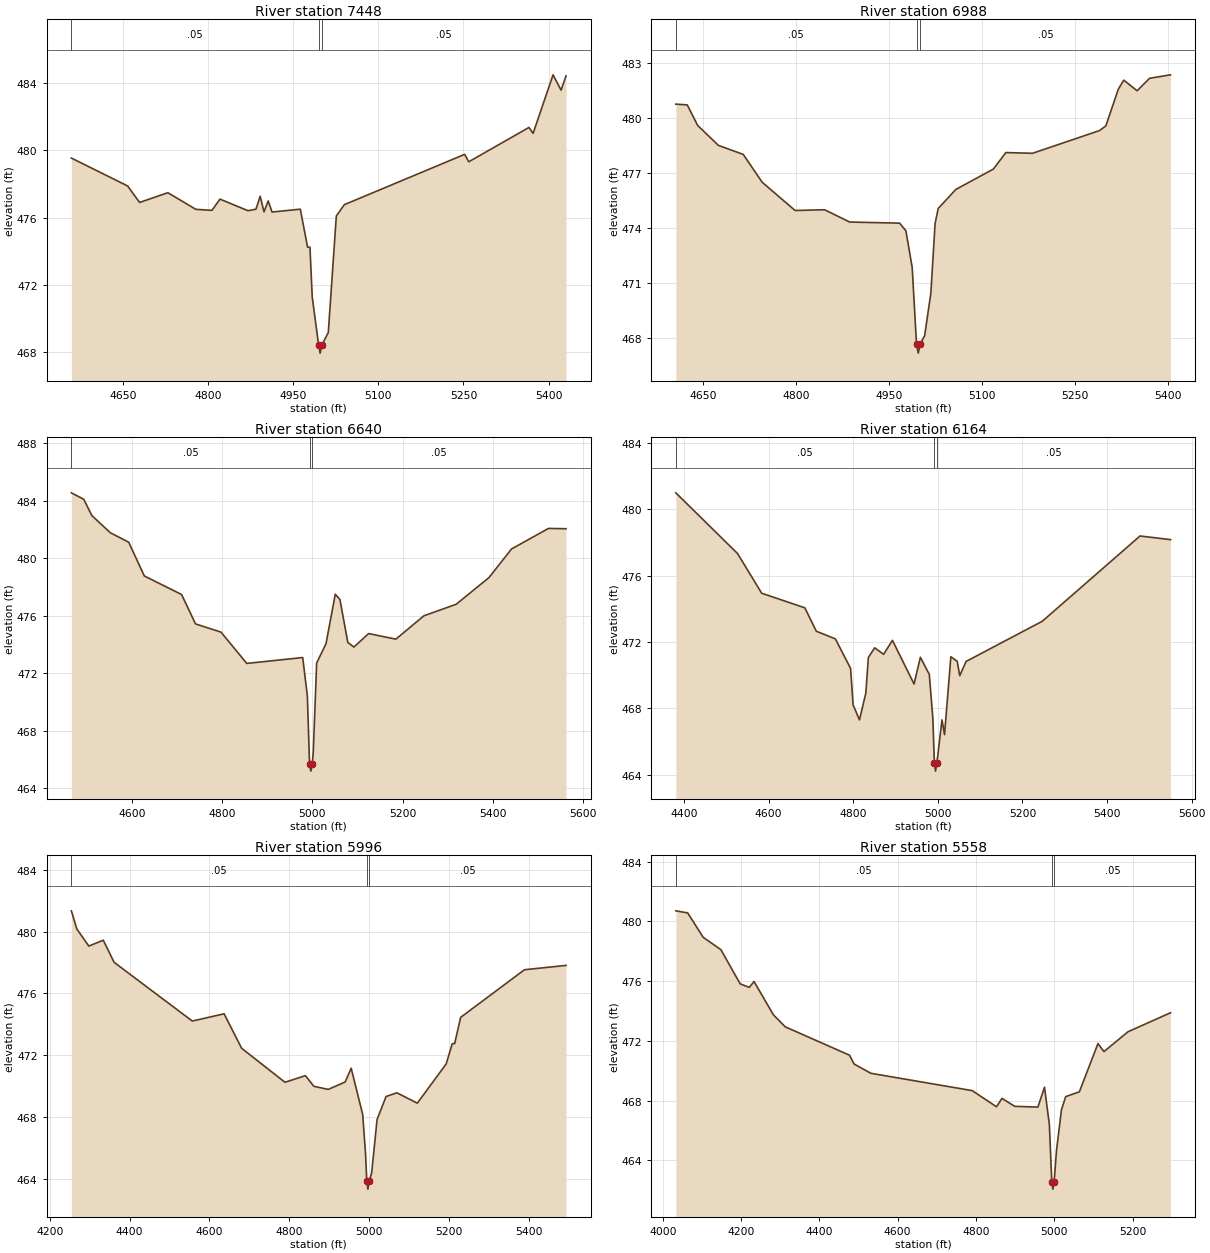
Type RM Length L Ch R = 1,7448,460,460,460
BEGIN DESCRIPTION:
UNT007 IN STEL 12.0
END DESCRIPTION:
XS GIS Cut Line= 3
      3457045.80     10507045.16      3456759.04     10507352.85
      3456451.21     10507683.15
#Sta/Elev= 30
  4558.8  479.55  4658.0  477.89  4679.0  476.91  4728.9  477.49  4778.2  476.50
  4806.6  476.44  4820.7  477.11  4870.1  476.42  4884.2  476.51  4891.6  477.28
  4898.4  476.35  4905.7  477.00  4912.6  476.34  4962.4  476.51  4975.2  474.25
  4979.4  474.25  4983.4  471.29  4994.6  468.45  4997.3  467.95  5000.6  468.45
  5011.7  469.17  5025.9  476.11  5040.1  476.78  5252.1  479.77  5259.4  479.33
  5365.5  481.37  5372.8  481.02  5408.0  484.50  5422.1  483.59  5430.9  484.44
#Mann=3,-1,0
  4558.8    0.05       0  4994.6    0.04       0  5000.6    0.05       0
Bank Sta=4994.6,5000.6
Exp/Cntr=0.3,0.1

Type RM Length L Ch R = 1,6988,348,348,348
BEGIN DESCRIPTION:
UNT007 IN STEL 11.0
END DESCRIPTION:
XS GIS Cut Line= 2
      3457080.30     10507021.45      3456288.62     10506917.29
#Sta/Elev= 30
  4606.2  480.78  4624.6  480.74  4641.4  479.62  4675.0  478.53  4715.0  478.04
  4745.6  476.52  4798.7  474.98  4846.4  475.02  4886.8  474.35  4967.5  474.29
  4977.6  473.87  4987.7  471.88  4994.7  467.70  4997.5  467.20  5000.7  467.70
  5007.8  468.15  5017.9  470.48  5024.7  474.27  5029.7  475.09  5058.3  476.13
  5118.8  477.24  5138.9  478.14  5182.0  478.10  5290.2  479.34  5300.3  479.59
  5320.5  481.60  5329.3  482.09  5350.8  481.51  5370.9  482.19  5404.7  482.38
#Mann=3,-1,0
  4606.2    0.05       0  4994.7    0.03       0  5000.7    0.05       0
Bank Sta=4994.7,5000.7
Exp/Cntr=0.3,0.1

Type RM Length L Ch R = 1,6640,476,476,476
BEGIN DESCRIPTION:
UNT007 IN STEL 10.0
END DESCRIPTION:
XS GIS Cut Line= 2
      3457288.69     10506778.41      3456226.65     10506507.69
#Sta/Elev= 30
  4466.1  484.56  4493.5  484.11  4511.4  482.98  4552.3  481.78  4593.1  481.12
  4627.7  478.77  4710.2  477.48  4741.2  475.43  4797.6  474.86  4854.7  472.68
  4978.6  473.09  4988.9  470.42  4993.8  465.68  4996.6  465.18  4999.8  465.68
  5002.0  466.49  5009.5  472.71  5030.2  474.05  5050.8  477.50  5061.1  477.13
  5078.6  474.14  5092.1  473.82  5124.6  474.76  5185.0  474.37  5247.3  476.00
  5318.7  476.80  5391.4  478.66  5441.3  480.65  5523.1  482.08  5562.1  482.06
#Mann=3,-1,0
  4466.1    0.05       0  4993.8   0.035       0  4999.8    0.05       0
Bank Sta=4993.8,4999.8
Exp/Cntr=0.3,0.1

Type RM Length L Ch R = 1,6164,168,168,168
BEGIN DESCRIPTION:
UNT007 IN STEL 9.0
END DESCRIPTION:
XS GIS Cut Line= 2
      3457316.41     10506549.22      3456345.80     10505897.52
#Sta/Elev= 30
  4380.9  480.99  4526.8  477.33  4583.8  474.94  4685.8  474.06  4712.9  472.65
  4757.9  472.19  4793.9  470.41  4799.9  468.21  4814.9  467.31  4829.9  468.92
  4835.9  471.07  4850.9  471.65  4871.9  471.26  4892.9  472.10  4943.9  469.47
  4958.9  471.08  4979.9  470.05  4988.3  467.43  4991.9  464.72  4994.7  464.22
  4997.9  464.72  5009.9  467.31  5015.9  466.42  5030.9  471.11  5045.9  470.84
  5051.9  469.97  5066.9  470.83  5247.0  473.25  5478.0  478.39  5550.0  478.17
#Mann=3,-1,0
  4380.9    0.05       0  4991.9    0.03       0  4997.9    0.05       0
Bank Sta=4991.9,4997.9
Exp/Cntr=0.3,0.1

Type RM Length L Ch R = 1,5996,438,438,438
BEGIN DESCRIPTION:
UNT007 IN STEL 8.0
END DESCRIPTION:
XS GIS Cut Line= 2
      3457441.45     10506452.02      3456406.86     10505771.56
#Sta/Elev= 30
  4254.5  481.34  4268.0  480.17  4298.1  479.06  4334.3  479.44  4361.4  478.01
  4557.2  474.21  4636.7  474.68  4680.7  472.45  4789.2  470.25  4840.2  470.68
  4861.5  469.99  4897.6  469.79  4939.8  470.27  4954.9  471.16  4983.8  468.16
  4991.0  465.56  4994.0  463.84  4996.7  463.34  5000.0  463.84  5006.1  464.38
  5019.7  467.84  5042.2  469.33  5069.3  469.57  5120.5  468.90  5192.8  471.44
  5207.9  472.75  5213.9  472.75  5229.0  474.45  5388.7  477.53  5492.8  477.81
#Mann=3,-1,0
  4254.5    0.05       0  4994.0    0.04       0  5000.0    0.05       0
Bank Sta=4994,5000
Exp/Cntr=0.3,0.1

Type RM Length L Ch R = 1,5558,925,925,925
BEGIN DESCRIPTION:
UNT007 IN STEL 7.0
END DESCRIPTION:
XS GIS Cut Line= 3
      3457837.26     10505986.73      3457274.76     10505771.46
      3456665.41     10505515.25
#Sta/Elev= 30
  4033.5  480.70  4063.8  480.56  4103.3  478.93  4148.6  478.10  4197.9  475.81
  4221.0  475.58  4233.3  475.97  4282.7  473.74  4312.8  472.94  4477.0  471.04
  4488.7  470.45  4531.6  469.83  4790.5  468.67  4852.4  467.59  4866.5  468.15
  4899.0  467.62  4958.2  467.57  4975.0  468.90  4987.4  466.41  4993.6  462.58
  4996.4  462.08  4999.6  462.58  5005.7  464.67  5018.3  467.39  5029.2  468.27
  5064.1  468.59  5111.6  471.82  5126.8  471.28  5188.3  472.61  5296.8  473.88
#Mann=3,-1,0
  4033.5    0.05       0  4993.6   0.035       0  4999.6    0.05       0
Bank Sta=4993.6,4999.6
Exp/Cntr=0.3,0.1

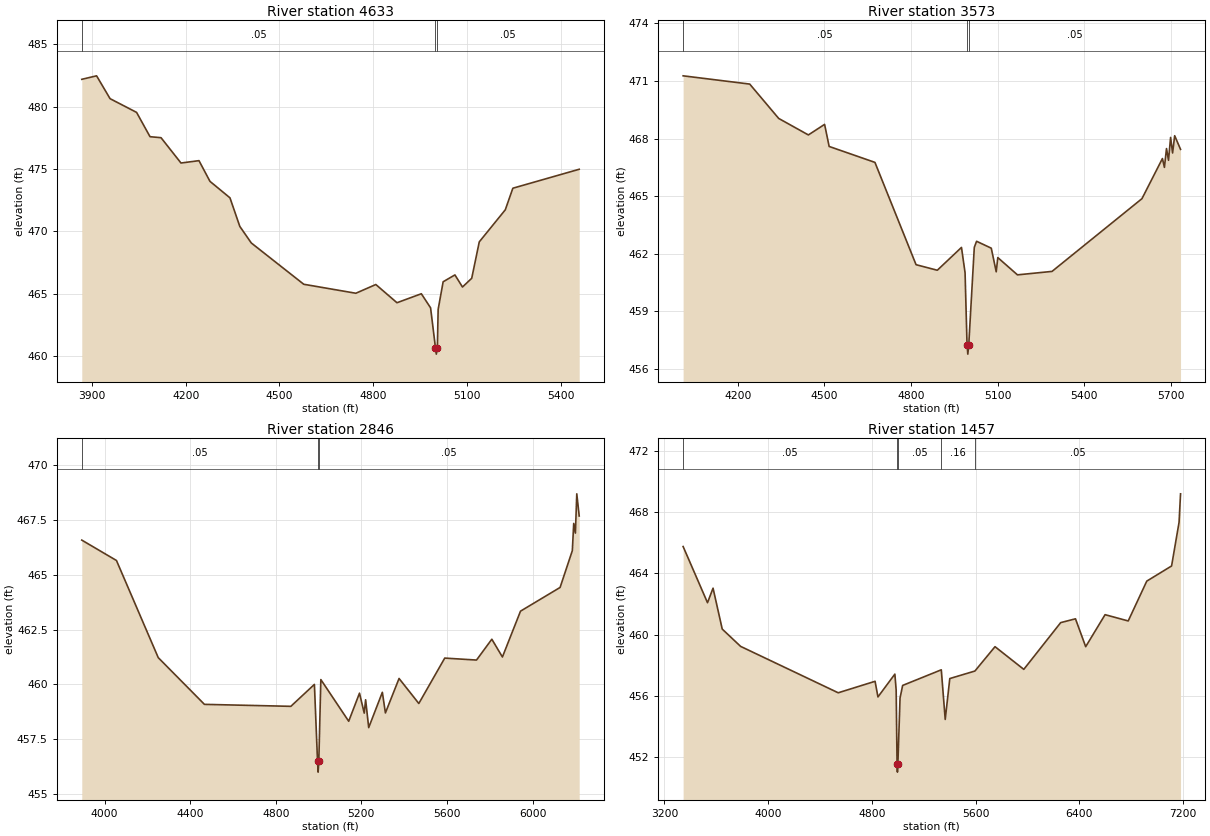
Type RM Length L Ch R = 1,4633,1060,1060,1060
BEGIN DESCRIPTION:
UNT007 IN STEL 5.0
END DESCRIPTION:
XS GIS Cut Line= 4
      3458233.11     10505438.15      3457913.65     10505042.29
      3457066.43     10504702.01      3456935.77     10504812.04
#Sta/Elev= 30
  3867.3  482.19  3914.7  482.47  3957.8  480.64  4042.7  479.54  4085.8  477.59
  4121.0  477.51  4184.9  475.48  4242.5  475.67  4277.7  474.01  4341.7  472.69
  4373.2  470.40  4410.0  469.07  4578.0  465.76  4744.7  465.04  4808.7  465.74
  4876.4  464.28  4954.4  465.00  4984.0  463.87  4999.7  460.66  5002.4  460.16
  5005.7  460.66  5008.2  463.74  5024.2  465.96  5061.9  466.51  5086.1  465.54
  5115.7  466.24  5139.9  469.16  5223.2  471.73  5247.4  473.46  5459.8  474.98
#Mann=3,-1,0
  3867.3    0.05       0  4999.7   0.035       0  5005.7    0.05       0
Bank Sta=4999.7,5005.7
Exp/Cntr=0.3,0.1

Type RM Length L Ch R = 1,3573,727,727,727
BEGIN DESCRIPTION:
UNT007 IN STEL 3.0
END DESCRIPTION:
XS GIS Cut Line= 4
      3458389.37     10504663.48      3458259.17     10504111.45
      3457623.75     10503806.76      3457299.62     10504117.93
#Sta/Elev= 30
  4011.4  471.27  4241.8  470.84  4342.1  469.05  4444.8  468.19  4500.9  468.74
  4516.7  467.59  4675.1  466.76  4817.4  461.43  4890.9  461.14  4974.6  462.33
  4987.0  461.01  4993.8  457.27  4996.5  456.77  4999.8  457.27  5018.9  462.33
  5026.8  462.65  5077.7  462.29  5094.8  461.06  5100.3  461.80  5168.3  460.90
  5287.9  461.08  5599.1  464.87  5669.9  466.96  5676.8  466.50  5684.0  467.48
  5691.0  466.87  5698.2  468.06  5705.1  467.25  5712.3  468.15  5732.6  467.44
#Mann=3,-1,0
  4011.4    0.05       0  4993.8   0.035       0  4999.8    0.05       0
Bank Sta=4993.8,4999.8
Exp/Cntr=0.3,0.1

Type RM Length L Ch R = 1,2846,1389,1389,1389
BEGIN DESCRIPTION:
UNT007 IN STEL 1.1
END DESCRIPTION:
XS GIS Cut Line= 4
      3458668.03     10504079.33      3458480.52     10503292.87
      3458001.36     10503266.83      3457339.04     10504064.27
#Sta/Elev= 30
  3893.2  466.58  4055.3  465.65  4250.6  461.22  4466.5  459.09  4870.4  459.00
  4980.5  460.00  4995.1  456.50  4997.9  456.00  5001.1  456.50  5010.6  460.22
  5140.8  458.32  5191.3  459.60  5213.4  458.69  5219.9  459.30  5234.3  458.03
  5298.1  459.64  5312.4  458.70  5376.2  460.27  5468.6  459.13  5589.7  461.20
  5738.2  461.11  5809.8  462.06  5859.3  461.25  5943.9  463.34  6128.8  464.42
  6186.1  466.10  6192.6  467.34  6200.4  466.90  6206.9  468.69  6218.2  467.68
#Mann=3,-1,0
  3893.2    0.05       0  4995.1   0.035       0  5001.1    0.05       0
Bank Sta=4995.1,5001.1
Exp/Cntr=0.3,0.1

Type RM Length L Ch R = 1,1457,0,0,0
BEGIN DESCRIPTION:
UNT007 IN STEL 1.0
END DESCRIPTION:
XS GIS Cut Line= 5
      3458755.87     10504029.84      3458644.76     10503300.68
      3458818.20     10502469.09      3458549.97     10502476.90
      3457340.74     10504046.38
#Sta/Elev= 30
  3343.8  465.76  3531.9  462.09  3574.6  463.04  3645.4  460.37  3787.1  459.24
  4540.1  456.21  4824.3  456.96  4846.5  455.94  4977.0  457.43  4987.0  456.39
  4994.0  451.53  4996.7  451.03  5000.0  451.53  5017.0  455.87  5037.0  456.69
  5335.1  457.71  5365.4  454.47  5400.7  457.14  5594.4  457.63  5749.5  459.22
  5971.5  457.74  6255.9  460.79  6370.1  461.04  6448.9  459.22  6598.4  461.31
  6776.9  460.90  6920.0  463.50  7111.4  464.49  7169.1  467.34  7180.5  469.20
#Mann=5,-1,0
  3343.8    0.05       0  4994.0   0.035       0  5000.0    0.05       0
  5335.1    0.16       0  5594.4    0.05       0
Bank Sta=4994,5000
Exp/Cntr=0.3,0.1

Chan Stop Cuts=-1