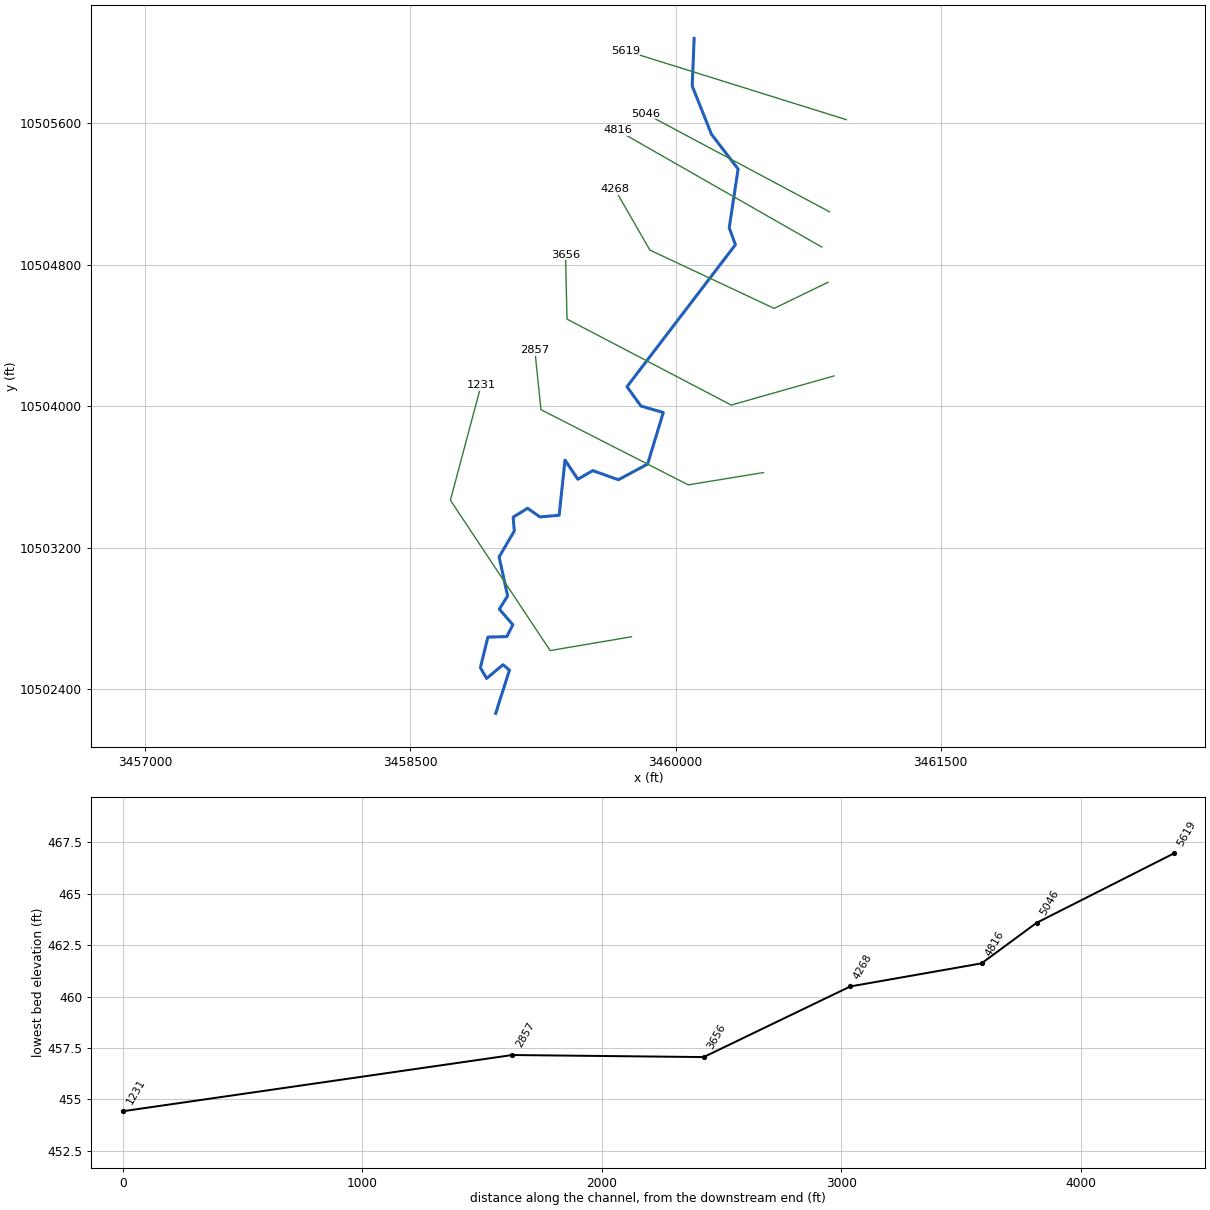
--- UNT008 IN STEL.prj (project) ---

Proj Title=UNT008 IN STEL Base Level Engineering
Current Plan=p01
Default Exp/Contr=0.3,0.1
English Units
Geom File=g01
Flow File=f01
Plan File=p01
BEGIN DESCRIPTION:
UNT008 IN STEL
END DESCRIPTION:

--- UNT008 IN STEL.p01 (plan) ---

Plan Title=Multiple Run
Short Identifier=Multiple
Geom File=g01
Flow File=f01
Subcritical Flow
K Sum by GR= 0
Std Step Tol= 0.01
Critical Tol= 0.01
Num of Std Step Trials= 20
Max Error Tol= 0.3
Flow Tol Ratio= 0.001
Split Flow NTrial= 30
Split Flow Tol= 0.02
Split Flow Ratio= 0.02
Log Output Level= 0
Friction Slope Method= 1
Unsteady Friction Slope Method= 2
Unsteady Bridges Friction Slope Method= 1
Parabolic Critical Depth
Global Vel Dist=  1 , 1 , 1
Global Log Level= 0
CheckData=True
Encroach Param= -1, 0, 0, 0
BEGIN DESCRIPTION:
Multiple Run
END DESCRIPTION:

--- UNT008 IN STEL.f01 (steady flow) ---

Flow Title=Multiple
Number of Profiles=7
Profile Names=10-year,25-year,50-year,1pct_min,100-year,1pct_plu,500-year
River Rch & RM= UNT008 IN STEL,Reach-1,5619
     979    1337    1628    1446    1955    2644    2813
Boundary for River Rch & Prof#=UNT008 IN STEL,Reach-1,1
Up Type=0
Dn Type=3
Dn Slope=0.005
Boundary for River Rch & Prof#=UNT008 IN STEL,Reach-1,2
Up Type=0
Dn Type=3
Dn Slope=0.005
Boundary for River Rch & Prof#=UNT008 IN STEL,Reach-1,3
Up Type=0
Dn Type=3
Dn Slope=0.005
Boundary for River Rch & Prof#=UNT008 IN STEL,Reach-1,4
Up Type=0
Dn Type=3
Dn Slope=0.005
Boundary for River Rch & Prof#=UNT008 IN STEL,Reach-1,5
Up Type=0
Dn Type=3
Dn Slope=0.005
Boundary for River Rch & Prof#=UNT008 IN STEL,Reach-1,6
Up Type=0
Dn Type=3
Dn Slope=0.005
Boundary for River Rch & Prof#=UNT008 IN STEL,Reach-1,7
Up Type=0
Dn Type=3
Dn Slope=0.005

--- UNT008 IN STEL.g01 (geometry) ---

Geom Title=Existing Conditions

River Reach=UNT008 IN STEL,Reach-1
Reach XY= 30
      3460104.95     10506080.47      3460094.03     10505810.30
      3460202.53     10505538.60      3460353.58     10505341.12
      3460303.44     10505008.65      3460338.43     10504912.96
      3459725.12     10504109.81      3459803.66     10504000.41
      3459930.40     10503963.51      3459841.52     10503671.92
      3459676.59     10503583.26      3459531.78     10503635.07
      3459447.08     10503586.13      3459374.39     10503694.73
      3459341.33     10503382.32      3459232.69     10503372.92
      3459163.04     10503421.85      3459081.01     10503371.93
      3459087.74     10503293.20      3459001.67     10503146.70
      3459049.69     10502926.07      3459002.88     10502851.42
      3459079.51     10502762.78      3459044.96     10502695.92
      3458938.23     10502693.00      3458895.73     10502520.56
      3458930.89     10502459.09      3459023.55     10502537.09
      3459060.30     10502506.51      3458982.11     10502261.64

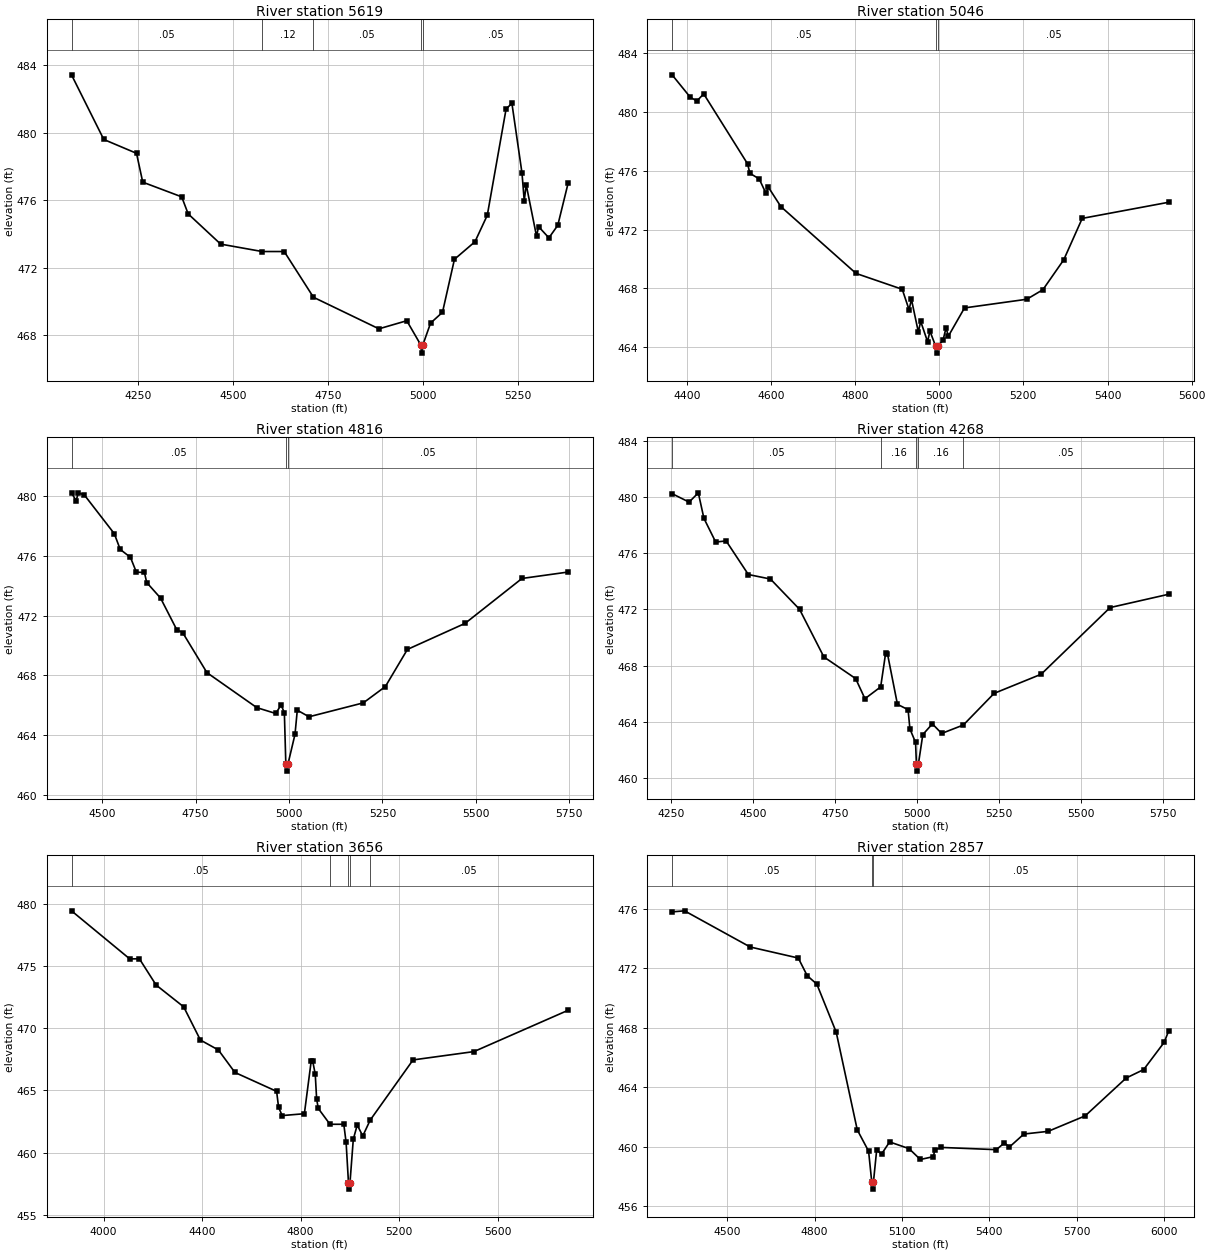
Type RM Length L Ch R = 1,5619,573,573,573
BEGIN DESCRIPTION:
UNT008 IN STEL 2.0
END DESCRIPTION:
XS GIS Cut Line= 2
      3460965.72     10505620.42      3459715.74     10506011.04
#Sta/Elev= 30
  4074.0  483.44  4159.1  479.61  4245.4  478.79  4261.8  477.08  4364.5  476.21
  4381.6  475.20  4467.2  473.41  4576.6  472.97  4634.8  472.97  4711.9  470.26
  4884.5  468.39  4957.9  468.87  4994.5  467.45  4997.2  466.95  5000.5  467.45
  5020.7  468.73  5052.1  469.37  5083.6  472.51  5137.7  473.55  5170.2  475.12
  5219.8  481.42  5235.1  481.75  5261.7  477.62  5267.6  475.98  5272.8  476.93
  5300.1  473.87  5305.3  474.45  5332.6  473.78  5356.0  474.52  5383.6  477.05
#Mann=5,-1,0
  4074.0    0.05       0  4576.6    0.12       0  4711.9    0.05       0
  4994.5   0.035       0  5000.5    0.05       0
Bank Sta=4994.5,5000.5
Exp/Cntr=0.3,0.1

Type RM Length L Ch R = 1,5046,230,230,230
BEGIN DESCRIPTION:
UNT008 IN STEL 3.0
END DESCRIPTION:
XS GIS Cut Line= 2
      3460870.29     10505099.56      3459828.58     10505655.13
#Sta/Elev= 30
  4365.1  482.54  4408.4  481.01  4424.0  480.76  4440.3  481.24  4544.4  476.48
  4550.1  475.83  4572.1  475.45  4588.3  474.46  4594.0  474.88  4623.7  473.56
  4802.3  469.01  4912.1  467.93  4928.3  466.54  4934.0  467.24  4950.3  465.03
  4956.0  465.74  4972.3  464.36  4977.9  465.08  4991.2  464.08  4994.0  463.58
  4997.2  464.08  5009.0  464.45  5016.2  465.30  5021.8  464.74  5060.1  466.66
  5208.1  467.25  5246.4  467.90  5296.0  469.94  5339.9  472.76  5545.7  473.86
#Mann=3,-1,0
  4365.1    0.05       0  4991.2   0.035       0  4997.2    0.05       0
Bank Sta=4991.2,4997.2
Exp/Cntr=0.3,0.1

Type RM Length L Ch R = 1,4816,548,548,548
BEGIN DESCRIPTION:
UNT008 IN STEL 4.0
END DESCRIPTION:
XS GIS Cut Line= 2
      3460826.85     10504899.92      3459672.35     10505559.64
#Sta/Elev= 30
  4417.6  480.20  4430.0  479.67  4435.7  480.19  4451.6  480.07  4532.2  477.47
  4548.0  476.42  4575.4  475.89  4591.2  474.90  4612.8  474.88  4618.9  474.21
  4656.0  473.17  4699.5  471.05  4715.0  470.87  4780.1  468.19  4913.7  465.85
  4964.4  465.46  4978.5  466.03  4987.4  465.52  4991.3  462.11  4994.1  461.61
  4997.3  462.11  5015.9  464.07  5022.0  465.68  5053.4  465.24  5198.8  466.17
  5257.8  467.26  5316.8  469.74  5471.2  471.48  5623.5  474.48  5747.3  474.91
#Mann=3,-1,0
  4417.6    0.05       0  4991.3    0.04       0  4997.3    0.05       0
Bank Sta=4991.3,4997.3
Exp/Cntr=0.3,0.1

Type RM Length L Ch R = 1,4268,612,612,612
BEGIN DESCRIPTION:
UNT008 IN STEL 6.0
END DESCRIPTION:
XS GIS Cut Line= 4
      3460861.60     10504700.29      3460557.75     10504552.71
      3459854.62     10504882.57      3459655.86     10505228.24
#Sta/Elev= 30
  4253.5  480.22  4305.3  479.62  4333.4  480.28  4350.4  478.47  4386.3  476.78
  4418.1  476.86  4485.8  474.47  4553.1  474.15  4641.7  472.00  4715.9  468.61
  4812.7  467.07  4841.0  465.64  4888.9  466.48  4904.0  468.87  4909.5  468.85
  4940.0  465.24  4972.4  464.86  4978.0  463.49  4995.2  462.53  4997.8  460.99
  5000.5  460.49  5003.8  460.99  5017.3  463.09  5046.4  463.85  5074.7  463.17
  5140.8  463.77  5234.5  466.02  5377.8  467.38  5587.7  472.12  5766.7  473.07
#Mann=5,-1,0
  4253.5    0.05       0  4888.9    0.16       0  4997.8    0.07       0
  5003.8    0.16       0  5140.8    0.05       0
Bank Sta=4997.8,5003.8
Exp/Cntr=0.3,0.1

Type RM Length L Ch R = 1,3656,799,799,799
BEGIN DESCRIPTION:
UNT008 IN STEL 5.0
END DESCRIPTION:
XS GIS Cut Line= 4
      3460896.25     10504170.75      3460314.69     10504005.83
      3459385.87     10504491.94      3459377.19     10504856.51
#Sta/Elev= 30
  3869.5  479.46  4106.1  475.59  4145.2  475.60  4213.0  473.49  4325.2  471.73
  4393.0  469.06  4466.1  468.26  4533.3  466.45  4702.6  464.93  4710.6  463.64
  4725.2  462.98  4815.3  463.13  4843.0  467.36  4849.4  467.34  4859.5  466.31
  4865.1  464.31  4871.9  463.55  4919.3  462.28  4975.5  462.28  4984.8  460.82
  4994.5  457.56  4997.3  457.06  5000.5  457.56  5014.0  461.07  5030.0  462.22
  5052.5  461.34  5082.8  462.62  5256.7  467.46  5504.0  468.13  5887.0  471.46
#Mann=5,-1,0
  3869.5    0.05       0  4919.3    0.16       0  4994.5    0.07       0
  5000.5    0.16       0  5082.8    0.05       0
Bank Sta=4994.5,5000.5
Exp/Cntr=0.3,0.1

Type RM Length L Ch R = 1,2857,1626,1626,1626
BEGIN DESCRIPTION:
UNT008 IN STEL 7.0
END DESCRIPTION:
XS GIS Cut Line= 4
      3460497.03     10503623.89      3460071.63     10503554.44
      3459238.30     10503979.79      3459203.67     10504317.48
#Sta/Elev= 30
  4310.6  475.78  4353.3  475.85  4579.0  473.42  4744.0  472.68  4774.8  471.49
  4807.7  470.93  4874.3  467.70  4946.6  461.14  4985.5  459.71  4996.3  457.66
  4999.1  457.16  5002.3  457.66  5013.3  459.79  5029.9  459.51  5057.7  460.33
  5124.4  459.88  5163.3  459.15  5207.7  459.34  5213.3  459.80  5235.6  459.96
  5424.4  459.81  5452.2  460.27  5468.8  459.98  5518.9  460.86  5602.2  461.04
  5729.4  462.08  5870.1  464.62  5930.4  465.19  6000.8  467.02  6016.7  467.81
#Mann=3,-1,0
  4310.6    0.05       0  4996.3   0.035       0  5002.3    0.05       0
Bank Sta=4996.3,5002.3
Exp/Cntr=0.3,0.1

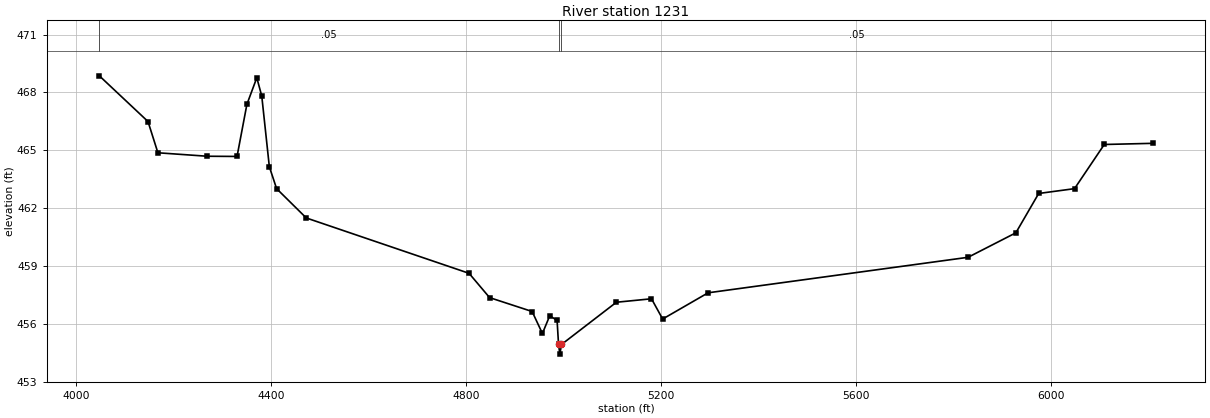
Type RM Length L Ch R = 1,1231,0,0,0
BEGIN DESCRIPTION:
UNT008 IN STEL 1.0
END DESCRIPTION:
XS GIS Cut Line= 4
      3459750.48     10502695.07      3459290.38     10502616.94
      3458726.15     10503467.64      3458899.48     10504117.64
#Sta/Elev= 30
  4047.9  468.86  4147.7  466.49  4168.0  464.87  4269.4  464.69  4330.3  464.68
  4350.5  467.38  4370.8  468.76  4381.0  467.81  4396.5  464.15  4411.4  463.01
  4472.3  461.49  4806.1  458.62  4848.2  457.36  4935.4  456.64  4956.5  455.50
  4971.5  456.42  4986.6  456.18  4989.6  454.93  4992.3  454.43  4995.6  454.93
  5108.2  457.12  5180.2  457.30  5203.1  456.25  5296.3  457.61  5829.3  459.45
  5927.4  460.72  5974.2  462.76  6047.7  463.01  6108.7  465.30  6208.1  465.36
#Mann=3,-1,0
  4047.9    0.05       0  4989.6   0.035       0  4995.6    0.05       0
Bank Sta=4989.6,4995.6
Exp/Cntr=0.3,0.1

Chan Stop Cuts=-1