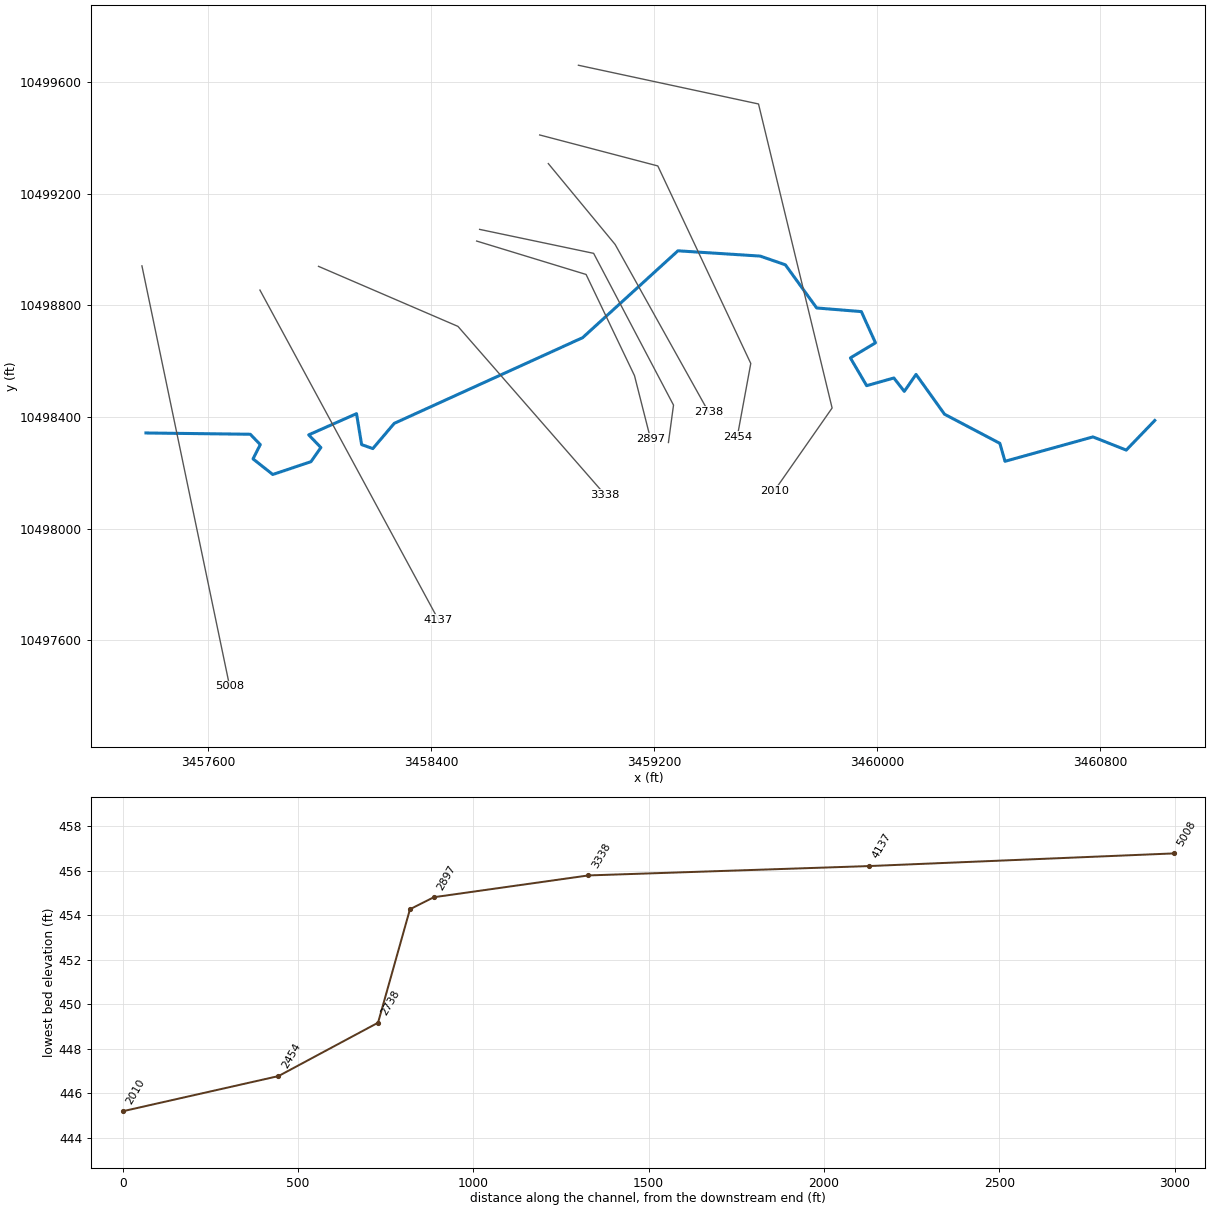
--- UNT009 IN STEL.prj (project) ---

Proj Title=UNT009 IN STEL Base Level Engineering
Current Plan=p01
Default Exp/Contr=0.3,0.1
English Units
Geom File=g01
Flow File=f01
Plan File=p01
BEGIN DESCRIPTION:
UNT009 IN STEL
END DESCRIPTION:

--- UNT009 IN STEL.p01 (plan) ---

Plan Title=Multiple Run
Short Identifier=Multiple
Geom File=g01
Flow File=f01
Subcritical Flow
K Sum by GR= 0
Std Step Tol= 0.01
Critical Tol= 0.01
Num of Std Step Trials= 20
Max Error Tol= 0.3
Flow Tol Ratio= 0.001
Split Flow NTrial= 30
Split Flow Tol= 0.02
Split Flow Ratio= 0.02
Log Output Level= 0
Friction Slope Method= 1
Unsteady Friction Slope Method= 2
Unsteady Bridges Friction Slope Method= 1
Parabolic Critical Depth
Global Vel Dist=  1 , 1 , 1
Global Log Level= 0
CheckData=True
Encroach Param= -1, 0, 0, 0
BEGIN DESCRIPTION:
Multiple Run
END DESCRIPTION:

--- UNT009 IN STEL.f01 (steady flow) ---

Flow Title=Multiple
Number of Profiles=7
Profile Names=10-year,25-year,50-year,1pct_min,100-year,1pct_plu,500-year
River Rch & RM= UNT009 IN STEL,Reach-1,5008
     977    1341    1639    1462    1977    2674    2868
Boundary for River Rch & Prof#=UNT009 IN STEL,Reach-1,1
Up Type=0
Dn Type=3
Dn Slope=0.005
Boundary for River Rch & Prof#=UNT009 IN STEL,Reach-1,2
Up Type=0
Dn Type=3
Dn Slope=0.005
Boundary for River Rch & Prof#=UNT009 IN STEL,Reach-1,3
Up Type=0
Dn Type=3
Dn Slope=0.005
Boundary for River Rch & Prof#=UNT009 IN STEL,Reach-1,4
Up Type=0
Dn Type=3
Dn Slope=0.005
Boundary for River Rch & Prof#=UNT009 IN STEL,Reach-1,5
Up Type=0
Dn Type=3
Dn Slope=0.005
Boundary for River Rch & Prof#=UNT009 IN STEL,Reach-1,6
Up Type=0
Dn Type=3
Dn Slope=0.005
Boundary for River Rch & Prof#=UNT009 IN STEL,Reach-1,7
Up Type=0
Dn Type=3
Dn Slope=0.005

--- UNT009 IN STEL.g01 (geometry) ---

Geom Title=Existing Conditions

River Reach=UNT009 IN STEL,Reach-1
Reach XY= 30
      3457377.23     10498342.67      3457751.16     10498338.09
      3457787.04     10498300.98      3457761.05     10498249.77
      3457831.78     10498193.84      3457968.74     10498239.67
      3458004.40     10498290.49      3457960.69     10498335.92
      3458132.16     10498411.92      3458150.46     10498301.10
      3458190.64     10498286.61      3458267.45     10498377.09
      3458943.15     10498684.53      3459284.75     10498995.93
      3459579.71     10498977.01      3459669.99     10498945.76
      3459782.28     10498790.94      3459942.43     10498777.92
      3459993.21     10498665.94      3459903.16     10498611.89
      3459961.53     10498512.30      3460059.05     10498539.85
      3460096.55     10498491.86      3460138.61     10498552.66
      3460240.74     10498409.95      3460439.21     10498305.47
      3460457.62     10498241.12      3460773.10     10498328.58
      3460892.44     10498281.32      3460994.71     10498387.52

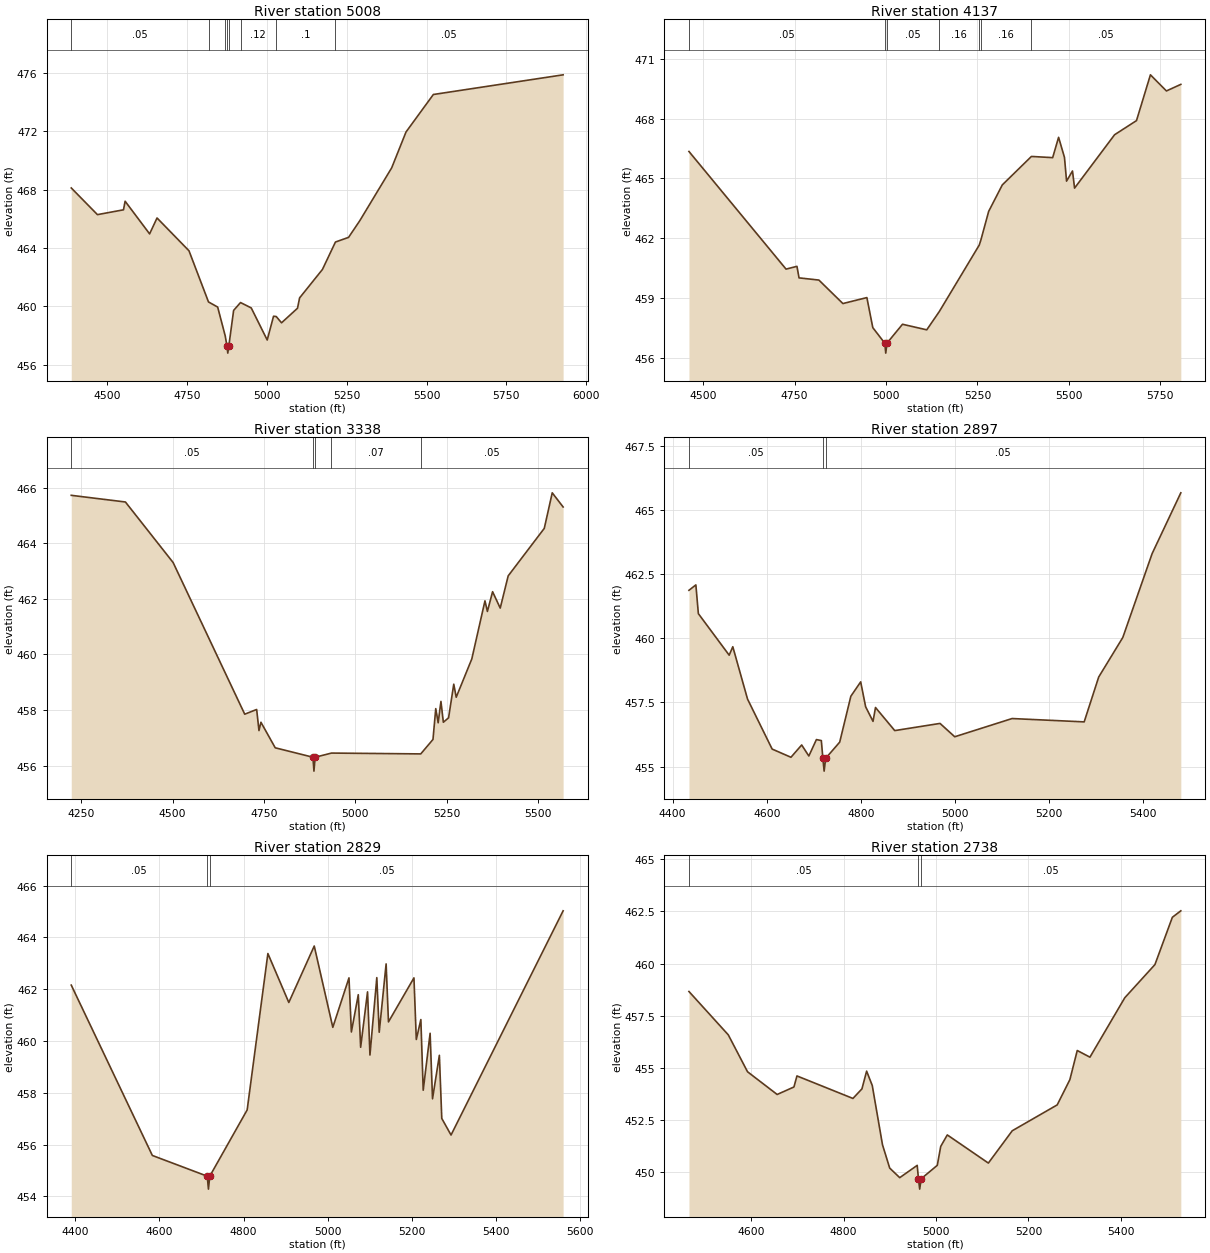
Type RM Length L Ch R = 1,5008,871,871,871
BEGIN DESCRIPTION:
UNT009 IN STEL 7.0
END DESCRIPTION:
XS GIS Cut Line= 2
      3457362.67     10498941.90      3457677.34     10497433.67
#Sta/Elev= 30
  4387.1  468.12  4469.1  466.29  4550.7  466.62  4555.8  467.21  4632.5  464.97
  4655.8  466.06  4755.9  463.81  4817.0  460.30  4845.7  459.95  4869.4  457.97
  4874.7  457.29  4877.4  456.79  4880.7  457.29  4895.7  459.72  4917.3  460.26
  4950.9  459.89  5000.9  457.69  5020.7  459.32  5029.1  459.30  5045.8  458.87
  5095.8  459.87  5102.4  460.58  5173.9  462.53  5214.6  464.41  5255.7  464.73
  5290.8  465.87  5390.8  469.50  5435.7  471.96  5521.3  474.53  5927.8  475.88
#Mann=8,-1,0
  4387.1    0.05       0  4817.0     0.1       0  4869.4    0.05       0
  4874.7    0.07       0  4880.7    0.05       0  4917.3    0.12       0
  5029.1     0.1       0  5214.6    0.05       0
Bank Sta=4874.7,4880.7
Exp/Cntr=0.3,0.1

Type RM Length L Ch R = 1,4137,799,799,799
BEGIN DESCRIPTION:
Mapping XS 0e02534f
END DESCRIPTION:
XS GIS Cut Line= 2
      3457785.84     10498855.12      3458426.04     10497672.38
#Sta/Elev= 30
  4461.1  466.35  4726.6  460.44  4756.4  460.58  4762.1  460.00  4816.4  459.89
  4882.0  458.71  4947.6  459.01  4963.8  457.50  4996.5  456.72  4999.2  456.22
  5002.5  456.72  5045.0  457.67  5111.3  457.39  5145.7  458.31  5254.9  461.65
  5259.6  461.92  5280.6  463.34  5317.9  464.67  5397.5  466.10  5455.6  466.04
  5471.8  467.06  5487.9  466.05  5493.6  464.86  5509.8  465.37  5515.5  464.51
  5624.9  467.19  5684.8  467.90  5722.9  470.20  5766.6  469.39  5806.0  469.72
#Mann=7,-1,0
  4461.1    0.05       0  4996.5   0.035       0  5002.5    0.05       0
  5145.7    0.16       0  5254.9    0.05       0  5259.6    0.16       0
  5397.5    0.05       0
Bank Sta=4996.5,5002.5
Exp/Cntr=0.3,0.1

Type RM Length L Ch R = 1,3338,441,441,441
BEGIN DESCRIPTION:
UNT009 IN STEL 6.0
END DESCRIPTION:
XS GIS Cut Line= 3
      3457995.92     10498940.18      3458495.92     10498724.91
      3459023.69     10498120.74
#Sta/Elev= 30
  4222.6  465.73  4370.9  465.49  4501.5  463.31  4697.5  457.85  4730.2  458.02
  4736.5  457.26  4741.9  457.56  4781.0  456.64  4884.3  456.30  4887.0  455.80
  4890.3  456.30  4935.0  456.45  5179.4  456.42  5212.9  456.94  5220.5  458.05
  5227.1  457.54  5234.7  458.31  5241.3  457.56  5255.6  457.72  5269.8  458.93
  5276.5  458.46  5319.2  459.84  5355.2  461.93  5361.9  461.55  5376.1  462.26
  5397.0  461.67  5418.8  462.83  5517.6  464.54  5539.4  465.82  5569.2  465.31
#Mann=5,-1,0
  4222.6    0.05       0  4884.3    0.07       0  4890.3    0.05       0
  4935.0    0.07       0  5179.4    0.05       0
Bank Sta=4884.3,4890.3
Exp/Cntr=0.3,0.1

Type RM Length L Ch R = 1,2897,68,68,68
BEGIN DESCRIPTION:
UNT009 IN STEL 5.0
END DESCRIPTION:
XS GIS Cut Line= 4
      3458562.99     10499030.91      3458955.38     10498911.11
      3459129.00     10498548.26      3459186.29     10498322.54
#Sta/Elev= 30
  4434.7  461.87  4449.4  462.08  4454.7  460.96  4520.2  459.34  4527.9  459.67
  4559.2  457.63  4611.5  455.68  4651.5  455.36  4674.3  455.84  4689.5  455.41
  4705.6  456.05  4716.1  456.01  4719.3  455.32  4722.0  454.82  4725.3  455.32
  4755.1  455.95  4778.8  457.74  4799.7  458.30  4810.2  457.33  4825.9  456.76
  4831.2  457.30  4872.1  456.40  4968.3  456.68  4999.6  456.16  5121.5  456.87
  5274.7  456.74  5305.6  458.49  5356.8  460.03  5419.1  463.30  5480.1  465.67
#Mann=3,-1,0
  4434.7    0.05       0  4719.3   0.033       0  4725.3    0.05       0
Bank Sta=4719.3,4725.3
Exp/Cntr=0.3,0.1

Type RM Length L Ch R = 1,2829,91,91,91
BEGIN DESCRIPTION:
UNT009 IN STEL 4.0
END DESCRIPTION:
XS GIS Cut Line= 4
      3458573.61     10499072.78      3458982.46     10498986.84
      3459268.92     10498442.57      3459250.69     10498308.44
#Sta/Elev= 30
  4390.8  462.16  4583.4  455.58  4713.8  454.78  4716.6  454.28  4719.8  454.78
  4808.6  457.34  4857.8  463.38  4907.5  461.49  4967.9  463.67  5012.0  460.53
  5050.4  462.44  5056.1  460.35  5072.5  461.79  5078.1  459.76  5094.5  461.90
  5100.2  459.46  5116.5  462.45  5122.2  460.34  5138.6  462.98  5144.2  460.74
  5204.7  462.44  5210.3  460.06  5221.1  460.83  5226.7  458.10  5243.1  460.30
  5248.8  457.77  5265.1  459.45  5270.8  457.01  5292.8  456.37  5559.0  465.03
#Mann=3,-1,0
  4390.8    0.05       0  4713.8   0.035       0  4719.8    0.05       0
Bank Sta=4713.8,4719.8
Exp/Cntr=0.3,0.1

Type RM Length L Ch R = 1,2738,284,284,284
BEGIN DESCRIPTION:
UNT009 IN STEL 3.0
END DESCRIPTION:
XS GIS Cut Line= 4
      3458819.96     10499308.69      3459059.55     10499018.75
      3459345.49     10498506.13      3459394.60     10498418.10
#Sta/Elev= 30
  4465.7  458.66  4550.8  456.58  4592.4  454.81  4656.5  453.72  4692.8  454.08
  4699.3  454.61  4820.4  453.53  4839.9  453.99  4850.0  454.84  4862.2  454.15
  4884.3  451.31  4899.9  450.19  4921.6  449.73  4959.4  450.32  4962.1  449.68
  4964.8  449.18  4968.1  449.68  5002.8  450.32  5010.3  451.23  5024.5  451.78
  5113.3  450.43  5165.0  451.98  5262.2  453.22  5289.6  454.43  5305.6  455.83
  5333.0  455.51  5408.4  458.36  5473.6  459.95  5511.3  462.22  5529.6  462.53
#Mann=3,-1,0
  4465.7    0.05       0  4962.1   0.035       0  4968.1    0.05       0
Bank Sta=4962.1,4968.1
Exp/Cntr=0.3,0.1

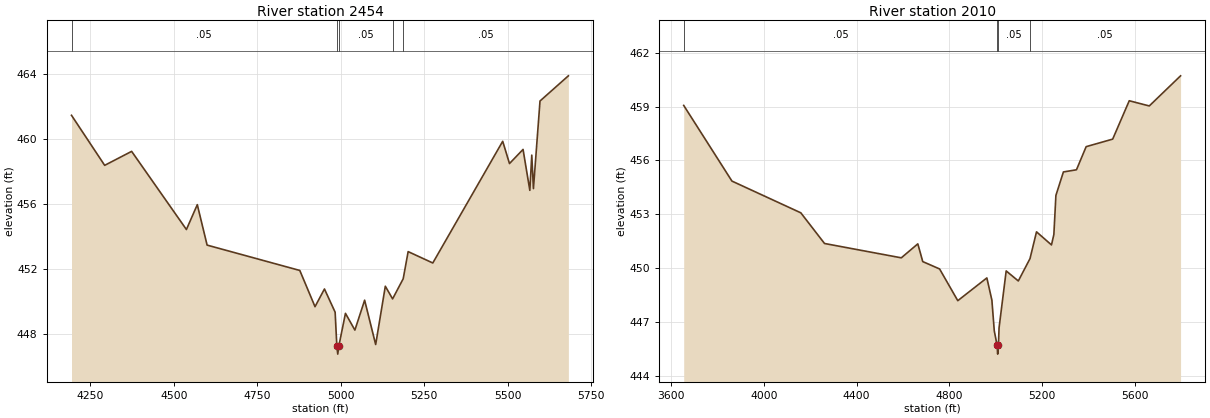
Type RM Length L Ch R = 1,2454,444,444,444
BEGIN DESCRIPTION:
UNT009 IN STEL 2.0
END DESCRIPTION:
XS GIS Cut Line= 4
      3458789.01     10499411.37      3459212.62     10499300.26
      3459545.95     10498591.93      3459497.35     10498328.05
#Sta/Elev= 30
  4193.3  461.48  4292.7  458.40  4373.5  459.26  4537.7  454.45  4570.3  455.98
  4599.7  453.49  4877.5  451.93  4923.1  449.70  4951.4  450.79  4983.4  449.36
  4988.5  447.28  4991.2  446.78  4994.5  447.28  5014.3  449.29  5042.6  448.26
  5071.8  450.10  5104.9  447.37  5133.8  450.96  5155.6  450.18  5187.4  451.42
  5202.2  453.09  5276.1  452.39  5485.6  459.88  5505.9  458.51  5546.6  459.38
  5566.9  456.86  5572.7  459.03  5577.7  456.97  5597.4  462.36  5682.4  463.91
#Mann=5,-1,0
  4193.3    0.05       0  4988.5   0.035       0  4994.5    0.05       0
  5155.6    0.16       0  5187.4    0.05       0
Bank Sta=4988.5,4994.5
Exp/Cntr=0.3,0.1

Type RM Length L Ch R = 1,2010,0,0,0
BEGIN DESCRIPTION:
UNT009 IN STEL 1.0
END DESCRIPTION:
XS GIS Cut Line= 4
      3458927.93     10499661.37      3459573.73     10499522.49
      3459837.62     10498432.21      3459630.34     10498135.10
#Sta/Elev= 30
  3653.9  459.07  3862.1  454.85  4159.4  453.08  4261.7  451.37  4593.1  450.57
  4664.4  451.35  4685.7  450.36  4758.4  449.95  4836.9  448.18  4962.4  449.45
  4984.1  448.21  4994.4  446.50  5006.4  445.70  5009.1  445.20  5012.4  445.70
  5015.0  446.66  5045.8  449.84  5098.2  449.28  5148.7  450.53  5176.7  452.02
  5241.3  451.29  5251.6  451.87  5260.4  454.05  5292.8  455.36  5349.2  455.48
  5391.0  456.77  5505.5  457.19  5577.0  459.33  5663.4  459.04  5798.5  460.72
#Mann=4,-1,0
  3653.9    0.05       0  5006.4   0.035       0  5012.4    0.05       0
  5148.7    0.05       0
Bank Sta=5006.4,5012.4
Exp/Cntr=0.3,0.1

Chan Stop Cuts=-1