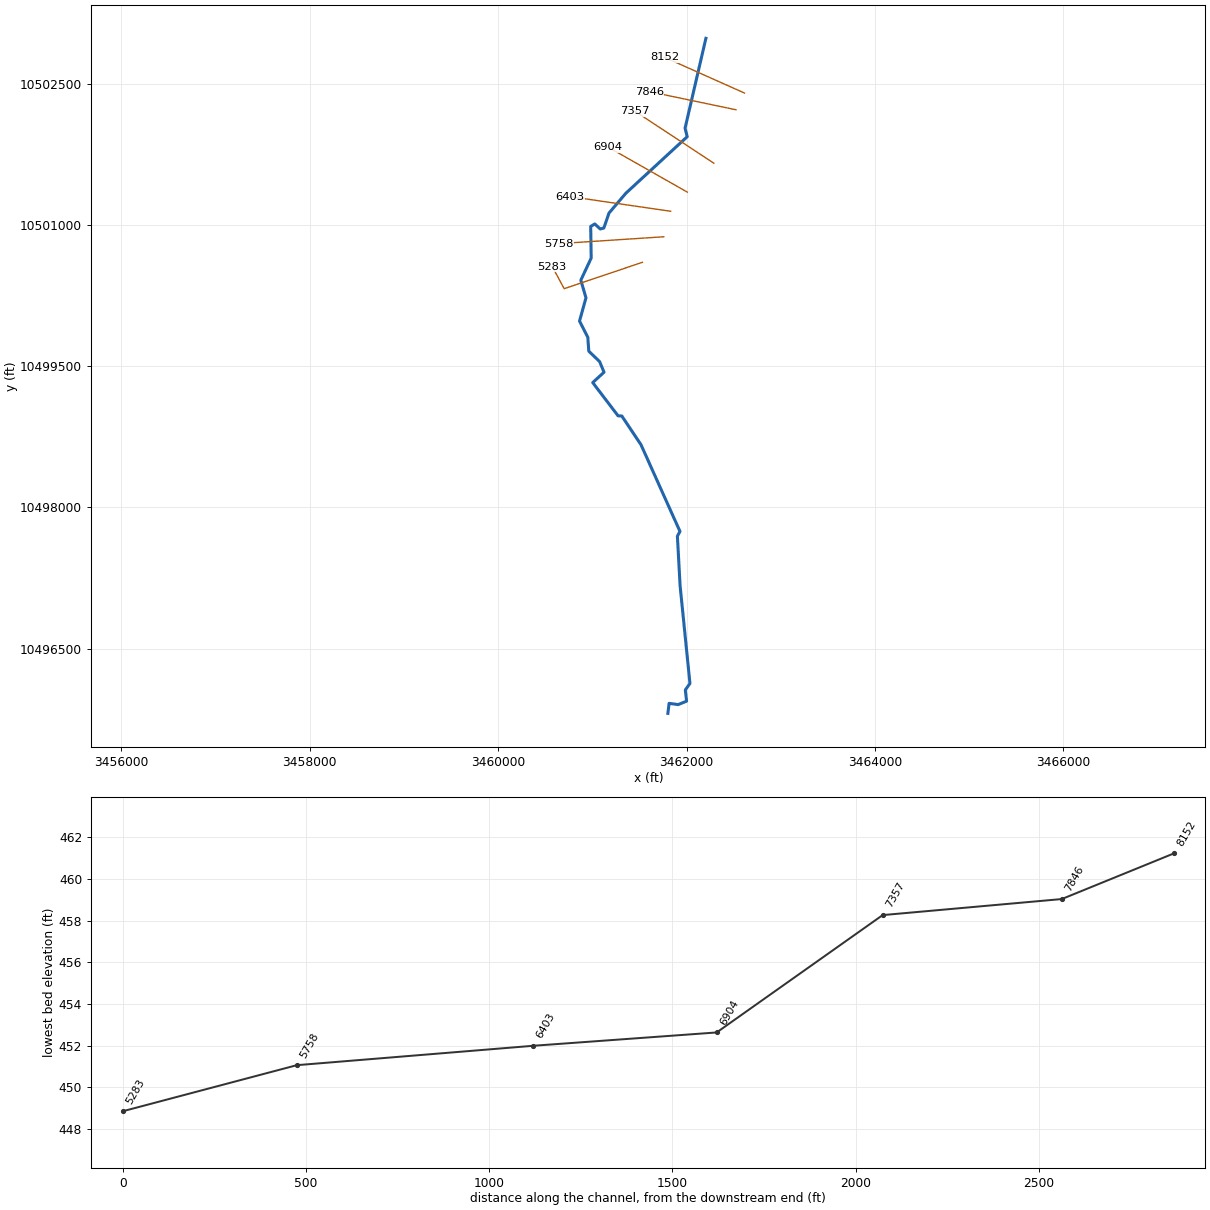
--- UNT010 IN STEL.prj (project) ---

Proj Title=UNT010 IN STEL Base Level Engineering
Current Plan=p01
Default Exp/Contr=0.3,0.1
English Units
Geom File=g01
Flow File=f01
Plan File=p01
Y Axis Title=Elevation
X Axis Title(PF)=Main Channel Distance
X Axis Title(XS)=Station
BEGIN DESCRIPTION:
UNT010 IN STEL
END DESCRIPTION:
DSS Export Rating Curves= 0
DSS Export Rating Curve Sorted= 0
DSS Export Volume Flow Curves= 0
DXF OffsetX= 0
DXF OffsetY= 0
DXF ScaleX= 1
DXF ScaleY= 10

--- UNT010 IN STEL.p01 (plan) ---

Plan Title=Multiple Run
Short Identifier=Multiple
Geom File=g01
Flow File=f01
Subcritical Flow
K Sum by GR= 0
Std Step Tol= 0.01
Critical Tol= 0.01
Num of Std Step Trials= 20
Max Error Tol= 0.3
Flow Tol Ratio= 0.001
Split Flow NTrial= 30
Split Flow Tol= 0.02
Split Flow Ratio= 0.02
Log Output Level= 0
Friction Slope Method= 1
Unsteady Friction Slope Method= 2
Unsteady Bridges Friction Slope Method= 1
Parabolic Critical Depth
Global Vel Dist=  1 , 1 , 1
Global Log Level= 0
CheckData=True
Encroach Param= -1, 0, 0, 0
BEGIN DESCRIPTION:
Multiple Run
END DESCRIPTION:

--- UNT010 IN STEL.f01 (steady flow) ---

Flow Title=Multiple
Number of Profiles=7
Profile Names=10-year,25-year,50-year,1pct_min,100-year,1pct_plu,500-year
River Rch & RM= UNT010 IN STEL,Reach-1,8152
     842    1139    1380    1219    1648    2229    2347
Boundary for River Rch & Prof#=UNT010 IN STEL,Reach-1,1
Up Type=0
Dn Type=3
Dn Slope=0.005
Boundary for River Rch & Prof#=UNT010 IN STEL,Reach-1,2
Up Type=0
Dn Type=3
Dn Slope=0.005
Boundary for River Rch & Prof#=UNT010 IN STEL,Reach-1,3
Up Type=0
Dn Type=3
Dn Slope=0.005
Boundary for River Rch & Prof#=UNT010 IN STEL,Reach-1,4
Up Type=0
Dn Type=3
Dn Slope=0.005
Boundary for River Rch & Prof#=UNT010 IN STEL,Reach-1,5
Up Type=0
Dn Type=3
Dn Slope=0.005
Boundary for River Rch & Prof#=UNT010 IN STEL,Reach-1,6
Up Type=0
Dn Type=3
Dn Slope=0.005
Boundary for River Rch & Prof#=UNT010 IN STEL,Reach-1,7
Up Type=0
Dn Type=3
Dn Slope=0.005

--- UNT010 IN STEL.g01 (geometry) ---

Geom Title=Existing Conditions
Program Version=4.10

River Reach=UNT010 IN STEL  ,Reach-1
Reach XY= 30
       3462205.8     10502979.88      3461984.67     10502025.86
      3462007.35     10501935.37      3461355.79     10501335.04
       3461176.8     10501124.41      3461122.31     10500965.69
       3461083.9      10500955.3      3461025.69     10501008.92
      3460982.41      10500982.2      3460987.85     10500646.72
      3460877.74      10500411.6      3460932.35      10500224.7
      3460863.92     10499977.48      3460951.88     10499805.43
      3460962.29     10499657.42      3461076.88     10499547.61
       3461124.1     10499434.84      3461003.87     10499324.16
       3461273.4      10498971.3       3461312.9     10498969.56
      3461516.89       10498664.      3461930.52     10497743.87
      3461903.18     10497693.08      3461931.82     10497167.04
      3462036.42     10496129.28      3461987.21     10496060.56
      3462000.92     10495941.29      3461911.07     10495904.84
      3461815.15     10495918.38      3461802.11     10495811.64

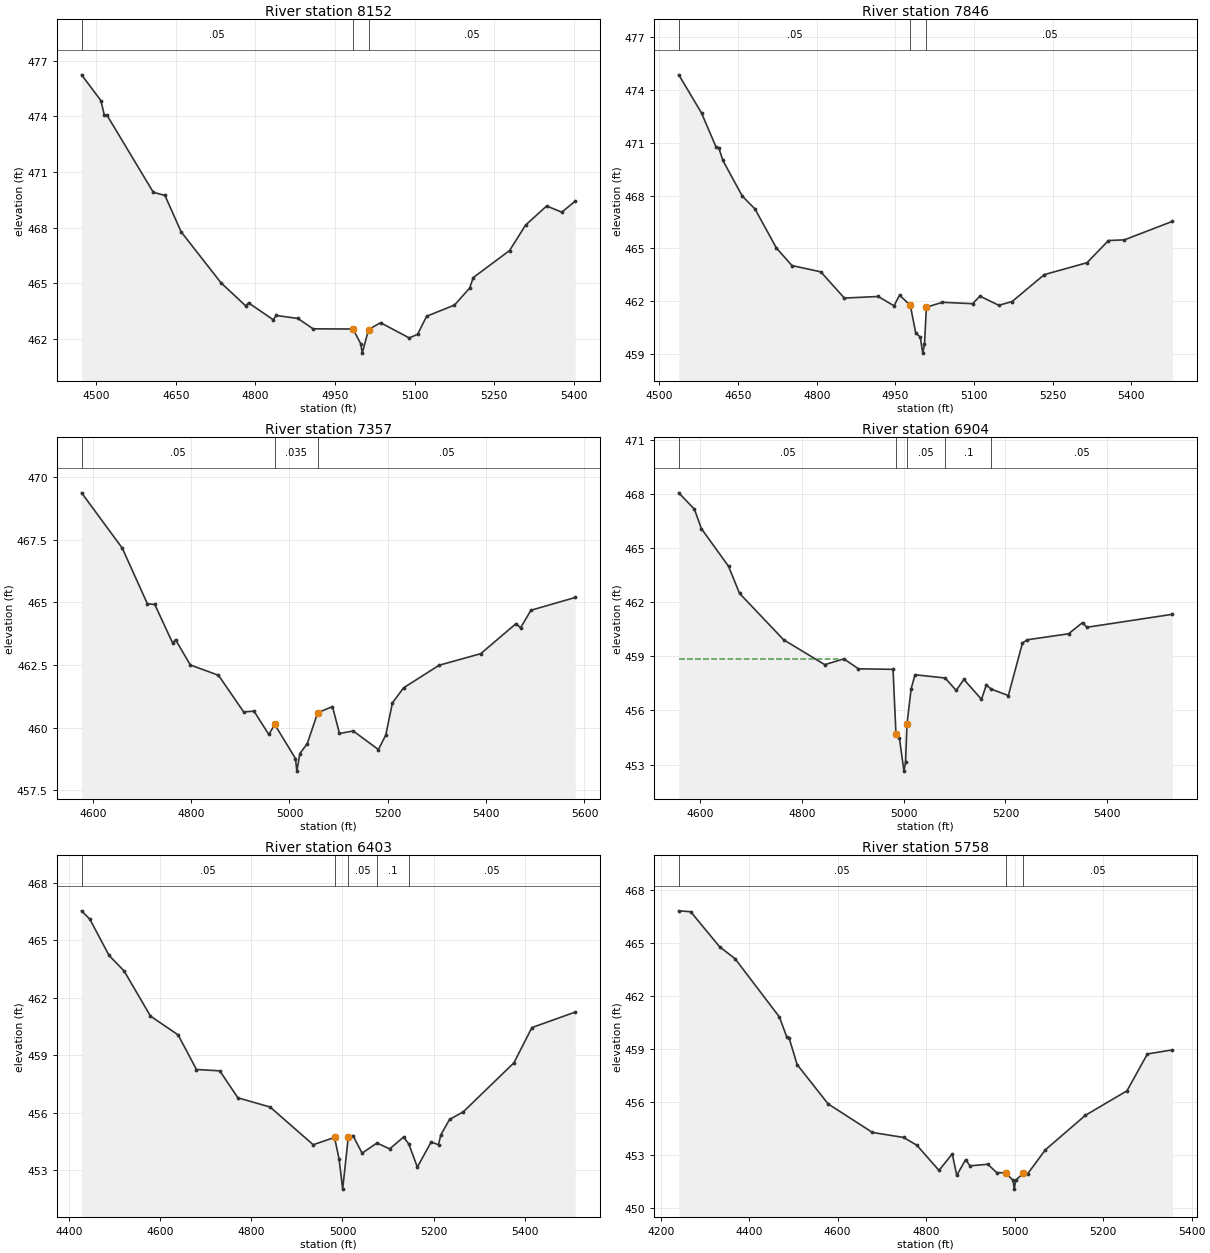
Type RM Length L Ch R = 1 ,8152    ,306,306,306
BEGIN DESCRIPTION:
UNT010 IN STEL 10.0
END DESCRIPTION:
XS GIS Cut Line= 2
      3462615.38     10502398.97      3461766.74     10502778.15
#Sta/Elev= 30
  4472.8  476.23  4509.2  474.84  4515.4  474.08  4520.9  474.04  4607.8   469.9
  4629.7  469.73  4660.2  467.77  4735.3  465.02  4781.7  463.78  4787.2  463.94
  4833.6  463.03  4839.1  463.26    4880   463.1  4908.7  462.54  4983.8  462.53
  4998.5  461.73  5001.3  461.23  5013.1   462.5  5035.7  462.87  5089.7  462.05
  5105.3  462.24  5122.6  463.22  5174.9  463.82  5203.6  464.74  5210.2   465.3
  5278.7  466.76  5308.8  468.13  5348.4  469.16    5377  468.83  5402.3  469.42
#Mann= 3 , 0 , 0
  4472.8     .05       0  4983.8    .035       0  5013.1     .05       0
Bank Sta=4983.8,5013.1
XS Rating Curve= 0 ,0
Exp/Cntr=0.3,0.1

Type RM Length L Ch R = 1 ,7846    ,489,489,489
BEGIN DESCRIPTION:
Mapping XS e56ccea0
END DESCRIPTION:
XS GIS Cut Line= 2
      3462524.54     10502221.65      3461602.67     10502414.35
#Sta/Elev= 30
  4536.8  474.86  4580.2  472.69  4607.9  470.76    4613  470.72    4621  469.99
  4657.9  467.97  4682.3  467.23  4723.2  465.01  4752.7  464.02  4807.8  463.66
  4852.7  462.17  4917.3  462.26  4947.5  461.73  4958.1  462.34  4978.6  461.75
  4988.8   460.2  4997.5  459.95  5002.3  459.04  5005.6  459.54  5009.2  461.65
  5039.9  461.93  5097.4  461.85  5111.4  462.28  5147.4  461.76  5172.7  461.97
    5234   463.5  5315.7  464.18  5356.6  465.44  5387.1  465.48  5478.6  466.53
#Mann= 3 , 0 , 0
  4536.8     .05       0  4978.6    .035       0  5009.2     .05       0
Bank Sta=4978.6,5009.2
XS Rating Curve= 0 ,0
Exp/Cntr=0.3,0.1

Type RM Length L Ch R = 1 ,7357    ,453,453,453
BEGIN DESCRIPTION:
Mapping XS 763af538
END DESCRIPTION:
XS GIS Cut Line= 2
      3462290.16     10501653.93      3461451.59     10502206.03
#Sta/Elev= 30
  4577.2  469.36  4659.8  467.16    4711  464.94  4726.1  464.91  4762.2  463.38
  4768.2  463.51  4798.4   462.5  4855.6  462.09  4906.8  460.63  4927.9  460.66
    4958  459.73    4970  460.13  5012.2  458.77    5015  458.27  5021.2  458.97
  5036.3  459.37  5057.4   460.6  5087.5  460.84  5101.7  459.77  5129.6  459.87
  5180.9  459.13  5195.9  459.71  5209.4  460.99  5232.1  461.59  5304.4  462.49
    5389  462.95  5460.9  464.15    5470  463.98  5491.1  464.68  5581.2  465.19
#Mann= 3 , 0 , 0
  4577.2     .05       0    4970    .035       0  5057.4     .05       0
Bank Sta=4970,5057.4
XS Rating Curve= 0 ,0
Exp/Cntr=0.3,0.1

Type RM Length L Ch R = 1 ,6904    ,501,501,501
BEGIN DESCRIPTION:
Mapping XS 36fdc6ee
END DESCRIPTION:
XS GIS Cut Line= 2
      3462008.92     10501346.63      3461166.14     10501825.25
#Sta/Elev= 30
  4558.6  468.06  4589.4  467.15  4602.9  466.08  4656.3  463.99  4677.9  462.49
  4764.4  459.92  4845.2  458.54  4882.7  458.86  4911.4  458.31  4979.3  458.28
    4985  454.72  4991.9  454.46  5000.7  452.64  5003.9  453.14  5006.7  455.27
  5014.9  457.21  5022.5  457.98  5081.7   457.8  5103.3  457.11  5118.4  457.72
  5152.9  456.62  5162.4  457.41  5172.3  457.18  5205.7  456.83  5233.4  459.74
  5243.2  459.92  5323.9  460.25  5351.3  460.87  5359.9  460.61  5527.8  461.33
#Mann= 5 ,-1 , 0
  4558.6     .05       0    4985    .035       0  5006.7     .05       0
  5081.7      .1       0  5172.3     .05       0
#XS Ineff= 2 , 0
         4875.91  458.85
Permanent Ineff=
       F       F
Bank Sta=4985,5006.7
XS Rating Curve= 0 ,0
Exp/Cntr=0.3,0.1

Type RM Length L Ch R = 1 ,6403    ,645,645,645
BEGIN DESCRIPTION:
Mapping XS 52b3ee36
END DESCRIPTION:
XS GIS Cut Line= 2
      3461831.79     10501143.53       3460758.9     10501299.77
#Sta/Elev= 30
    4427  466.54  4445.2   466.1  4487.3  464.21  4520.3   463.4  4578.3  461.04
  4638.9  460.06  4679.3  458.25  4730.5  458.18  4770.3  456.77    4841  456.29
  4935.7  454.32  4982.5   454.7  4992.6  453.57  5000.4     452  5012.8  454.73
  5022.9   454.8  5043.1  453.88  5075.8  454.41  5103.7   454.1  5134.1  454.72
  5145.9  454.35  5164.4  453.15  5194.7  454.46  5210.9  454.32  5215.9  454.83
  5235.1  455.64  5265.4  456.04  5376.6   458.6    5416  460.44  5511.2  461.25
#Mann= 5 ,-1 , 0
    4427     .05       0  4982.5    .035       0  5012.8     .05       0
  5075.8      .1       0  5145.9     .05       0
Bank Sta=4982.5,5012.8
XS Rating Curve= 0 ,0
Exp/Cntr=0.3,0.1

Type RM Length L Ch R = 1 ,5758    ,475,475,475
BEGIN DESCRIPTION:
Mapping XS 707d913a
END DESCRIPTION:
XS GIS Cut Line= 2
      3461758.93      10500872.7      3460645.71     10500799.87
#Sta/Elev= 30
  4240.9  466.84  4267.8  466.79  4333.3   464.8    4368  464.13  4468.2  460.83
    4485  459.69    4490  459.66  4508.3  458.13  4578.4   455.9  4678.7  454.28
  4748.8     454  4778.9  453.56    4829  452.13    4859  453.07  4869.1  451.85
  4889.1  452.74  4899.1  452.39  4939.2  452.48  4959.3  452.01  4979.3  451.99
  4996.3  451.57  4999.1  451.07  5002.3  451.57  5019.4  451.97  5029.4  451.94
  5069.5   453.3  5159.7  455.25  5253.8  456.64    5300  458.73  5356.5  458.96
#Mann= 3 , 0 , 0
  4240.9     .05       0  4979.3    .035       0  5019.4     .05       0
Bank Sta=4979.3,5019.4
XS Rating Curve= 0 ,0
Exp/Cntr=0.3,0.1

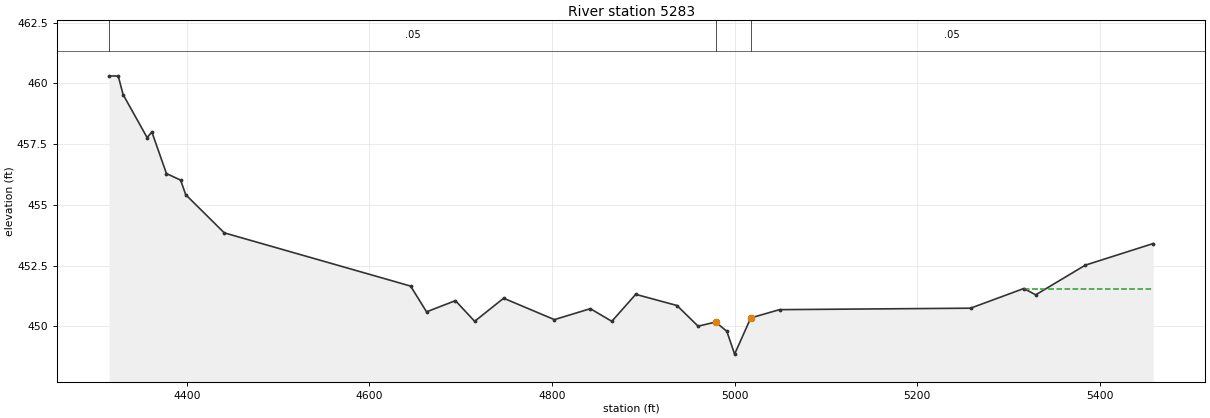
Type RM Length L Ch R = 1 ,5283    ,0,0,0
BEGIN DESCRIPTION:
UNT010 IN STEL 1.0
END DESCRIPTION:
XS GIS Cut Line= 3
      3461531.59     10500601.56      3460700.61     10500321.56
      3460574.16     10500556.39
#Sta/Elev= 30
    4315  460.31    4325   460.3  4330.3  459.54  4356.6  457.77  4361.8     458
  4377.8  456.29  4393.3  456.02  4398.9  455.42  4441.1  453.85  4645.2  451.66
  4662.7   450.6  4694.3  451.06  4715.4  450.21  4747.1  451.16  4802.7  450.28
  4842.1  450.73  4865.6  450.21  4891.8  451.32    4937  450.86  4960.1  450.01
  4979.3  450.18  4991.6   449.8  5000.1  448.86  5017.8  450.35  5049.3  450.69
  5258.5  450.75  5316.9  451.56  5329.9   451.3  5384.2  452.52  5458.6  453.41
#Mann= 3 , 0 , 0
    4315     .05       0  4979.3    .035       0  5017.8     .05       0
#XS Ineff= 2 , 0
                         5316.82          451.56
Permanent Ineff=
       F       F
Bank Sta=4979.3,5017.8
XS Rating Curve= 0 ,0
Exp/Cntr=0.3,0.1

Chan Stop Cuts=-1
Use User Specified Reach Order=0
Composite Channel Slope=5