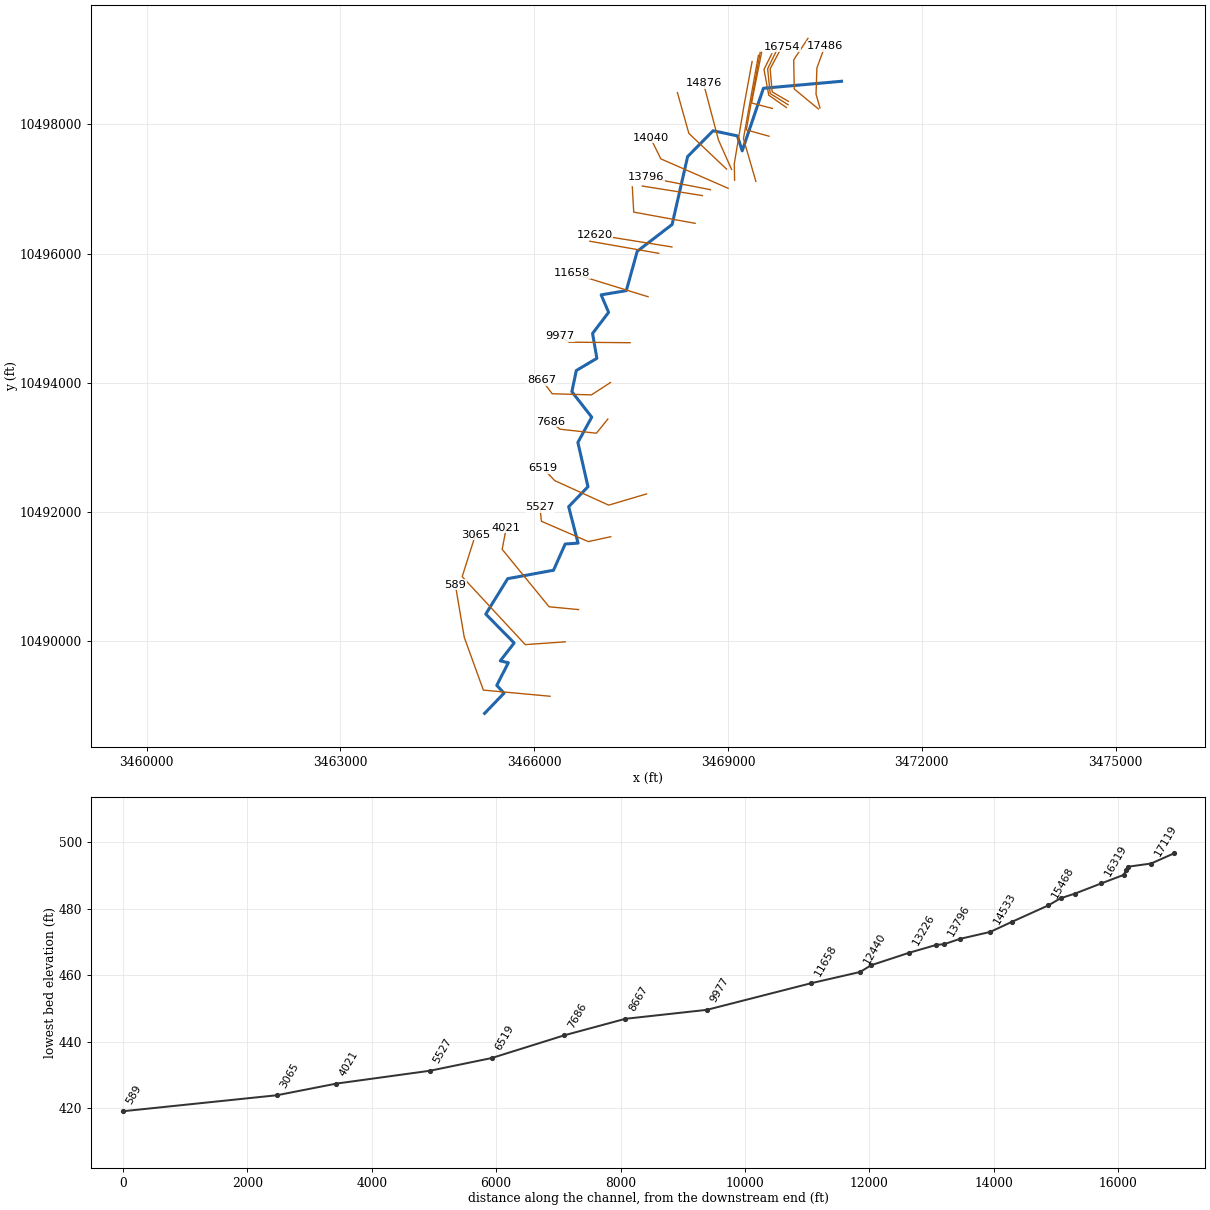
--- UNT013 IN STEL.prj (project) ---

Proj Title=UNT013 IN STEL Base Level Engineering
Current Plan=p01
Default Exp/Contr=0.3,0.1
English Units
Geom File=g01
Flow File=f01
Plan File=p01
Y Axis Title=Elevation
X Axis Title(PF)=Main Channel Distance
X Axis Title(XS)=Station
BEGIN DESCRIPTION:
UNT013 IN STEL
END DESCRIPTION:
DSS Export Rating Curves= 0
DSS Export Rating Curve Sorted= 0
DSS Export Volume Flow Curves= 0
DXF OffsetX= 0
DXF OffsetY= 0
DXF ScaleX= 1
DXF ScaleY= 10

--- UNT013 IN STEL.p01 (plan) ---

Plan Title=Multiple Run
Short Identifier=Multiple
Geom File=g01
Flow File=f01
Subcritical Flow
K Sum by GR= 0
Std Step Tol= 0.01
Critical Tol= 0.01
Num of Std Step Trials= 20
Max Error Tol= 0.3
Flow Tol Ratio= 0.001
Split Flow NTrial= 30
Split Flow Tol= 0.02
Split Flow Ratio= 0.02
Log Output Level= 0
Friction Slope Method= 1
Unsteady Friction Slope Method= 2
Unsteady Bridges Friction Slope Method= 1
Parabolic Critical Depth
Global Vel Dist=  1 , 1 , 1
Global Log Level= 0
CheckData=True
Encroach Param= -1, 0, 0, 0
BEGIN DESCRIPTION:
Multiple Run
END DESCRIPTION:

--- UNT013 IN STEL.f01 (steady flow) ---

Flow Title=Multiple
Program Version=4.10
Number of Profiles= 7
Profile Names=10-year,25-year,50-year,1pct_min,100-year,1pct_plu,500-year
River Rch & RM=UNT013 IN STEL,Reach-1         ,17486
     632     842    1009     882    1193    1614    1666
River Rch & RM=UNT013 IN STEL,Reach-1         ,6519
    1111    1527    1868    1665    2252    3045    3266
Boundary for River Rch & Prof#=UNT013 IN STEL,Reach-1         , 1
Up Type= 0
Dn Type= 3
Dn Slope=0.005
Boundary for River Rch & Prof#=UNT013 IN STEL,Reach-1         , 2
Up Type= 0
Dn Type= 3
Dn Slope=0.005
Boundary for River Rch & Prof#=UNT013 IN STEL,Reach-1         , 3
Up Type= 0
Dn Type= 3
Dn Slope=0.005
Boundary for River Rch & Prof#=UNT013 IN STEL,Reach-1         , 4
Up Type= 0
Dn Type= 3
Dn Slope=0.005
Boundary for River Rch & Prof#=UNT013 IN STEL,Reach-1         , 5
Up Type= 0
Dn Type= 3
Dn Slope=0.005
Boundary for River Rch & Prof#=UNT013 IN STEL,Reach-1         , 6
Up Type= 0
Dn Type= 3
Dn Slope=0.005
Boundary for River Rch & Prof#=UNT013 IN STEL,Reach-1         , 7
Up Type= 0
Dn Type= 3
Dn Slope=0.005
DSS Import GetInterval= 0
DSS Import GetPeak= 0
DSS Import FillOption= 0

--- UNT013 IN STEL.g01 (geometry) ---

Geom Title=Existing Conditions
Program Version=4.10

River Reach=UNT013 IN STEL  ,Reach-1
Reach XY= 30
      3470757.11     10498666.64      3469548.03     10498558.08
      3469219.12     10497589.24      3469145.27     10497821.26
      3468768.53     10497900.26      3468375.03     10497501.31
      3468134.56     10496449.33      3467594.46      10496034.4
      3467425.46     10495425.16       3467035.9     10495360.19
      3467151.75      10495090.3      3466903.14     10494762.53
      3466969.74     10494377.49       3466651.4     10494188.91
        3466583.     10493860.79      3466890.28     10493467.29
      3466676.05      10493076.7      3466831.98     10492390.04
      3466533.04      10492080.8      3466678.84     10491517.12
      3466479.09     10491503.15      3466299.14     10491097.57
      3465589.66     10490967.07      3465249.93     10490417.98
      3465689.88     10489971.77      3465474.05      10489694.5
      3465599.42     10489665.99      3465420.26     10489315.55
      3465532.78     10489194.56      3465232.11     10488881.64

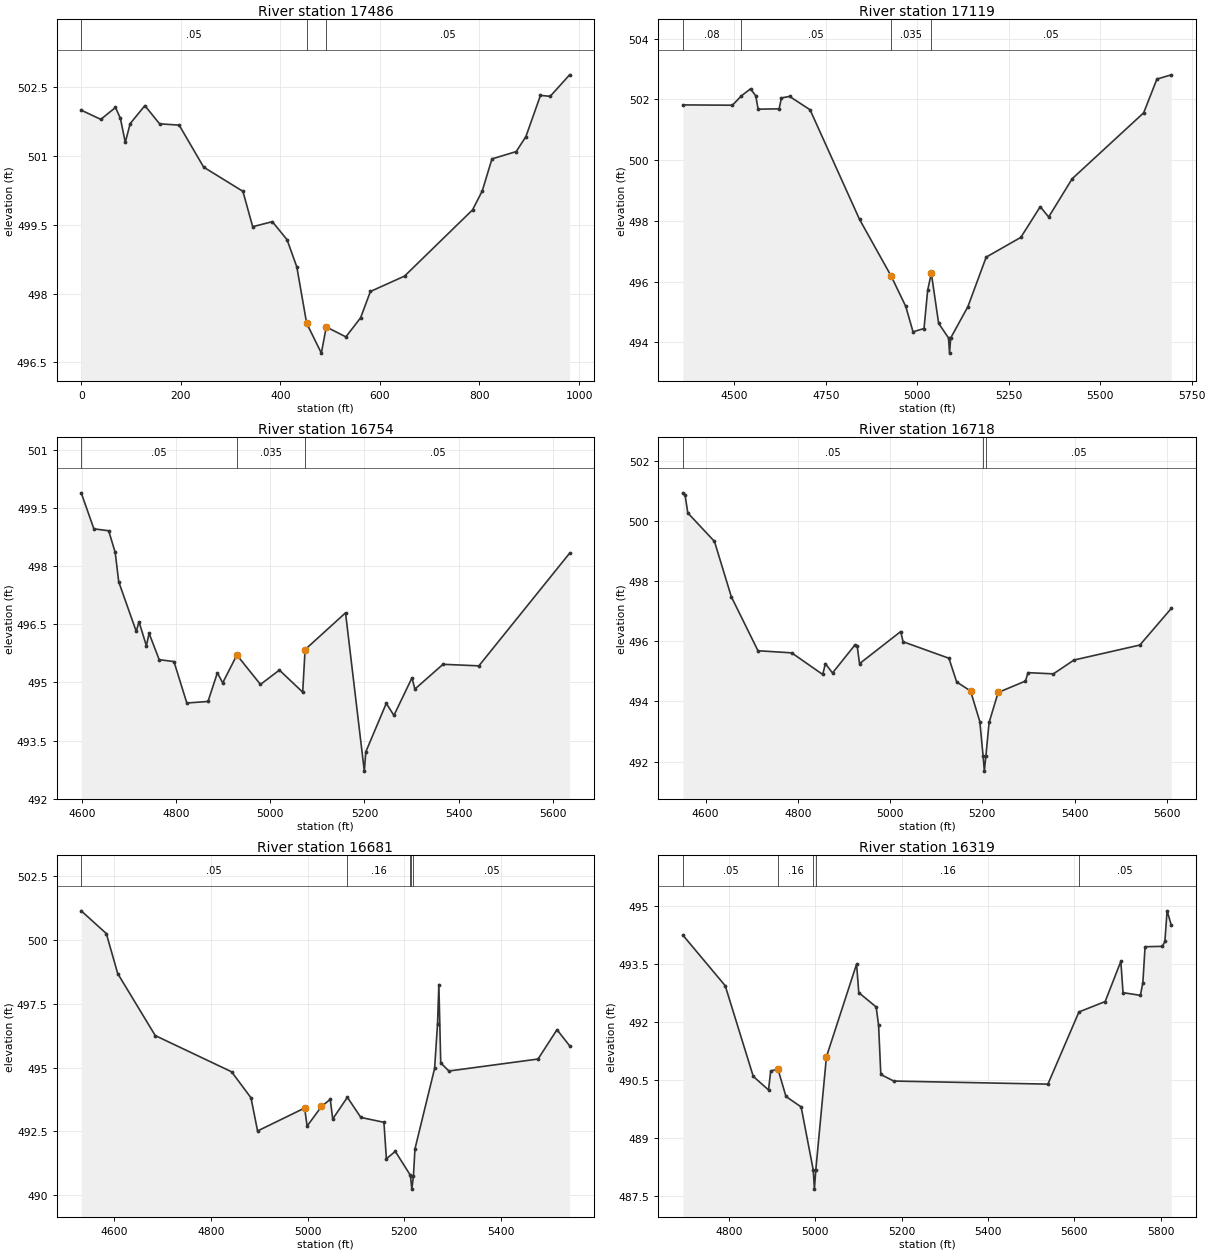
Type RM Length L Ch R = 1 ,17486   ,367,367,367
XS GIS Cut Line= 4
     3470423.428    10498253.823     3470362.664    10498466.497
     3470375.685    10498871.227     3470499.962    10499211.288
#Sta/Elev= 30
       0501.997239.34842501.796768.85973502.056278.69683501.819188.53394501.2956
98.37103 501.705127.8823 502.096157.3937501.6998196.7421501.6711245.9667500.7556
324.7678500.2287344.4681499.4576383.8687499.5676413.4191499.1758433.1194498.5799
452.8197 497.355482.3701496.7032492.2202497.2739531.6208497.0573561.1712497.4723
580.8715498.0463649.5219498.3822 786.021 499.824805.5209500.2363825.0208500.9349
873.7704501.0952893.2703 501.423922.5201502.3194  942.02502.2985981.0197502.7671
#Mann= 3 ,-1 , 0
       0     .05       0452.8197    .035       0492.2202     .05       0
Bank Sta=452.8197,492.2202
XS Rating Curve= 0 ,0
Exp/Cntr=0.3,0.1

Type RM Length L Ch R = 1 ,17119   ,365,365,365
BEGIN DESCRIPTION:
UNT013 IN STEL 26.0
END DESCRIPTION:
XS GIS Cut Line= 4
      3470398.84     10498238.25      3470025.56     10498546.43
      3470016.88     10498997.82      3470237.68     10499331.19
#Sta/Elev= 30
  4358.9  501.82  4494.3  501.81  4519.1  502.12  4543.8  502.35  4558.1  502.12
  4564.6  501.68    4622  501.69  4628.4  502.05  4650.6   502.1  4706.6  501.66
    4842  498.05  4928.2  496.19  4968.2  495.19  4988.2  494.35  5018.2  494.46
  5028.2  495.72  5038.2  496.28  5058.2  494.63  5085.2  494.15    5088  493.65
  5091.2  494.15  5138.2  495.18  5188.2  496.81  5282.9  497.46    5336  498.47
    5359  498.13  5423.3  499.39  5618.8  501.56    5655  502.67  5694.3  502.81
#Mann= 4 ,-1 , 0
  4358.9     .08       0  4519.1     .05       0  4928.2    .035       0
  5038.2     .05       0
Bank Sta=4928.2,5038.2
XS Rating Curve= 0 ,0
Exp/Cntr=0.3,0.1

Type RM Length L Ch R = 1 ,16754   ,36,36,36
BEGIN DESCRIPTION:
Mapping XS 46f5d481
END DESCRIPTION:
XS GIS Cut Line= 4
      3469934.41     10498355.45      3469682.67     10498503.03
      3469652.29     10498858.93      3469834.57     10499201.78
#Sta/Elev= 30
  4598.4   499.9  4625.3  498.97  4656.7  498.92  4670.6  498.36  4678.1   497.6
  4715.3  496.32  4721.1  496.57  4736.8  495.95  4742.6  496.27    4764  495.59
  4795.4  495.54  4822.7  494.47  4867.7  494.51  4887.6  495.25  4898.9  494.99
    4929  495.71  4979.1  494.95  5019.3  495.32  5068.8  494.75  5073.9  495.85
  5159.8   496.8  5199.7  492.71  5202.9  493.21  5246.3  494.46  5262.6  494.15
  5300.9  495.12  5307.1  494.83  5366.8  495.47    5443  495.43  5635.7  498.34
#Mann= 3 , 0 , 0
  4598.4     .05       0    4929    .035       0  5073.9     .05       0
Bank Sta=4929,5073.9
XS Rating Curve= 0 ,0
Exp/Cntr=0.3,0.1

Type RM Length L Ch R = 1 ,16718   ,37,37,37
BEGIN DESCRIPTION:
Mapping XS 17176bce
END DESCRIPTION:
XS GIS Cut Line= 4
      3469930.03      10498303.4      3469652.29     10498476.99
      3469613.23     10498858.93      3469765.13     10499171.41
#Sta/Elev= 30
  4550.9  500.95  4555.7  500.87  4561.6  500.28  4619.4  499.33  4655.9  497.49
  4713.7  495.69  4786.8  495.62    4854   494.9  4859.9  495.26  4875.3  494.95
  4923.3  495.87  4928.9  495.84  4933.9  495.26  5023.2  496.33  5028.3  495.99
  5127.7  495.44  5144.5  494.65  5174.6  494.35  5194.7  493.33  5201.8  492.18
  5204.5  491.68  5207.8  492.18  5214.8   493.3 5234.43   494.3  5293.6  494.68
  5299.2  494.96  5354.3  494.92  5398.8  495.38  5541.7  495.88  5609.8   497.1
#Mann= 3 ,-1 , 0
  4550.9     .05       0  5201.8    .035       0  5207.8     .05       0
Bank Sta=5174.6,5234.43
XS Rating Curve= 0 ,0
Exp/Cntr=0.3,0.1

Type RM Length L Ch R = 1 ,16681   ,362,362,362
BEGIN DESCRIPTION:
Mapping XS 79a58f26
END DESCRIPTION:
XS GIS Cut Line= 4
      3469904.03     10498259.97      3469630.59     10498450.94
      3469556.81     10498850.25      3469677.74     10499092.11
#Sta/Elev= 30
  4531.9  501.15  4583.8  500.26  4607.4  498.69    4685  496.26  4842.9  494.84
    4883  493.82  4896.6  492.52    4994  493.42    4999  492.71  5028.8  493.48
  5046.9  493.76    5052  492.99  5082.3  493.84  5110.2  493.05  5157.9  492.86
    5163  491.43  5181.4  491.72  5212.4  490.79  5212.9  490.74  5215.6  490.24
  5218.9  490.74  5222.1  491.82  5262.7  494.97  5268.8  496.73  5271.5  498.26
  5275.4  495.19  5292.2  494.87  5476.6  495.34  5515.8  496.49  5541.9  495.86
#Mann= 5 ,-1 , 0
  4531.9     .05       0  5082.3     .16       0  5212.4     .05       0
  5212.9    .035       0  5218.9     .05       0
Bank Sta=4994,5028.8
XS Rating Curve= 0 ,0
Exp/Cntr=0.3,0.1

Type RM Length L Ch R = 1 ,16319   ,426,426,426
BEGIN DESCRIPTION:
Mapping XS d27a7738
END DESCRIPTION:
XS GIS Cut Line= 3
      3469686.96     10498245.92      3469363.65     10498330.55
       3469519.9     10499111.78
#Sta/Elev= 30
  4693.7  494.25  4791.7  492.94  4856.7  490.59    4892  490.24  4897.1  490.73
  4913.8  490.78  4932.4  490.07  4967.5   489.8  4995.5  488.17  4998.2  487.67
  5001.5  488.17  5026.1   491.1  5095.9   493.5    5101  492.76  5141.2  492.39
  5146.9  491.91    5152  490.64    5182  490.47  5538.9  490.39  5610.8  492.26
  5671.5  492.53  5707.8  493.57  5712.9  492.76  5753.1  492.69  5758.8  493.02
  5763.9  493.95  5804.1  493.96  5809.8  494.09  5814.9  494.88  5824.6  494.51
#Mann= 5 ,-1 , 0
  4693.7     .05       0  4913.8     .16       0  4995.5     .07       0
  5001.5     .16       0  5610.8     .05       0
Bank Sta=4913.8,5026.1
XS Rating Curve= 0 ,0
Exp/Cntr=0.3,0.1

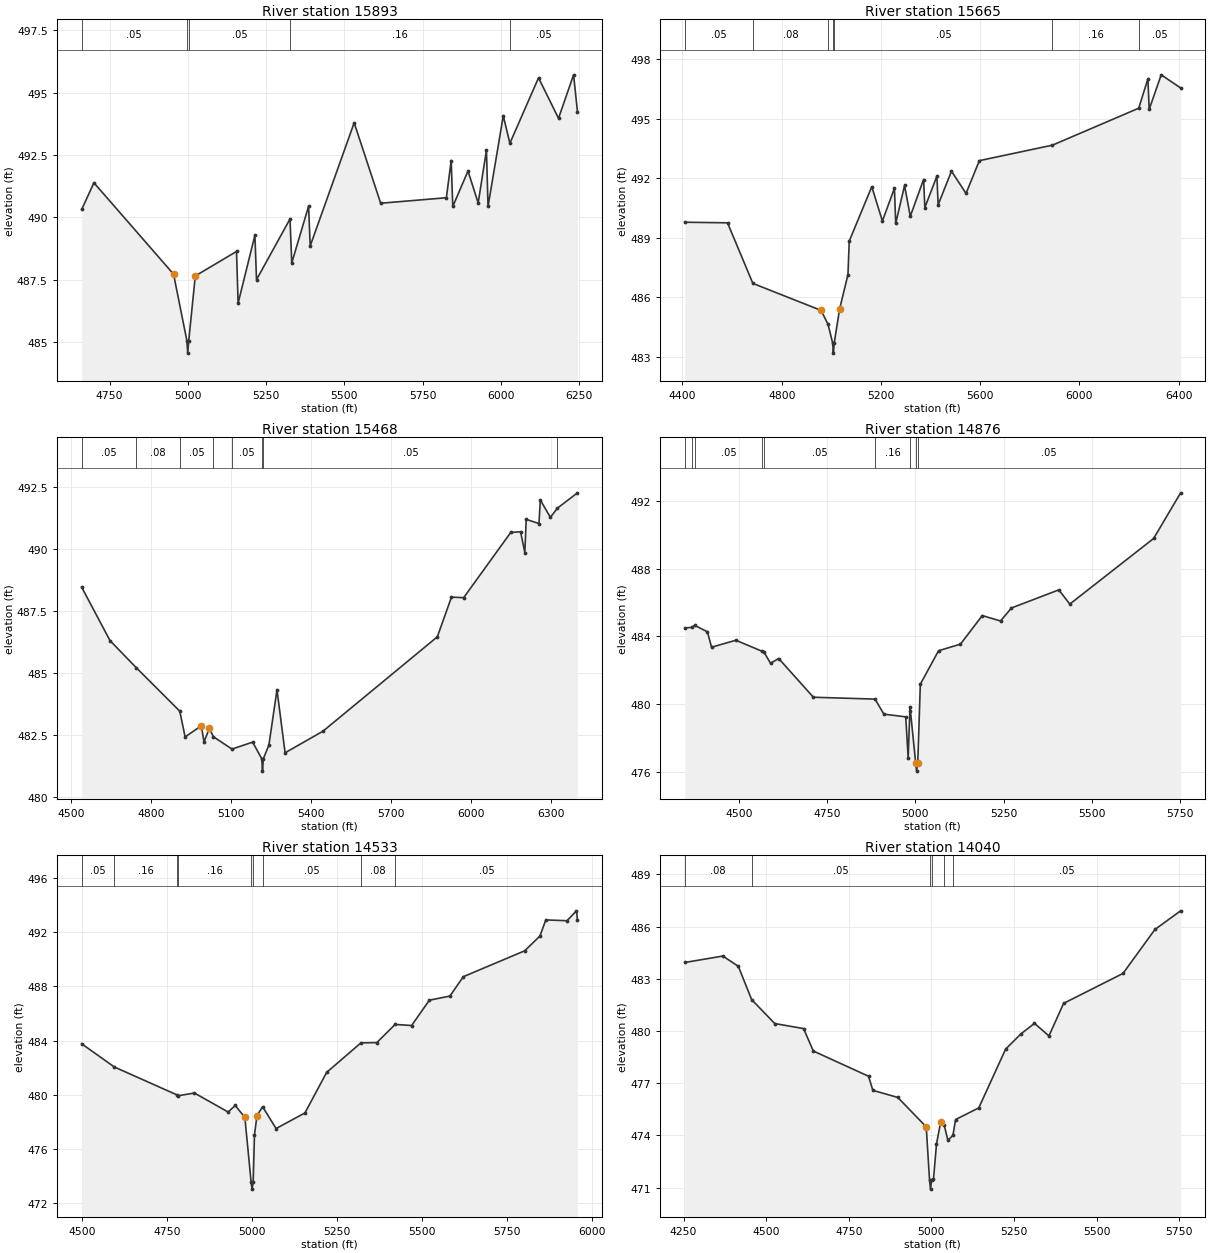
Type RM Length L Ch R = 1 ,15893   ,228,228,228
BEGIN DESCRIPTION:
Mapping XS 855531d6
END DESCRIPTION:
XS GIS Cut Line= 3
      3469634.87     10497816.23      3469283.35     10497913.88
       3469498.2     10499113.97
#Sta/Elev= 30
    4661  490.32    4700  491.39  4954.5  487.73    4997  485.07  4999.7  484.57
    5003  485.07  5023.9  487.66  5155.6  488.64  5160.7  486.57  5214.4  489.29
  5219.5  487.51  5326.5  489.94  5332.1  488.18  5385.9  490.45    5391  488.86
  5531.5  493.79  5616.2  490.57  5826.1  490.79  5841.5  492.28  5846.5  490.44
  5895.2  491.86  5927.7  490.58  5954.1  492.69  5959.2  490.44  6007.9  494.07
    6029  492.97  6120.5  495.59  6184.4  493.97  6232.5  495.71    6245  494.23
#Mann= 5 ,-1 , 0
    4661     .05       0    4997     .04       0    5003     .05       0
  5326.5     .16       0    6029     .05       0
Bank Sta=4954.5,5023.9
XS Rating Curve= 0 ,0
Exp/Cntr=0.3,0.1

Type RM Length L Ch R = 1 ,15665   ,197,197,197
BEGIN DESCRIPTION:
Mapping XS 9815920d
END DESCRIPTION:
XS GIS Cut Line= 3
      3469431.37     10497116.53      3469238.65     10497778.03
      3469470.38     10499066.86
#Sta/Elev= 30
  4409.5  489.78  4581.5  489.75  4683.7   486.7 4958.81  485.34  4986.7  484.64
  5005.5  483.69  5008.3  483.19  5011.5  483.69  5033.5  485.42    5067  487.14
  5072.2  488.83  5163.1  491.57  5205.8  489.84  5254.4  491.49  5259.5  489.72
  5295.2  491.63  5318.2  490.08  5371.9  491.93    5377  490.52  5425.5   492.1
  5430.6  490.66  5484.3  492.35    5543  491.23  5596.7  492.88  5891.4  493.66
  6239.1  495.52  6276.1     497  6281.2  495.46  6329.7   497.2    6408  496.54
#Mann= 7 ,-1 , 0
  4409.5     .05       0  4683.7     .08       0  4986.7     .05       0
  5005.5     .04       0  5011.5     .05       0  5891.4     .16       0
  6239.1     .05       0
Bank Sta=4958.81,5033.5
XS Rating Curve= 0 ,0
Exp/Cntr=0.3,0.1

Type RM Length L Ch R = 1 ,15468   ,592,592,592
BEGIN DESCRIPTION:
UNT013 IN STEL 24.0
END DESCRIPTION:
XS GIS Cut Line= 4
      3469101.93     10497135.65      3469096.98     10497390.96
      3469250.51     10498307.91      3469372.76     10498971.57
#Sta/Elev= 30
  4539.4  488.46  4645.4  486.31  4744.4  485.21  4907.3  483.46  4927.3  482.42
  4988.1  482.87  4998.2  482.22  5018.5  482.77  5033.1  482.43  5103.2  481.93
  5180.7  482.21  5214.8  481.54  5217.6  481.04  5220.8  481.54  5241.6  482.09
    5272  484.32  5302.4  481.78  5444.4  482.65  5873.5  486.46  5926.5  488.06
  5972.3  488.04  6148.8  490.67  6185.8   490.7  6201.8  489.86  6206.9   491.2
  6254.8  491.03  6259.9  491.98  6297.7  491.28  6323.8  491.65  6399.3  492.27
#Mann= 8 ,-1 , 0
  4539.4     .05       0  4744.4     .08       0  4907.3     .05       0
  5033.1     .08       0  5103.2     .05       0  5214.8     .04       0
  5220.8     .05       0  6323.8     .16       0
Bank Sta=4988.1,5018.5
XS Rating Curve= 0 ,0
Exp/Cntr=0.3,0.1

Type RM Length L Ch R = 1 ,14876   ,343,343,343
BEGIN DESCRIPTION:
UNT013 IN STEL 23.0
END DESCRIPTION:
XS GIS Cut Line= 3
      3469055.04     10497302.37      3468851.93     10497758.06
      3468620.16     10498635.66
#Sta/Elev= 30
  4345.8   484.5    4366  484.53  4373.8  484.65  4409.8  484.27  4421.6  483.36
  4490.5  483.77  4564.9  483.12  4570.8  483.05  4588.9  482.41  4612.1  482.69
  4710.5   480.4  4885.4  480.29  4910.5   479.4  4972.5  479.24  4979.4  476.82
  4984.6  479.84  4985.9  479.58  5000.6  476.53  5003.3  476.03  5006.6  476.53
  5013.9  481.17  5065.6  483.15  5127.7  483.54  5189.7  485.23  5241.4  484.91
  5272.5  485.68  5406.8  486.75    5438  485.91  5675.8  489.79  5752.4  492.49
#Mann= 9 ,-1 , 0
  4345.8     .05       0    4366     .08       0  4373.8     .05       0
  4564.9     .16       0  4570.8     .05       0  4885.4     .16       0
  4985.9     .05       0  5000.6     .04       0  5006.6     .05       0
Bank Sta=5000.6,5006.6
XS Rating Curve= 0 ,0
Exp/Cntr=0.3,0.1

Type RM Length L Ch R = 1 ,14533   ,493,493,493
BEGIN DESCRIPTION:
UNT013 IN STEL 22.0
END DESCRIPTION:
XS GIS Cut Line= 3
      3468976.94     10497307.53       3468393.6     10497859.62
      3468216.81     10498491.37
#Sta/Elev= 30
  4497.8  483.76  4593.9  482.05  4778.3  479.99  4781.6  479.93  4829.6  480.13
  4928.7  478.73  4949.7  479.21    4978  478.33  4996.5  473.54  4999.2  473.04
  5002.5  473.54  5006.3  477.04  5013.6  478.46  5030.2  479.12  5069.9  477.51
  5154.8  478.66  5218.7  481.65  5319.6  483.83  5366.4  483.85  5420.3  485.19
  5468.8  485.11  5521.1  486.98  5581.5  487.28  5620.9  488.71  5801.5  490.62
  5846.4  491.71  5863.8   492.9  5926.1  492.84    5954  493.57    5957  492.88
#Mann= 9 ,-1 , 0
  4497.8     .05       0  4593.9     .16       0  4778.3     .05       0
  4781.6     .16       0  4996.5     .07       0  5002.5     .16       0
  5030.2     .05       0  5319.6     .08       0  5420.3     .05       0
Bank Sta=4978,5013.6
XS Rating Curve= 0 ,0
Exp/Cntr=0.3,0.1

Type RM Length L Ch R = 1 ,14040   ,244,244,244
BEGIN DESCRIPTION:
UNT013 IN STEL 21.0
END DESCRIPTION:
XS GIS Cut Line= 3
      3469001.21     10497009.99      3467959.58      10497465.7
      3467799.01     10497791.19
#Sta/Elev= 30
    4254  483.94    4369  484.31  4415.8  483.72    4456  481.81  4525.9  480.43
  4613.2  480.14  4642.7  478.85  4809.7   477.4  4822.8  476.59  4898.4  476.18
  4984.3  474.49  4994.4  471.41  4997.2  470.91  5000.4  471.41  5006.2  471.48
  5015.3   473.5    5028  474.78  5038.4  474.61  5049.8  473.72  5065.1     474
    5073  474.91  5143.2  475.58  5224.5  478.96  5271.1  479.84  5311.8  480.44
  5355.5  479.72  5399.9  481.59  5579.5  483.31  5676.3  485.84  5753.9  486.91
#Mann= 6 ,-1 , 0
    4254     .08       0    4456     .05       0  4994.4     .04       0
  5000.4     .05       0  5038.4     .16       0  5065.1     .05       0
Bank Sta=4984.3,5028
XS Rating Curve= 0 ,0
Exp/Cntr=0.3,0.1

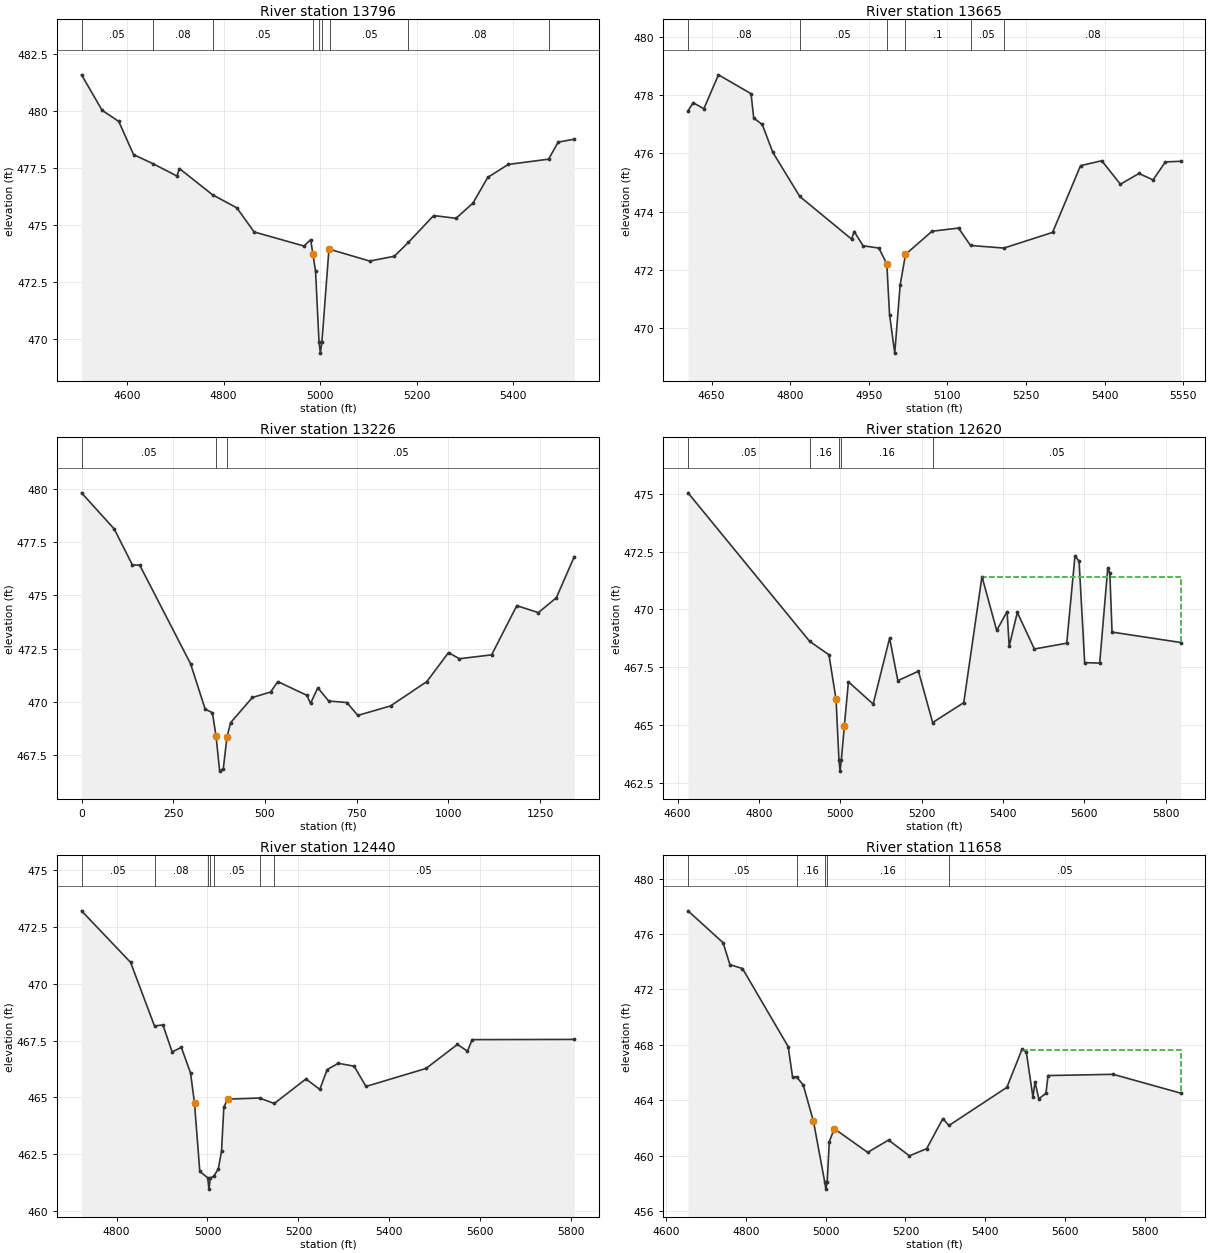
Type RM Length L Ch R = 1 ,13796   ,131,131,131
BEGIN DESCRIPTION:
UNT013 IN STEL 20.0
END DESCRIPTION:
XS GIS Cut Line= 2
      3468727.81     10496988.27      3467726.14      10497183.4
#Sta/Elev= 30
  4505.7   481.6  4548.3  480.04  4582.8  479.55  4613.4  478.09  4653.8  477.69
  4703.2  477.15  4708.3  477.48  4777.2  476.32  4827.3  475.75  4863.1  474.69
  4966.4  474.07  4980.2  474.35  4984.8  473.72  4990.3  472.97  4997.5  469.86
  5000.3  469.36  5003.5  469.86    5018  473.92  5020.8  473.92  5102.4  473.41
  5153.4  473.62  5182.5  474.23  5234.9  475.41  5281.2  475.29  5316.4  475.96
  5346.9  477.09  5389.5  477.66  5472.9  477.89  5492.7  478.64  5526.2  478.77
#Mann= 9 ,-1 , 0
  4505.7     .05       0  4653.8     .08       0  4777.2     .05       0
  4984.8      .1       0  4997.5     .07       0  5003.5      .1       0
  5020.8     .05       0  5182.5     .08       0  5472.9      .1       0
Bank Sta=4984.8,5018
XS Rating Curve= 0 ,0
Exp/Cntr=0.3,0.1

Type RM Length L Ch R = 1 ,13665   ,439,439,439
BEGIN DESCRIPTION:
UNT013 IN STEL 19.0
END DESCRIPTION:
XS GIS Cut Line= 2
      3468601.92     10496897.13      3467673.17     10497044.69
#Sta/Elev= 30
    4605  477.47  4614.9  477.75  4635.2  477.54  4663.1  478.71  4725.3  478.06
  4730.4  477.22  4746.6     477  4766.8  476.04  4818.2  474.52  4917.1  473.05
  4922.2  473.31    4939  472.82  4969.3  472.74  4984.4  472.19  4989.6  470.45
  4999.5  469.12  5009.8  471.46    5020  472.52  5070.6  473.32  5121.2  473.43
  5144.1  472.83  5207.8  472.74  5300.7  473.28  5354.1  475.58  5394.6  475.75
  5430.2  474.94  5465.5  475.31  5492.5  475.09  5516.1  475.71  5545.4  475.73
#Mann= 6 ,-1 , 0
    4605     .08       0  4818.2     .05       0  4984.4    .035       0
    5020      .1       0  5144.1     .05       0  5207.8     .08       0
Bank Sta=4984.4,5020
XS Rating Curve= 0 ,0
Exp/Cntr=0.3,0.1

Type RM Length L Ch R = 1 ,13226   ,606,606,606
XS GIS Cut Line= 3
     3468490.585    10496467.623     3467540.064    10496641.235
     3467518.363     10497031.86
#Sta/Elev= 30
       0  479.82 89.1909478.1185138.7414476.4272158.5616476.4234 297.303471.7806
336.9434469.6555356.7636469.4822366.6737468.3875376.5838466.7371386.4939466.8598
 396.404468.3254406.3141469.0139465.7747470.1985515.3252470.4547535.1454470.9453
614.4262470.2993624.3363469.9191644.1565470.6557673.8868470.0327723.4373469.9625
753.1676469.3561842.3585469.8021941.4595470.94661000.483472.31061029.885472.0214
1118.092472.20341186.697474.51621245.502474.18871294.506474.88751343.509476.8227
#Mann= 3 , 0 , 0
       0     .05       0366.6737    .035       0 396.404     .05       0
Bank Sta=366.6737,396.404
XS Rating Curve= 0 ,0
Exp/Cntr=0.3,0.1

Type RM Length L Ch R = 1 ,12620   ,180,180,180
BEGIN DESCRIPTION:
UNT013 IN STEL 17.0
END DESCRIPTION:
XS GIS Cut Line= 2
       3468131.5     10496101.98      3466935.28     10496294.41
#Sta/Elev= 30
  4625.5  475.04  4924.6  468.62    4972  468.04  4989.5  466.11  4996.6  463.51
  4999.4  463.01  5002.6  463.51  5009.8  464.96  5019.9  466.87  5080.7  465.91
  5121.2  468.76  5141.4  466.92  5192.1  467.33    5227  465.11  5303.5  465.97
  5348.3  471.42  5384.5  469.09  5410.1  469.91  5415.2  468.41  5435.2  469.87
  5477.1  468.29  5556.7  468.54    5577  472.32  5587.1  472.08  5600.8   467.7
  5637.7  467.68  5657.6   471.8  5662.7  471.56  5668.1  469.02  5837.1  468.57
#Mann= 5 ,-1 , 0
  4625.5     .05       0  4924.6     .16       0  4996.6     .07       0
  5002.6     .16       0    5227     .05       0
#XS Ineff= 2 , 0
                         5347.73          471.41
Permanent Ineff=
       F       F
Bank Sta=4989.5,5009.8
XS Rating Curve= 0 ,0
Exp/Cntr=0.3,0.1

Type RM Length L Ch R = 1 ,12440   ,782,782,782
BEGIN DESCRIPTION:
UNT013 IN STEL 16.0
END DESCRIPTION:
XS GIS Cut Line= 2
      3467928.33     10496003.03      3466860.67     10496190.52
#Sta/Elev= 30
    4723  473.21  4830.9  470.94  4883.5  468.14  4901.9  468.19  4922.3     467
  4942.5   467.2  4962.8  466.07  4971.5  464.74  4983.1  461.74  5000.5  461.46
  5003.2  460.96  5006.5  461.46  5013.4  461.52  5023.8  461.84  5030.9  462.63
    5036  464.56  5044.1  464.92  5114.5  464.97    5147  464.73  5216.7  465.81
  5247.1  465.35  5263.3  466.22  5287.7   466.5  5322.7  466.37  5348.7  465.48
  5480.6  466.27    5550  467.33    5572  467.03  5582.2  467.54    5807  467.55
#Mann= 7 ,-1 , 0
    4723     .05       0  4883.5     .08       0  5000.5     .07       0
  5006.5     .08       0  5013.4     .05       0  5114.5     .16       0
    5147     .05       0
Bank Sta=4971.5,5044.1
XS Rating Curve= 0 ,0
Exp/Cntr=0.3,0.1

Type RM Length L Ch R = 1 ,11658   ,1681,1681,1681
BEGIN DESCRIPTION:
UNT013 IN STEL 14.0
END DESCRIPTION:
XS GIS Cut Line= 2
      3467762.56     10495331.14      3466581.97     10495695.74
#Sta/Elev= 30
  4654.7  477.67  4742.6  475.37  4759.8  473.79  4791.2  473.51  4905.8  467.88
  4916.8  465.69  4926.8   465.7  4943.7   465.1  4969.2   462.5  4997.6   458.1
  5000.3   457.6  5003.6   458.1    5009  461.03  5021.5  461.96  5105.2  460.25
  5157.5  461.14  5209.9     460  5253.2  460.52  5293.6  462.68    5309  462.19
  5454.3  464.94  5492.5  467.71  5502.9   467.5  5519.6  464.23  5524.8  465.35
  5534.3  464.11  5552.2  464.51  5557.5  465.79  5720.7  465.88  5890.3  464.52
#Mann= 5 ,-1 , 0
  4654.7     .05       0  4926.8     .16       0  4997.6     .07       0
  5003.6     .16       0    5309     .05       0
#XS Ineff= 2 , 0
                          5492.5          467.64
Permanent Ineff=
       F       F
Bank Sta=4969.2,5021.5
XS Rating Curve= 0 ,0
Exp/Cntr=0.3,0.1

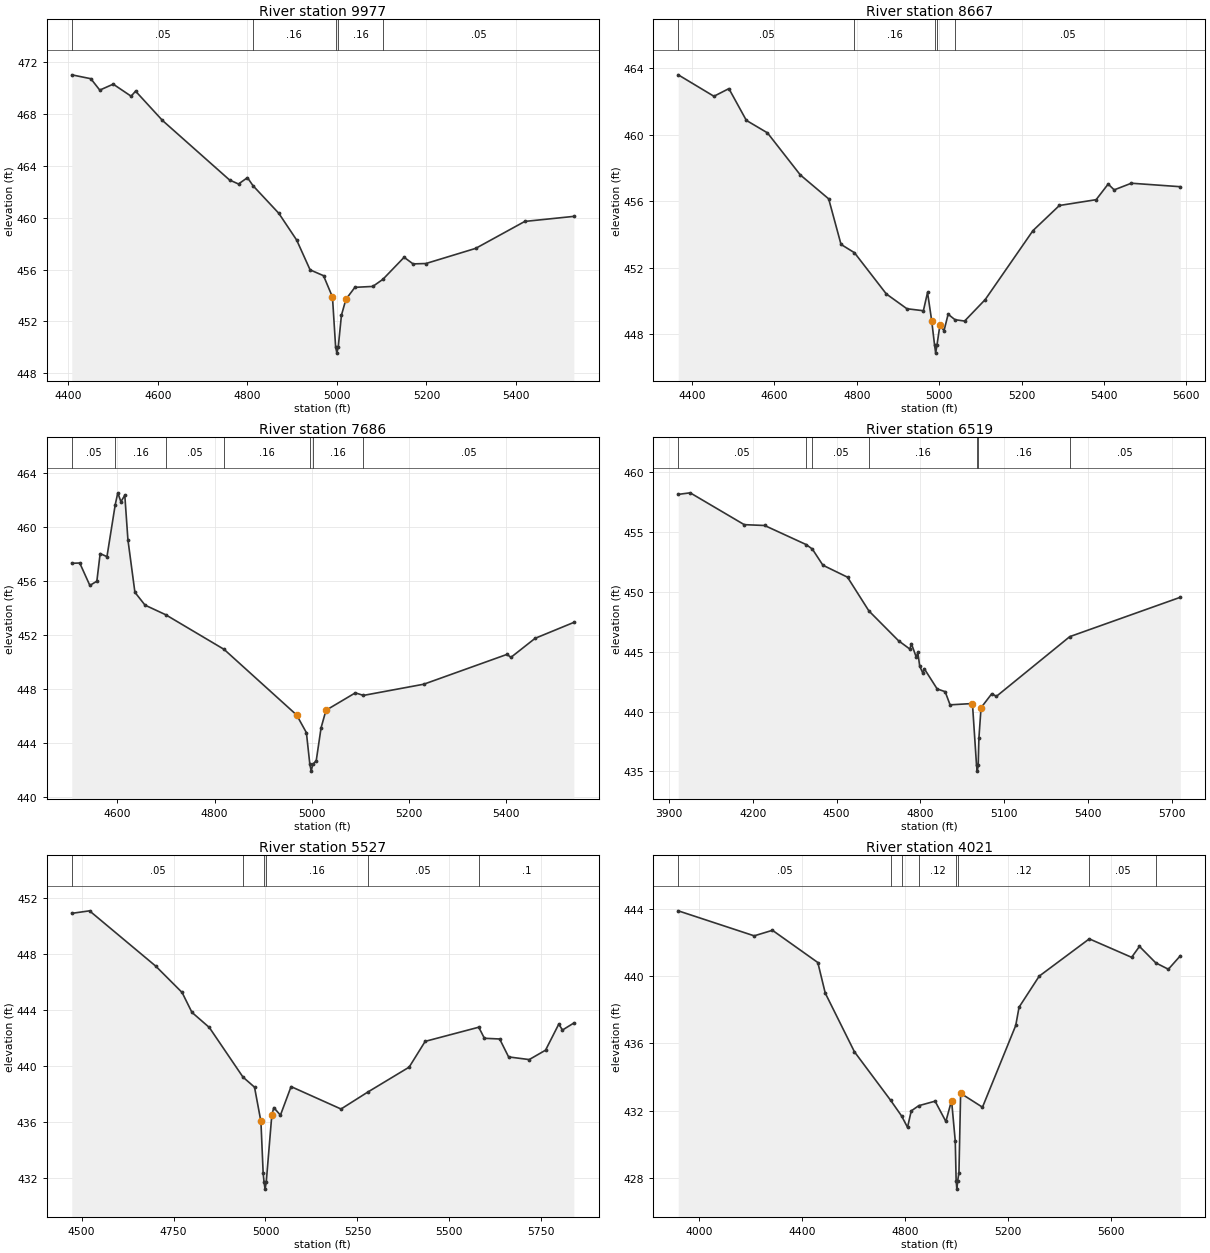
Type RM Length L Ch R = 1 ,9977    ,1310,1310,1310
BEGIN DESCRIPTION:
UNT013 IN STEL 12.0
END DESCRIPTION:
XS GIS Cut Line= 3
      3467484.73     10494619.35      3466538.58     10494628.03
      3466390.97     10494723.53
#Sta/Elev= 30
  4407.4  471.04    4450  470.74    4470  469.86    4500  470.32    4540  469.39
    4550  469.78    4610  467.52    4760  462.92    4780  462.61    4800   463.1
  4812.4  462.48    4870  460.35    4910  458.28    4940  455.98    4970  455.53
    4990  453.88    4997  450.05  4999.8  449.55    5003  450.05    5010  452.47
  5020.1  453.71  5040.1  454.63  5080.1   454.7  5102.7  455.25  5150.1  456.95
  5170.1  456.44  5198.9  456.47  5310.1  457.64  5419.8  459.72  5529.4  460.11
#Mann= 5 ,-1 , 0
  4407.4     .05       0  4812.4     .16       0    4997     .07       0
    5003     .16       0  5102.7     .05       0
Bank Sta=4990,5020.1
XS Rating Curve= 0 ,0
Exp/Cntr=0.3,0.1

Type RM Length L Ch R = 1 ,8667    ,981,981,981
BEGIN DESCRIPTION:
UNT013 IN STEL 10.0
END DESCRIPTION:
XS GIS Cut Line= 4
      3467180.95     10494003.04       3466885.8     10493812.05
      3466278.16     10493829.42       3466122.3     10494037.22
#Sta/Elev= 30
  4366.4  463.59  4453.1   462.3  4489.4  462.76  4531.8  460.85    4583   460.1
  4662.8  457.57  4731.7  456.13  4761.7  453.39  4794.3  452.89  4871.7  450.41
  4921.7  449.52  4961.7   449.4  4971.8   450.5  4981.8  448.81  4988.8  447.35
  4991.5  446.85  4994.8  447.35  5001.8  448.53  5011.8   448.2  5021.8  449.19
  5038.5  448.86  5061.8  448.78  5111.8  450.07  5227.8  454.22  5291.9  455.73
  5381.2  456.08  5410.4  457.02    5425  456.67  5466.7  457.07  5585.6  456.86
#Mann= 5 ,-1 , 0
  4366.4     .05       0  4794.3     .16       0  4988.8     .07       0
  4994.8     .16       0  5038.5     .05       0
Bank Sta=4981.8,5001.8
XS Rating Curve= 0 ,0
Exp/Cntr=0.3,0.1

Type RM Length L Ch R = 1 ,7686    ,1167,1167,1167
BEGIN DESCRIPTION:
UNT013 IN STEL 8.0
END DESCRIPTION:
XS GIS Cut Line= 4
      3467139.27     10493437.05      3466962.19      10493218.3
      3466399.69      10493280.8      3466253.82     10493395.41
#Sta/Elev= 30
  4506.2  457.28  4522.6   457.3  4543.4  455.64  4557.8  455.95  4564.6     458
  4578.6  457.77  4595.6  461.62  4600.9   462.5  4607.3  461.84  4615.3  462.32
  4621.7  459.03  4636.1  455.13  4656.9  454.18  4699.3  453.47  4819.6   450.9
  4968.8  446.04  4988.9  444.73    4996  442.38  4998.8  441.88    5002  442.38
  5009.1  442.65  5019.1  445.09  5029.2  446.39  5089.6  447.68  5106.2  447.49
  5230.4  448.32  5401.6  450.53  5409.7  450.31  5459.4  451.72  5539.1   452.9
#Mann= 7 ,-1 , 0
  4506.2     .05       0  4595.6     .16       0  4699.3     .05       0
  4819.6     .16       0    4996     .07       0    5002     .16       0
  5106.2     .05       0
Bank Sta=4968.8,5029.2
XS Rating Curve= 0 ,0
Exp/Cntr=0.3,0.1

Type RM Length L Ch R = 1 ,6519    ,992,992,992
BEGIN DESCRIPTION:
UNT013 IN STEL 6.0
END DESCRIPTION:
XS GIS Cut Line= 4
      3467738.66     10492278.63      3467152.73     10492105.02
      3466317.22      10492484.8      3466132.78     10492680.09
#Sta/Elev= 30
  3932.8  458.16  3975.6  458.29  4169.1  455.63  4242.1  455.56  4390.4  453.97
    4413  453.59  4450.7  452.24  4538.8  451.24  4615.4  448.42  4721.4  445.93
  4762.1  445.23  4767.5  445.68  4785.1  444.55  4790.6  444.96  4797.2  443.81
  4808.2  443.24  4813.7  443.59  4859.8   441.9  4888.4  441.67    4906  440.57
  4986.1  440.68  5000.7  435.53  5003.5  435.03  5006.7  435.53  5009.2  437.77
  5016.9  440.33  5055.3   441.5  5071.9  441.28  5334.5  446.27  5730.3  449.56
#Mann= 7 ,-1 , 0
  3932.8     .05       0  4390.4     .16       0    4413     .05       0
  4615.4     .16       0  5000.7     .07       0  5006.7     .16       0
  5334.5     .05       0
Bank Sta=4986.1,5016.9
XS Rating Curve= 0 ,0
Exp/Cntr=0.3,0.1

Type RM Length L Ch R = 1 ,5527    ,1506,1506,1506
BEGIN DESCRIPTION:
UNT013 IN STEL 4.0
END DESCRIPTION:
XS GIS Cut Line= 4
      3467185.31     10491616.75      3466838.06     10491540.79
      3466111.06     10491855.46      3466089.36     10492072.44
#Sta/Elev= 30
  4473.1  450.89  4521.4  451.07  4701.6  447.12  4773.2  445.24    4800  443.82
  4847.3  442.74  4938.8   439.2  4970.2  438.48  4987.6  436.03  4993.7  432.35
  4996.1   431.7  4998.9   431.2  5002.1   431.7  5017.2  436.47  5022.6  437.02
  5040.7  436.48  5069.6  438.52  5205.5  436.92  5277.7  438.12  5390.8  439.91
  5434.4  441.75  5580.1  442.76  5595.5  441.97    5637  441.92  5661.3  440.64
  5717.4  440.45  5761.8  441.12  5797.8  442.98  5807.9  442.56  5838.8  443.06
#Mann= 6 ,-1 , 0
  4473.1     .05       0  4938.8     .16       0  4996.1     .07       0
  5002.1     .16       0  5277.7     .05       0  5580.1      .1       0
Bank Sta=4987.6,5017.2
XS Rating Curve= 0 ,0
Exp/Cntr=0.3,0.1

Type RM Length L Ch R = 1 ,4021    ,956,956,956
BEGIN DESCRIPTION:
UNT013 IN STEL 3.0
END DESCRIPTION:
XS GIS Cut Line= 4
      3466686.12     10490488.27      3466230.42     10490531.67
      3465503.42     10491421.43      3465568.41     10491757.23
#Sta/Elev= 30
  3919.4   443.9  4214.2  442.41  4285.1  442.74  4461.2  440.82    4490     439
  4603.4   435.5  4743.9  432.61  4786.3  431.68  4809.4     431  4823.8  431.98
  4852.8  432.29  4916.4  432.56  4958.2  431.35  4980.3   432.6  4994.7  430.18
  4998.1  427.82  5000.9  427.32  5004.1  427.82    5009  428.31  5015.5  433.03
  5100.3   432.2  5229.4  437.07  5242.3  438.16  5320.6  440.01  5514.9  442.23
  5679.2  441.13  5709.7  441.78  5772.9   440.8  5821.8  440.42  5868.2  441.22
#Mann= 8 ,-1 , 0
  3919.4     .05       0  4743.9     .12       0  4786.3     .16       0
  4852.8     .12       0  4998.1     .07       0  5004.1     .12       0
  5514.9     .05       0  5772.9      .1       0
Bank Sta=4980.3,5015.5
XS Rating Curve= 0 ,0
Exp/Cntr=0.3,0.1

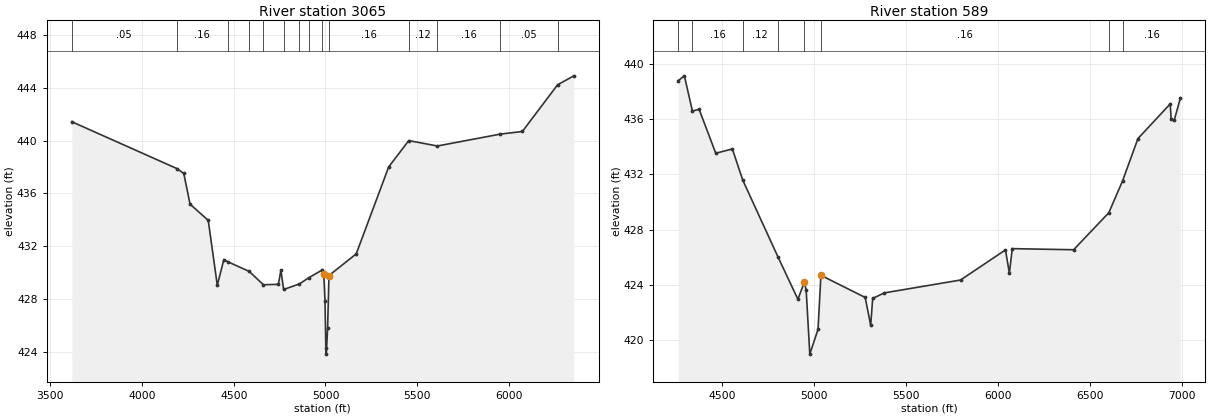
Type RM Length L Ch R = 1 ,3065    ,2476,2476,2476
BEGIN DESCRIPTION:
UNT013 IN STEL 2.0
END DESCRIPTION:
XS GIS Cut Line= 4
        3466480.     10489989.14      3465861.49     10489945.74
      3464884.93     10490998.25      3465090.67     10491647.95
#Sta/Elev= 30
  3616.7  441.43  4189.5  437.88  4227.4  437.51  4261.6  435.18  4360.8  433.95
  4410.1  429.03  4445.8  430.98  4467.9  430.81  4584.4  430.08  4661.2  429.07
  4742.9   429.1    4757  430.16  4771.7  428.71  4857.6  429.13  4908.8   429.6
  4983.3   430.2  4990.6  429.85  4997.4  427.84  5001.8  424.31  5004.5  423.81
  5011.6  425.81    5019  429.77  5167.5  431.41  5344.4     438    5454     440
  5609.7  439.59  5952.6  440.49  6073.3  440.69  6265.3  444.23    6354  444.91
#Mann= 14 ,-1 , 0
  3616.7     .05       0  4189.5     .16       0  4467.9     .12       0
  4584.4     .16       0  4661.2     .12       0  4771.7     .16       0
  4857.6     .12       0  4908.8     .16       0  4983.3     .07       0
    5019     .16       0    5454     .12       0  5609.7     .16       0
  5952.6     .05       0  6265.3      .1       0
Bank Sta=4990.6,5019
XS Rating Curve= 0 ,0
Exp/Cntr=0.3,0.1

Type RM Length L Ch R = 1 ,589     ,0,0,0
BEGIN DESCRIPTION:
UNT013 IN STEL 1.0
END DESCRIPTION:
XS GIS Cut Line= 4
      3466245.45     10489146.67      3465212.47     10489242.16
      3464917.33     10490058.13      3464778.44     10490874.11
#Sta/Elev= 30
  4259.6  438.77  4293.1  439.12  4336.5  436.58  4373.4  436.69  4463.8  433.52
  4554.2  433.83  4610.7  431.58  4801.5  426.05  4910.9  422.96  4945.9  424.19
  4955.9  423.64  4975.7  418.99  5020.5  420.78  5036.2  424.69  5277.3  423.09
  5307.1  421.07  5317.9  423.02  5381.5  423.42  5796.2  424.35  6040.8  426.53
  6062.1  424.84  6077.6  426.62  6411.7  426.54  6603.3  429.22  6678.1  431.52
  6761.8  434.58  6937.4  437.09  6942.5  436.01  6959.5  435.92  6992.4  437.49
#Mann= 8 ,-1 , 0
  4259.6     .05       0  4336.5     .16       0  4610.7     .12       0
  4801.5     .16       0  4945.9     .07       0  5036.2     .16       0
  6603.3     .12       0  6678.1     .16       0
Bank Sta=4945.9,5036.2
XS Rating Curve= 0 ,0
Exp/Cntr=0.3,0.1

Chan Stop Cuts=-1
Use User Specified Reach Order=0
Composite Channel Slope=5