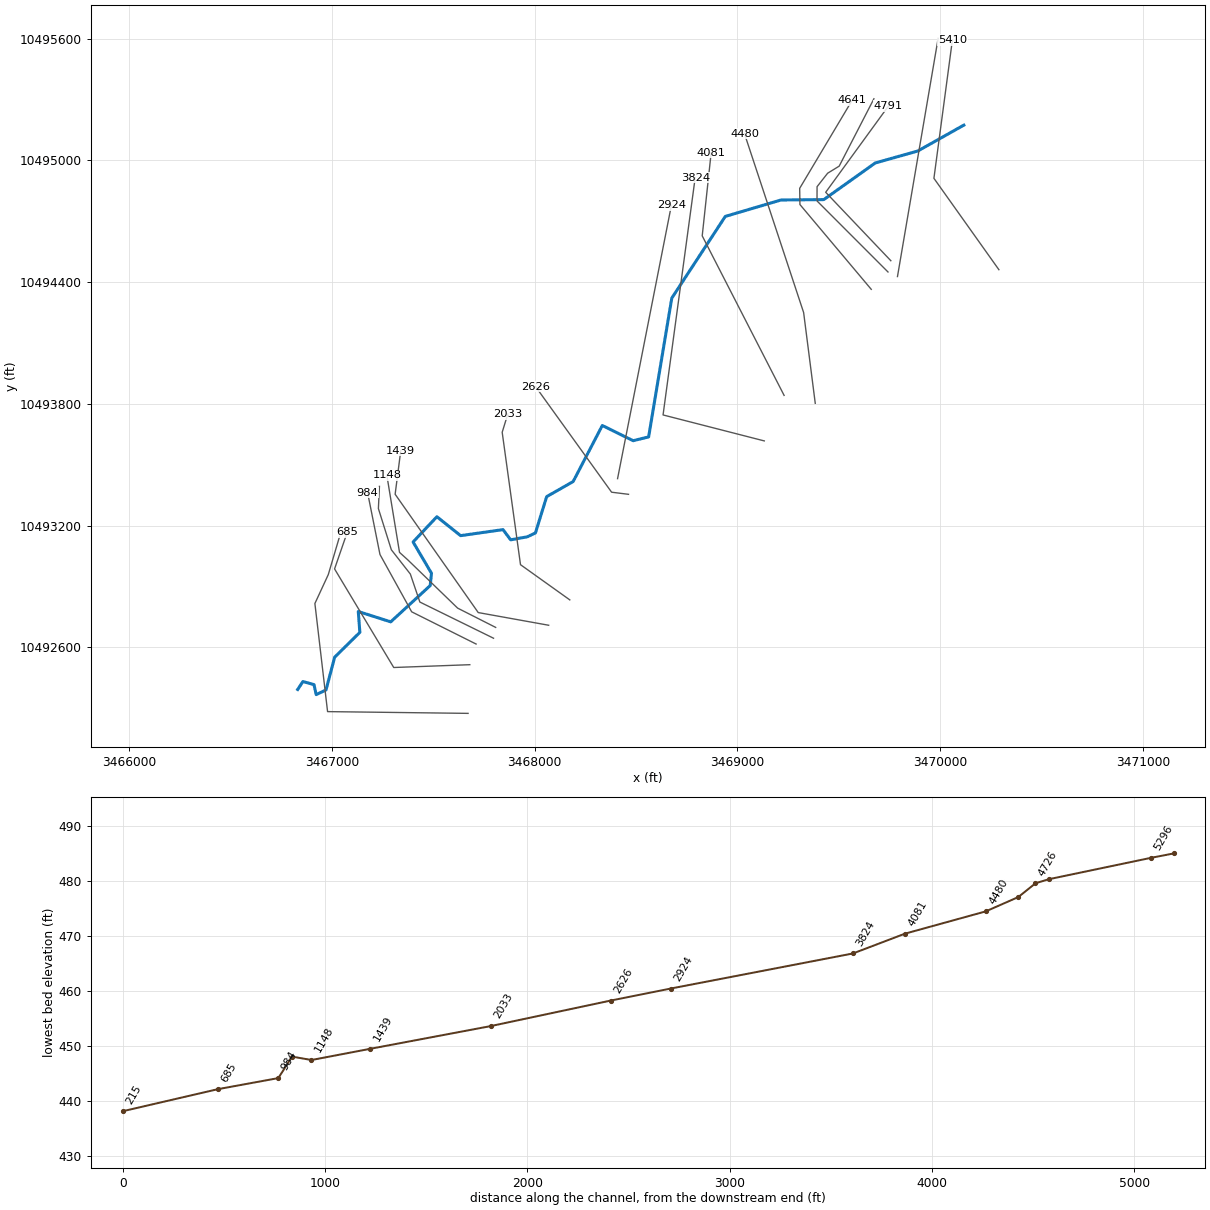
--- UNT014 IN STEL.prj (project) ---

Proj Title=UNT014 IN STEL Base Level Engineering
Current Plan=p01
Default Exp/Contr=0.3,0.1
English Units
Geom File=g01
Flow File=f01
Plan File=p01
Y Axis Title=Elevation
X Axis Title(PF)=Main Channel Distance
X Axis Title(XS)=Station
BEGIN DESCRIPTION:
UNT014 IN STEL
END DESCRIPTION:
DSS Export Rating Curves= 0
DSS Export Rating Curve Sorted= 0
DSS Export Volume Flow Curves= 0
DXF OffsetX= 0
DXF OffsetY= 0
DXF ScaleX= 1
DXF ScaleY= 10

--- UNT014 IN STEL.p01 (plan) ---

Plan Title=Multiple Run
Short Identifier=Multiple
Geom File=g01
Flow File=f01
Subcritical Flow
K Sum by GR= 0
Std Step Tol= 0.01
Critical Tol= 0.01
Num of Std Step Trials= 20
Max Error Tol= 0.3
Flow Tol Ratio= 0.001
Split Flow NTrial= 30
Split Flow Tol= 0.02
Split Flow Ratio= 0.02
Log Output Level= 0
Friction Slope Method= 1
Unsteady Friction Slope Method= 2
Unsteady Bridges Friction Slope Method= 1
Parabolic Critical Depth
Global Vel Dist=  1 , 1 , 1
Global Log Level= 0
CheckData=True
Encroach Param= -1, 0, 0, 0
BEGIN DESCRIPTION:
Multiple Run
END DESCRIPTION:

--- UNT014 IN STEL.f01 (steady flow) ---

Flow Title=Multiple
Program Version=4.10
Number of Profiles= 7
Profile Names=10-year,25-year,50-year,1pct_min,100-year,1pct_plu,500-year
River Rch & RM=UNT014 IN STEL,Reach-1         ,5410
     361     464     543     465     629     851     841
River Rch & RM=UNT014 IN STEL,Reach-1         ,2033
     464     608     721     625     845    1143    1157
Boundary for River Rch & Prof#=UNT014 IN STEL,Reach-1         , 1
Up Type= 0
Dn Type= 3
Dn Slope=0.0083
Boundary for River Rch & Prof#=UNT014 IN STEL,Reach-1         , 2
Up Type= 0
Dn Type= 3
Dn Slope=0.0083
Boundary for River Rch & Prof#=UNT014 IN STEL,Reach-1         , 3
Up Type= 0
Dn Type= 3
Dn Slope=0.0083
Boundary for River Rch & Prof#=UNT014 IN STEL,Reach-1         , 4
Up Type= 0
Dn Type= 3
Dn Slope=0.0083
Boundary for River Rch & Prof#=UNT014 IN STEL,Reach-1         , 5
Up Type= 0
Dn Type= 3
Dn Slope=0.0083
Boundary for River Rch & Prof#=UNT014 IN STEL,Reach-1         , 6
Up Type= 0
Dn Type= 3
Dn Slope=0.0083
Boundary for River Rch & Prof#=UNT014 IN STEL,Reach-1         , 7
Up Type= 0
Dn Type= 3
Dn Slope=0.0083
DSS Import GetInterval= 0
DSS Import GetPeak= 0
DSS Import FillOption= 0

--- UNT014 IN STEL.g01 (geometry) ---

Geom Title=Existing Conditions
Program Version=4.10

River Reach=UNT014 IN STEL  ,Reach-1
Reach XY= 30
      3470116.25       10495174.      3469889.13      10495046.4
       3469679.4     10494987.37      3469425.88     10494806.82
      3469214.74     10494804.91      3468940.21     10494723.96
      3468676.54      10494321.4      3468562.37     10493636.94
      3468485.98     10493618.19       3468333.9     10493693.19
      3468190.15      10493416.8       3468059.6     10493342.49
      3468004.26      10493163.6      3467964.33      10493144.5
       3467882.1     10493129.56      3467844.34     10493179.91
      3467635.33     10493150.14      3467518.33     10493243.42
      3467400.96     10493118.89      3467491.67     10492964.81
      3467485.46     10492904.07      3467290.82     10492725.14
      3467130.89     10492776.02      3467138.52     10492673.17
      3467014.33     10492550.83      3466971.73     10492389.41
      3466923.21     10492366.37      3466912.48     10492415.62
      3466857.86     10492430.98      3466832.11     10492391.64

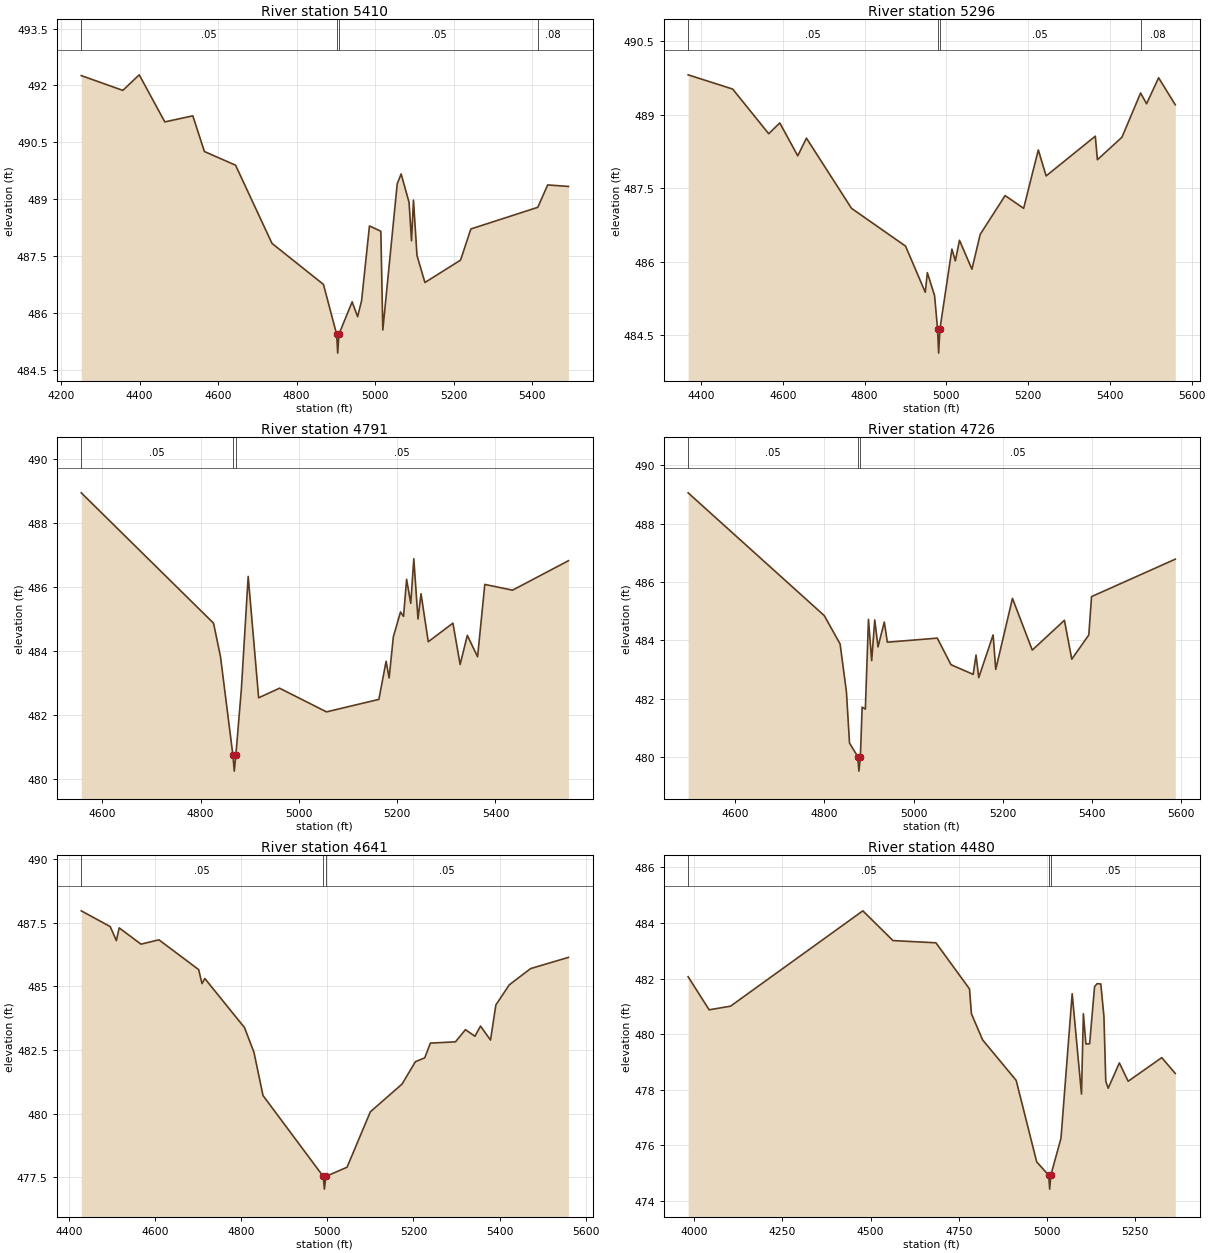
Type RM Length L Ch R = 1 ,5410    ,114,114,114
BEGIN DESCRIPTION:
UNT014 IN STEL 10.0
END DESCRIPTION:
XS GIS Cut Line= 3
      3470289.07     10494461.27      3469968.76     10494911.79
       3470059.9     10495594.05
#Sta/Elev= 30
  4251.6  492.26  4357.4  491.87  4399.3  492.28  4464.4  491.04  4535.8   491.2
  4565.3  490.26  4644.7   489.9  4737.5  487.84  4868.6  486.76  4902.1  485.45
  4904.9  484.95  4908.1  485.45  4941.7   486.3  4955.6  485.91  4965.7  486.33
  4985.8   488.3  5014.8  488.16  5019.8  485.56  5056.5  489.41  5066.5  489.67
  5086.7  488.92  5092.9  487.91  5097.9  488.98  5106.9  487.52  5127.1  486.81
  5217.9   487.4  5244.1  488.22  5414.6  488.79  5439.8  489.38  5492.7  489.34
#Mann= 4 ,-1 , 0
  4251.6     .05       0  4902.1     .04       0  4908.1     .05       0
  5414.6     .08       0
Bank Sta=4902.1,4908.1
XS Rating Curve= 0 ,0
Exp/Cntr=0.3,0.1

Type RM Length L Ch R = 1 ,5296    ,505,505,505
BEGIN DESCRIPTION:
Mapping XS a3390b80
END DESCRIPTION:
XS GIS Cut Line= 2
      3469789.07      10494427.4      3469989.59     10495601.91
#Sta/Elev= 30
  4368.5  489.81  4477.5  489.52  4565.6  488.61  4592.7  488.83  4636.6  488.16
  4657.9  488.52  4768.1  487.09  4900.3  486.32  4948.5  485.38  4953.6  485.78
  4971.3  485.31  4978.5  484.64  4981.2  484.14  4984.5  484.64  5013.7  486.26
  5022.1  486.02  5032.2  486.44  5062.6  485.85  5082.9  486.56  5143.8  487.35
  5189.1  487.09    5225  488.28  5244.1  487.75  5364.4  488.56  5369.5  488.08
  5429.7  488.54  5475.2  489.44  5489.8  489.22  5519.2  489.75    5560   489.2
#Mann= 4 ,-1 , 0
  4368.5     .05       0  4978.5     .04       0  4984.5     .05       0
  5475.2     .08       0
Bank Sta=4978.5,4984.5
XS Rating Curve= 0 ,0
Exp/Cntr=0.3,0.1

Type RM Length L Ch R = 1 ,4791    ,65,65,65
BEGIN DESCRIPTION:
Mapping XS 59975189
END DESCRIPTION:
XS GIS Cut Line= 3
      3469756.35     10494505.55       3469435.2     10494842.97
      3469744.51     10495268.01
#Sta/Elev= 30
    4557  488.95  4826.2  484.88  4840.3  483.84  4865.6  480.76  4868.4  480.26
  4871.6  480.76  4882.8  482.81  4896.7  486.34    4918  482.55  4960.5  482.85
  5056.1  482.11  5162.7   482.5  5177.4  483.69  5183.6  483.17  5192.1  484.45
  5206.7  485.23  5212.9  485.09  5219.1  486.25  5227.6   485.5  5233.8  486.89
  5242.3  485.01  5248.5   485.8  5263.2   484.3  5313.4  484.88  5328.1  483.59
  5342.7   484.5  5363.6  483.83  5378.3  486.09  5434.7  485.91  5548.5  486.83
#Mann= 3 ,-1 , 0
    4557     .05       0  4865.6    .035       0  4871.6     .05       0
Bank Sta=4865.6,4871.6
XS Rating Curve= 0 ,0
Exp/Cntr=0.3,0.1

Type RM Length L Ch R = 1 ,4726    ,85,85,85
BEGIN DESCRIPTION:
Mapping XS 197860ab
END DESCRIPTION:
XS GIS Cut Line= 6
      3469742.34     10494450.01      3469392.44     10494800.25
      3469392.65     10494870.51      3469444.73     10494936.92
      3469501.69     10494971.83      3469672.93     10495303.97
#Sta/Elev= 30
  4494.6  489.05  4799.9  484.85  4835.4  483.88  4849.6  482.24  4856.5  480.49
  4874.9  480.03  4877.6  479.53  4880.9  480.03  4884.8  481.72    4892  481.65
    4899  484.72  4906.2  483.31  4913.1   484.7  4920.4  483.78  4934.5  484.63
  4941.4  483.94  5053.3  484.08  5084.1  483.17  5133.8  482.84  5140.2   483.5
  5146.3  482.73  5178.5  484.19  5184.4  483.01  5221.9  485.44  5266.3  483.67
  5338.4  484.69  5354.9  483.36  5393.1  484.19  5399.2   485.5    5587  486.78
#Mann= 3 ,-1 , 0
  4494.6     .05       0  4874.9    .035       0  4880.9     .05       0
Bank Sta=4874.9,4880.9
XS Rating Curve= 0 ,0
Exp/Cntr=0.3,0.1

Type RM Length L Ch R = 1 ,4641    ,161,161,161
BEGIN DESCRIPTION:
Mapping XS 442c0b1c
END DESCRIPTION:
XS GIS Cut Line= 4
      3469659.82     10494364.44      3469308.22     10494782.51
      3469306.92     10494862.37      3469566.03     10495297.19
#Sta/Elev= 30
  4427.9  487.97  4495.2  487.35  4509.5   486.8    4516   487.3  4566.7  486.66
  4608.4  486.83  4700.7  485.66  4708.5  485.11    4715  485.31  4807.3  483.38
  4829.3  482.41  4850.3  480.71  4990.3  477.53    4993  477.03  4996.3  477.53
  5045.6  477.89  5099.8  480.07  5173.5  481.16  5204.5  482.04  5226.1  482.19
  5239.4  482.77  5297.6  482.82  5320.9   483.3  5342.9  483.04  5355.8  483.44
  5379.1  482.89  5391.5  484.27  5422.7  485.06  5472.3   485.7  5560.2  486.14
#Mann= 3 ,-1 , 0
  4427.9     .05       0  4990.3    .035       0  4996.3     .05       0
Bank Sta=4990.3,4996.3
XS Rating Curve= 0 ,0
Exp/Cntr=0.3,0.1

Type RM Length L Ch R = 1 ,4480    ,399,399,399
BEGIN DESCRIPTION:
UNT014 IN STEL 8.0
END DESCRIPTION:
XS GIS Cut Line= 3
      3469383.74     10493802.55      3469326.41     10494250.04
      3469034.73     10495132.01
#Sta/Elev= 30
  3983.3  482.07  4042.9  480.88  4103.4  481.01  4478.3  484.44  4563.7  483.37
  4685.3  483.29  4780.5  481.63  4785.8  480.74  4817.5   479.8  4912.7  478.34
  4970.8  475.41  5004.8  474.93  5007.6  474.43  5010.8  474.93  5039.6  476.26
  5071.3  481.46  5097.7  477.85    5103  480.74  5110.2  479.65  5120.8  479.66
  5134.7  481.71  5141.8  481.82  5152.4  481.81  5161.2  480.65  5166.5  478.31
  5173.4  478.06    5205  478.97  5229.9  478.31  5325.1  479.16  5363.4  478.59
#Mann= 3 ,-1 , 0
  3983.3     .05       0  5004.8     .04       0  5010.8     .05       0
Bank Sta=5004.8,5010.8
XS Rating Curve= 0 ,0
Exp/Cntr=0.3,0.1

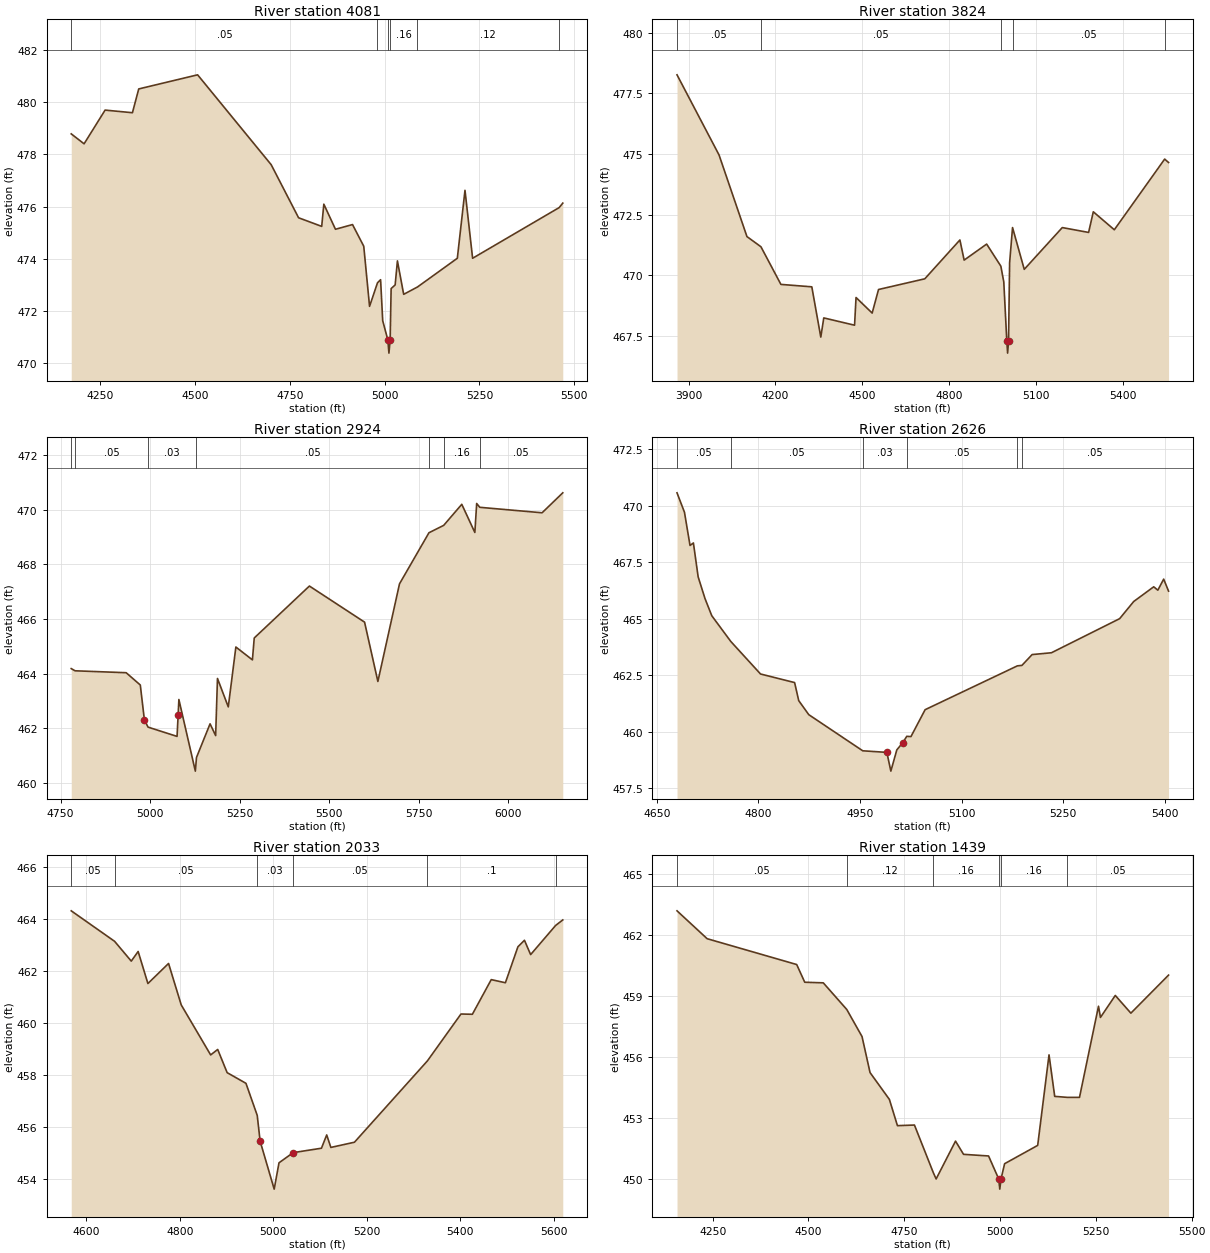
Type RM Length L Ch R = 1 ,4081    ,257,257,257
BEGIN DESCRIPTION:
Mapping XS 3bfdf63b
END DESCRIPTION:
XS GIS Cut Line= 3
      3469230.11     10493841.62      3468826.45     10494628.09
      3468870.57     10495038.11
#Sta/Elev= 30
  4173.4  478.78  4207.3   478.4  4262.7  479.69  4334.8  479.59  4351.4   480.5
  4506.7  481.04  4700.8   477.6    4773  475.57    4834  475.24  4839.6  476.09
  4870.3  475.13  4915.3  475.31  4944.9  474.48  4960.2  472.18  4981.1  473.08
  4989.3   473.2  4994.9  471.63  5008.5  470.89  5011.3  470.39  5014.5  470.89
  5017.1  472.86  5027.7     473  5033.7  473.92  5050.2  472.64  5086.5  472.92
  5191.7  474.02  5211.9  476.62    5232  474.02  5460.4  475.96  5469.8  476.13
#Mann= 6 ,-1 , 0
  4173.4     .05       0  4981.1     .16       0  5008.5     .07       0
  5014.5     .16       0  5086.5     .12       0  5460.4     .05       0
Bank Sta=5008.5,5014.5
XS Rating Curve= 0 ,0
Exp/Cntr=0.3,0.1

Type RM Length L Ch R = 1 ,3824    ,900,900,900
BEGIN DESCRIPTION:
Mapping XS f848318e
END DESCRIPTION:
XS GIS Cut Line= 3
      3469132.51     10493617.16      3468633.39      10493745.2
      3468791.81     10494914.93
#Sta/Elev= 30
  3860.4  478.26  4005.4  474.96  4101.6   471.6  4149.9  471.18  4218.8  469.63
  4325.4  469.53  4356.4  467.46  4366.7  468.25  4472.9  467.95    4478  469.09
  4533.6  468.45  4555.6  469.42  4715.2  469.86  4836.3  471.46  4850.9  470.63
  4928.6  471.29  4977.6  470.38  4987.7  469.73  4998.1   467.3  5000.9   466.8
  5004.1   467.3  5007.8  470.52  5017.9  471.97  5058.3  470.25  5189.5  471.97
  5280.3  471.77  5296.5  472.62    5369  471.88  5542.7  474.79  5556.1  474.65
#Mann= 5 ,-1 , 0
  3860.4     .05       0  4149.9     .05       0  4977.6     .03       0
  5017.9     .05       0  5542.7     .12       0
Bank Sta=4998.1,5004.1
XS Rating Curve= 0 ,0
Exp/Cntr=0.3,0.1

Type RM Length L Ch R = 1 ,2924    ,298,298,298
BEGIN DESCRIPTION:
UNT014 IN STEL 4.0
END DESCRIPTION:
XS GIS Cut Line= 2
      3468409.11     10493431.16      3468674.39     10494778.39
#Sta/Elev= 30
  4779.6  464.19  4790.3  464.11    4933  464.04  4972.5  463.59  4983.9  462.32
  4994.1  462.05  5075.2  461.71 5078.18  462.48  5080.3  463.06  5126.3  460.44
  5129.5  460.94  5167.4  462.17    5183  461.74  5188.1  463.83  5218.3  462.79
  5239.5  464.98  5285.7  464.51  5290.8  465.31  5444.9  467.21    5599  465.89
  5636.2  463.72  5696.6  467.29  5778.9  469.16  5820.1  469.43  5870.6   470.2
  5907.1  469.17  5912.2  470.23  5920.9  470.09  6094.9  469.89  6152.7  470.62
#Mann= 7 ,-1 , 0
  4779.6     .16       0  4790.3     .05       0  4994.1     .03       0
  5129.5     .05       0  5778.9     .12       0  5820.1     .16       0
  5920.9     .05       0
Bank Sta=4983.9,5078.18
XS Rating Curve= 0 ,0
Exp/Cntr=0.3,0.1

Type RM Length L Ch R = 1 ,2626    ,593,593,593
BEGIN DESCRIPTION:
UNT014 IN STEL 4.1
END DESCRIPTION:
XS GIS Cut Line= 3
      3468463.06     10493353.88      3468379.75      10493364.3
      3468004.77     10493885.09
#Sta/Elev= 30
  4679.9  470.57  4690.9  469.71  4699.1  468.24  4704.1  468.35  4711.1  466.85
  4721.2  465.89  4731.2  465.13  4759.3  463.99  4803.2  462.55  4853.5  462.17
  4859.6  461.37  4874.4  460.75  4954.1  459.15  4989.7  459.08  4995.6  458.25
  5004.4  459.19  5013.2  459.51  5019.1  459.79  5025.3  459.78  5046.2  460.97
  5182.4  462.91  5189.1  462.93  5204.2  463.41  5232.7  463.49  5333.4     465
  5354.2  465.76  5383.7  466.41  5389.8  466.26  5398.4  466.75  5405.6  466.22
#Mann= 6 ,-1 , 0
  4679.9     .05       0  4759.3     .05       0  4954.1     .03       0
  5019.1     .05       0  5182.4     .12       0  5189.1     .05       0
Bank Sta=4989.7,5013.2
XS Rating Curve= 0 ,0
Exp/Cntr=0.3,0.1

Type RM Length L Ch R = 1 ,2033    ,594,594,594
BEGIN DESCRIPTION:
UNT014 IN STEL 3.0
END DESCRIPTION:
XS GIS Cut Line= 4
      3468173.61     10492833.39      3467930.58     10493006.99
       3467840.3     10493659.77      3467868.07     10493750.03
#Sta/Elev= 30
  4567.4   464.3  4660.2  463.13  4695.9  462.37  4710.6  462.74  4731.5  461.51
  4775.7  462.28  4802.8  460.69  4865.8  458.77  4880.9  458.98  4901.1  458.09
  4941.4  457.68  4965.5  456.45  4971.7  455.46  5001.8  453.62  5012.1  454.63
  5042.4  455.02    5103  455.19  5114.2   455.7  5123.1  455.22  5173.6  455.42
  5329.7  458.54  5401.6  460.34    5426  460.33  5466.4  461.66  5496.7  461.54
  5523.5  462.92  5537.5  463.17  5550.7  462.62  5604.3  463.74  5619.5  463.95
#Mann= 6 ,-1 , 0
  4567.4     .05       0  4660.2     .05       0  4965.5     .03       0
  5042.4     .05       0  5329.7      .1       0  5604.3     .05       0
Bank Sta=4971.7,5042.4
XS Rating Curve= 0 ,0
Exp/Cntr=0.3,0.1

Type RM Length L Ch R = 1 ,1439    ,291,291,291
BEGIN DESCRIPTION:
UNT014 IN STEL 2.0
END DESCRIPTION:
XS GIS Cut Line= 4
      3468069.46     10492708.38      3467722.24     10492770.88
      3467312.52     10493354.21       3467340.3     10493569.48
#Sta/Elev= 30
    4157  463.19  4235.6  461.82  4469.3  460.55  4490.3  459.68  4538.7  459.65
    4600  458.34  4639.8  457.01  4660.7  455.24  4711.2  453.92  4732.2  452.63
  4776.6  452.66  4825.8  450.32  4833.2  450.01  4883.8  451.87  4904.7  451.22
    4970  451.14  4996.5  450.01  4999.3  449.51  5002.5  450.01  5011.9  450.76
  5098.2  451.66  5127.8  456.11  5142.6  454.07  5175.8  454.02  5207.3  454.02
  5256.9   458.5    5262  457.95  5300.7  459.03  5341.4  458.16  5439.7  460.03
#Mann= 6 ,-1 , 0
    4157     .05       0    4600     .12       0  4825.8     .16       0
  4996.5     .07       0  5002.5     .16       0  5175.8     .05       0
Bank Sta=4996.5,5002.5
XS Rating Curve= 0 ,0
Exp/Cntr=0.3,0.1

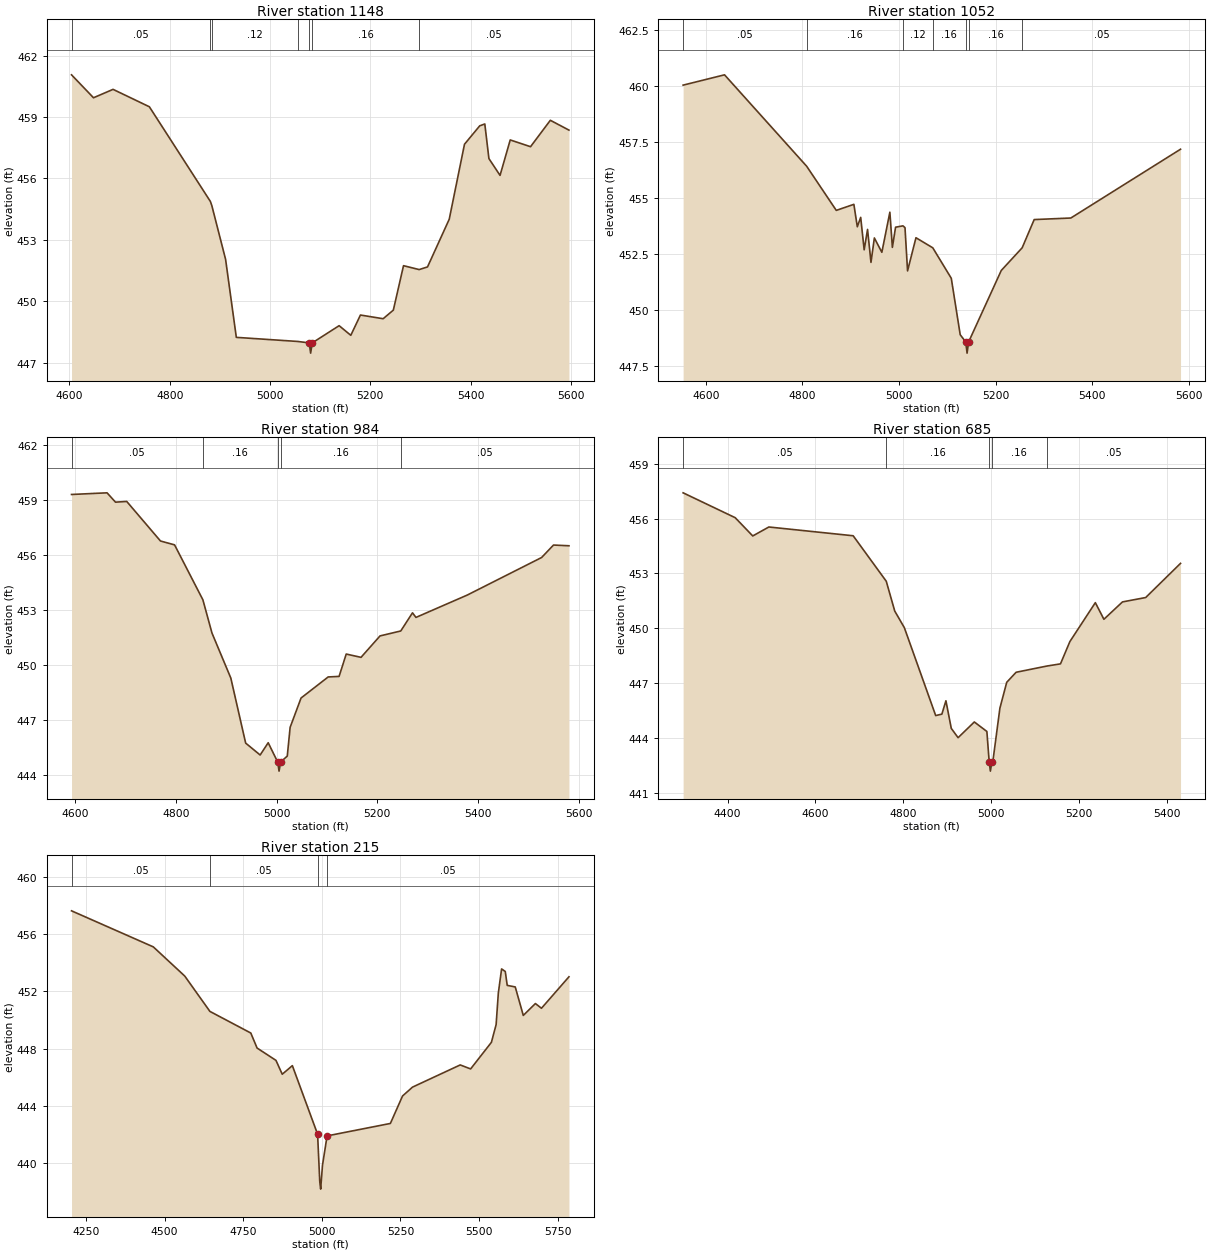
Type RM Length L Ch R = 1 ,1148    ,96,96,96
BEGIN DESCRIPTION:
Mapping XS 93591362
END DESCRIPTION:
XS GIS Cut Line= 5
      3467808.12     10492697.78      3467620.58     10492792.85
      3467374.49     10493031.13      3467334.13     10493067.59
      3467271.72      10493447.2
#Sta/Elev= 30
  4604.2  461.06    4648  459.94    4687  460.35  4759.4   459.5    4881  454.88
  4883.9  454.68  4911.4  452.05  4932.8  448.24  5055.1  448.04  5078.2  447.97
    5081  447.47  5084.2  447.97  5137.8  448.81  5161.1  448.34  5180.3  449.33
  5225.6  449.15  5245.9  449.57  5266.2  451.74  5297.4  451.55  5314.1  451.68
  5357.4  454.01  5387.8  457.67  5418.2  458.57  5428.3  458.66  5436.5  456.97
  5458.7  456.15    5479  457.88  5519.5  457.55    5559  458.84  5596.1  458.36
#Mann= 7 ,-1 , 0
  4604.2     .05       0    4881     .16       0  4883.9     .12       0
  5055.1     .16       0  5078.2     .07       0  5084.2     .16       0
  5297.4     .05       0
Bank Sta=5078.2,5084.2
XS Rating Curve= 0 ,0
Exp/Cntr=0.3,0.1

Type RM Length L Ch R = 1 ,1052    ,68,68,68
BEGIN DESCRIPTION:
Mapping XS 84ea61b1
END DESCRIPTION:
XS GIS Cut Line= 6
      3467797.67     10492644.41      3467434.39      10492822.8
      3467387.51     10492960.82      3467293.76     10493080.61
      3467229.96     10493283.74      3467235.17     10493393.09
#Sta/Elev= 30
    4553  460.05  4638.7  460.51  4808.7  456.43    4870  454.46  4906.4  454.73
  4913.5  453.73  4920.5  454.15  4927.7   452.7  4934.7  453.61  4941.8  452.14
  4948.8  453.23  4964.3  452.59  4980.9  454.38  4986.1  452.81  4992.7  453.71
    5008  453.77  5012.2  453.69  5017.5  451.76  5034.9  453.24  5069.7  452.79
    5108  451.43  5126.5  448.91  5137.9  448.59  5140.7  448.09  5143.9  448.59
  5211.5  451.78  5254.7  452.79  5279.6  454.05  5355.5  454.12  5582.5  457.19
#Mann= 7 ,-1 , 0
    4553     .05       0  4808.7     .16       0    5008     .12       0
  5069.7     .16       0  5137.9     .07       0  5143.9     .16       0
  5254.7     .05       0
Bank Sta=5137.9,5143.9
XS Rating Curve= 0 ,0
Exp/Cntr=0.3,0.1

Type RM Length L Ch R = 1 ,984     ,299,299,299
BEGIN DESCRIPTION:
Mapping XS 419683cb
END DESCRIPTION:
XS GIS Cut Line= 4
       3467711.7     10492615.78      3467394.02     10492774.62
      3467237.77     10493057.17      3467176.85     10493361.79
#Sta/Elev= 30
  4592.2  459.29  4662.8  459.38  4679.6  458.87  4701.9  458.91    4769  456.75
    4797  456.54  4853.3  453.54  4871.3  451.73  4908.8  449.27  4938.3  445.72
  4967.1  445.07  4983.1  445.74  5001.9  444.69  5004.7  444.19  5007.9  444.69
    5021  445.01  5026.7  446.58  5048.4  448.18  5102.3  449.33    5124  449.36
  5138.2  450.58  5167.6   450.4  5205.4  451.57  5246.6  451.84  5269.9  452.83
  5276.8  452.58  5378.8   453.8  5526.6  455.85  5550.2  456.53  5580.9  456.49
#Mann= 5 ,-1 , 0
  4592.2     .05       0  4853.3     .16       0  5001.9     .07       0
  5007.9     .16       0  5246.6     .05       0
Bank Sta=5001.9,5007.9
XS Rating Curve= 0 ,0
Exp/Cntr=0.3,0.1

Type RM Length L Ch R = 1 ,685     ,470,470,470
BEGIN DESCRIPTION:
UNT014 IN STEL 1.2
END DESCRIPTION:
XS GIS Cut Line= 4
       3467680.6     10492513.93      3467305.58     10492500.04
      3467013.91     10492986.15      3467076.39     10493166.66
#Sta/Elev= 30
  4298.7  457.41  4417.3  456.05  4457.3  455.05    4494  455.54  4686.1  455.06
  4761.5  452.57  4780.8  450.94  4802.7  450.03  4874.1  445.22  4888.2   445.3
  4897.4  446.03  4909.6  444.52  4925.1  444.01  4962.1  444.87  4990.7  444.35
    4996  442.68  4998.7  442.18    5002  442.68  5004.8   442.8  5020.4  445.63
  5035.9  447.04  5057.3  447.59  5127.3  447.93  5158.4  448.05  5179.8  449.27
  5237.8   451.4  5257.3  450.49  5299.6  451.44  5352.5  451.68  5431.9  453.55
#Mann= 5 ,-1 , 0
  4298.7     .05       0  4761.5     .16       0    4996     .07       0
    5002     .16       0  5127.3     .05       0
Bank Sta=4996,5002
XS Rating Curve= 0 ,0
Exp/Cntr=0.3,0.1

Type RM Length L Ch R = 1 ,215     ,0,0,0
BEGIN DESCRIPTION:
UNT014 IN STEL 1.0
END DESCRIPTION:
XS GIS Cut Line= 5
      3467672.17     10492273.92      3466979.42      10492282.6
      3466916.92     10492815.59      3466982.89     10492957.95
      3467038.45     10493145.45
#Sta/Elev= 30
  4204.2  457.63  4464.3  455.11  4564.3  453.07  4644.3   450.6  4774.3  449.09
  4794.3  448.04  4854.3  447.18  4874.3  446.21  4906.5  446.81  4986.7  442.02
  4993.7  438.68  4996.5  438.18  5002.3  439.85  5016.9   441.9  5218.2  442.77
  5256.9  444.69  5288.7  445.31  5440.3  446.86  5473.4  446.58  5539.5  448.44
  5554.5  449.68  5561.5  451.88  5571.9  453.57  5583.6  453.39  5589.8  452.42
  5615.3  452.31  5640.9  450.32  5679.4  451.15  5698.7  450.82  5786.1  453.02
#Mann= 4 ,-1 , 0
  4204.2     .05       0  4644.3     .05       0  4986.7     .03       0
  5016.9     .05       0
Bank Sta=4986.7,5016.9
XS Rating Curve= 0 ,0
Exp/Cntr=0.3,0.1

Chan Stop Cuts=-1
Use User Specified Reach Order=0
Composite Channel Slope=5