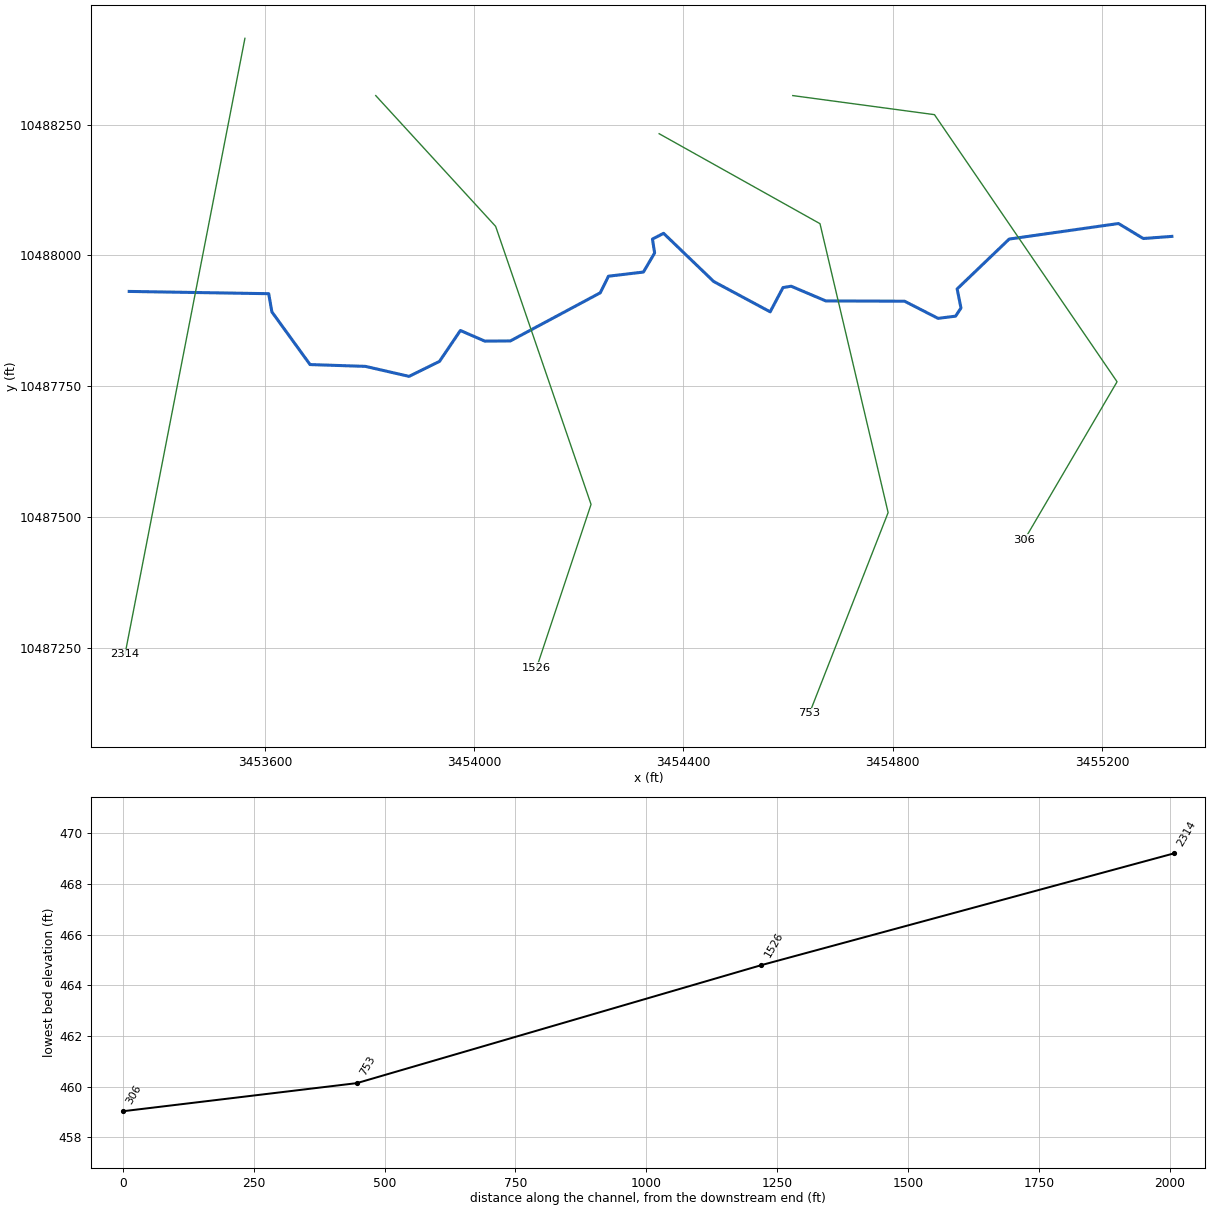
--- UNT015 IN STEL.prj (project) ---

Proj Title=UNT015 IN STEL Base Level Engineering
Current Plan=p01
Default Exp/Contr=0.3,0.1
English Units
Geom File=g01
Flow File=f01
Plan File=p01
BEGIN DESCRIPTION:
UNT015 IN STEL
END DESCRIPTION:

--- UNT015 IN STEL.p01 (plan) ---

Plan Title=Multiple Run
Short Identifier=Multiple
Geom File=g01
Flow File=f01
Subcritical Flow
K Sum by GR= 0
Std Step Tol= 0.01
Critical Tol= 0.01
Num of Std Step Trials= 20
Max Error Tol= 0.3
Flow Tol Ratio= 0.001
Split Flow NTrial= 30
Split Flow Tol= 0.02
Split Flow Ratio= 0.02
Log Output Level= 0
Friction Slope Method= 1
Unsteady Friction Slope Method= 2
Unsteady Bridges Friction Slope Method= 1
Parabolic Critical Depth
Global Vel Dist=  1 , 1 , 1
Global Log Level= 0
CheckData=True
Encroach Param= -1, 0, 0, 0
BEGIN DESCRIPTION:
Multiple Run
END DESCRIPTION:

--- UNT015 IN STEL.f01 (steady flow) ---

Flow Title=Multiple
Number of Profiles=7
Profile Names=10-year,25-year,50-year,1pct_min,100-year,1pct_plu,500-year
River Rch & RM= UNT015 IN STEL,Reach-1,2314
     910    1244    1517    1351    1827    2470    2640
Boundary for River Rch & Prof#=UNT015 IN STEL,Reach-1,1
Up Type=0
Dn Type=3
Dn Slope=0.005
Boundary for River Rch & Prof#=UNT015 IN STEL,Reach-1,2
Up Type=0
Dn Type=3
Dn Slope=0.005
Boundary for River Rch & Prof#=UNT015 IN STEL,Reach-1,3
Up Type=0
Dn Type=3
Dn Slope=0.005
Boundary for River Rch & Prof#=UNT015 IN STEL,Reach-1,4
Up Type=0
Dn Type=3
Dn Slope=0.005
Boundary for River Rch & Prof#=UNT015 IN STEL,Reach-1,5
Up Type=0
Dn Type=3
Dn Slope=0.005
Boundary for River Rch & Prof#=UNT015 IN STEL,Reach-1,6
Up Type=0
Dn Type=3
Dn Slope=0.005
Boundary for River Rch & Prof#=UNT015 IN STEL,Reach-1,7
Up Type=0
Dn Type=3
Dn Slope=0.005

--- UNT015 IN STEL.g01 (geometry) ---

Geom Title=Existing Conditions

River Reach=UNT015 IN STEL,Reach-1
Reach XY= 30
      3453340.90     10487931.33      3453607.39     10487926.99
      3453613.47     10487892.26      3453686.39     10487791.57
      3453792.29     10487788.10      3453875.62     10487769.00
      3453933.78     10487797.65      3453973.71     10487856.67
      3454020.34     10487836.36      3454069.20     10487836.71
      3454241.07     10487928.72      3454256.70     10487960.41
      3454323.53     10487968.38      3454344.89     10488004.84
      3454340.72     10488031.41      3454362.07     10488042.34
      3454457.88     10487950.22      3454565.72     10487892.34
      3454590.20     10487938.70      3454605.82     10487941.30
      3454671.97     10487913.18      3454822.49     10487912.65
      3454886.55     10487879.84      3454920.05     10487884.08
      3454930.30     10487899.63      3454923.01     10487936.09
      3455022.49     10488031.41      3455231.35     10488061.09
      3455278.74     10488032.45      3455333.28     10488036.50

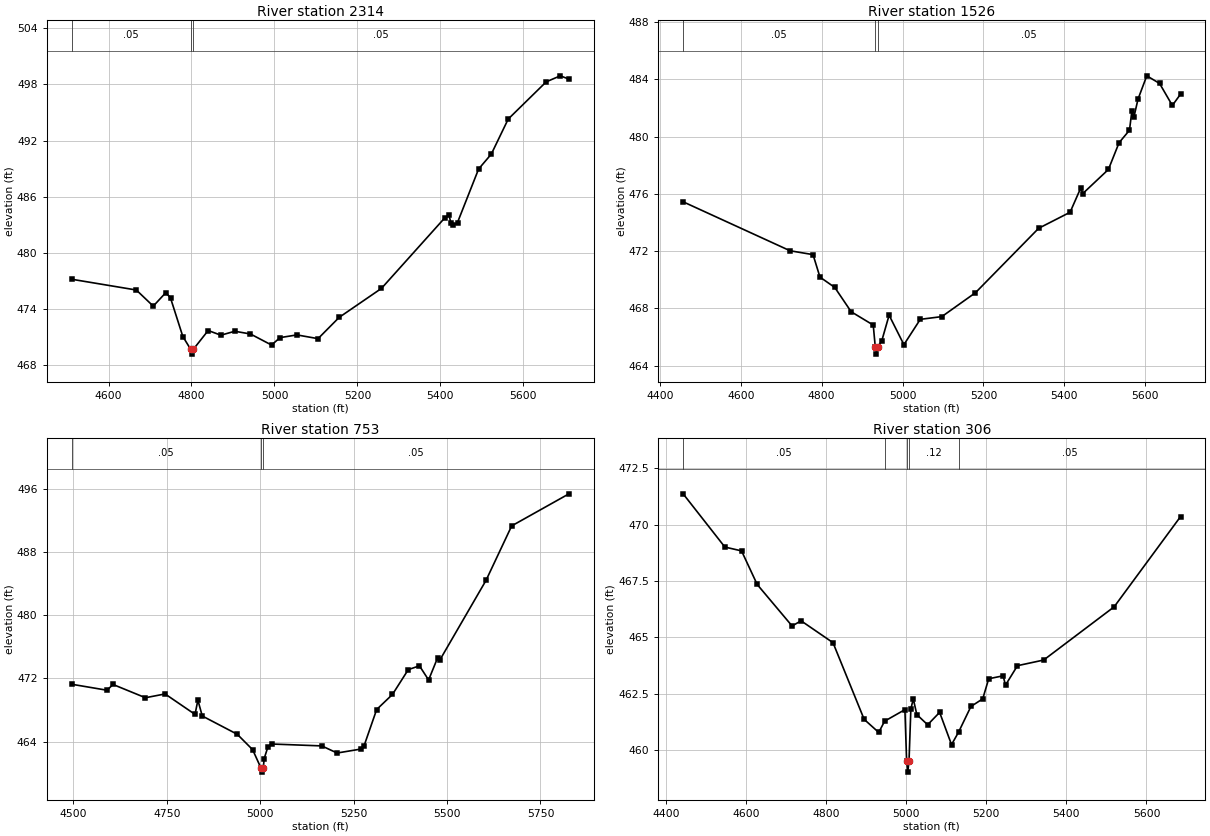
Type RM Length L Ch R = 1,2314,788,788,788
BEGIN DESCRIPTION:
UNT015 IN STEL 2.0
END DESCRIPTION:
XS GIS Cut Line= 2
      3453561.95     10488414.99      3453332.78     10487237.90
#Sta/Elev= 30
  4510.8  477.20  4667.0  476.05  4707.8  474.33  4738.3  475.78  4749.5  475.19
  4779.1  471.09  4798.2  469.71  4800.9  469.21  4804.2  469.71  4840.2  471.73
  4870.8  471.23  4904.4  471.65  4942.1  471.36  4993.0  470.18  5013.4  470.97
  5054.2  471.26  5105.1  470.86  5156.0  473.13  5257.9  476.22  5410.7  483.75
  5420.8  484.01  5425.9  483.15  5431.1  482.94  5441.3  483.25  5492.2  488.96
  5522.8  490.55  5563.6  494.29  5655.2  498.26  5689.1  498.90  5710.0  498.55
#Mann=3,-1,0
  4510.8    0.05       0  4798.2    0.03       0  4804.2    0.05       0
Bank Sta=4798.2,4804.2
Exp/Cntr=0.3,0.1

Type RM Length L Ch R = 1,1526,773,773,773
BEGIN DESCRIPTION:
Mapping XS ad196d59
END DESCRIPTION:
XS GIS Cut Line= 4
      3453811.95     10488305.58      3454041.11     10488055.60
      3454223.40     10487524.35      3454119.23     10487211.83
#Sta/Elev= 30
  4457.4  475.44  4721.9  472.02  4778.7  471.75  4795.8  470.18  4832.4  469.46
  4873.0  467.76  4927.6  466.83  4932.6  465.30  4935.3  464.80  4938.6  465.30
  4948.7  465.73  4966.8  467.52  5003.4  465.46  5043.9  467.23  5097.2  467.42
  5180.4  469.09  5336.7  473.59  5414.4  474.71  5440.7  476.40  5446.0  476.02
  5509.2  477.70  5535.6  479.57  5561.3  480.44  5567.2  481.78  5572.5  481.39
  5582.4  482.61  5604.1  484.24  5635.7  483.71  5667.3  482.17  5687.6  482.96
#Mann=3,-1,0
  4457.4    0.05       0  4932.6    0.03       0  4938.6    0.05       0
Bank Sta=4932.6,4938.6
Exp/Cntr=0.3,0.1

Type RM Length L Ch R = 1,753,447,447,447
BEGIN DESCRIPTION:
Mapping XS 5caaa86d
END DESCRIPTION:
XS GIS Cut Line= 4
      3454353.58     10488232.70      3454660.90     10488060.81
      3454791.11     10487508.72      3454640.73     10487124.99
#Sta/Elev= 30
  4494.8  471.27  4589.8  470.51  4605.8  471.24  4692.6  469.56  4745.2  470.04
  4825.4  467.45  4833.0  469.26  4844.7  467.25  4938.5  464.93  4979.6  462.98
  5002.0  460.64  5004.7  460.14  5008.0  460.64  5010.5  461.86  5020.7  463.37
  5031.0  463.70  5164.6  463.46  5205.7  462.56  5269.2  463.06  5277.6  463.44
  5311.6  468.07  5353.9  469.98  5396.2  473.12  5426.1  473.60  5450.6  471.81
  5475.0  474.65  5480.4  474.31  5604.3  484.42  5673.0  491.32  5826.3  495.38
#Mann=3,-1,0
  4494.8    0.05       0  5002.0    0.03       0  5008.0    0.05       0
Bank Sta=5002,5008
Exp/Cntr=0.3,0.1

Type RM Length L Ch R = 1,306,0,0,0
BEGIN DESCRIPTION:
UNT015 IN STEL 1.0
END DESCRIPTION:
XS GIS Cut Line= 4
      3454608.85     10488305.59      3454879.65     10488269.14
      3455228.61     10487758.72      3455051.53     10487456.65
#Sta/Elev= 30
  4443.4  471.37  4547.6  469.01  4589.2  468.84  4628.3  467.35  4715.4  465.51
  4737.8  465.74  4817.5  464.77  4895.3  461.37  4931.7  460.79  4946.4  461.29
  4997.0  461.80  5001.3  459.53  5004.1  459.03  5007.3  459.53  5011.9  461.83
  5017.9  462.28  5026.8  461.58  5053.8  461.13  5083.7  461.68  5113.4  460.25
  5130.9  460.80  5161.8  461.94  5191.3  462.28  5206.2  463.17  5242.1  463.30
  5248.2  462.89  5278.0  463.75  5343.4  464.00  5519.4  466.36  5685.1  470.36
#Mann=5,-1,0
  4443.4    0.05       0  4946.4    0.12       0  5001.3    0.07       0
  5007.3    0.12       0  5130.9    0.05       0
Bank Sta=5001.3,5007.3
Exp/Cntr=0.3,0.1

Chan Stop Cuts=-1