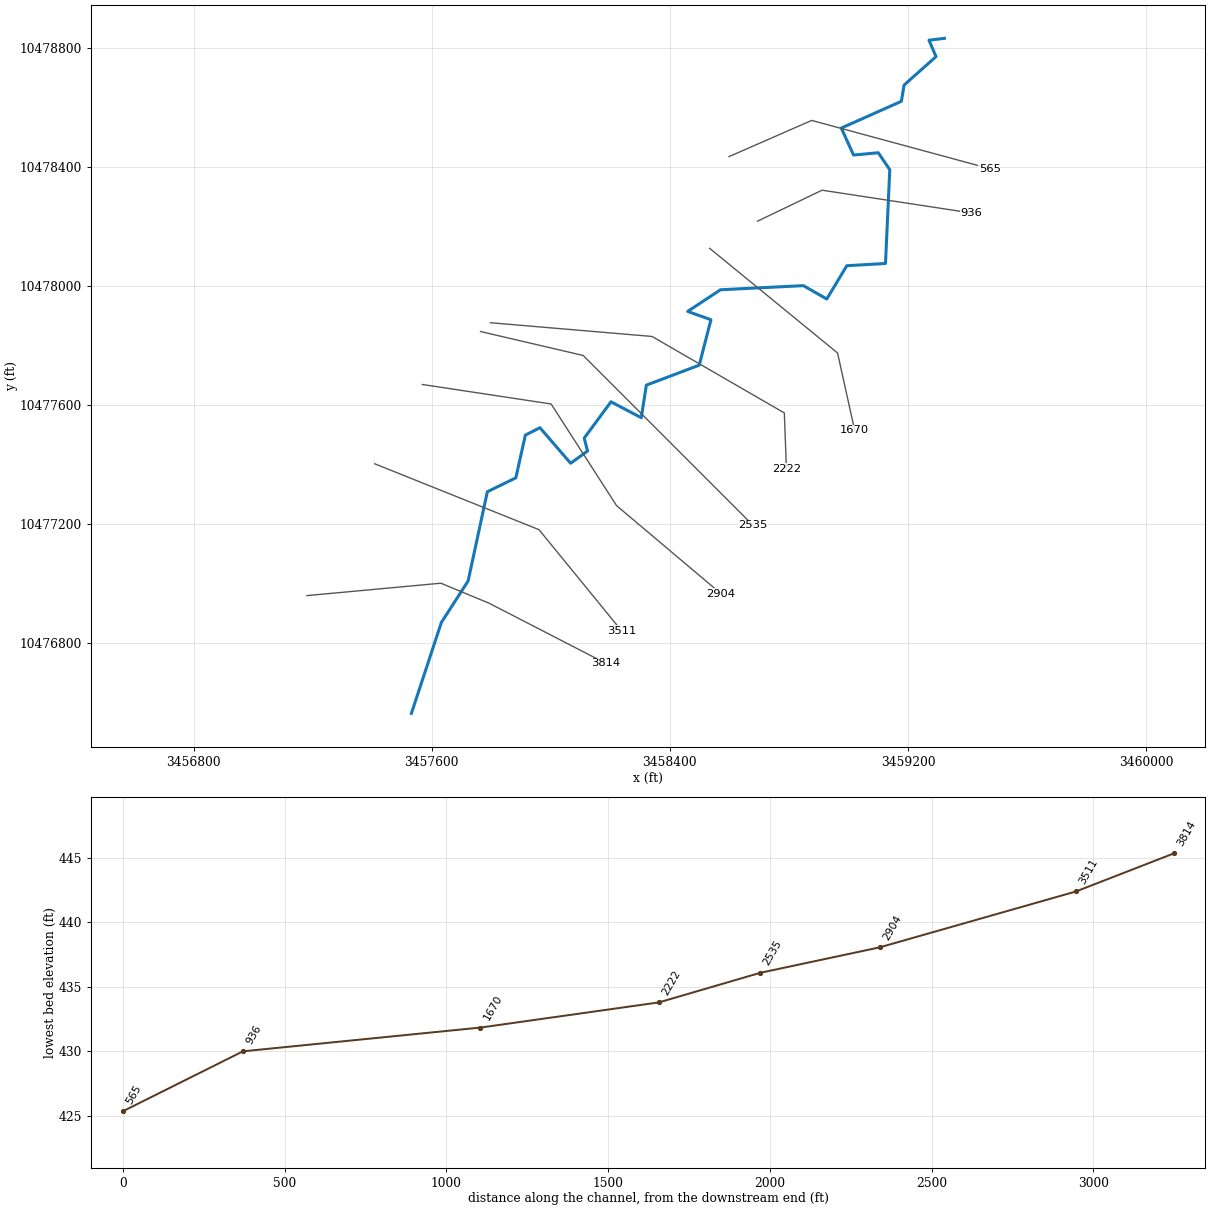
--- UNT018 IN STEL.prj (project) ---

Proj Title=UNT018 IN STEL Base Level Engineering
Current Plan=p01
Default Exp/Contr=0.3,0.1
English Units
Geom File=g01
Flow File=f01
Plan File=p01
Y Axis Title=Elevation
X Axis Title(PF)=Main Channel Distance
X Axis Title(XS)=Station
BEGIN DESCRIPTION:
UNT018 IN STEL
END DESCRIPTION:
DSS Export Rating Curves= 0
DSS Export Rating Curve Sorted= 0
DSS Export Volume Flow Curves= 0
DXF OffsetX= 0
DXF OffsetY= 0
DXF ScaleX= 1
DXF ScaleY= 10

--- UNT018 IN STEL.p01 (plan) ---

Plan Title=Multiple Run
Short Identifier=Multiple
Geom File=g01
Flow File=f01
Subcritical Flow
K Sum by GR= 0
Std Step Tol= 0.01
Critical Tol= 0.01
Num of Std Step Trials= 20
Max Error Tol= 0.3
Flow Tol Ratio= 0.001
Split Flow NTrial= 30
Split Flow Tol= 0.02
Split Flow Ratio= 0.02
Log Output Level= 0
Friction Slope Method= 1
Unsteady Friction Slope Method= 2
Unsteady Bridges Friction Slope Method= 1
Parabolic Critical Depth
Global Vel Dist=  1 , 1 , 1
Global Log Level= 0
CheckData=True
Encroach Param= -1, 0, 0, 0
BEGIN DESCRIPTION:
Multiple Run
END DESCRIPTION:

--- UNT018 IN STEL.f01 (steady flow) ---

Flow Title=Multiple
Number of Profiles=7
Profile Names=10-year,25-year,50-year,1pct_min,100-year,1pct_plu,500-year
River Rch & RM= UNT018 IN STEL,Reach-1,3814
     505     670     801     701     948    1282    1323
Boundary for River Rch & Prof#=UNT018 IN STEL,Reach-1,1
Up Type=0
Dn Type=3
Dn Slope=0.005
Boundary for River Rch & Prof#=UNT018 IN STEL,Reach-1,2
Up Type=0
Dn Type=3
Dn Slope=0.005
Boundary for River Rch & Prof#=UNT018 IN STEL,Reach-1,3
Up Type=0
Dn Type=3
Dn Slope=0.005
Boundary for River Rch & Prof#=UNT018 IN STEL,Reach-1,4
Up Type=0
Dn Type=3
Dn Slope=0.005
Boundary for River Rch & Prof#=UNT018 IN STEL,Reach-1,5
Up Type=0
Dn Type=3
Dn Slope=0.005
Boundary for River Rch & Prof#=UNT018 IN STEL,Reach-1,6
Up Type=0
Dn Type=3
Dn Slope=0.005
Boundary for River Rch & Prof#=UNT018 IN STEL,Reach-1,7
Up Type=0
Dn Type=3
Dn Slope=0.005

--- UNT018 IN STEL.g01 (geometry) ---

Geom Title=Existing Conditions
Program Version=4.10

River Reach=UNT018 IN STEL  ,Reach-1
Reach XY= 30
      3457531.54     10476563.99      3457632.17     10476869.33
      3457722.03     10477008.63      3457786.68     10477308.56
      3457882.44     10477355.22      3457914.28     10477498.67
      3457963.32     10477523.64      3458066.43     10477404.14
      3458123.38     10477445.55      3458112.04     10477488.57
      3458201.93     10477610.64      3458303.78     10477557.23
      3458320.76     10477666.58      3458498.44      10477733.7
      3458537.76      10477886.3       3458459.7     10477914.32
      3458569.87     10477987.02      3458848.44     10478000.88
      3458926.92     10477956.01      3458994.22      10478067.8
      3459124.11     10478075.31      3459138.57     10478390.23
      3459099.95     10478447.33      3459016.91     10478439.55
      3458975.66      10478530.2      3459177.46     10478620.08
      3459186.64     10478674.61      3459293.86     10478770.25
      3459270.29     10478825.33      3459322.11     10478831.64

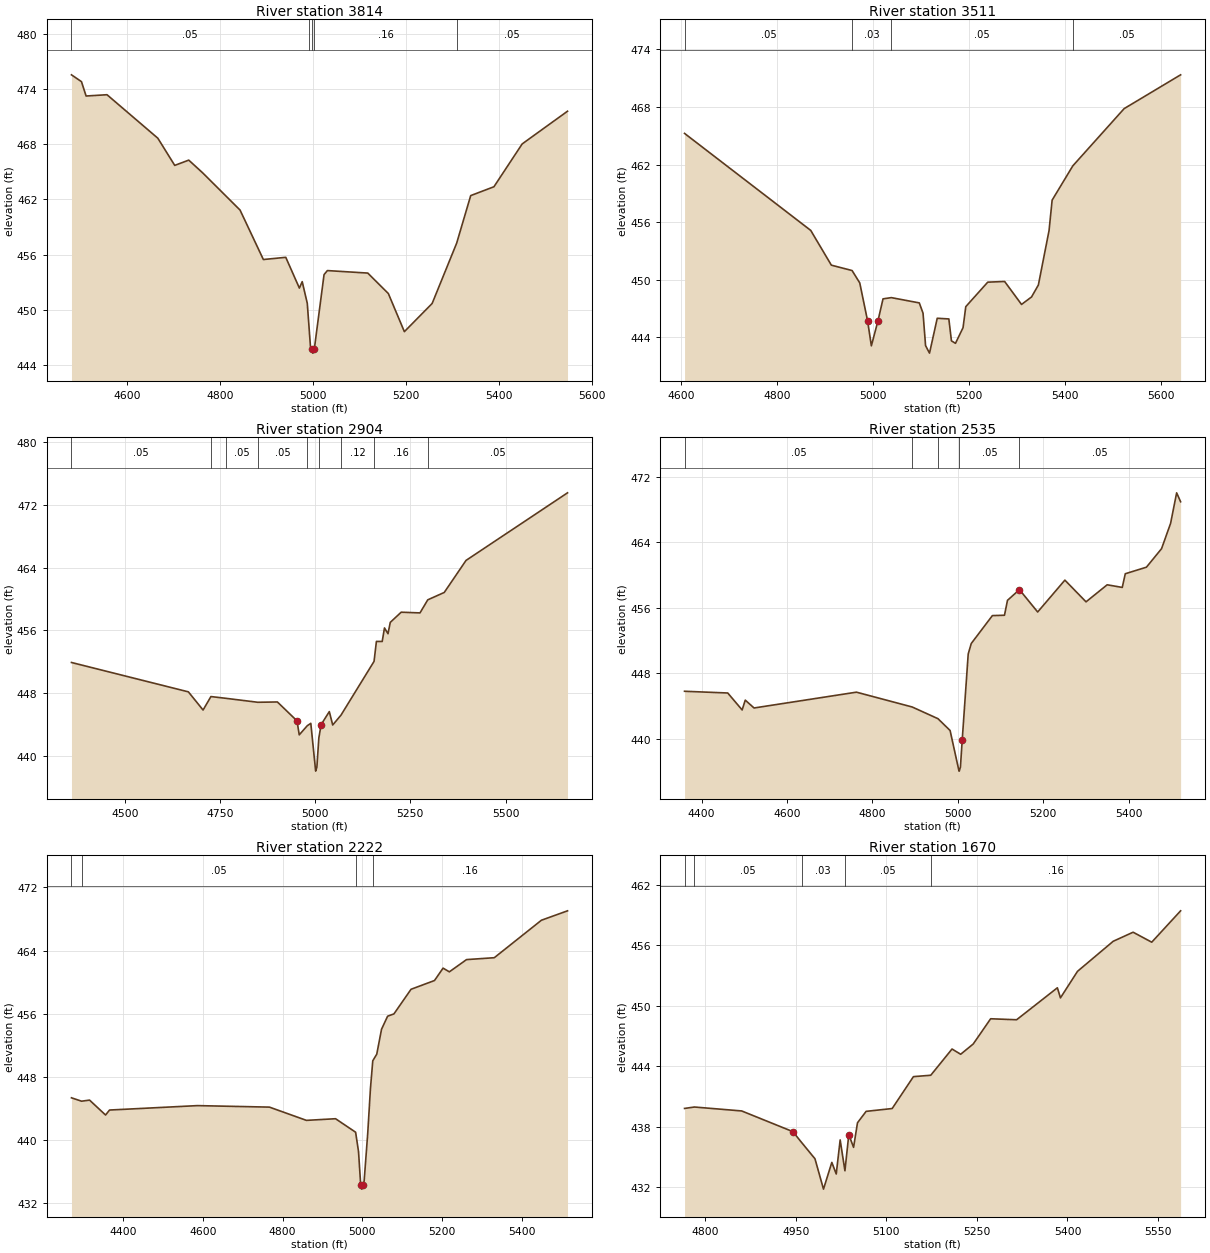
Type RM Length L Ch R = 1 ,3814    ,303,303,303
BEGIN DESCRIPTION:
UNT018 IN STEL 4.0
END DESCRIPTION:
XS GIS Cut Line= 4
      3457180.73      10476959.6      3457630.43     10477001.27
      3457793.62     10476933.56      3458184.26     10476732.17
#Sta/Elev= 30
  4479.9  475.53  4501.4  474.79  4511.4  473.23  4556.4  473.37  4665.8  468.65
  4702.2   465.7  4732.4  466.27  4762.5  464.88  4842.8  460.85    4893  455.48
  4941.2  455.72  4970.5  452.38  4976.6  453.08  4987.5  450.73  4991.4  448.06
  4994.3  446.07  4996.8  445.82  4999.5  445.32  5002.8  445.82  5023.6  453.84
  5030.8  454.28  5117.7  454.01    5162  451.79  5196.5  447.65  5256.3  450.71
  5309.1  457.26  5339.3  462.42  5389.3  463.38  5450.1  468.03  5547.7  471.58
#Mann= 5 ,-1 , 0
  4479.9     .05       0  4991.4     .16       0  4996.8     .07       0
  5002.8     .16       0  5309.1     .05       0
Bank Sta=4996.8,5002.8
XS Rating Curve= 0 ,0
Exp/Cntr=0.3,0.1

Type RM Length L Ch R = 1 ,3511    ,607,607,607
BEGIN DESCRIPTION:
Mapping XS 798a2ab8
END DESCRIPTION:
XS GIS Cut Line= 3
      3457407.99     10477402.52      3457960.07     10477181.17
       3458237.9     10476841.01
#Sta/Elev= 30
  4607.7  465.25  4870.7  455.15  4913.7  451.53  4956.9  450.97  4972.9  449.68
  4989.2  445.74  4997.1  443.13  5010.8  445.72  5021.4  448.02  5038.7  448.15
    5097   447.6  5104.8  446.53  5110.1  443.15  5118.3  442.37  5134.4     446
  5158.6  445.93    5164  443.65  5172.4  443.39  5188.2  445.02  5193.9  447.21
  5239.7  449.76  5274.9  449.83  5310.1  447.44    5331  448.22  5345.2  449.46
  5367.5  455.14  5373.9   458.3    5417  461.87    5524  467.83  5641.7  471.35
#Mann= 4 ,-1 , 0
  4607.7     .05       0  4956.9     .03       0  5038.7     .05       0
    5417     .05       0
Bank Sta=4989.2,5010.8
XS Rating Curve= 0 ,0
Exp/Cntr=0.3,0.1

Type RM Length L Ch R = 1 ,2904    ,369,369,369
BEGIN DESCRIPTION:
UNT018 IN STEL 3.0
END DESCRIPTION:
XS GIS Cut Line= 4
      3457568.41      10477668.8      3458000.85      10477603.4
      3458220.79     10477261.82      3458571.98     10476965.69
#Sta/Elev= 30
  4359.9  451.91    4667  448.16  4705.6  445.84  4726.2  447.56  4764.9  447.34
  4849.4  446.83  4900.8  446.87  4952.3  444.46  4958.2  442.67  4979.4  443.84
  4988.6  444.14  5001.3  438.04  5004.5  438.54  5009.7  442.28  5015.7  443.98
  5037.2  445.64  5046.1  443.93  5067.9  445.19  5154.7  452.05  5160.9   454.6
  5176.1  454.59  5182.1  456.32  5191.3  455.58  5197.3  457.03    5226  458.33
  5275.4  458.24  5295.8  459.91  5339.1  460.85  5396.3  464.94  5662.9  473.57
#Mann= 9 ,-1 , 0
  4359.9     .05       0  4726.2     .12       0  4764.9     .05       0
  4849.4     .05       0  4979.4     .03       0  5009.7     .05       0
  5067.9     .12       0  5154.7     .16       0  5295.8     .05       0
Bank Sta=4952.3,5015.7
XS Rating Curve= 0 ,0
Exp/Cntr=0.3,0.1

Type RM Length L Ch R = 1 ,2535    ,313,313,313
BEGIN DESCRIPTION:
Mapping XS 0916fef6
END DESCRIPTION:
XS GIS Cut Line= 3
      3457763.68     10477846.76      3458108.68     10477766.26
      3458679.27     10477195.67
#Sta/Elev= 30
  4360.2  445.82  4461.3  445.61    4495  443.54  4502.3  444.74  4522.9  443.78
  4762.6  445.71  4893.1   443.9  4953.5  442.47  4981.8  441.03  5002.7  436.07
  5003.2  436.07    5006  436.57  5010.1  439.82  5024.2  450.37  5031.3  451.65
  5080.8  455.06  5109.1   455.1  5116.1  456.92  5144.1  458.23  5186.8   455.5
  5250.5  459.39    5300  456.74  5349.5  458.82  5384.8   458.5  5391.9  460.17
  5441.4  460.97  5476.8  463.23    5498  466.33  5512.1  470.05  5521.4  468.96
#Mann= 5 ,-1 , 0
  4360.2     .05       0  4893.1     .05       0  4953.5     .03       0
  5003.2     .05       0  5144.1     .05       0
Bank Sta=5010.1,5144.1
XS Rating Curve= 0 ,0
Exp/Cntr=0.3,0.1

Type RM Length L Ch R = 1 ,2222    ,552,552,552
BEGIN DESCRIPTION:
Mapping XS 41c6add4
END DESCRIPTION:
XS GIS Cut Line= 4
      3457796.82     10477876.29      3458339.89     10477830.18
      3458784.34     10477573.24      3458791.27     10477386.16
#Sta/Elev= 30
  4269.7  445.35  4295.1  444.92  4315.1  445.06  4355.3  443.17  4365.3   443.8
  4586.1  444.36  4766.8  444.17  4859.7  442.49  4932.8   442.7  4983.2  440.99
  4990.5  438.54    4996  434.28  4998.7  433.78    5002  434.28  5004.7  434.87
  5013.6  440.83  5020.5  446.57  5026.3  450.04  5036.3  450.88  5048.3  454.04
  5063.6  455.69  5079.4  455.98  5122.4   459.1  5181.3  460.21  5202.8  461.78
  5218.6  461.31  5261.7  462.86  5331.4   463.1  5449.8  467.85  5515.3  469.04
#Mann= 4 ,-1 , 0
  4269.7     .05       0  4295.1     .05       0  4983.2     .03       0
  5026.3     .16       0
Bank Sta=4996,5002
XS Rating Curve= 0 ,0
Exp/Cntr=0.3,0.1

Type RM Length L Ch R = 1 ,1670    ,734,734,734
BEGIN DESCRIPTION:
Mapping XS f98bd02d
END DESCRIPTION:
XS GIS Cut Line= 3
      3458533.44     10478126.22      3458963.16     10477774.63
      3459020.59     10477514.93
#Sta/Elev= 30
  4766.1  439.83  4782.5  439.97  4860.7  439.58  4945.4  437.53  4959.8  436.46
    4982  434.84  4996.1  431.83  5009.9  434.48  5017.2  433.33  5023.7  436.71
  5031.6  433.65    5038  437.24  5045.9  435.97  5052.4  438.41  5066.7  439.54
  5109.8  439.82    5145  442.98  5173.7  443.12  5208.9  445.72  5223.2   445.2
    5244  446.22  5272.8  448.72  5315.8  448.62  5383.3  451.79  5388.4  450.79
  5416.6  453.42  5475.7   456.4  5508.7   457.3  5539.5  456.31  5587.3  459.42
#Mann= 5 ,-1 , 0
  4766.1      .1       0  4782.5     .05       0  4959.8     .03       0
  5031.6     .05       0  5173.7     .16       0
Bank Sta=4945.4,5038
XS Rating Curve= 0 ,0
Exp/Cntr=0.3,0.1

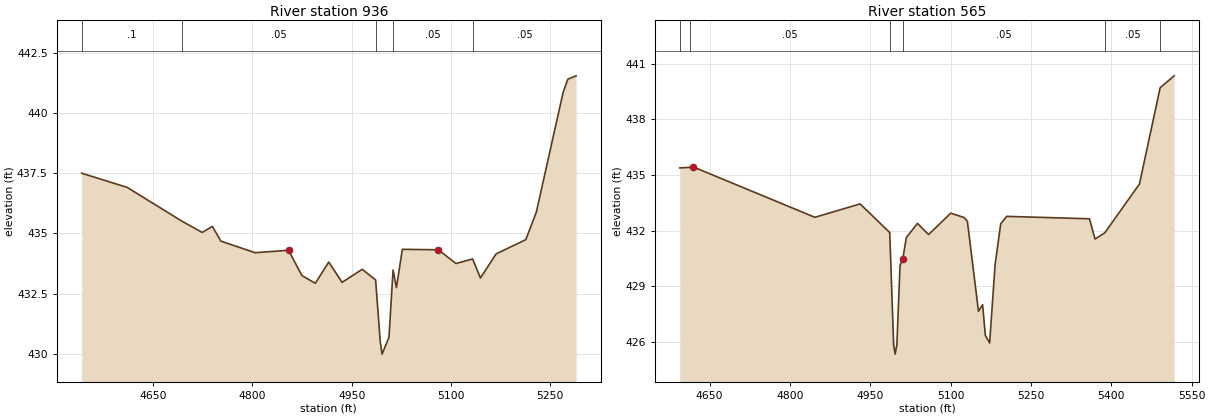
Type RM Length L Ch R = 1 ,936     ,371,371,371
BEGIN DESCRIPTION:
UNT018 IN STEL 2.0
END DESCRIPTION:
XS GIS Cut Line= 3
      3458694.06     10478217.33      3458911.08      10478321.5
      3459411.55     10478245.07
#Sta/Elev= 30
  4541.9   437.5  4610.7  436.91  4693.3  435.51    4724  435.04  4739.4  435.29
  4752.2  434.68  4803.9   434.2  4854.5   434.3  4874.7  433.25  4894.9  432.93
  4915.2  433.81  4935.4  432.97  4965.8  433.51    4986  433.07  4993.1  430.49
  4995.8  429.99  5006.2  430.69  5012.4  433.48  5017.5  432.75  5026.4  434.34
  5080.9  434.32  5107.4  433.75  5132.6  433.94  5144.4  433.15  5168.1  434.15
  5212.9  434.74  5228.8  435.88  5269.2  440.84  5276.4   441.4  5288.9  441.54
#Mann= 5 ,-1 , 0
  4541.9      .1       0  4693.3     .05       0    4986     .03       0
  5012.4     .05       0  5132.6     .05       0
Bank Sta=4854.5,5080.9
XS Rating Curve= 0 ,0
Exp/Cntr=0.3,0.1

Type RM Length L Ch R = 1 ,565     ,0,0,0
BEGIN DESCRIPTION:
UNT018 IN STEL 1.0
END DESCRIPTION:
XS GIS Cut Line= 3
      3458598.56     10478434.34      3458876.35     10478555.88
      3459474.76     10478393.71
#Sta/Elev= 30
  4594.2  435.38  4613.4  435.41  4619.7  435.43  4846.5  432.72    4931  433.44
  4986.3   431.9  4993.6  425.85  4996.4  425.35  4999.6  425.85  5005.5  430.12
  5010.7  430.49  5017.3  431.63  5038.1  432.39  5058.8  431.79  5100.2  432.94
    5125  432.71  5131.3   432.5    5152  427.66  5159.7  428.01  5164.8  426.36
  5172.8  425.95  5183.1  430.19  5193.5  432.37  5204.7  432.77  5359.2  432.64
  5369.6  431.55  5387.7  431.88  5452.5  434.51  5491.2   439.7  5517.4  440.34
#Mann= 6 ,-1 , 0
  4594.2      .1       0  4613.4     .05       0  4986.3     .03       0
  5010.7     .05       0  5387.7     .05       0  5491.2     .08       0
Bank Sta=4619.7,5010.7
XS Rating Curve= 0 ,0
Exp/Cntr=0.3,0.1

Chan Stop Cuts=-1
Use User Specified Reach Order=0
Composite Channel Slope=5