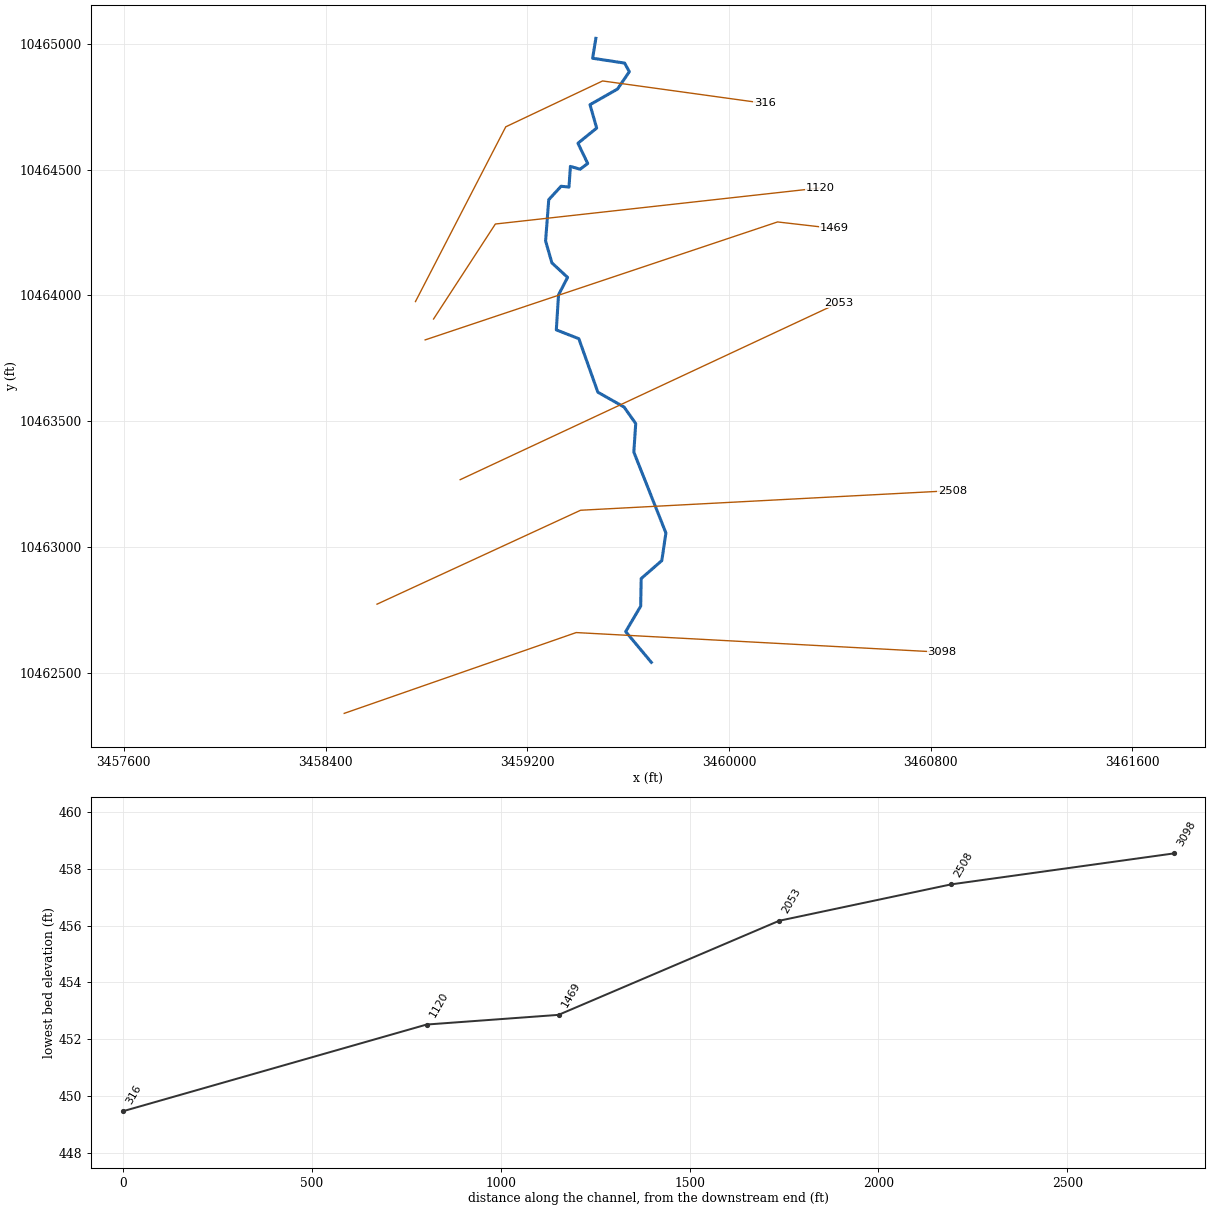
--- UNT019 IN STEL.prj (project) ---

Proj Title=UNT019 IN STEL Base Level Engineering
Current Plan=p01
Default Exp/Contr=0.3,0.1
English Units
Geom File=g01
Flow File=f01
Plan File=p01
Y Axis Title=Elevation
X Axis Title(PF)=Main Channel Distance
X Axis Title(XS)=Station
BEGIN DESCRIPTION:
UNT019 IN STEL
END DESCRIPTION:
DSS Export Rating Curves= 0
DSS Export Rating Curve Sorted= 0
DSS Export Volume Flow Curves= 0
DXF OffsetX= 0
DXF OffsetY= 0
DXF ScaleX= 1
DXF ScaleY= 10

--- UNT019 IN STEL.p01 (plan) ---

Plan Title=Multiple Run
Short Identifier=Multiple
Geom File=g01
Flow File=f01
Subcritical Flow
K Sum by GR= 0
Std Step Tol= 0.01
Critical Tol= 0.01
Num of Std Step Trials= 20
Max Error Tol= 0.3
Flow Tol Ratio= 0.001
Split Flow NTrial= 30
Split Flow Tol= 0.02
Split Flow Ratio= 0.02
Log Output Level= 0
Friction Slope Method= 1
Unsteady Friction Slope Method= 2
Unsteady Bridges Friction Slope Method= 1
Parabolic Critical Depth
Global Vel Dist=  1 , 1 , 1
Global Log Level= 0
CheckData=True
Encroach Param= -1, 0, 0, 0
BEGIN DESCRIPTION:
Multiple Run
END DESCRIPTION:

--- UNT019 IN STEL.f01 (steady flow) ---

Flow Title=Multiple
Number of Profiles=7
Profile Names=10-year,25-year,50-year,1pct_min,100-year,1pct_plu,500-year
River Rch & RM= UNT019 IN STEL,Reach-1,3098
    1138    1590    1968    1778    2405    3252    3581
Boundary for River Rch & Prof#=UNT019 IN STEL,Reach-1,1
Up Type=0
Dn Type=3
Dn Slope=0.005
Boundary for River Rch & Prof#=UNT019 IN STEL,Reach-1,2
Up Type=0
Dn Type=3
Dn Slope=0.005
Boundary for River Rch & Prof#=UNT019 IN STEL,Reach-1,3
Up Type=0
Dn Type=3
Dn Slope=0.005
Boundary for River Rch & Prof#=UNT019 IN STEL,Reach-1,4
Up Type=0
Dn Type=3
Dn Slope=0.005
Boundary for River Rch & Prof#=UNT019 IN STEL,Reach-1,5
Up Type=0
Dn Type=3
Dn Slope=0.005
Boundary for River Rch & Prof#=UNT019 IN STEL,Reach-1,6
Up Type=0
Dn Type=3
Dn Slope=0.005
Boundary for River Rch & Prof#=UNT019 IN STEL,Reach-1,7
Up Type=0
Dn Type=3
Dn Slope=0.005

--- UNT019 IN STEL.g01 (geometry) ---

Geom Title=Existing Conditions
Program Version=4.10

River Reach=UNT019 IN STEL  ,Reach-1
Reach XY= 30
      3459692.11     10462541.64      3459590.45      10462663.7
      3459649.82     10462764.74      3459651.91     10462874.63
      3459733.68     10462945.99      3459749.88     10463055.94
      3459622.68     10463377.13      3459630.19     10463490.66
      3459583.84     10463556.35      3459479.99     10463615.22
      3459404.54      10463827.9      3459315.28     10463862.89
      3459323.99     10464002.08      3459359.91     10464071.46
       3459297.7     10464129.34      3459272.69      10464216.4
      3459285.21     10464380.36      3459334.01     10464433.65
      3459365.51     10464430.64      3459371.15     10464512.67
      3459409.78     10464501.39      3459439.73     10464524.39
       3459401.1     10464604.69      3459475.32     10464665.02
      3459448.84      10464757.9      3459557.79     10464819.99
      3459604.84     10464889.05      3459586.17     10464923.25
      3459459.05     10464942.48      3459472.11     10465021.64

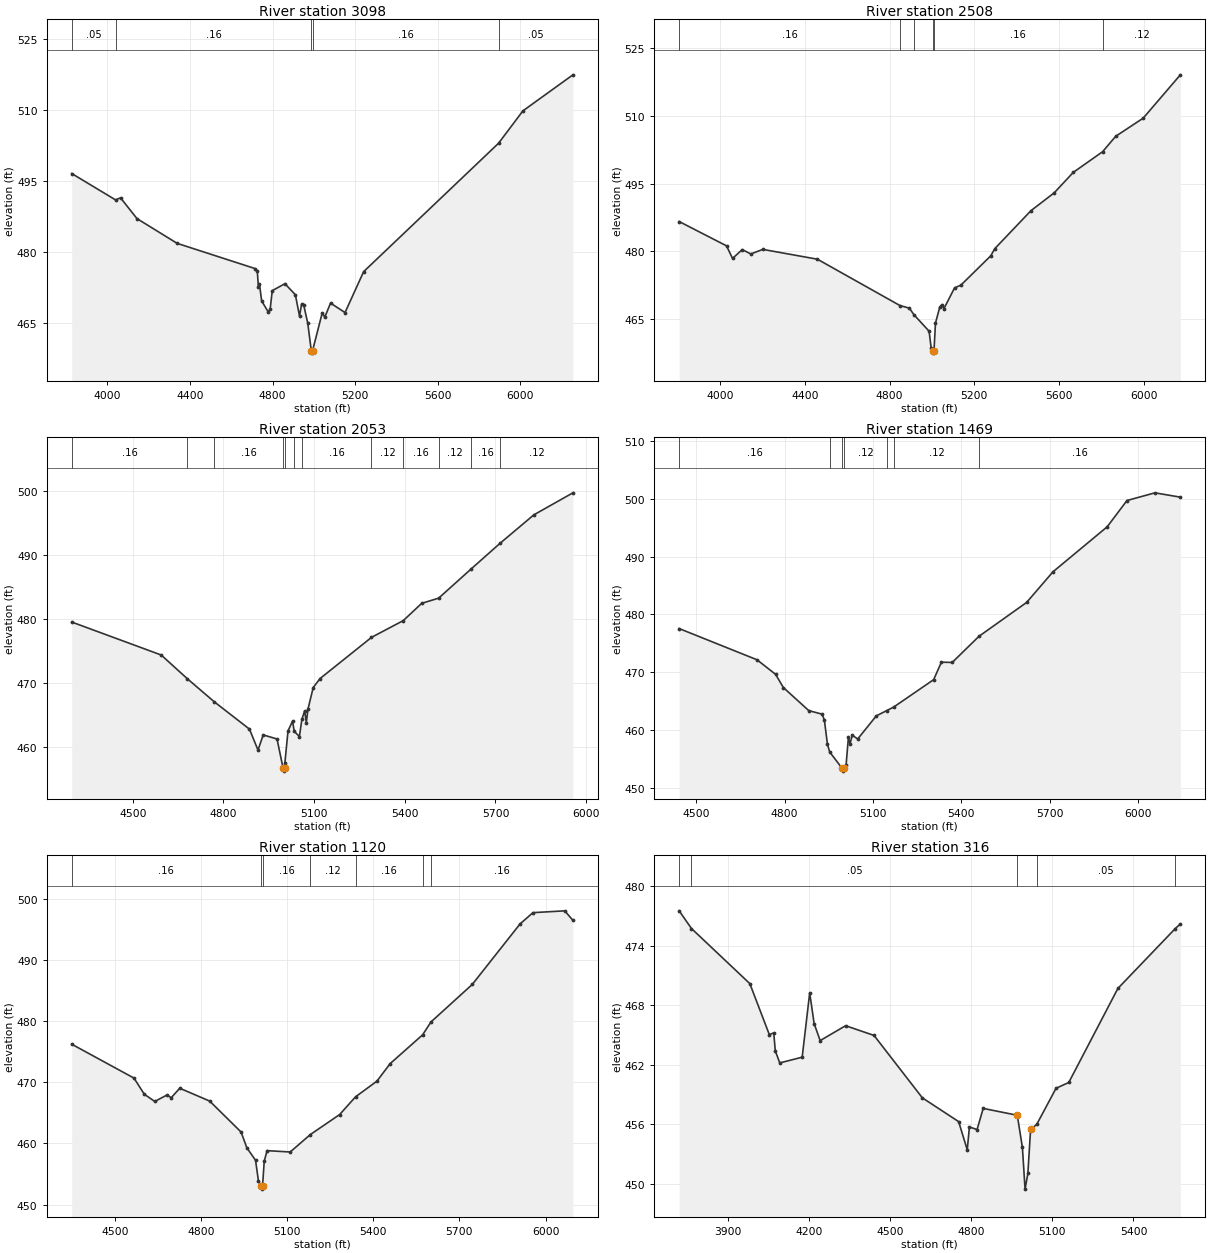
Type RM Length L Ch R = 1 ,3098    ,590,590,590
BEGIN DESCRIPTION:
UNT019 IN STEL 5.0
END DESCRIPTION:
XS GIS Cut Line= 3
      3458473.97     10462338.81      3459394.07     10462659.98
      3460843.73     10462581.85
#Sta/Elev= 30
  3827.7  496.52    4040  490.94    4064  491.38  4143.5  486.99  4338.2  481.75
  4715.4  476.42    4726  475.91  4731.4  472.61  4736.7  473.08  4747.2  469.58
    4779  467.24  4788.2  467.78  4798.5  471.75  4859.8  473.22  4910.4  470.88
  4930.5  466.37  4940.5   468.9  4950.5  468.78  4970.5  464.84  4987.5  459.04
  4990.3  458.54  4993.5  459.04  5040.6  467.08  5052.8  466.14  5080.7  469.12
  5150.8  467.12  5240.9  475.77    5894  502.92    6012  509.77    6254  517.39
#Mann= 5 ,-1 , 0
  3827.7     .05       0    4040     .16       0  4987.5     .07       0
  4993.5     .16       0    5894     .05       0
Bank Sta=4987.5,4993.5
XS Rating Curve= 0 ,0
Exp/Cntr=0.3,0.1

Type RM Length L Ch R = 1 ,2508    ,455,455,455
BEGIN DESCRIPTION:
UNT019 IN STEL 4.0
END DESCRIPTION:
XS GIS Cut Line= 3
      3458604.11     10462772.81      3459411.43     10463146.09
      3460887.12     10463224.21
#Sta/Elev= 30
  3806.2  486.59  4029.8  481.21  4058.3  478.42  4104.1  480.38  4144.5  479.41
  4201.3  480.42  4459.1  478.25  4848.8  467.99  4893.4  467.41  4915.5  465.93
  4986.7   462.3  4996.7  458.48  5003.8  457.95  5006.5  457.45  5009.8  457.95
  5016.8   464.1  5036.8  467.59  5046.8  468.18  5056.8   467.3  5106.9   471.9
  5136.9  472.51  5277.9     479  5297.2   480.6  5467.6  488.99  5577.6  492.95
  5667.7  497.48  5806.1  502.05    5868  505.47  5998.1  509.49  6173.4  519.08
#Mann= 6 ,-1 , 0
  3806.2     .16       0  4848.8     .12       0  4915.5     .16       0
  5003.8     .07       0  5009.8     .16       0  5806.1     .12       0
Bank Sta=5003.8,5009.8
XS Rating Curve= 0 ,0
Exp/Cntr=0.3,0.1

Type RM Length L Ch R = 1 ,2053    ,584,584,584
BEGIN DESCRIPTION:
UNT019 IN STEL 3.0
END DESCRIPTION:
XS GIS Cut Line= 2
      3458934.01     10463267.62      3460435.75     10463970.75
#Sta/Elev= 30
    4298  479.51    4594  474.35  4680.4  470.64  4769.4  467.03    4886  462.75
  4914.3  459.47  4931.6  461.84  4977.3   461.2  4997.1  456.67  4999.9  456.17
  5003.1  456.67  5003.2  457.41  5013.6  462.47  5028.5  463.99  5034.2  462.41
  5051.3  461.58  5059.4  464.26  5068.6  465.61  5074.1  463.77  5079.9  465.93
    5097  469.26  5119.8  470.67  5289.8  477.11    5395  479.74    5456  482.44
    5512  483.25  5619.2  487.81  5715.2  491.84  5826.9  496.29  5956.2  499.74
#Mann= 12 ,-1 , 0
    4298     .16       0  4680.4     .12       0  4769.4     .16       0
  4997.1     .07       0  5003.1     .16       0  5034.2     .12       0
  5059.4     .16       0  5289.8     .12       0    5395     .16       0
    5512     .12       0  5619.2     .16       0  5715.2     .12       0
Bank Sta=4997.1,5003.1
XS Rating Curve= 0 ,0
Exp/Cntr=0.3,0.1

Type RM Length L Ch R = 1 ,1469    ,349,349,349
BEGIN DESCRIPTION:
UNT019 IN STEL 2.0
END DESCRIPTION:
XS GIS Cut Line= 3
      3458795.12     10463823.17      3460192.68     10464291.92
      3460417.71     10464265.96
#Sta/Elev= 30
  4442.4  477.53  4706.5  472.13  4769.6  469.61  4795.9  467.33  4882.2  463.33
  4927.3  462.72    4935  461.73  4945.5  457.52  4953.2  456.17  4995.2  453.36
    4998  452.86  5001.2  453.36  5008.8  453.93  5016.7  458.74    5022  457.59
  5029.9  459.06  5048.3  458.43  5111.3  462.42  5147.3  463.35  5170.4  463.95
  5305.9  468.69  5332.2  471.71    5369  471.67  5459.9   476.2  5621.3  482.05
  5710.7  487.35  5894.7  495.14  5961.9  499.69  6056.8  501.02    6143  500.27
#Mann= 7 ,-1 , 0
  4442.4     .16       0  4953.2     .12       0  4995.2     .07       0
  5001.2     .12       0  5147.3     .16       0  5170.4     .12       0
  5459.9     .16       0
Bank Sta=4995.2,5001.2
XS Rating Curve= 0 ,0
Exp/Cntr=0.3,0.1

Type RM Length L Ch R = 1 ,1120    ,804,804,804
BEGIN DESCRIPTION:
UNT019 IN STEL 1.1
END DESCRIPTION:
XS GIS Cut Line= 3
      3458828.29     10463906.12      3459073.49     10464283.69
      3460360.34     10464426.92
#Sta/Elev= 30
  4350.3  476.21    4567  470.67  4603.2  468.02  4639.5  466.85  4681.7   467.9
  4696.8  467.47  4726.5  469.01  4830.7  466.91    4940  461.85  4960.1  459.27
  4990.3  457.24  5000.3   453.9  5008.7  453.02  5011.5  452.52  5014.7  453.02
  5020.5  457.08  5030.5  458.81    5111  458.59  5181.1  461.44  5283.1  464.71
  5338.5  467.61  5412.9  470.17  5459.1  473.04    5572  477.74  5601.2  479.85
  5744.9  485.98  5911.5  495.88  5956.2  497.71  6066.9  498.01  6095.3  496.45
#Mann= 7 ,-1 , 0
  4350.3     .16       0  5008.7     .07       0  5014.7     .16       0
  5181.1     .12       0  5338.5     .16       0    5572     .12       0
  5601.2     .16       0
Bank Sta=5008.7,5014.7
XS Rating Curve= 0 ,0
Exp/Cntr=0.3,0.1

Type RM Length L Ch R = 1 ,316     ,0,0,0
BEGIN DESCRIPTION:
UNT019 IN STEL 1.0
END DESCRIPTION:
XS GIS Cut Line= 4
      3458756.64     10463975.51      3459114.73     10464669.98
      3459498.84     10464852.27      3460141.18      10464763.3
#Sta/Elev= 30
  3718.6   477.5  3764.1  475.72  3980.1  470.17  4052.2  465.04  4068.7   465.2
  4074.3   463.4  4090.9  462.18  4173.9  462.76  4201.7  469.24  4218.2  466.14
  4240.4  464.43  4334.6  465.93  4439.8  464.95  4618.8  458.66    4753  456.27
  4784.8  453.43  4792.9  455.73  4821.2  455.47  4843.9   457.6    4970  456.91
    4989  453.67  4998.8  449.47  5009.2  451.05  5019.3  455.48  5041.8  455.98
  5113.6  459.63  5160.6  460.21  5342.3  469.68  5554.3   475.7  5573.6  476.18
#Mann= 5 ,-1 , 0
  3718.6     .16       0  3764.1     .05       0    4970     .03       0
  5041.8     .05       0  5554.3     .16       0
Bank Sta=4970,5019.3
XS Rating Curve= 0 ,0
Exp/Cntr=0.3,0.1

Chan Stop Cuts=-1
Use User Specified Reach Order=0
Composite Channel Slope=5