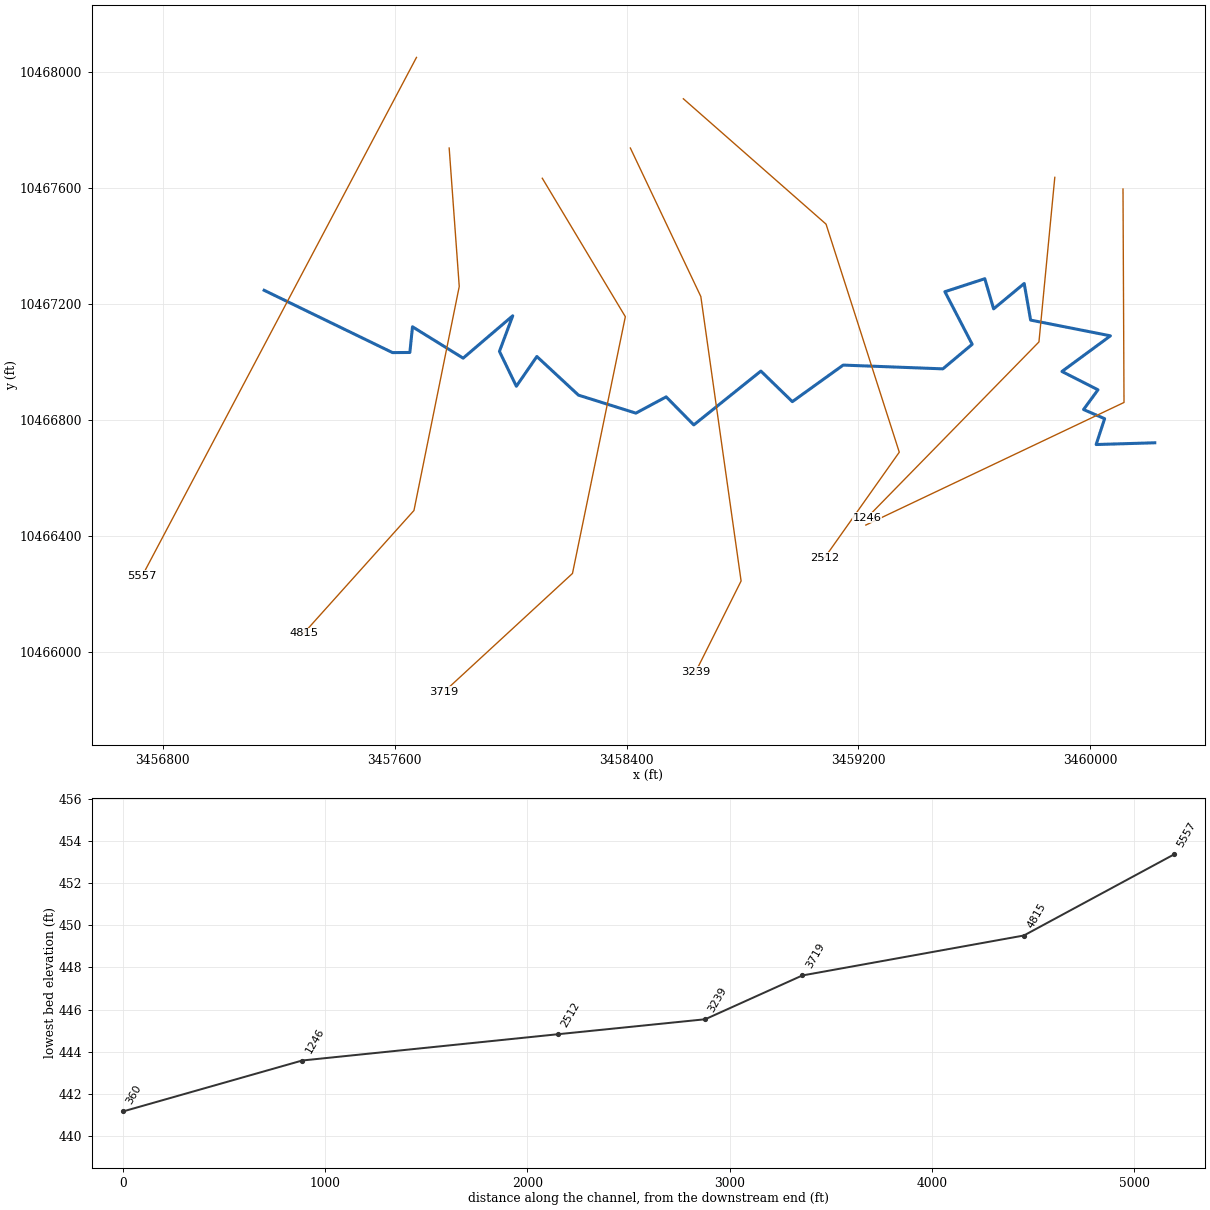
--- UNT021 IN STEL.prj (project) ---

Proj Title=UNT021 IN STEL Base Level Engineering
Current Plan=p01
Default Exp/Contr=0.3,0.1
English Units
Geom File=g01
Flow File=f01
Plan File=p01
BEGIN DESCRIPTION:
UNT021 IN STEL
END DESCRIPTION:

--- UNT021 IN STEL.p01 (plan) ---

Plan Title=Multiple Run
Short Identifier=Multiple
Geom File=g01
Flow File=f01
Subcritical Flow
K Sum by GR= 0
Std Step Tol= 0.01
Critical Tol= 0.01
Num of Std Step Trials= 20
Max Error Tol= 0.3
Flow Tol Ratio= 0.001
Split Flow NTrial= 30
Split Flow Tol= 0.02
Split Flow Ratio= 0.02
Log Output Level= 0
Friction Slope Method= 1
Unsteady Friction Slope Method= 2
Unsteady Bridges Friction Slope Method= 1
Parabolic Critical Depth
Global Vel Dist=  1 , 1 , 1
Global Log Level= 0
CheckData=True
Encroach Param= -1, 0, 0, 0
BEGIN DESCRIPTION:
Multiple Run
END DESCRIPTION:

--- UNT021 IN STEL.f01 (steady flow) ---

Flow Title=Multiple
Number of Profiles=7
Profile Names=10-year,25-year,50-year,1pct_min,100-year,1pct_plu,500-year
River Rch & RM= UNT021 IN STEL,Reach-1,5557
    1295    1804    2229    2006    2712    3668    4010
Boundary for River Rch & Prof#=UNT021 IN STEL,Reach-1,1
Up Type=0
Dn Type=3
Dn Slope=0.005
Boundary for River Rch & Prof#=UNT021 IN STEL,Reach-1,2
Up Type=0
Dn Type=3
Dn Slope=0.005
Boundary for River Rch & Prof#=UNT021 IN STEL,Reach-1,3
Up Type=0
Dn Type=3
Dn Slope=0.005
Boundary for River Rch & Prof#=UNT021 IN STEL,Reach-1,4
Up Type=0
Dn Type=3
Dn Slope=0.005
Boundary for River Rch & Prof#=UNT021 IN STEL,Reach-1,5
Up Type=0
Dn Type=3
Dn Slope=0.005
Boundary for River Rch & Prof#=UNT021 IN STEL,Reach-1,6
Up Type=0
Dn Type=3
Dn Slope=0.005
Boundary for River Rch & Prof#=UNT021 IN STEL,Reach-1,7
Up Type=0
Dn Type=3
Dn Slope=0.005

--- UNT021 IN STEL.g01 (geometry) ---

Geom Title=Existing Conditions

River Reach=UNT021 IN STEL,Reach-1
Reach XY= 30
      3457149.90     10467247.53      3457592.61     10467032.69
      3457652.50     10467033.12      3457661.62     10467121.66
      3457836.33     10467013.52      3458007.42     10467159.64
      3457961.54     10467036.87      3458019.87     10466916.58
      3458090.63     10467019.24      3458234.22     10466885.95
      3458432.16     10466823.96      3458536.64     10466880.00
      3458631.89     10466783.29      3458863.30     10466968.96
      3458971.88     10466863.54      3459147.25     10466989.60
      3459491.16     10466976.63      3459592.27     10467061.32
      3459498.13     10467242.67      3459635.74     10467287.45
      3459666.20     10467183.53      3459771.65     10467271.03
      3459793.83     10467144.76      3460069.15     10467090.51
      3459901.86     10466967.57      3460026.17     10466904.39
      3459976.44     10466836.31      3460049.13     10466804.79
      3460019.81     10466715.65      3460222.11     10466721.64

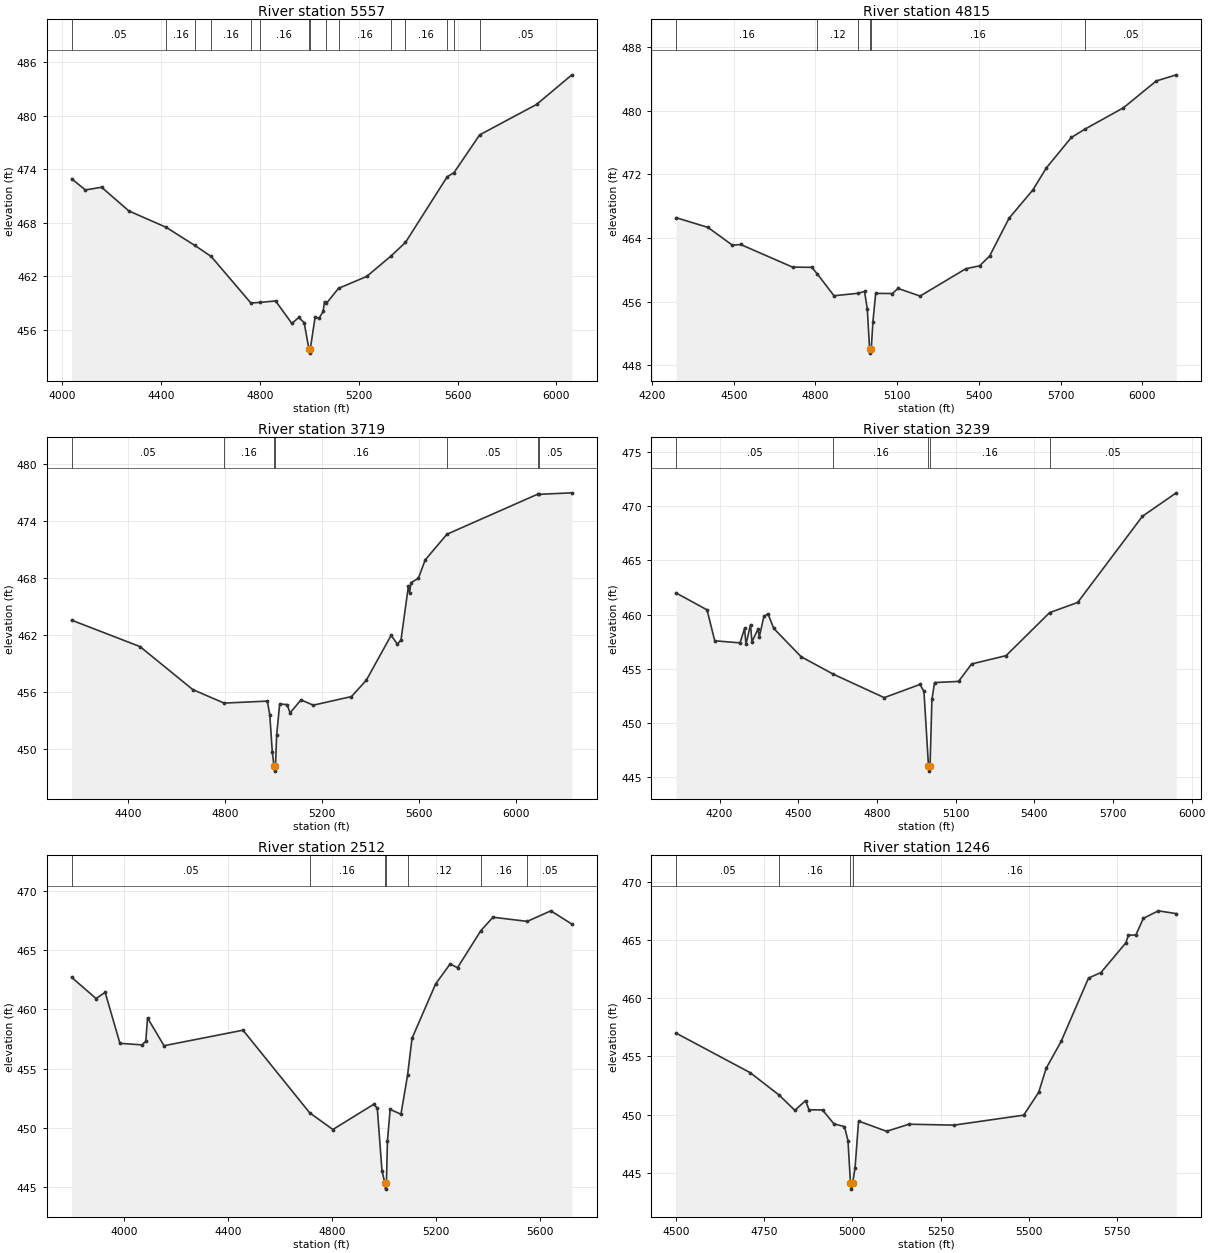
Type RM Length L Ch R = 1,5557,742,742,742
BEGIN DESCRIPTION:
UNT021 IN STEL 5.0
END DESCRIPTION:
XS GIS Cut Line= 2
      3457675.34     10468050.64      3456729.16     10466262.44
#Sta/Elev= 30
  4039.4  472.91  4094.5  471.66  4160.5  471.96  4270.5  469.31  4422.3  467.46
  4537.3  465.44  4603.4  464.21  4764.1  458.99  4799.9  459.05  4864.0  459.22
  4930.0  456.70  4957.7  457.37  4979.7  456.79  4998.7  453.87  5001.4  453.37
  5004.7  453.87  5023.7  457.37  5040.0  457.29  5056.4  458.04  5062.0  459.14
  5069.7  458.95  5118.6  460.63  5232.4  461.96  5331.2  464.26  5389.5  465.78
  5558.0  473.13  5586.0  473.61  5689.4  477.83  5919.6  481.24  6062.5  484.56
#Mann=15,-1,0
  4039.4    0.05       0  4422.3    0.16       0  4537.3    0.05       0
  4603.4    0.16       0  4764.1    0.05       0  4799.9    0.16       0
  4998.7    0.07       0  5004.7    0.16       0  5069.7    0.05       0
  5118.6    0.16       0  5331.2    0.05       0  5389.5    0.16       0
  5558.0    0.05       0  5586.0    0.16       0  5689.4    0.05       0
Bank Sta=4998.7,5004.7
Exp/Cntr=0.3,0.1

Type RM Length L Ch R = 1,4815,1096,1096,1096
BEGIN DESCRIPTION:
UNT021 IN STEL 4.0
END DESCRIPTION:
XS GIS Cut Line= 4
      3457788.16     10467738.13      3457822.89     10467260.67
      3457666.64     10466488.10      3457285.90     10466064.09
#Sta/Elev= 30
  4288.2  466.54  4405.0  465.32  4495.2  463.08  4525.3  463.17  4715.8  460.33
  4786.3  460.30  4806.8  459.47  4868.0  456.73  4955.9  457.04  4980.2  457.27
  4990.4  455.06  4998.8  450.02  5001.5  449.52  5004.8  450.02  5010.8  453.39
  5021.0  457.03  5082.2  457.01  5103.2  457.65  5184.2  456.69  5351.8  460.12
  5402.5  460.49  5439.3  461.71  5510.7  466.46  5598.4  470.03  5647.7  472.79
  5739.6  476.62  5790.7  477.69  5931.0  480.35  6051.4  483.72  6125.0  484.49
#Mann=6,-1,0
  4288.2    0.16       0  4806.8    0.12       0  4955.9    0.16       0
  4998.8    0.07       0  5004.8    0.16       0  5790.7    0.05       0
Bank Sta=4998.8,5004.8
Exp/Cntr=0.3,0.1

Type RM Length L Ch R = 1,3719,480,480,480
BEGIN DESCRIPTION:
UNT021 IN STEL 3.0
END DESCRIPTION:
XS GIS Cut Line= 4
      3458109.35     10467633.94      3458395.81     10467156.50
      3458213.51     10466271.09      3457770.80     10465863.10
#Sta/Elev= 30
  4167.4  463.55  4449.4  460.76  4667.1  456.22  4796.1  454.80  4974.2  455.01
  4984.4  453.56  4994.6  449.69  5001.8  448.12  5004.6  447.62  5007.8  448.12
  5012.6  451.42  5025.2  454.71  5055.9  454.64  5068.0  453.77  5113.2  455.14
  5163.6  454.58  5321.3  455.49  5382.6  457.22  5484.7  461.95  5510.7  461.02
  5525.5  461.47  5555.9  467.13  5561.0  466.44  5566.3  467.51  5597.0  467.96
  5625.3  469.91  5714.9  472.62  6089.4  476.85  6093.0  476.83  6230.2  476.99
#Mann=7,-1,0
  4167.4    0.05       0  4796.1    0.16       0  5001.8    0.07       0
  5007.8    0.16       0  5714.9    0.05       0  6089.4     0.1       0
  6093.0    0.05       0
Bank Sta=5001.8,5007.8
Exp/Cntr=0.3,0.1

Type RM Length L Ch R = 1,3239,727,727,727
BEGIN DESCRIPTION:
UNT021 IN STEL 2.0
END DESCRIPTION:
XS GIS Cut Line= 4
      3458413.15     10467738.13      3458656.22     10467225.95
      3458795.11     10466245.05      3458638.86     10465932.55
#Sta/Elev= 30
  4034.5  462.00  4152.4  460.44  4181.9  457.58  4278.3  457.39  4295.5  458.72
  4301.0  457.28  4318.2  459.07  4323.8  457.49  4346.5  458.65  4352.0  457.97
  4369.2  459.83  4384.8  460.07  4407.0  458.72  4511.2  456.11  4634.3  454.49
  4828.0  452.33  4964.4  453.55  4979.5  452.90  4996.7  446.04  4999.4  445.54
  5002.7  446.04  5009.8  452.16  5019.9  453.72  5111.4  453.83  5161.3  455.44
  5292.6  456.21  5458.3  460.18  5565.3  461.12  5812.6  469.09  5941.5  471.25
#Mann=5,-1,0
  4034.5    0.05       0  4634.3    0.16       0  4996.7    0.07       0
  5002.7    0.16       0  5458.3    0.05       0
Bank Sta=4996.7,5002.7
Exp/Cntr=0.3,0.1

Type RM Length L Ch R = 1,2512,1266,1266,1266
BEGIN DESCRIPTION:
Mapping XS 17943001
END DESCRIPTION:
XS GIS Cut Line= 4
      3458595.97     10467907.99      3459088.16     10467475.69
      3459340.76     10466689.24      3459083.67     10466325.66
#Sta/Elev= 30
  3796.9  462.70  3890.7  460.91  3925.8  461.43  3982.8  457.13  4068.2  457.00
  4082.4  457.32  4089.0  459.27  4152.6  456.93  4456.7  458.24  4713.5  451.27
  4802.8  449.86  4960.4  451.99  4973.9  451.66  4991.9  446.39  5003.0  445.33
  5005.8  444.83  5009.0  445.33  5012.9  448.86  5023.4  451.56  5065.0  451.15
  5090.5  454.44  5107.6  457.55  5198.7  462.15  5254.5  463.83  5282.8  463.51
  5372.7  466.64  5419.4  467.77  5551.5  467.42  5642.2  468.31  5723.3  467.19
#Mann=7,-1,0
  3796.9    0.05       0  4713.5    0.16       0  5003.0    0.07       0
  5009.0    0.16       0  5090.5    0.12       0  5372.7    0.16       0
  5551.5    0.05       0
Bank Sta=5003,5009
Exp/Cntr=0.3,0.1

Type RM Length L Ch R = 1,1246,886,886,886
BEGIN DESCRIPTION:
Mapping XS 674efab5
END DESCRIPTION:
XS GIS Cut Line= 3
      3459877.22     10467637.11      3459822.54     10467069.44
      3459228.81     10466462.70
#Sta/Elev= 30
  4499.7  457.01  4710.3  453.60  4792.7  451.66  4836.7  450.36  4866.9  451.20
  4876.9  450.41  4915.1  450.40  4947.2  449.21  4977.4  448.96  4987.4  447.76
  4994.5  444.08  4997.2  443.58  5000.5  444.08  5007.5  445.43  5017.4  449.44
  5097.0  448.56  5160.7  449.17  5288.0  449.09  5486.0  449.95  5528.5  451.92
  5549.6  453.98  5592.0  456.29  5669.8  461.75  5705.2  462.23  5775.9  464.79
  5782.9  465.44  5804.2  465.46  5825.3  466.89  5867.8  467.54  5918.9  467.30
#Mann=4,-1,0
  4499.7    0.05       0  4792.7    0.16       0  4994.5    0.07       0
  5000.5    0.16       0
Bank Sta=4994.5,5000.5
Exp/Cntr=0.3,0.1

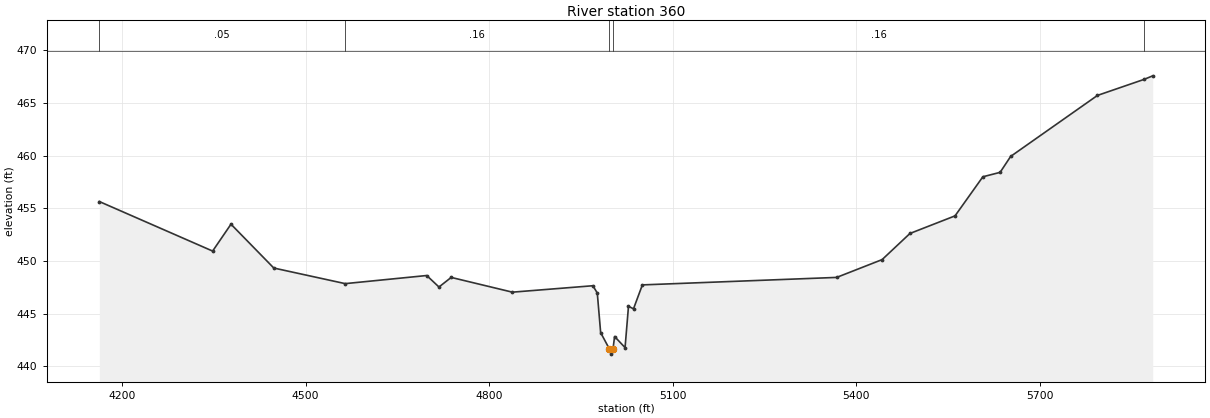
Type RM Length L Ch R = 1,360,0,0,0
BEGIN DESCRIPTION:
UNT021 IN STEL 1.0
END DESCRIPTION:
XS GIS Cut Line= 4
      3460112.48     10467596.86      3460115.95     10466860.73
      3459662.47     10466645.46      3459225.35     10466437.95
#Sta/Elev= 30
  4162.8  455.64  4348.0  450.94  4378.0  453.49  4448.0  449.33  4564.7  447.85
  4698.0  448.62  4718.0  447.53  4738.0  448.44  4838.0  447.04  4969.6  447.65
  4976.8  446.96  4982.3  443.20  4996.5  441.66  4999.3  441.16  5002.5  441.66
  5005.1  442.83  5022.2  441.78  5027.8  445.70  5036.0  445.46  5050.5  447.73
  5368.1  448.44  5442.4  450.13  5487.9  452.61  5561.6  454.28  5607.1  457.99
  5635.3  458.41  5652.5  459.92  5794.4  465.71  5871.0  467.24  5884.8  467.57
#Mann=5,-1,0
  4162.8    0.05       0  4564.7    0.16       0  4996.5    0.07       0
  5002.5    0.16       0  5871.0    0.05       0
Bank Sta=4996.5,5002.5
Exp/Cntr=0.3,0.1

Chan Stop Cuts=-1