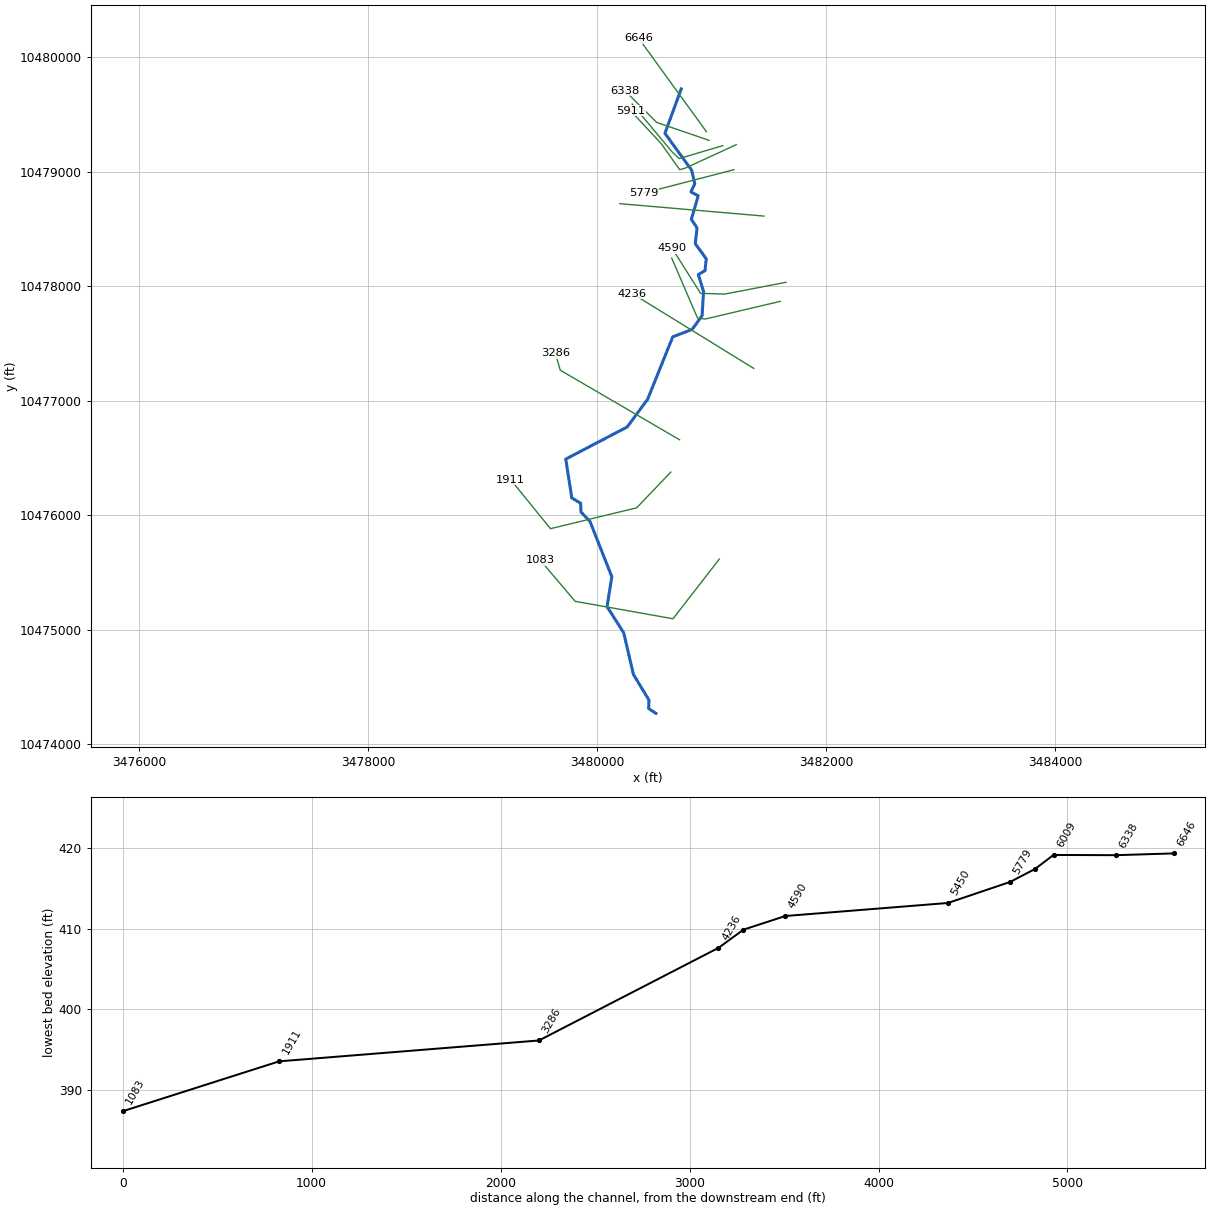
--- UNT023 IN STEL.prj (project) ---

Proj Title=UNT023 IN STEL Base Level Engineering
Current Plan=p01
Default Exp/Contr=0.3,0.1
English Units
Geom File=g01
Flow File=f01
Plan File=p01
BEGIN DESCRIPTION:
UNT023 IN STEL
END DESCRIPTION:

--- UNT023 IN STEL.p01 (plan) ---

Plan Title=Multiple Run
Short Identifier=Multiple
Geom File=g01
Flow File=f01
Subcritical Flow
K Sum by GR= 0
Std Step Tol= 0.01
Critical Tol= 0.01
Num of Std Step Trials= 20
Max Error Tol= 0.3
Flow Tol Ratio= 0.001
Split Flow NTrial= 30
Split Flow Tol= 0.02
Split Flow Ratio= 0.02
Log Output Level= 0
Friction Slope Method= 1
Unsteady Friction Slope Method= 2
Unsteady Bridges Friction Slope Method= 1
Parabolic Critical Depth
Global Vel Dist=  1 , 1 , 1
Global Log Level= 0
CheckData=True
Encroach Param= -1, 0, 0, 0
BEGIN DESCRIPTION:
Multiple Run
END DESCRIPTION:

--- UNT023 IN STEL.f01 (steady flow) ---

Flow Title=Multiple
Number of Profiles=7
Profile Names=10-year,25-year,50-year,1pct_min,100-year,1pct_plu,500-year
River Rch & RM= UNT023 IN STEL,Reach-1,6646
     527     696     829     722     977    1321    1350
River Rch & RM= UNT023 IN STEL,Reach-1,3286
     769    1040    1260    1113    1505    2036    2144
Boundary for River Rch & Prof#=UNT023 IN STEL,Reach-1,1
Up Type=0
Dn Type=3
Dn Slope=0.005
Boundary for River Rch & Prof#=UNT023 IN STEL,Reach-1,2
Up Type=0
Dn Type=3
Dn Slope=0.005
Boundary for River Rch & Prof#=UNT023 IN STEL,Reach-1,3
Up Type=0
Dn Type=3
Dn Slope=0.005
Boundary for River Rch & Prof#=UNT023 IN STEL,Reach-1,4
Up Type=0
Dn Type=3
Dn Slope=0.005
Boundary for River Rch & Prof#=UNT023 IN STEL,Reach-1,5
Up Type=0
Dn Type=3
Dn Slope=0.005
Boundary for River Rch & Prof#=UNT023 IN STEL,Reach-1,6
Up Type=0
Dn Type=3
Dn Slope=0.005
Boundary for River Rch & Prof#=UNT023 IN STEL,Reach-1,7
Up Type=0
Dn Type=3
Dn Slope=0.005

--- UNT023 IN STEL.g01 (geometry) ---

Geom Title=Existing Conditions

River Reach=UNT023 IN STEL,Reach-1
Reach XY= 30
      3480732.79     10479723.92      3480590.62     10479336.90
      3480824.19     10479014.15      3480851.26     10478896.78
      3480817.14     10478824.33      3480881.01     10478791.87
      3480821.34     10478584.58      3480871.10     10478511.16
      3480855.43     10478373.03      3480951.25     10478241.18
      3480940.57     10478137.65      3480882.12     10478102.91
      3480927.63     10477956.64      3480915.29     10477745.06
      3480828.48     10477624.62      3480659.21     10477559.51
      3480438.73     10477013.04      3480261.21     10476772.56
      3479724.64     10476492.00      3479777.34     10476153.13
      3479854.19     10476106.28      3479858.19     10476029.53
      3479936.32     10475947.40      3480126.80     10475464.88
      3480085.40     10475203.50      3480230.42     10474975.94
      3480315.72     10474611.27      3480451.95     10474386.52
      3480448.14     10474314.79      3480512.11     10474271.64

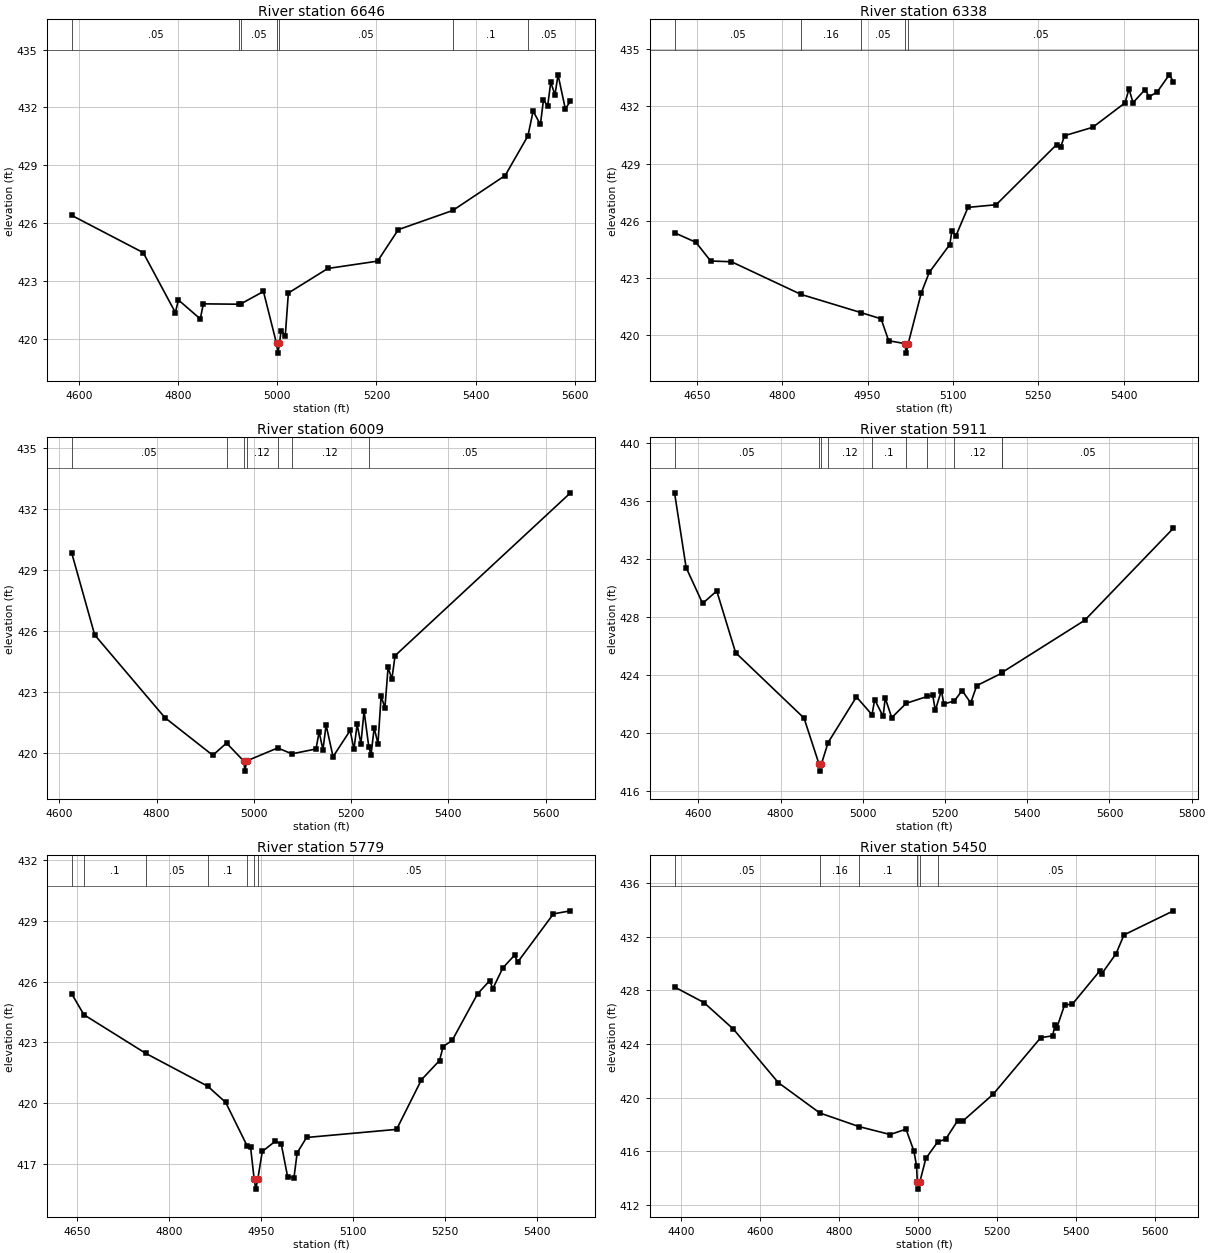
Type RM Length L Ch R = 1,6646,308,308,308
BEGIN DESCRIPTION:
UNT023 IN STEL 14.0
END DESCRIPTION:
XS GIS Cut Line= 2
      3480952.81     10479350.91      3480361.67     10480166.01
#Sta/Elev= 30
  4584.7  426.42  4729.2  424.49  4794.1  421.39  4800.3  422.04  4844.4  421.06
  4850.6  421.84  4923.1  421.82  4926.4  421.84  4971.9  422.48  4998.3  419.79
  5001.1  419.29  5004.3  419.79  5007.5  420.45  5016.0  420.20  5022.2  422.40
  5101.8  423.67  5202.3  424.05  5244.1  425.68  5353.9  426.67  5459.8  428.48
  5505.7  430.53  5516.2  431.81  5530.9  431.12  5537.1  432.39  5545.6  432.08
  5551.8  433.31  5560.3  432.65  5566.5  433.69  5581.2  431.93  5591.6  432.33
#Mann=7,-1,0
  4584.7    0.05       0  4923.1    0.16       0  4926.4    0.05       0
  4998.3    0.04       0  5004.3    0.05       0  5353.9     0.1       0
  5505.7    0.05       0
Bank Sta=4998.3,5004.3
Exp/Cntr=0.3,0.1

Type RM Length L Ch R = 1,6338,329,329,329
BEGIN DESCRIPTION:
UNT023 IN STEL 13.0
END DESCRIPTION:
XS GIS Cut Line= 3
      3480975.19     10479275.39      3480517.96     10479432.23
      3480240.20     10479709.99
#Sta/Elev= 30
  4611.0  425.38  4648.5  424.88  4674.4  423.90  4711.0  423.86  4833.0  422.15
  4939.0  421.19  4973.7  420.87  4987.1  419.72  5015.4  419.57  5018.1  419.07
  5021.4  419.57  5044.4  422.23  5058.3  423.30  5094.4  424.76  5098.1  425.46
  5105.2  425.22  5126.4  426.71  5175.9  426.85  5282.0  430.00  5289.0  429.86
  5296.1  430.47  5345.6  430.91  5402.2  432.19  5409.2  432.92  5416.3  432.20
  5437.5  432.89  5444.6  432.51  5458.7  432.76  5479.9  433.66  5487.2  433.31
#Mann=5,-1,0
  4611.0    0.05       0  4833.0    0.16       0  4939.0    0.05       0
  5015.4   0.035       0  5021.4    0.05       0
Bank Sta=5015.4,5021.4
Exp/Cntr=0.3,0.1

Type RM Length L Ch R = 1,6009,98,98,98
BEGIN DESCRIPTION:
Mapping XS 168ef745
END DESCRIPTION:
XS GIS Cut Line= 4
      3481096.09     10479229.11      3480715.87     10479116.26
      3480656.85     10479170.08      3480304.42     10479591.95
#Sta/Elev= 30
  4625.1  429.85  4672.6  425.80  4817.0  421.73  4915.5  419.88  4943.8  420.48
  4979.0  419.60  4981.7  419.10  4985.0  419.60  5049.0  420.24  5078.3  419.95
  5127.8  420.19  5134.3  421.03  5142.1  420.15  5148.6  421.37  5162.9  419.81
  5198.1  421.10  5205.9  420.17  5212.4  421.40  5220.2  420.45  5226.7  422.06
  5236.4  420.30  5241.0  419.89  5247.5  421.23  5255.3  420.45  5261.8  422.79
  5269.6  422.21  5276.1  424.20  5283.9  423.63  5290.5  424.78  5651.3  432.79
#Mann=7,-1,0
  4625.1    0.05       0  4943.8    0.12       0  4979.0    0.07       0
  4985.0    0.12       0  5049.0    0.05       0  5078.3    0.12       0
  5236.4    0.05       0
Bank Sta=4979,4985
Exp/Cntr=0.3,0.1

Type RM Length L Ch R = 1,5911,132,132,132
BEGIN DESCRIPTION:
Mapping XS 50141584
END DESCRIPTION:
XS GIS Cut Line= 5
      3481214.15     10479237.79      3480764.49     10479031.19
      3480719.35     10479019.04      3480559.62     10479244.73
      3480290.50     10479534.69
#Sta/Elev= 30
  4541.9  436.56  4570.1  431.40  4610.2  428.93  4644.6  429.79  4690.5  425.53
  4856.9  421.02  4893.3  417.86  4896.1  417.36  4899.3  417.86  4915.5  419.33
  4984.4  422.48  5022.4  421.25  5028.8  422.30  5049.3  421.13  5054.5  422.40
  5070.3  421.05  5105.5  422.04  5156.7  422.51  5170.1  422.60  5176.3  421.55
  5191.0  422.92  5197.2  422.00  5222.4  422.19  5241.5  422.92  5262.4  422.07
  5277.2  423.26  5338.1  424.12  5338.9  424.17  5540.0  427.77  5755.6  434.12
#Mann=10,-1,0
  4541.9    0.05       0  4893.3    0.07       0  4899.3    0.05       0
  4915.5    0.12       0  5022.4     0.1       0  5105.5    0.12       0
  5156.7    0.05       0  5222.4    0.12       0  5338.1     0.1       0
  5338.9    0.05       0
Bank Sta=4893.3,4899.3
Exp/Cntr=0.3,0.1

Type RM Length L Ch R = 1,5779,329,329,329
BEGIN DESCRIPTION:
Mapping XS db6e27cf
END DESCRIPTION:
XS GIS Cut Line= 2
      3481193.35     10479019.05      3480405.22     10478814.66
#Sta/Elev= 30
  4640.5  425.41  4660.6  424.37  4761.7  422.46  4862.7  420.84  4892.0  420.04
  4926.9  417.90  4932.6  417.83  4938.4  416.26  4941.1  415.76  4944.4  416.26
  4951.7  417.62  4973.2  418.13  4982.7  417.98  4993.0  416.38  5003.4  416.32
  5008.6  417.55  5024.0  418.31  5170.9  418.71  5211.5  421.16  5241.0  422.11
  5246.9  422.80  5261.6  423.10  5303.0  425.40  5322.9  426.05  5328.0  425.66
  5344.3  426.68  5363.4  427.31  5368.6  426.97  5426.9  429.35  5454.7  429.50
#Mann=7,-1,0
  4640.5    0.05       0  4660.6     0.1       0  4761.7    0.05       0
  4862.7     0.1       0  4926.9    0.05       0  4938.4    0.03       0
  4944.4    0.05       0
Bank Sta=4938.4,4944.4
Exp/Cntr=0.3,0.1

Type RM Length L Ch R = 1,5450,860,860,860
BEGIN DESCRIPTION:
UNT023 IN STEL 12.0
END DESCRIPTION:
XS GIS Cut Line= 2
      3481456.14     10478613.86      3480197.41     10478722.37
#Sta/Elev= 30
  4383.5  428.26  4457.8  427.10  4532.7  425.11  4646.1  421.12  4751.3  418.85
  4850.8  417.83  4929.6  417.24  4969.7  417.64  4989.8  416.00  4996.4  414.89
  4998.4  413.66  5001.2  413.16  5004.4  413.66  5019.9  415.45  5050.0  416.69
  5070.1  416.89  5100.2  418.26  5114.9  418.28  5190.5  420.25  5311.0  424.48
  5341.1  424.61  5346.7  425.41  5351.7  425.22  5371.2  426.91  5391.3  426.99
  5460.1  429.45  5465.2  429.24  5501.7  430.75  5521.7  432.15  5646.9  433.95
#Mann=6,-1,0
  4383.5    0.05       0  4751.3    0.16       0  4850.8     0.1       0
  4998.4    0.07       0  5004.4     0.1       0  5050.0    0.05       0
Bank Sta=4998.4,5004.4
Exp/Cntr=0.3,0.1

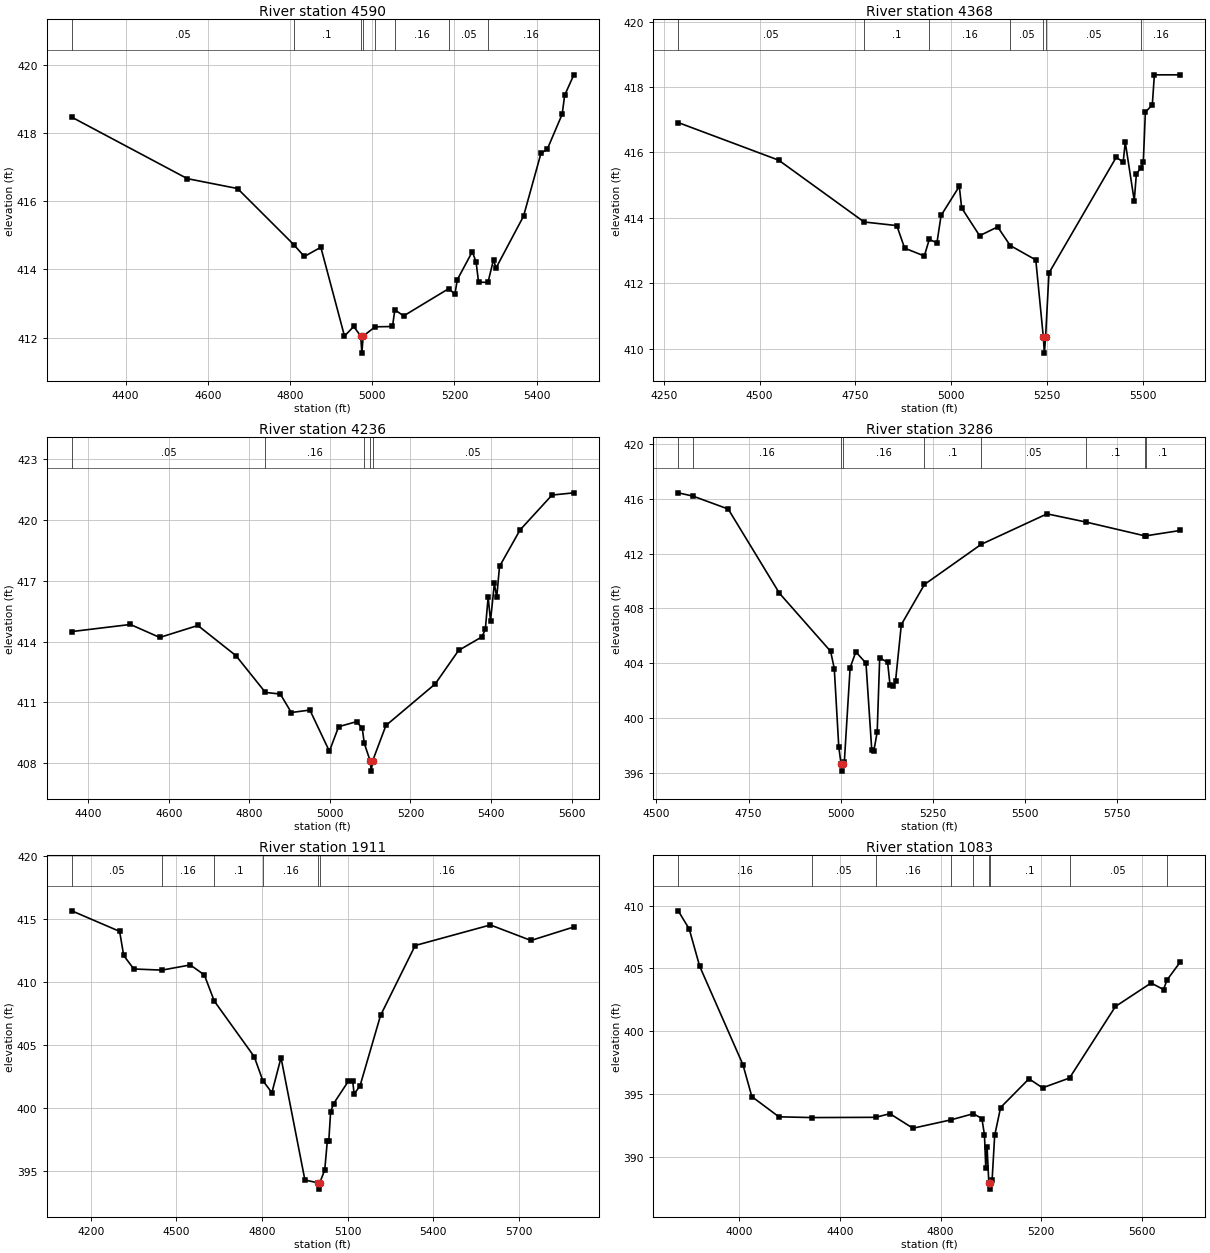
Type RM Length L Ch R = 1,4590,222,222,222
BEGIN DESCRIPTION:
UNT023 IN STEL 10.0
END DESCRIPTION:
XS GIS Cut Line= 4
      3481648.05     10478035.77      3481112.92     10477932.91
      3480901.99     10477939.42      3480653.30     10478332.63
#Sta/Elev= 30
  4269.3  418.46  4550.3  416.66  4672.5  416.37  4809.0  414.73  4835.0  414.38
  4875.1  414.65  4932.6  412.05  4955.1  412.33  4972.1  412.05  4974.9  411.55
  4978.1  412.05  5007.1  412.32  5049.4  412.33  5055.1  412.82  5076.5  412.64
  5186.4  413.44  5201.1  413.27  5207.0  413.70  5243.5  414.52  5252.7  414.22
  5258.7  413.63  5281.6  413.62  5295.2  414.29  5301.1  414.04  5368.1  415.56
  5410.5  417.40  5425.8  417.52  5462.2  418.55  5468.1  419.10  5490.5  419.70
#Mann=8,-1,0
  4269.3    0.05       0  4809.0     0.1       0  4972.1    0.07       0
  4978.1     0.1       0  5007.1    0.05       0  5055.1    0.16       0
  5186.4    0.05       0  5281.6    0.16       0
Bank Sta=4972.1,4978.1
Exp/Cntr=0.3,0.1

Type RM Length L Ch R = 1,4368,132,132,132
BEGIN DESCRIPTION:
Mapping XS 00a5f02b
END DESCRIPTION:
XS GIS Cut Line= 4
      3481597.32     10477869.12      3480943.04     10477715.12
      3480874.99     10477724.15      3480649.70     10478247.29
#Sta/Elev= 30
  4287.7  416.91  4549.9  415.76  4772.8  413.87  4858.1  413.76  4878.6  413.07
  4930.0  412.83  4942.9  413.34  4962.9  413.23  4973.7  414.07  5021.3  414.96
  5027.4  414.30  5074.3  413.45  5121.3  413.72  5154.2  413.15  5220.9  412.71
  5240.5  410.36  5243.3  409.86  5246.5  410.36  5255.3  412.31  5430.9  415.85
  5449.0  415.70  5454.4  416.31  5477.9  414.52  5483.4  415.34  5495.6  415.53
  5501.5  415.70  5506.9  417.23  5525.0  417.45  5530.4  418.37  5598.1  418.37
#Mann=7,-1,0
  4287.7    0.05       0  4772.8     0.1       0  4942.9    0.16       0
  5154.2    0.05       0  5240.5    0.07       0  5246.5    0.05       0
  5495.6    0.16       0
Bank Sta=5240.5,5246.5
Exp/Cntr=0.3,0.1

Type RM Length L Ch R = 1,4236,950,950,950
BEGIN DESCRIPTION:
UNT023 IN STEL 9.0
END DESCRIPTION:
XS GIS Cut Line= 2
      3481365.98     10477284.03      3480305.03     10477937.59
#Sta/Elev= 30
  4359.4  414.49  4504.9  414.84  4577.7  414.20  4672.3  414.79  4767.0  413.30
  4840.0  411.49  4877.0  411.41  4904.2  410.50  4950.4  410.62  4998.8  408.59
  5021.7  409.80  5066.3  410.05  5080.4  409.72  5085.4  408.98  5100.0  408.11
  5102.7  407.61  5106.0  408.11  5139.1  409.86  5261.5  411.91  5319.4  413.56
  5377.4  414.23  5385.8  414.60  5392.8  416.19  5398.7  415.02  5408.2  416.86
  5414.1  416.18  5421.0  417.70  5472.0  419.50  5551.3  421.22  5605.5  421.33
#Mann=5,-1,0
  4359.4    0.05       0  4840.0    0.16       0  5085.4    0.05       0
  5100.0    0.07       0  5106.0    0.05       0
Bank Sta=5100,5106
Exp/Cntr=0.3,0.1

Type RM Length L Ch R = 1,3286,1375,1375,1375
BEGIN DESCRIPTION:
UNT023 IN STEL 6.0
END DESCRIPTION:
XS GIS Cut Line= 3
      3480718.28     10476660.73      3479676.60     10477268.38
      3479633.73     10477418.43
#Sta/Elev= 30
  4559.0  416.42  4599.1  416.18  4694.5  415.24  4833.5  409.11  4972.4  404.88
  4982.3  403.63  4994.5  397.93  5000.8  396.66  5003.6  396.16  5006.8  396.66
  5009.6  396.85  5025.3  403.69  5040.8  404.84  5068.3  404.02  5084.0  397.69
  5089.8  397.65  5098.7  399.01  5105.5  404.41  5127.0  404.08  5133.4  402.44
  5142.7  402.38  5148.5  402.72  5164.2  406.83  5227.0  409.75  5380.9  412.67
  5559.5  414.89  5665.4  414.29  5826.1  413.28  5827.8  413.29  5921.0  413.68
#Mann=9,-1,0
  4559.0     0.1       0  4599.1    0.16       0  5000.8    0.07       0
  5006.8    0.16       0  5227.0     0.1       0  5380.9    0.05       0
  5665.4     0.1       0  5826.1    0.05       0  5827.8     0.1       0
Bank Sta=5000.8,5006.8
Exp/Cntr=0.3,0.1

Type RM Length L Ch R = 1,1911,828,828,828
BEGIN DESCRIPTION:
UNT023 IN STEL 3.0
END DESCRIPTION:
XS GIS Cut Line= 4
      3480642.32     10476378.63      3480343.79     10476066.60
      3479591.24     10475884.40      3479242.60     10476313.49
#Sta/Elev= 30
  4133.6  415.64  4301.3  414.01  4315.5  412.10  4350.9  411.03  4449.4  410.94
  4548.9  411.35  4598.0  410.56  4632.8  408.49  4772.8  404.08  4802.8  402.19
  4834.7  401.22  4866.7  404.00  4950.4  394.30  4996.3  394.08  4999.1  393.58
  5002.3  394.08  5019.9  395.10  5028.9  397.40  5034.0  397.37  5040.5  399.71
  5050.7  400.35  5102.2  402.12  5117.7  402.17  5122.8  401.13  5143.3  401.75
  5215.4  407.35  5336.7  412.89  5600.2  414.52  5742.4  413.29  5892.6  414.36
#Mann=6,-1,0
  4133.6    0.05       0  4449.4    0.16       0  4632.8     0.1       0
  4802.8    0.16       0  4996.3    0.07       0  5002.3    0.16       0
Bank Sta=4996.3,5002.3
Exp/Cntr=0.3,0.1

Type RM Length L Ch R = 1,1083,0,0,0
BEGIN DESCRIPTION:
UNT023 IN STEL 1.0
END DESCRIPTION:
XS GIS Cut Line= 4
      3481065.49     10475619.06      3480661.24     10475097.77
      3479806.81     10475250.15      3479503.69     10475607.40
#Sta/Elev= 30
  3757.2  409.58  3800.9  408.13  3842.5  405.16  4014.5  397.32  4049.8  394.78
  4157.5  393.17  4290.0  393.11  4541.8  393.13  4598.8  393.42  4690.2  392.26
  4841.9  392.93  4930.6  393.42  4964.5  393.03  4974.7  391.72  4979.9  389.07
  4985.0  390.79  4992.0  387.91  4994.7  387.41  4998.0  387.91  5005.1  388.15
  5015.3  391.69  5038.8  393.91  5151.7  396.20  5205.5  395.48  5312.8  396.26
  5495.4  401.96  5637.1  403.83  5686.5  403.31  5700.8  404.08  5753.3  405.51
#Mann=9,-1,0
  3757.2    0.16       0  4290.0    0.05       0  4541.8    0.16       0
  4841.9    0.12       0  4930.6     0.1       0  4992.0    0.07       0
  4998.0     0.1       0  5312.8    0.05       0  5700.8    0.16       0
Bank Sta=4992,4998
Exp/Cntr=0.3,0.1

Chan Stop Cuts=-1