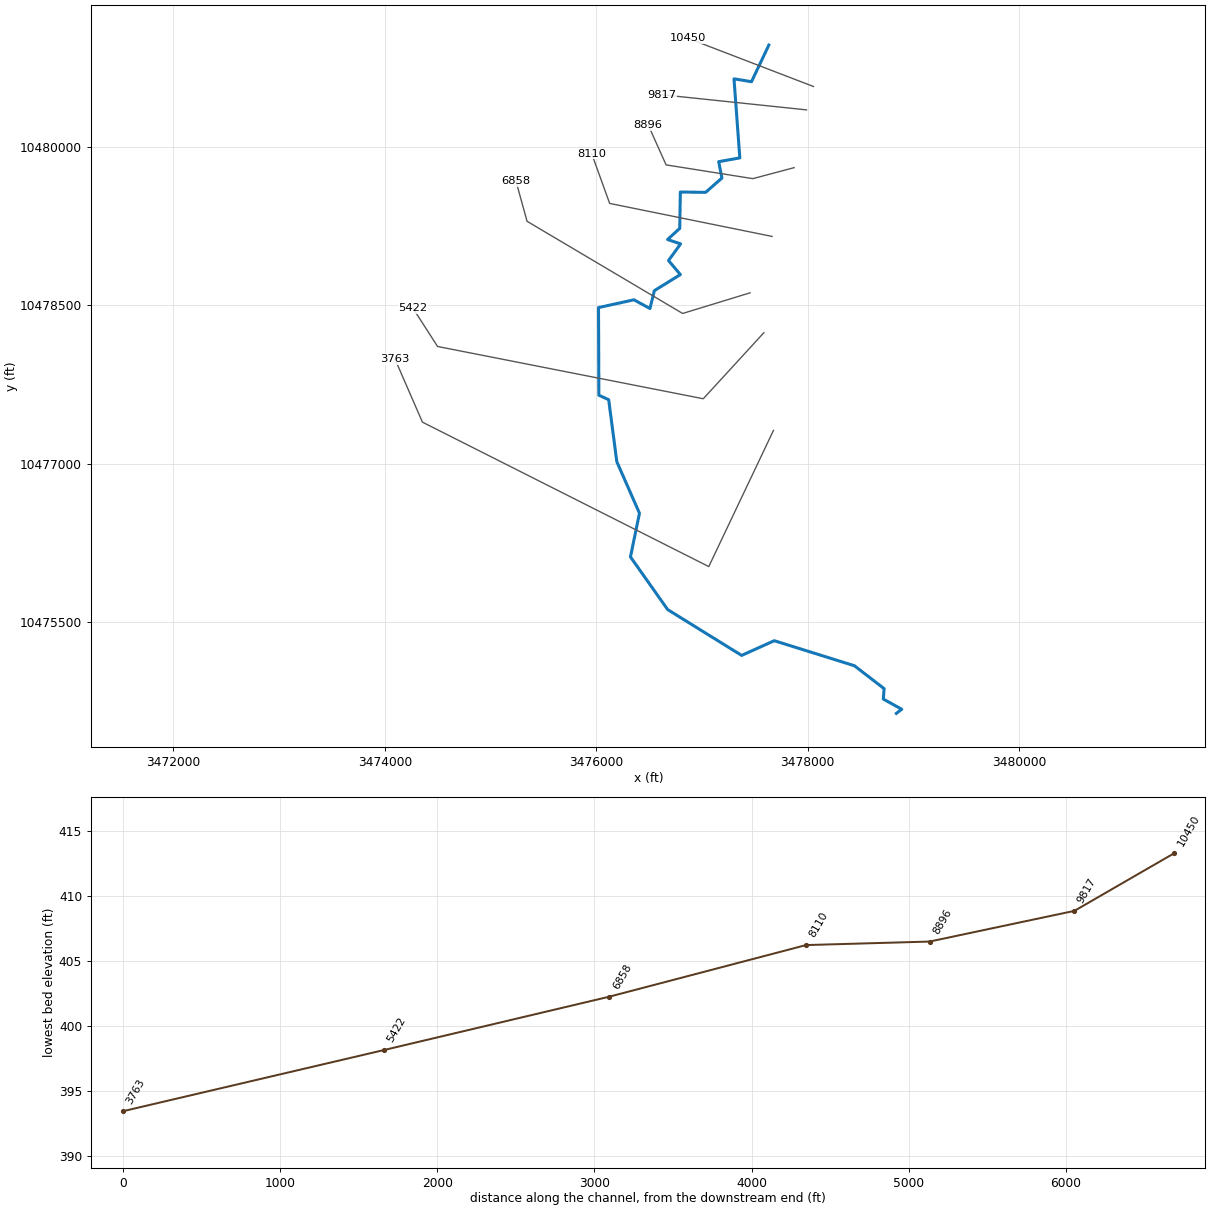
--- UNT024 IN STEL.prj (project) ---

Proj Title=UNT024 IN STEL Base Level Engineering
Current Plan=p01
Default Exp/Contr=0.3,0.1
English Units
Geom File=g01
Flow File=f01
Plan File=p01
BEGIN DESCRIPTION:
UNT024 IN STEL
END DESCRIPTION:

--- UNT024 IN STEL.p01 (plan) ---

Plan Title=Multiple Run
Short Identifier=Multiple
Geom File=g01
Flow File=f01
Subcritical Flow
K Sum by GR= 0
Std Step Tol= 0.01
Critical Tol= 0.01
Num of Std Step Trials= 20
Max Error Tol= 0.3
Flow Tol Ratio= 0.001
Split Flow NTrial= 30
Split Flow Tol= 0.02
Split Flow Ratio= 0.02
Log Output Level= 0
Friction Slope Method= 1
Unsteady Friction Slope Method= 2
Unsteady Bridges Friction Slope Method= 1
Parabolic Critical Depth
Global Vel Dist=  1 , 1 , 1
Global Log Level= 0
CheckData=True
Encroach Param= -1, 0, 0, 0
BEGIN DESCRIPTION:
Multiple Run
END DESCRIPTION:

--- UNT024 IN STEL.f01 (steady flow) ---

Flow Title=Multiple
Number of Profiles=7
Profile Names=10-year,25-year,50-year,1pct_min,100-year,1pct_plu,500-year
River Rch & RM= UNT024 IN STEL,Reach-1,10450
     781    1050    1267    1114    1506    2037    2126
Boundary for River Rch & Prof#=UNT024 IN STEL,Reach-1,1
Up Type=0
Dn Type=3
Dn Slope=0.005
Boundary for River Rch & Prof#=UNT024 IN STEL,Reach-1,2
Up Type=0
Dn Type=3
Dn Slope=0.005
Boundary for River Rch & Prof#=UNT024 IN STEL,Reach-1,3
Up Type=0
Dn Type=3
Dn Slope=0.005
Boundary for River Rch & Prof#=UNT024 IN STEL,Reach-1,4
Up Type=0
Dn Type=3
Dn Slope=0.005
Boundary for River Rch & Prof#=UNT024 IN STEL,Reach-1,5
Up Type=0
Dn Type=3
Dn Slope=0.005
Boundary for River Rch & Prof#=UNT024 IN STEL,Reach-1,6
Up Type=0
Dn Type=3
Dn Slope=0.005
Boundary for River Rch & Prof#=UNT024 IN STEL,Reach-1,7
Up Type=0
Dn Type=3
Dn Slope=0.005

--- UNT024 IN STEL.g01 (geometry) ---

Geom Title=Existing Conditions

River Reach=UNT024 IN STEL,Reach-1
Reach XY= 30
      3477632.68     10480960.98      3477468.56     10480614.75
      3477303.09     10480642.00      3477358.24     10479893.62
      3477158.55     10479858.01      3477188.82     10479702.75
      3477034.77     10479567.42      3476795.64     10479570.80
      3476790.11     10479226.46      3476674.73     10479121.30
      3476797.79     10479079.56      3476683.85     10478921.81
      3476796.18     10478789.27      3476549.92     10478637.04
      3476508.39     10478467.87      3476357.09     10478550.37
      3476021.69     10478476.81      3476025.03     10477647.25
      3476117.92     10477605.03      3476194.66     10477018.10
      3476409.02     10476530.29      3476323.98     10476117.01
      3476675.68     10475618.26      3477375.42     10475184.48
      3477684.02     10475323.80      3478441.83     10475086.82
      3478722.64     10474870.31      3478715.65     10474771.32
      3478889.72     10474674.71      3478838.79     10474635.87

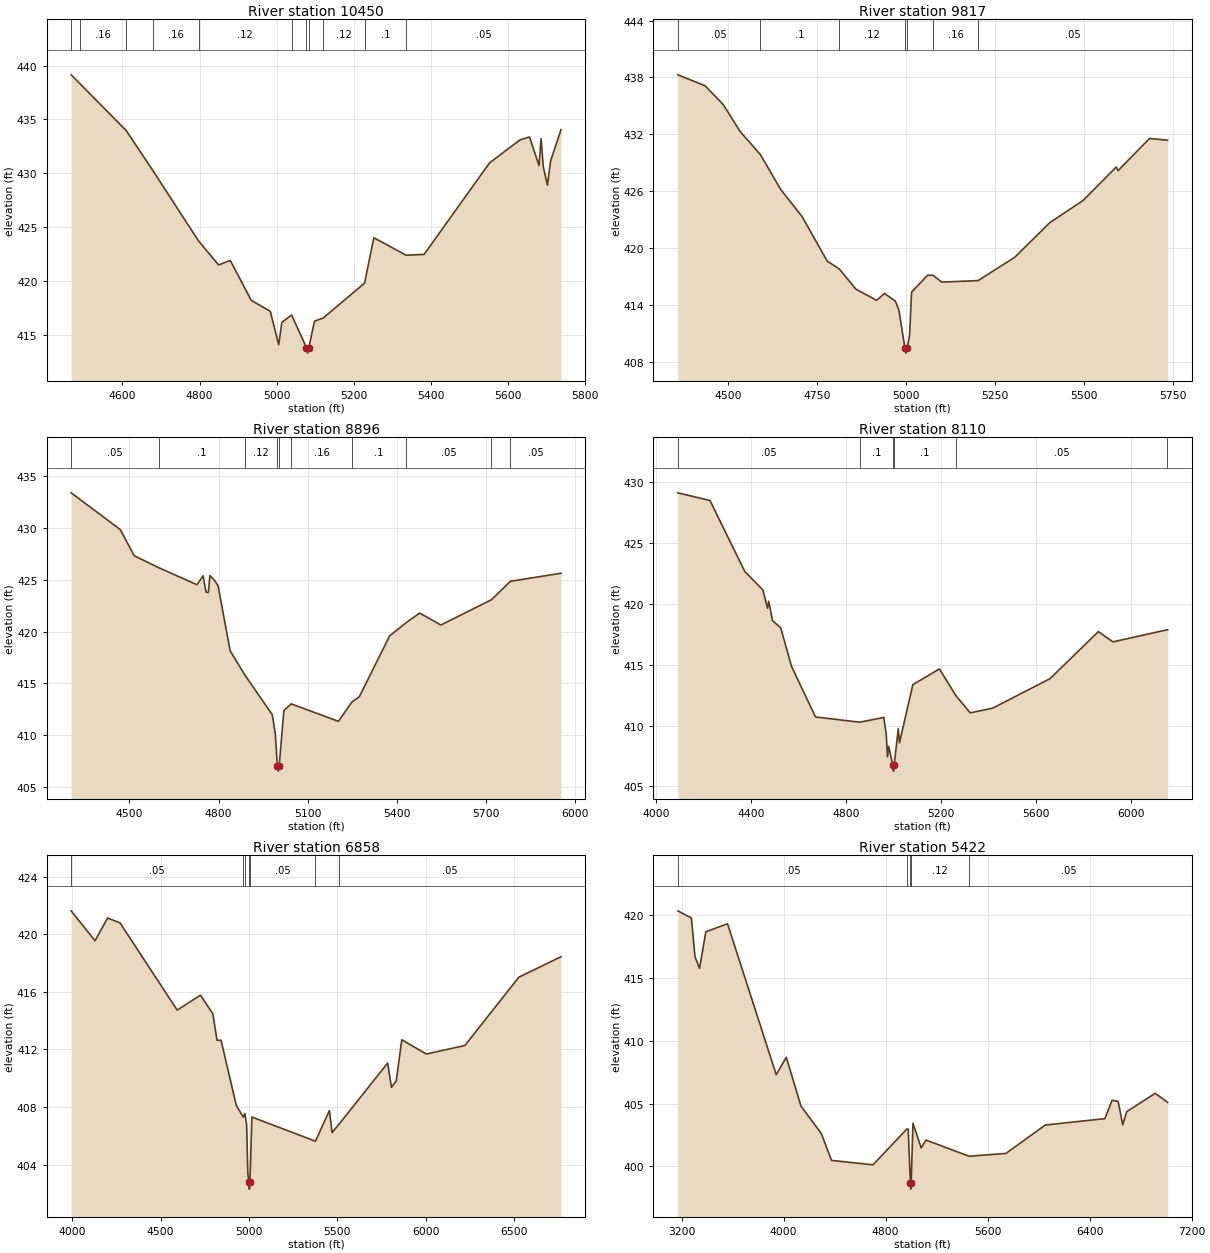
Type RM Length L Ch R = 1,10450,633,633,633
BEGIN DESCRIPTION:
UNT024 IN STEL 12.0
END DESCRIPTION:
XS GIS Cut Line= 2
      3478054.19     10480569.60      3476869.31     10481025.32
#Sta/Elev= 30
  4467.3  439.14  4490.6  438.30  4609.9  433.97  4679.0  430.26  4797.5  423.72
  4849.5  421.49  4879.5  421.92  4934.1  418.21  4983.4  417.19  5005.2  414.09
  5013.4  416.17  5038.7  416.85  5077.2  413.81  5080.0  413.31  5083.2  413.81
  5098.0  416.28  5120.2  416.56  5227.8  419.81  5251.7  424.02  5335.3  422.40
  5382.0  422.47  5551.7  430.97  5630.5  433.10  5655.2  433.37  5679.8  430.73
  5685.2  433.21  5690.9  430.61  5701.7  428.90  5709.8  431.13  5736.8  434.05
#Mann=11,-1,0
  4467.3    0.05       0  4490.6    0.16       0  4609.9     0.1       0
  4679.0    0.16       0  4797.5    0.12       0  5038.7     0.1       0
  5077.2    0.07       0  5083.2     0.1       0  5120.2    0.12       0
  5227.8     0.1       0  5335.3    0.05       0
Bank Sta=5077.2,5083.2
Exp/Cntr=0.3,0.1

Type RM Length L Ch R = 1,9817,921,921,921
BEGIN DESCRIPTION:
UNT024 IN STEL 11.0
END DESCRIPTION:
XS GIS Cut Line= 2
      3477989.07     10480348.24      3476621.95     10480491.46
#Sta/Elev= 30
  4359.3  438.28  4435.8  437.13  4487.0  435.13  4534.1  432.30  4591.1  429.85
  4647.8  426.19  4708.2  423.30  4778.5  418.61  4812.4  417.78  4859.0  415.65
  4917.1  414.47  4939.4  415.19  4969.6  414.39  4979.6  413.46  4996.8  409.39
  4999.5  408.89  5002.8  409.39  5009.8  410.79  5015.3  415.33  5060.1  417.11
  5075.5  417.11  5100.3  416.39  5201.9  416.55  5305.1  419.02  5403.3  422.67
  5496.6  425.01  5589.8  428.55  5594.8  428.16  5683.0  431.56  5733.9  431.37
#Mann=7,-1,0
  4359.3    0.05       0  4591.1     0.1       0  4812.4    0.12       0
  4996.8    0.07       0  5002.8    0.12       0  5075.5    0.16       0
  5201.9    0.05       0
Bank Sta=4996.8,5002.8
Exp/Cntr=0.3,0.1

Type RM Length L Ch R = 1,8896,786,786,786
BEGIN DESCRIPTION:
UNT024 IN STEL 9.0
END DESCRIPTION:
XS GIS Cut Line= 4
      3477871.96     10479801.37      3477481.29     10479697.20
      3476660.98     10479827.40      3476491.71     10480205.00
#Sta/Elev= 30
  4303.8  433.42  4469.2  429.87  4516.0  427.34  4599.1  426.18  4727.5  424.54
  4747.8  425.40  4757.9  423.82  4765.7  423.80  4770.7  425.43  4788.3  424.89
  4798.4  424.42  4838.9  418.16  4889.8  415.76  4980.7  411.98  4990.8  410.18
  4997.9  407.03  5000.7  406.53  5003.9  407.03  5019.8  412.38  5044.5  413.03
  5203.4  411.34  5248.2  413.19  5274.0  413.73  5375.6  419.59  5431.6  420.88
  5476.8  421.80  5548.5  420.65  5718.4  423.09  5782.3  424.87  5952.5  425.65
#Mann=10,-1,0
  4303.8    0.05       0  4599.1     0.1       0  4889.8    0.12       0
  4997.9    0.07       0  5003.9    0.12       0  5044.5    0.16       0
  5248.2     0.1       0  5431.6    0.05       0  5718.4     0.1       0
  5782.3    0.05       0
Bank Sta=4997.9,5003.9
Exp/Cntr=0.3,0.1

Type RM Length L Ch R = 1,8110,1252,1252,1252
BEGIN DESCRIPTION:
UNT024 IN STEL 7.0
END DESCRIPTION:
XS GIS Cut Line= 3
      3477663.61     10479150.31      3476127.13     10479462.82
      3475957.86     10479931.55
#Sta/Elev= 30
  4090.2  429.08  4225.9  428.45  4372.6  422.63  4448.9  421.12  4468.7  419.61
  4473.8  420.19  4489.7  418.60  4524.4  418.01  4569.9  414.85  4671.1  410.70
  4857.7  410.27  4959.1  410.66  4969.3  409.29  4974.7  407.43  4979.8  408.29
  4997.0  406.76  4999.7  406.26  5003.0  406.76  5020.2  409.74  5025.3  408.58
  5081.6  413.35  5193.8  414.64  5264.6  412.41  5323.8  411.04  5418.4  411.42
  5660.2  413.84  5864.3  417.70  5925.6  416.86  6152.3  417.84  6156.5  417.84
#Mann=6,-1,0
  4090.2    0.05       0  4857.7     0.1       0  4997.0    0.07       0
  5003.0     0.1       0  5264.6    0.05       0  6152.3     0.1       0
Bank Sta=4997,5003
Exp/Cntr=0.3,0.1

Type RM Length L Ch R = 1,6858,1436,1436,1436
BEGIN DESCRIPTION:
UNT024 IN STEL 5.0
END DESCRIPTION:
XS GIS Cut Line= 4
      3477455.22     10478616.46      3476817.23     10478421.15
      3475345.88     10479293.55      3475241.70     10479671.19
#Sta/Elev= 30
  3994.8  421.63  4129.8  419.55  4200.6  421.13  4271.3  420.79  4594.2  414.73
  4725.9  415.77  4796.0  414.47  4819.1  412.64  4842.4  412.63  4928.6  408.10
  4968.4  407.29  4976.7  407.55  4987.1  406.76  4993.5  403.40  4999.7  402.79
  5002.5  402.29  5005.7  402.79  5016.7  407.30  5376.0  405.62  5454.9  407.75
  5470.1  406.22  5509.3  406.80  5784.0  411.05  5805.7  409.37  5833.0  409.81
  5864.2  412.67  6002.6  411.68  6220.9  412.27  6526.2  417.02  6764.3  418.44
#Mann=7,-1,0
  3994.8    0.05       0  4968.4    0.12       0  4976.7    0.05       0
  4999.7   0.035       0  5005.7    0.05       0  5376.0    0.12       0
  5509.3    0.05       0
Bank Sta=4999.7,5005.7
Exp/Cntr=0.3,0.1

Type RM Length L Ch R = 1,5422,1659,1659,1659
BEGIN DESCRIPTION:
UNT024 IN STEL 4.0
END DESCRIPTION:
XS GIS Cut Line= 4
      3477585.48     10478238.89      3477012.54     10477613.86
      3474499.52     10478108.65      3474266.11     10478471.74
#Sta/Elev= 30
  3170.4  420.37  3276.8  419.80  3305.1  416.71  3340.9  415.79  3390.2  418.70
  3560.1  419.34  3942.1  407.31  4021.1  408.69  4136.1  404.80  4295.3  402.62
  4375.5  400.47  4701.1  400.12  4966.9  402.98  4976.8  402.96  4994.2  398.68
  4996.9  398.18  5000.2  398.68  5014.3  403.43  5078.7  401.47  5117.1  402.09
  5454.5  400.80  5743.6  401.03  6051.8  403.29  6519.1  403.80  6575.7  405.27
  6622.9  405.18  6659.2  403.31  6689.6  404.35  6913.5  405.82  7011.2  405.10
#Mann=5,-1,0
  3170.4    0.05       0  4966.9    0.12       0  4994.2    0.07       0
  5000.2    0.12       0  5454.5    0.05       0
Bank Sta=4994.2,5000.2
Exp/Cntr=0.3,0.1

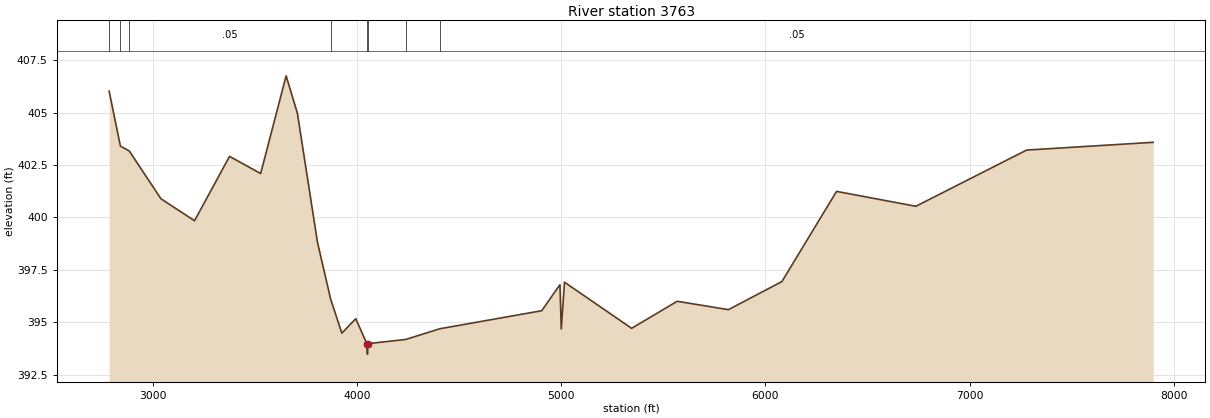
Type RM Length L Ch R = 1,3763,0,0,0
BEGIN DESCRIPTION:
UNT024 IN STEL 1.0
END DESCRIPTION:
XS GIS Cut Line= 4
      3477676.58     10477314.34      3477064.63     10476025.32
      3474356.29     10477392.51      3474096.51     10477990.01
#Sta/Elev= 30
  2786.1  406.02  2841.4  403.40  2884.5  403.17  3039.8  400.89  3204.4  399.84
  3375.8  402.91  3528.1  402.09  3652.8  406.75  3707.9  404.97  3806.4  398.81
  3870.6  396.11  3925.6  394.48  3993.8  395.17  4048.0  393.98  4050.8  393.48
  4054.0  393.98  4238.7  394.18  4405.5  394.69  4904.3  395.55  4993.5  396.79
  5000.0  394.68  5015.8  396.91  5344.6  394.71  5567.6  396.00  5818.5  395.60
  6080.4  396.94  6348.0  401.24  6736.3  400.53  7278.6  403.21  7898.4  403.58
#Mann=8,-1,0
  2786.1    0.05       0  2841.4     0.1       0  2884.5    0.05       0
  3870.6     0.1       0  4048.0    0.03       0  4054.0     0.1       0
  4238.7     0.1       0  4405.5    0.05       0
Bank Sta=4048,4054
Exp/Cntr=0.3,0.1

Chan Stop Cuts=-1