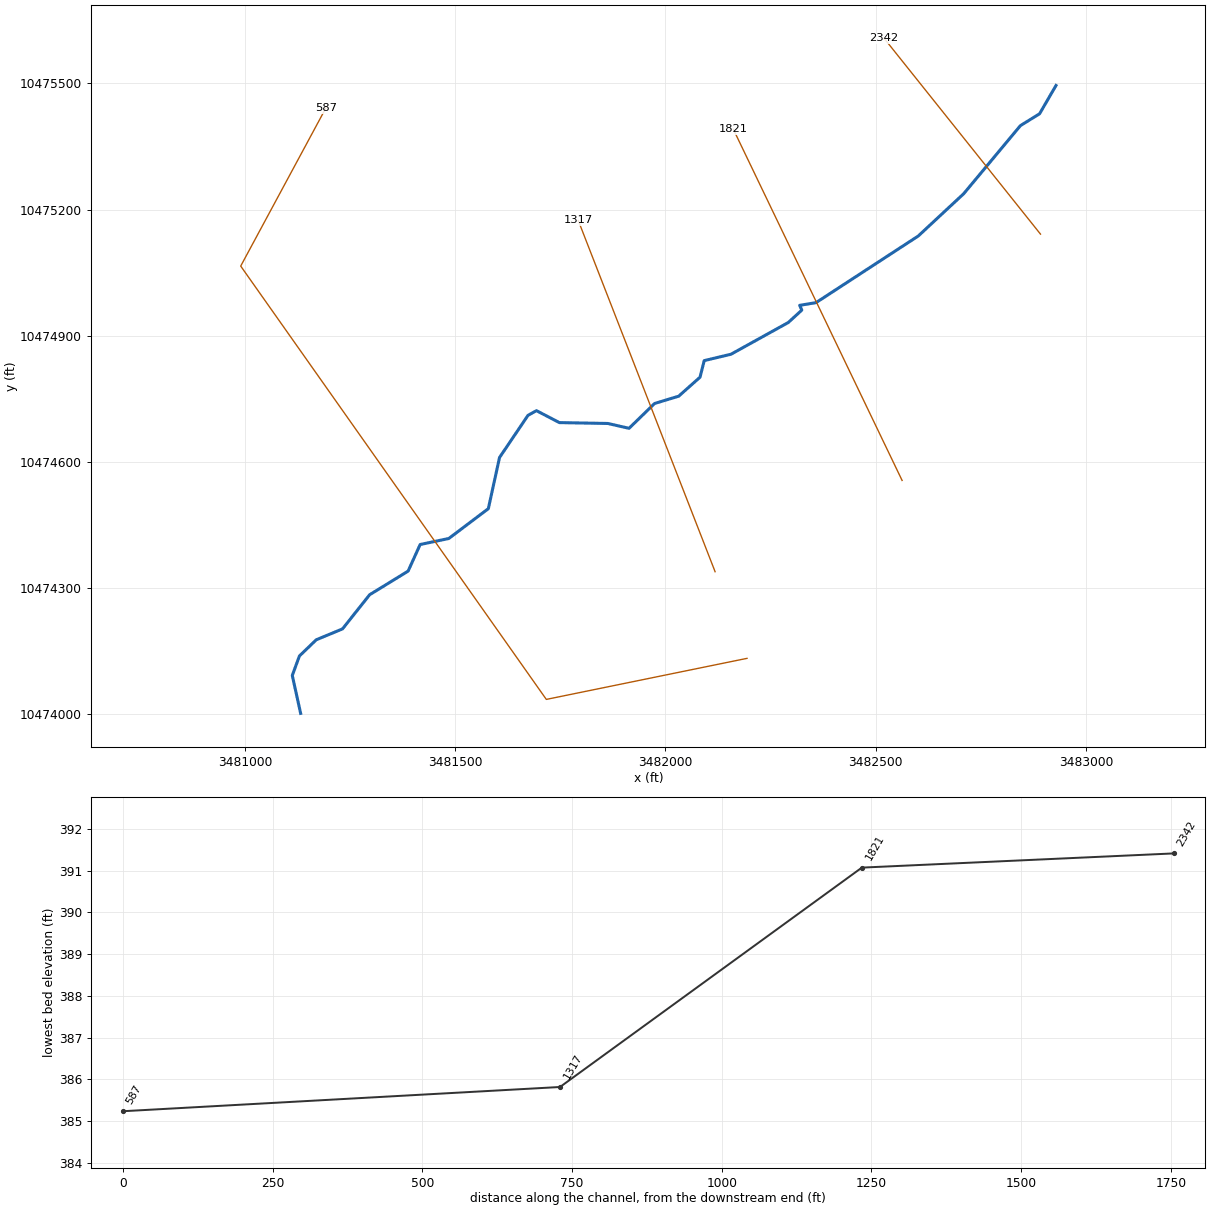
--- UNT026 IN STEL.prj (project) ---

Proj Title=UNT026 IN STEL Base Level Engineering
Current Plan=p01
Default Exp/Contr=0.3,0.1
English Units
Geom File=g01
Flow File=f01
Plan File=p01
BEGIN DESCRIPTION:
UNT026 IN STEL
END DESCRIPTION:

--- UNT026 IN STEL.p01 (plan) ---

Plan Title=Multiple Run
Short Identifier=Multiple
Geom File=g01
Flow File=f01
Subcritical Flow
K Sum by GR= 0
Std Step Tol= 0.01
Critical Tol= 0.01
Num of Std Step Trials= 20
Max Error Tol= 0.3
Flow Tol Ratio= 0.001
Split Flow NTrial= 30
Split Flow Tol= 0.02
Split Flow Ratio= 0.02
Log Output Level= 0
Friction Slope Method= 1
Unsteady Friction Slope Method= 2
Unsteady Bridges Friction Slope Method= 1
Parabolic Critical Depth
Global Vel Dist=  1 , 1 , 1
Global Log Level= 0
CheckData=True
Encroach Param= -1, 0, 0, 0
BEGIN DESCRIPTION:
Multiple Run
END DESCRIPTION:

--- UNT026 IN STEL.f01 (steady flow) ---

Flow Title=Multiple
Number of Profiles=7
Profile Names=10-year,25-year,50-year,1pct_min,100-year,1pct_plu,500-year
River Rch & RM= UNT026 IN STEL,Reach-1,2342
     914    1250    1525    1358    1836    2483    2654
Boundary for River Rch & Prof#=UNT026 IN STEL,Reach-1,1
Up Type=0
Dn Type=3
Dn Slope=0.005
Boundary for River Rch & Prof#=UNT026 IN STEL,Reach-1,2
Up Type=0
Dn Type=3
Dn Slope=0.005
Boundary for River Rch & Prof#=UNT026 IN STEL,Reach-1,3
Up Type=0
Dn Type=3
Dn Slope=0.005
Boundary for River Rch & Prof#=UNT026 IN STEL,Reach-1,4
Up Type=0
Dn Type=3
Dn Slope=0.005
Boundary for River Rch & Prof#=UNT026 IN STEL,Reach-1,5
Up Type=0
Dn Type=3
Dn Slope=0.005
Boundary for River Rch & Prof#=UNT026 IN STEL,Reach-1,6
Up Type=0
Dn Type=3
Dn Slope=0.005
Boundary for River Rch & Prof#=UNT026 IN STEL,Reach-1,7
Up Type=0
Dn Type=3
Dn Slope=0.005

--- UNT026 IN STEL.g01 (geometry) ---

Geom Title=Existing Conditions

River Reach=UNT026 IN STEL,Reach-1
Reach XY= 30
      3482928.97     10475495.25      3482889.90     10475427.98
      3482844.33     10475399.77      3482709.46     10475237.84
      3482601.27     10475137.18      3482358.22     10474978.76
      3482319.16     10474972.25      3482324.35     10474961.01
      3482292.24     10474931.50      3482155.88     10474855.97
      3482092.15     10474840.78      3482082.17     10474801.29
      3482031.39     10474756.15      3481974.09     10474738.79
      3481913.33     10474679.76      3481862.82     10474691.26
      3481747.63     10474693.32      3481693.10     10474721.75
      3481672.94     10474710.56      3481605.24     10474610.34
      3481578.59     10474488.58      3481484.55     10474417.65
      3481416.44     10474403.33      3481387.73     10474340.04
      3481296.24     10474283.82      3481231.68     10474202.55
      3481169.28     10474176.72      3481129.25     10474138.18
      3481112.23     10474091.79      3481132.11     10474001.64

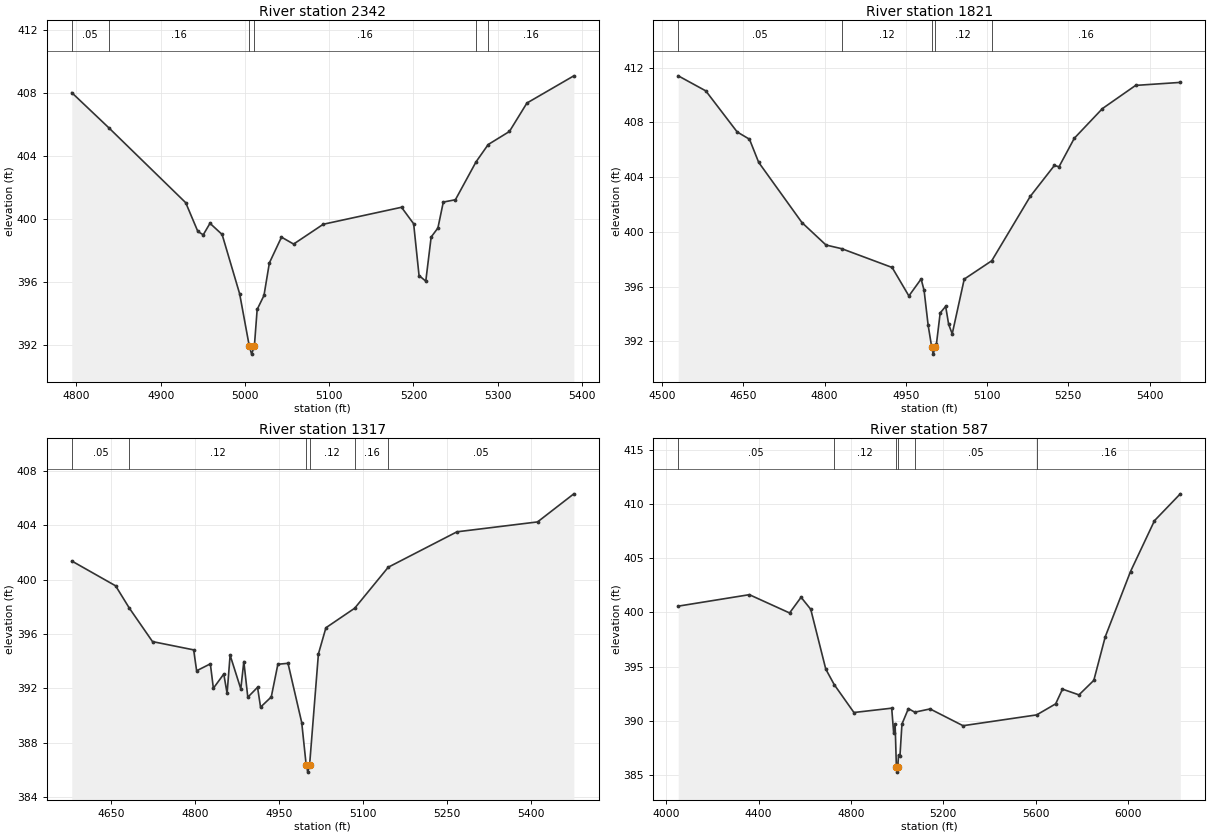
Type RM Length L Ch R = 1,2342,521,521,521
BEGIN DESCRIPTION:
UNT026 IN STEL 4.0
END DESCRIPTION:
XS GIS Cut Line= 2
      3482892.11     10475141.64      3482520.12     10475607.43
#Sta/Elev= 30
  4794.4  408.04  4838.3  405.81  4929.7  401.04  4944.1  399.21  4950.5  399.00
  4958.5  399.73  4972.9  399.02  4993.7  395.25  5005.2  391.91  5007.9  391.41
  5011.2  391.91  5014.5  394.25  5022.6  395.14  5029.0  397.21  5043.4  398.85
  5057.8  398.41  5093.0  399.67  5185.9  400.75  5200.3  399.70  5206.7  396.41
  5214.7  396.05  5221.1  398.86  5229.1  399.43  5235.5  401.08  5249.9  401.23
  5274.4  403.64  5288.8  404.74  5314.0  405.57  5334.8  407.38  5390.5  409.11
#Mann=6,-1,0
  4794.4    0.05       0  4838.3    0.16       0  5005.2    0.07       0
  5011.2    0.16       0  5274.4    0.05       0  5288.8    0.16       0
Bank Sta=5005.2,5011.2
Exp/Cntr=0.3,0.1

Type RM Length L Ch R = 1,1821,504,504,504
BEGIN DESCRIPTION:
UNT026 IN STEL 3.0
END DESCRIPTION:
XS GIS Cut Line= 2
      3482562.87     10474555.73      3482161.42     10475391.19
#Sta/Elev= 30
  4529.9  411.40  4580.8  410.30  4638.7  407.30  4661.4  406.77  4678.4  405.08
  4758.3  400.68  4802.7  399.04  4831.9  398.77  4924.8  397.40  4955.7  395.32
  4978.3  396.56  4983.8  395.72  4991.3  393.17  4997.9  391.57  5000.7  391.07
  5003.9  391.57  5006.5  391.78  5013.5  394.08  5023.6  394.56  5029.1  393.25
  5035.7  392.55  5057.9  396.55  5108.7  397.89  5179.9  402.60  5224.3  404.85
  5232.9  404.76  5261.1  406.84  5313.1  409.01  5374.3  410.70  5456.8  410.92
#Mann=5,-1,0
  4529.9    0.05       0  4831.9    0.12       0  4997.9    0.07       0
  5003.9    0.12       0  5108.7    0.16       0
Bank Sta=4997.9,5003.9
Exp/Cntr=0.3,0.1

Type RM Length L Ch R = 1,1317,730,730,730
BEGIN DESCRIPTION:
UNT026 IN STEL 2.0
END DESCRIPTION:
XS GIS Cut Line= 2
      3482118.02     10474338.67      3481792.49     10475174.20
#Sta/Elev= 30
  4579.5  401.38  4657.8  399.55  4682.1  397.92  4723.7  395.44  4797.2  394.83
  4802.5  393.29  4827.0  393.80  4832.4  392.00  4851.0  393.05  4856.9  391.62
  4862.3  394.44  4881.4  391.95  4886.8  393.97  4893.9  391.34  4911.3  392.07
  4916.7  390.61  4935.8  391.36  4947.6  393.77  4965.7  393.84  4990.2  389.47
  4998.2  386.32  5001.0  385.82  5004.2  386.32  5020.0  394.53  5033.4  396.46
  5084.8  397.90  5144.7  400.92  5267.4  403.53  5411.4  404.26  5476.2  406.33
#Mann=6,-1,0
  4579.5    0.05       0  4682.1    0.12       0  4998.2    0.07       0
  5004.2    0.12       0  5084.8    0.16       0  5144.7    0.05       0
Bank Sta=4998.2,5004.2
Exp/Cntr=0.3,0.1

Type RM Length L Ch R = 1,587,0,0,0
BEGIN DESCRIPTION:
UNT026 IN STEL 1.0
END DESCRIPTION:
XS GIS Cut Line= 4
      3482194.00     10474132.53      3481716.54     10474034.87
      3480989.54     10475065.69      3481192.10     10475441.64
#Sta/Elev= 30
  4051.5  400.58  4359.6  401.64  4534.1  399.95  4583.8  401.40  4625.7  400.29
  4690.9  394.76  4727.4  393.33  4812.9  390.75  4976.6  391.15  4985.3  388.81
  4991.4  389.65  4996.9  385.74  4999.7  385.24  5002.9  385.74  5006.2  386.83
  5012.3  386.72  5021.0  389.68  5048.9  391.11  5076.5  390.78  5142.9  391.08
  5285.7  389.53  5604.9  390.53  5687.1  391.55  5716.7  392.91  5788.1  392.38
  5852.4  393.72  5902.0  397.75  6011.5  403.78  6115.4  408.48  6227.3  410.96
#Mann=6,-1,0
  4051.5    0.05       0  4727.4    0.12       0  4996.9    0.07       0
  5002.9    0.12       0  5076.5    0.05       0  5604.9    0.16       0
Bank Sta=4996.9,5002.9
Exp/Cntr=0.3,0.1

Chan Stop Cuts=-1