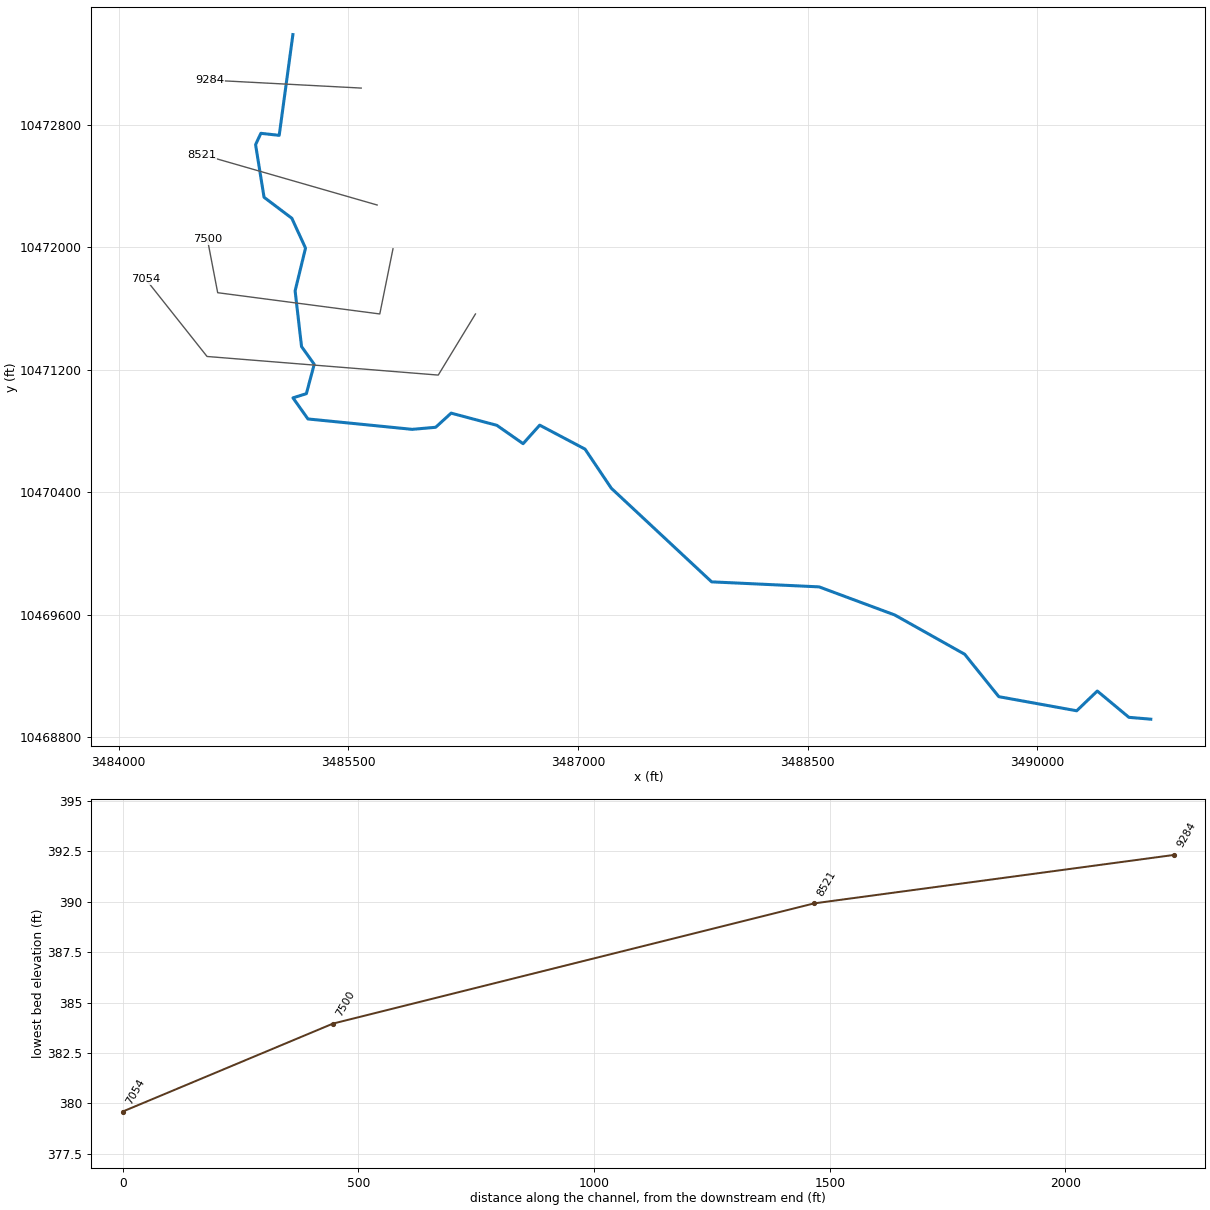
--- UNT027 IN STEL.prj (project) ---

Proj Title=UNT027 IN STEL Base Level Engineering
Current Plan=p01
Default Exp/Contr=0.3,0.1
English Units
Geom File=g01
Flow File=f01
Plan File=p01
BEGIN DESCRIPTION:
UNT027 IN STEL
END DESCRIPTION:

--- UNT027 IN STEL.p01 (plan) ---

Plan Title=Multiple Run
Short Identifier=Multiple
Geom File=g01
Flow File=f01
Subcritical Flow
K Sum by GR= 0
Std Step Tol= 0.01
Critical Tol= 0.01
Num of Std Step Trials= 20
Max Error Tol= 0.3
Flow Tol Ratio= 0.001
Split Flow NTrial= 30
Split Flow Tol= 0.02
Split Flow Ratio= 0.02
Log Output Level= 0
Friction Slope Method= 1
Unsteady Friction Slope Method= 2
Unsteady Bridges Friction Slope Method= 1
Parabolic Critical Depth
Global Vel Dist=  1 , 1 , 1
Global Log Level= 0
CheckData=True
Encroach Param= -1, 0, 0, 0
BEGIN DESCRIPTION:
Multiple Run
END DESCRIPTION:

--- UNT027 IN STEL.f01 (steady flow) ---

Flow Title=Multiple
Number of Profiles=7
Profile Names=10-year,25-year,50-year,1pct_min,100-year,1pct_plu,500-year
River Rch & RM= UNT027 IN STEL,Reach-1,9284
     829    1127    1370    1216    1644    2223    2360
Boundary for River Rch & Prof#=UNT027 IN STEL,Reach-1,1
Up Type=0
Dn Type=3
Dn Slope=0.005
Boundary for River Rch & Prof#=UNT027 IN STEL,Reach-1,2
Up Type=0
Dn Type=3
Dn Slope=0.005
Boundary for River Rch & Prof#=UNT027 IN STEL,Reach-1,3
Up Type=0
Dn Type=3
Dn Slope=0.005
Boundary for River Rch & Prof#=UNT027 IN STEL,Reach-1,4
Up Type=0
Dn Type=3
Dn Slope=0.005
Boundary for River Rch & Prof#=UNT027 IN STEL,Reach-1,5
Up Type=0
Dn Type=3
Dn Slope=0.005
Boundary for River Rch & Prof#=UNT027 IN STEL,Reach-1,6
Up Type=0
Dn Type=3
Dn Slope=0.005
Boundary for River Rch & Prof#=UNT027 IN STEL,Reach-1,7
Up Type=0
Dn Type=3
Dn Slope=0.005

--- UNT027 IN STEL.g01 (geometry) ---

Geom Title=Existing Conditions

River Reach=UNT027 IN STEL,Reach-1
Reach XY= 30
      3485138.10     10473390.69      3485048.74     10472732.41
      3484928.97     10472745.67      3484894.31     10472671.95
      3484949.68     10472327.88      3485131.11     10472190.96
      3485220.60     10471995.81      3485152.64     10471716.20
      3485194.61     10471352.59      3485277.38     10471236.74
      3485226.16     10471044.87      3485138.68     10471017.58
      3485236.24     10470879.70      3485917.55     10470811.86
      3486070.65     10470825.23      3486171.92     10470917.73
      3486470.62     10470838.06      3486641.99     10470718.15
      3486750.42     10470839.25      3487046.60     10470682.71
      3487218.22     10470427.09      3487873.69     10469815.48
      3488575.83     10469782.68      3489069.54     10469599.30
      3489526.76     10469342.55      3489749.70     10469065.43
      3490258.60     10468973.20      3490393.01     10469102.33
      3490599.60     10468930.46      3490742.53     10468918.35

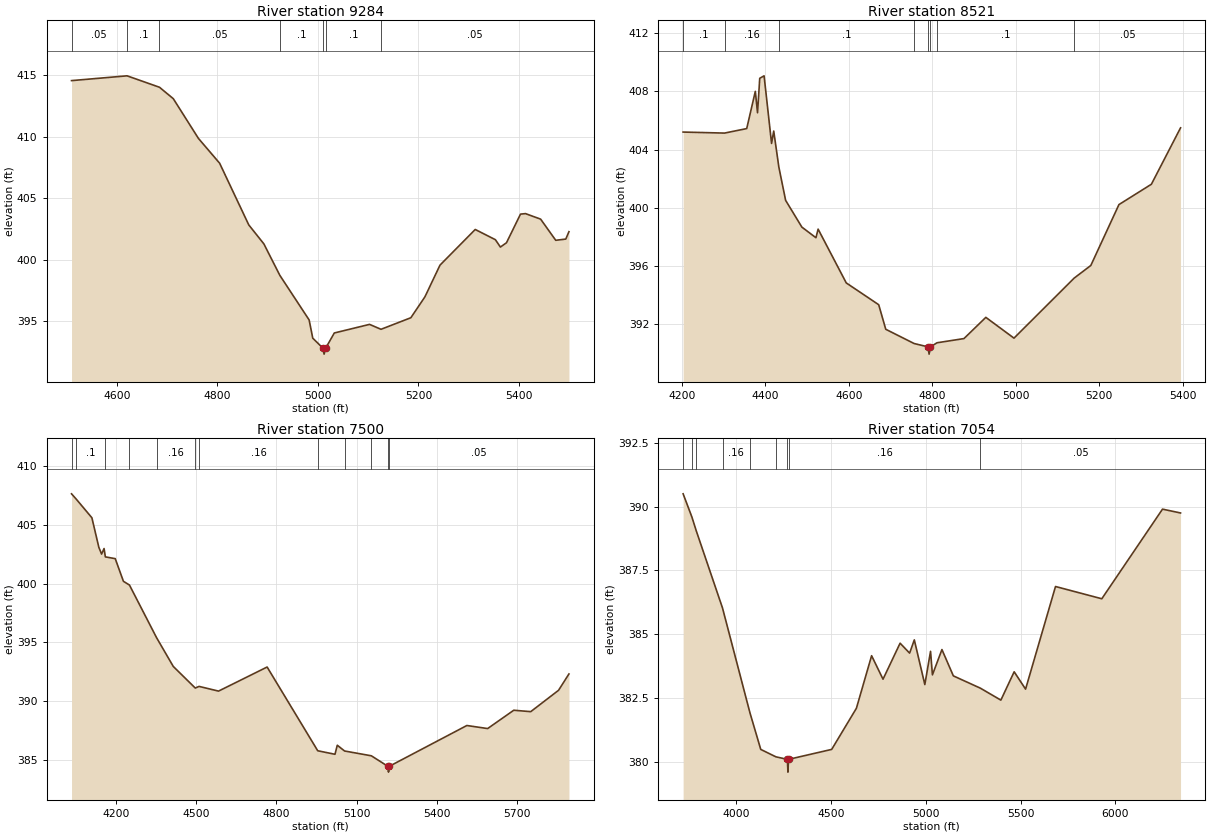
Type RM Length L Ch R = 1,9284,763,763,763
BEGIN DESCRIPTION:
UNT027 IN STEL 8.0
END DESCRIPTION:
XS GIS Cut Line= 2
      3485584.29     10473041.31      3484595.86     10473093.33
#Sta/Elev= 30
  4509.7  414.57  4620.2  414.96  4684.7  414.03  4712.2  413.10  4762.2  409.87
  4804.4  407.85  4862.4  402.83  4892.4  401.29  4924.2  398.73  4982.5  395.10
  4989.7  393.62  5009.6  392.82  5012.3  392.32  5015.6  392.82  5032.6  394.04
  5102.7  394.74  5125.5  394.34  5184.9  395.28  5212.9  396.98  5242.9  399.56
  5313.0  402.46  5353.1  401.63  5363.1  401.03  5375.2  401.38  5403.1  403.71
  5413.1  403.75  5443.2  403.30  5473.2  401.58  5493.2  401.68  5499.5  402.28
#Mann=7,-1,0
  4509.7    0.05       0  4620.2     0.1       0  4684.7    0.05       0
  4924.2     0.1       0  5009.6    0.07       0  5015.6     0.1       0
  5125.5    0.05       0
Bank Sta=5009.6,5015.6
Exp/Cntr=0.3,0.1

Type RM Length L Ch R = 1,8521,1021,1021,1021
BEGIN DESCRIPTION:
UNT027 IN STEL 6.0
END DESCRIPTION:
XS GIS Cut Line= 2
      3485688.47     10472277.41      3484543.67     10472606.97
#Sta/Elev= 30
  4203.2  405.20  4302.4  405.13  4355.5  405.44  4376.1  408.00  4381.4  406.53
  4386.7  408.90  4397.1  409.07  4415.0  404.42  4420.2  405.27  4432.4  402.80
  4448.7  400.50  4487.6  398.66  4521.3  397.93  4526.5  398.52  4593.9  394.82
  4671.6  393.32  4688.5  391.63  4756.4  390.65  4789.6  390.42  4792.3  389.92
  4795.6  390.42  4811.2  390.70  4875.8  390.99  4928.2  392.45  4995.6  391.02
  5139.7  395.15  5179.6  396.02  5247.0  400.21  5324.7  401.61  5394.5  405.49
#Mann=8,-1,0
  4203.2     0.1       0  4302.4    0.16       0  4432.4     0.1       0
  4756.4    0.16       0  4789.6    0.07       0  4795.6    0.16       0
  4811.2     0.1       0  5139.7    0.05       0
Bank Sta=4789.6,4795.6
Exp/Cntr=0.3,0.1

Type RM Length L Ch R = 1,7500,446,446,446
BEGIN DESCRIPTION:
UNT027 IN STEL 4.0
END DESCRIPTION:
XS GIS Cut Line= 4
      3485792.11     10471991.67      3485705.79     10471565.61
      3484646.77     10471704.50      3484579.67     10472054.11
#Sta/Elev= 30
  4035.1  407.66  4053.0  407.20  4111.2  405.62  4137.2  403.10  4147.4  402.53
  4156.7  403.00  4161.5  402.29  4198.4  402.14  4229.0  400.21  4251.6  399.89
  4352.6  395.42  4415.3  392.96  4497.5  391.12  4511.6  391.26  4584.5  390.86
  4766.0  392.91  4955.1  385.78  5019.6  385.48  5028.2  386.25  5055.3  385.76
  5155.5  385.35  5216.9  384.46  5219.6  383.96  5222.9  384.46  5512.4  387.93
  5590.1  387.67  5687.7  389.23  5751.1  389.11  5855.1  390.93  5893.9  392.32
#Mann=12,-1,0
  4035.1    0.05       0  4053.0     0.1       0  4161.5    0.05       0
  4251.6     0.1       0  4352.6    0.16       0  4497.5     0.1       0
  4511.6    0.16       0  4955.1     0.1       0  5055.3    0.16       0
  5155.5    0.05       0  5216.9    0.07       0  5222.9    0.05       0
Bank Sta=5216.9,5222.9
Exp/Cntr=0.3,0.1

Type RM Length L Ch R = 1,7054,0,0,0
BEGIN DESCRIPTION:
UNT027 IN STEL 1.0
END DESCRIPTION:
XS GIS Cut Line= 4
      3486330.78     10471565.59      3486087.74     10471166.31
      3484577.32     10471287.84      3484178.03     10471791.29
#Sta/Elev= 30
  3718.6  390.50  3765.0  389.59  3787.5  389.06  3926.4  386.03  4071.4  381.92
  4128.3  380.49  4207.9  380.20  4268.9  380.10  4271.7  379.60  4274.9  380.10
  4502.7  380.49  4633.1  382.10  4713.4  384.16  4773.6  383.24  4863.8  384.65
  4914.0  384.26  4938.7  384.78  4994.3  383.03  5024.4  384.33  5034.4  383.41
  5084.6  384.40  5144.8  383.37  5287.0  382.89  5395.6  382.42  5465.8  383.53
  5526.0  382.85  5684.0  386.87  5928.3  386.39  6248.7  389.90  6343.9  389.75
#Mann=9,-1,0
  3718.6    0.05       0  3765.0    0.16       0  3787.5    0.05       0
  3926.4    0.16       0  4071.4     0.1       0  4207.9    0.16       0
  4268.9    0.07       0  4274.9    0.16       0  5287.0    0.05       0
Bank Sta=4268.9,4274.9
Exp/Cntr=0.3,0.1

Chan Stop Cuts=-1