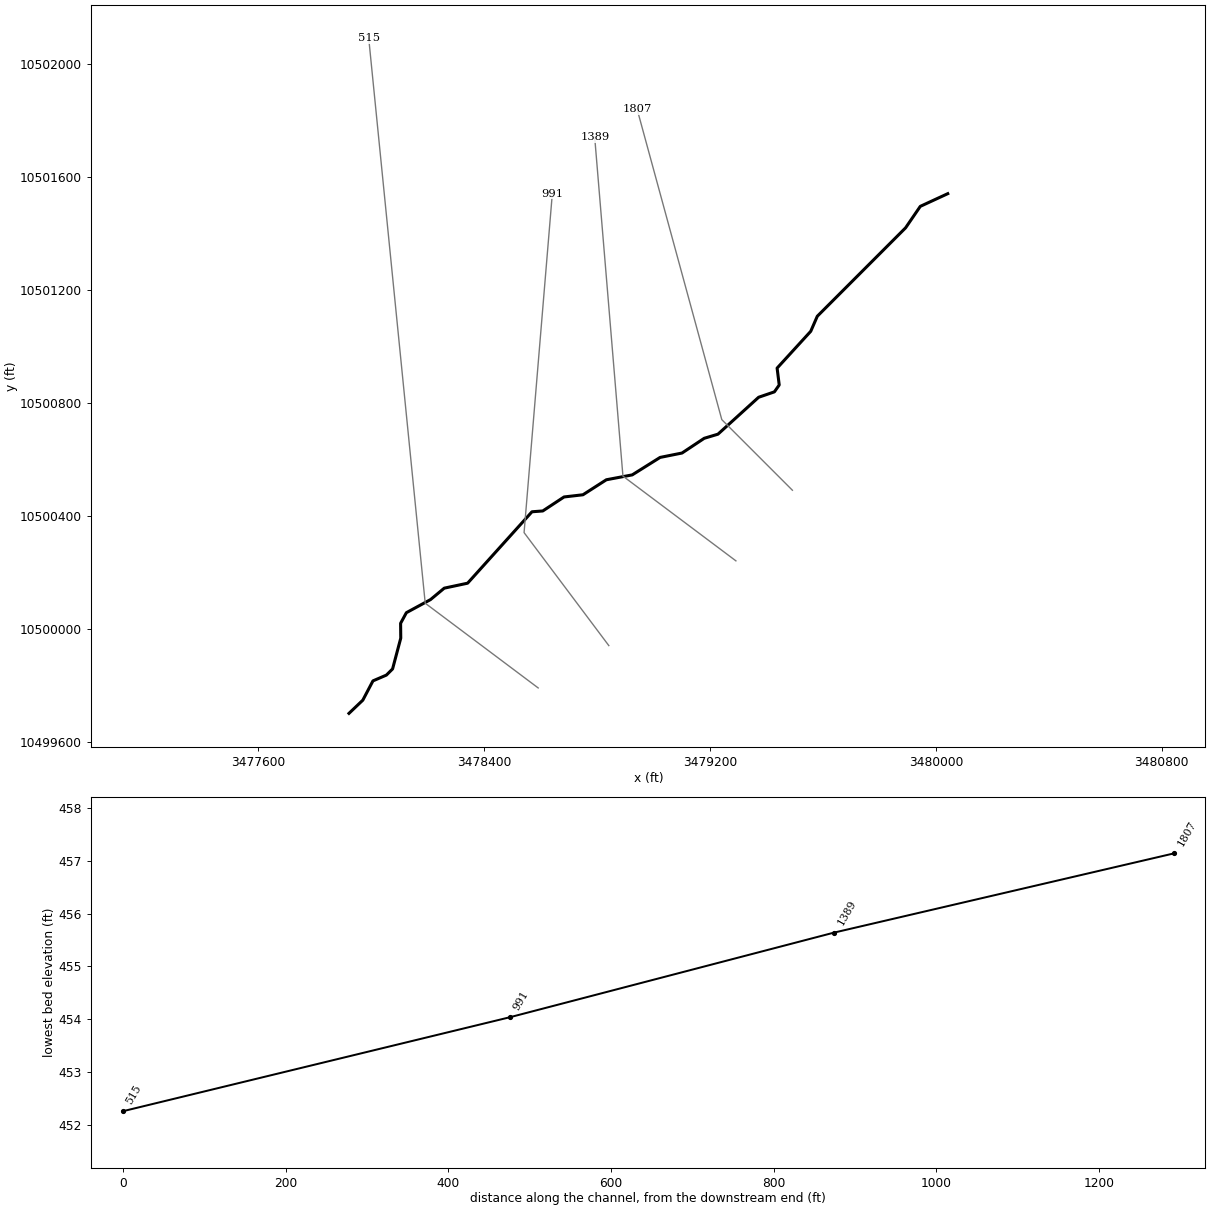
--- UNT032 IN STEL.prj (project) ---

Proj Title=UNT032 IN STEL Base Level Engineering
Current Plan=p01
Default Exp/Contr=0.3,0.1
English Units
Geom File=g01
Flow File=f01
Plan File=p01
BEGIN DESCRIPTION:
UNT032 IN STEL
END DESCRIPTION:

--- UNT032 IN STEL.p01 (plan) ---

Plan Title=Multiple Run
Short Identifier=Multiple
Geom File=g01
Flow File=f01
Subcritical Flow
K Sum by GR= 0
Std Step Tol= 0.01
Critical Tol= 0.01
Num of Std Step Trials= 20
Max Error Tol= 0.3
Flow Tol Ratio= 0.001
Split Flow NTrial= 30
Split Flow Tol= 0.02
Split Flow Ratio= 0.02
Log Output Level= 0
Friction Slope Method= 1
Unsteady Friction Slope Method= 2
Unsteady Bridges Friction Slope Method= 1
Parabolic Critical Depth
Global Vel Dist=  1 , 1 , 1
Global Log Level= 0
CheckData=True
Encroach Param= -1, 0, 0, 0
BEGIN DESCRIPTION:
Multiple Run
END DESCRIPTION:

--- UNT032 IN STEL.f01 (steady flow) ---

Flow Title=Multiple
Number of Profiles=7
Profile Names=10-year,25-year,50-year,1pct_min,100-year,1pct_plu,500-year
River Rch & RM= UNT032 IN STEL,Reach-1,1807
     898    1218    1477    1307    1768    2390    2522
Boundary for River Rch & Prof#=UNT032 IN STEL,Reach-1,1
Up Type=0
Dn Type=3
Dn Slope=0.005
Boundary for River Rch & Prof#=UNT032 IN STEL,Reach-1,2
Up Type=0
Dn Type=3
Dn Slope=0.005
Boundary for River Rch & Prof#=UNT032 IN STEL,Reach-1,3
Up Type=0
Dn Type=3
Dn Slope=0.005
Boundary for River Rch & Prof#=UNT032 IN STEL,Reach-1,4
Up Type=0
Dn Type=3
Dn Slope=0.005
Boundary for River Rch & Prof#=UNT032 IN STEL,Reach-1,5
Up Type=0
Dn Type=3
Dn Slope=0.005
Boundary for River Rch & Prof#=UNT032 IN STEL,Reach-1,6
Up Type=0
Dn Type=3
Dn Slope=0.005
Boundary for River Rch & Prof#=UNT032 IN STEL,Reach-1,7
Up Type=0
Dn Type=3
Dn Slope=0.005

--- UNT032 IN STEL.g01 (geometry) ---

Geom Title=Existing Conditions

River Reach=UNT032 IN STEL,Reach-1
Reach XY= 30
      3480042.11     10501541.64      3479944.89     10501496.71
      3479892.81     10501420.66      3479580.29     10501107.74
      3479557.01     10501054.33      3479437.97     10500924.08
      3479445.44     10500864.32      3479428.35     10500839.97
      3479372.56     10500820.84      3479228.57     10500690.15
      3479179.92     10500675.54      3479101.37     10500623.41
      3479023.68     10500607.83      3478924.95     10500545.97
      3478833.35     10500528.72      3478750.55     10500475.59
      3478683.63     10500467.86      3478608.32     10500418.29
      3478570.07     10500415.43      3478342.20     10500162.56
      3478259.48     10500144.96      3478210.94     10500104.54
      3478125.39     10500058.15      3478104.97     10500020.54
      3478105.50     10499967.96      3478076.55     10499859.02
      3478054.65     10499837.18      3478007.04     10499816.68
      3477971.15     10499748.38      3477922.11     10499701.64

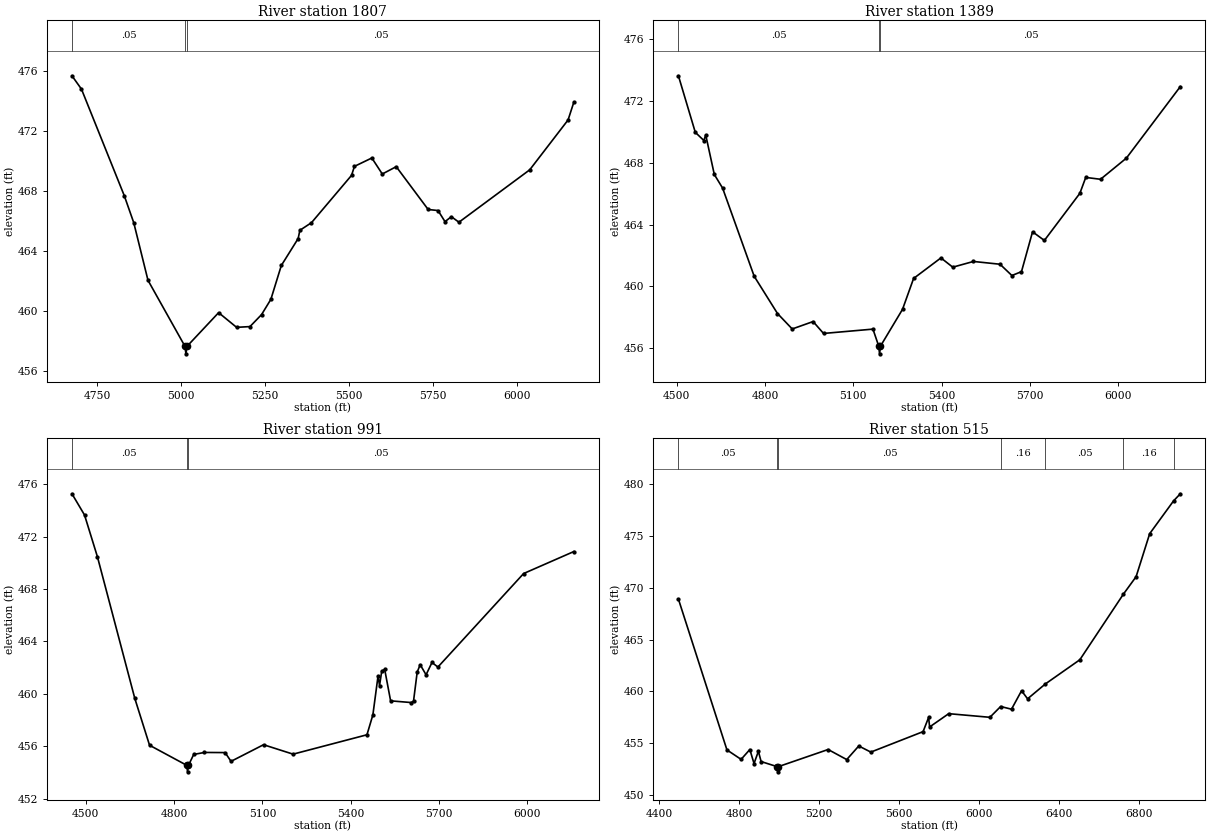
Type RM Length L Ch R = 1,1807,418,418,418
BEGIN DESCRIPTION:
UNT032 IN STEL 4.0
END DESCRIPTION:
XS GIS Cut Line= 3
      3479492.11     10500491.64      3479242.11     10500741.64
      3478942.11     10501841.61
#Sta/Elev= 30
  4675.0  475.71  4703.3  474.82  4830.6  467.71  4858.9  465.90  4901.3  462.05
  5011.4  457.64  5014.2  457.14  5017.4  457.64  5111.5  459.89  5165.0  458.91
  5204.8  458.96  5239.3  459.76  5267.0  460.78  5298.1  463.04  5348.2  464.84
  5353.3  465.39  5387.9  465.90  5507.1  469.06  5515.7  469.66  5567.5  470.22
  5598.6  469.15  5640.1  469.64  5735.1  466.78  5764.5  466.71  5785.2  465.97
  5804.2  466.30  5826.7  465.93  6037.4  469.43  6151.5  472.76  6168.7  473.95
#Mann=3,-1,0
  4675.0    0.05       0  5011.4   0.035       0  5017.4    0.05       0
Bank Sta=5011.4,5017.4
Exp/Cntr=0.3,0.1

Type RM Length L Ch R = 1,1389,398,398,398
BEGIN DESCRIPTION:
UNT032 IN STEL 3.0
END DESCRIPTION:
XS GIS Cut Line= 3
      3479292.09     10500241.65      3478892.11     10500541.64
      3478792.11     10501741.60
#Sta/Elev= 30
  4506.0  473.64  4563.3  469.98  4592.4  469.45  4598.7  469.81  4627.9  467.25
  4656.0  466.37  4763.3  460.66  4842.4  458.25  4892.4  457.25  4963.3  457.73
  4998.7  456.96  5166.5  457.24  5186.1  456.14  5188.9  455.64  5192.1  456.14
  5266.9  458.52  5304.5  460.52  5397.3  461.85  5437.5  461.25  5507.7  461.62
  5598.0  461.44  5638.2  460.71  5670.8  460.96  5708.4  463.54  5748.5  462.98
  5869.0  466.03  5889.0  467.06  5939.2  466.94  6027.0  468.31  6210.1  472.94
#Mann=3,-1,0
  4506.0    0.05       0  5186.1   0.035       0  5192.1    0.05       0
Bank Sta=5186.1,5192.1
Exp/Cntr=0.3,0.1

Type RM Length L Ch R = 1,991,476,476,476
BEGIN DESCRIPTION:
UNT032 IN STEL 2.0
END DESCRIPTION:
XS GIS Cut Line= 3
      3478842.11     10499941.64      3478542.11     10500341.64
      3478642.11     10501541.68
#Sta/Elev= 30
  4453.3  475.27  4496.0  473.65  4539.8  470.46  4666.8  459.64  4716.8  456.07
  4843.0  454.54  4845.8  454.04  4849.0  454.54  4866.8  455.37  4903.3  455.52
  4973.4  455.51  4993.4  454.84  5103.8  456.11  5204.2  455.39  5455.0  456.87
  5475.1  458.39  5492.7  461.37  5497.7  460.63  5505.2  461.73  5515.2  461.86
  5535.3  459.46  5605.6  459.33  5613.1  459.44  5625.6  461.66  5635.7  462.22
  5655.7  461.45  5675.8  462.39  5695.9  462.04  5986.9  469.18  6157.5  470.86
#Mann=3,-1,0
  4453.3    0.05       0  4843.0    0.03       0  4849.0    0.05       0
Bank Sta=4843,4849
Exp/Cntr=0.3,0.1

Type RM Length L Ch R = 1,515,0,0,0
BEGIN DESCRIPTION:
UNT032 IN STEL 1.0
END DESCRIPTION:
XS GIS Cut Line= 3
      3478592.07     10499791.67      3478192.11     10500091.64
      3477992.11     10502091.61
#Sta/Elev= 30
  4496.8  468.89  4739.5  454.37  4810.3  453.46  4854.0  454.41  4874.9  453.06
  4896.8  454.24  4910.3  453.25  4990.6  452.76  4993.4  452.26  4996.6  452.76
  5245.5  454.41  5338.5  453.44  5398.7  454.75  5459.0  454.16  5720.3  456.13
  5748.0  457.50  5753.0  456.58  5848.5  457.86  6054.5  457.51  6108.2  458.55
  6162.5  458.29  6212.8  460.07  6242.9  459.29  6332.4  460.73  6504.2  463.05
  6721.8  469.36  6785.6  471.05  6853.5  475.19  6973.1  478.35  7006.7  479.03
#Mann=7,-1,0
  4496.8    0.05       0  4990.6    0.03       0  4996.6    0.05       0
  6108.2    0.16       0  6332.4    0.05       0  6721.8    0.16       0
  6973.1    0.05       0
Bank Sta=4990.6,4996.6
Exp/Cntr=0.3,0.1

Chan Stop Cuts=-1