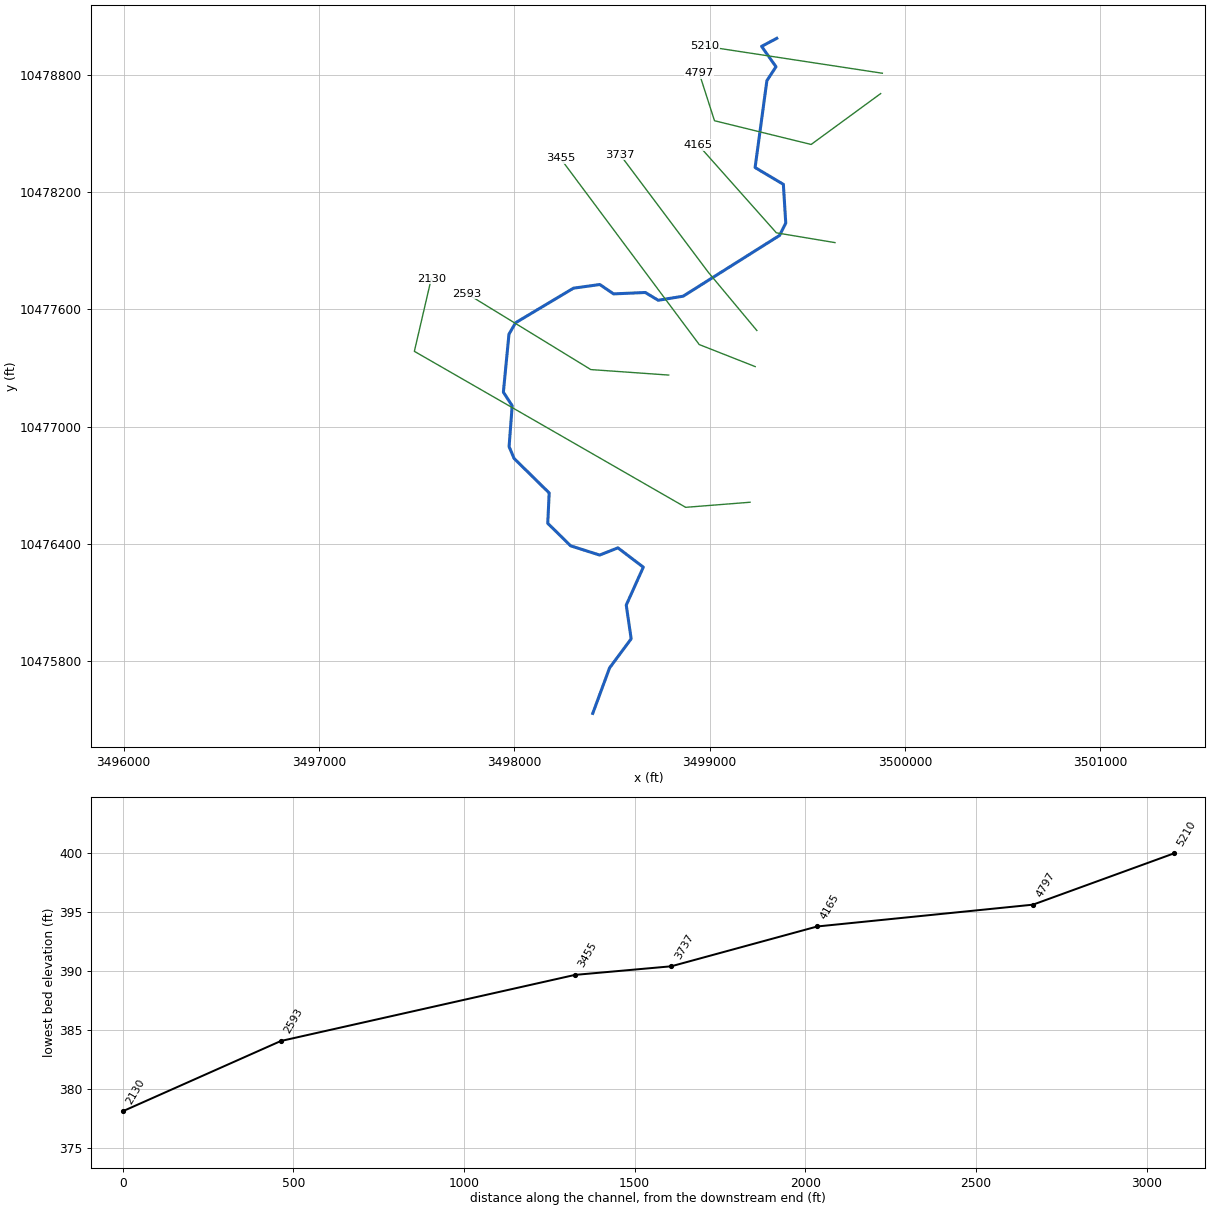
--- UNT036 IN STEL.prj (project) ---

Proj Title=UNT036 IN STEL Base Level Engineering
Current Plan=p01
Default Exp/Contr=0.3,0.1
English Units
Geom File=g01
Flow File=f01
Plan File=p01
BEGIN DESCRIPTION:
UNT036 IN STEL
END DESCRIPTION:

--- UNT036 IN STEL.p01 (plan) ---

Plan Title=Multiple Run
Short Identifier=Multiple
Geom File=g01
Flow File=f01
Subcritical Flow
K Sum by GR= 0
Std Step Tol= 0.01
Critical Tol= 0.01
Num of Std Step Trials= 20
Max Error Tol= 0.3
Flow Tol Ratio= 0.001
Split Flow NTrial= 30
Split Flow Tol= 0.02
Split Flow Ratio= 0.02
Log Output Level= 0
Friction Slope Method= 1
Unsteady Friction Slope Method= 2
Unsteady Bridges Friction Slope Method= 1
Parabolic Critical Depth
Global Vel Dist=  1 , 1 , 1
Global Log Level= 0
CheckData=True
Encroach Param= -1, 0, 0, 0
BEGIN DESCRIPTION:
Multiple Run
END DESCRIPTION:

--- UNT036 IN STEL.f01 (steady flow) ---

Flow Title=Multiple
Number of Profiles=7
Profile Names=10-year,25-year,50-year,1pct_min,100-year,1pct_plu,500-year
River Rch & RM= UNT036 IN STEL,Reach-1,5210
    1184    1654    2049    1851    2503    3385    3726
Boundary for River Rch & Prof#=UNT036 IN STEL,Reach-1,1
Up Type=0
Dn Type=3
Dn Slope=0.005
Boundary for River Rch & Prof#=UNT036 IN STEL,Reach-1,2
Up Type=0
Dn Type=3
Dn Slope=0.005
Boundary for River Rch & Prof#=UNT036 IN STEL,Reach-1,3
Up Type=0
Dn Type=3
Dn Slope=0.005
Boundary for River Rch & Prof#=UNT036 IN STEL,Reach-1,4
Up Type=0
Dn Type=3
Dn Slope=0.005
Boundary for River Rch & Prof#=UNT036 IN STEL,Reach-1,5
Up Type=0
Dn Type=3
Dn Slope=0.005
Boundary for River Rch & Prof#=UNT036 IN STEL,Reach-1,6
Up Type=0
Dn Type=3
Dn Slope=0.005
Boundary for River Rch & Prof#=UNT036 IN STEL,Reach-1,7
Up Type=0
Dn Type=3
Dn Slope=0.005

--- UNT036 IN STEL.g01 (geometry) ---

Geom Title=Existing Conditions

River Reach=UNT036 IN STEL,Reach-1
Reach XY= 30
      3499344.08     10478987.36      3499266.40     10478946.25
      3499340.05     10478841.83      3499293.53     10478770.63
      3499233.15     10478326.02      3499377.83     10478239.83
      3499390.10     10478041.57      3499358.50     10477978.46
      3498864.80     10477667.31      3498737.04     10477646.40
      3498671.22     10477686.23      3498508.68     10477679.11
      3498438.18     10477727.11      3498303.13     10477708.27
      3498007.09     10477531.36      3497973.08     10477472.78
      3497944.51     10477176.03      3497989.55     10477106.31
      3497973.77     10476897.06      3497999.56     10476836.38
      3498178.99     10476660.15      3498171.69     10476504.56
      3498289.07     10476389.27      3498437.40     10476342.09
      3498530.77     10476378.99      3498660.84     10476280.13
      3498573.57     10476086.02      3498598.66     10475913.31
      3498488.04     10475764.13      3498402.11     10475531.64

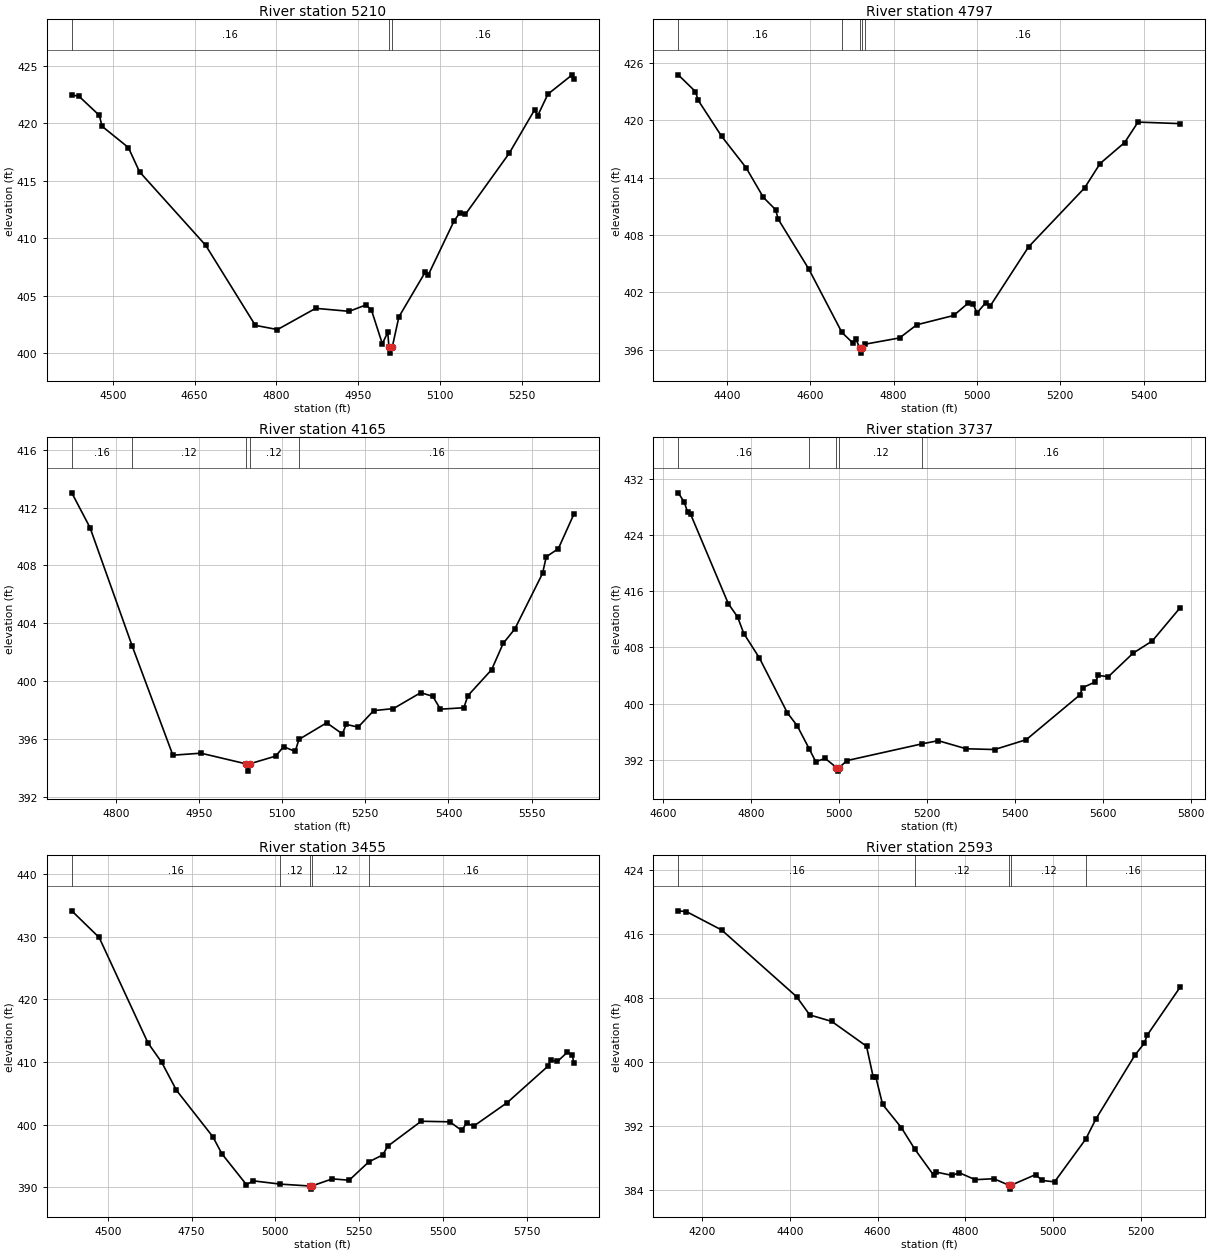
Type RM Length L Ch R = 1,5210,413,413,413
BEGIN DESCRIPTION:
UNT036 IN STEL 9.0
END DESCRIPTION:
XS GIS Cut Line= 2
      3499884.59     10478808.67      3498975.19     10478947.24
#Sta/Elev= 30
  4425.0  422.44  4437.6  422.38  4475.5  420.69  4480.5  419.74  4528.7  417.89
  4549.1  415.78  4670.3  409.38  4761.3  402.41  4801.8  402.04  4871.9  403.89
  4933.3  403.63  4963.6  404.18  4973.8  403.78  4994.0  400.80  5004.0  401.81
  5006.1  400.49  5008.8  399.99  5012.1  400.49  5024.3  403.14  5072.6  407.04
  5077.7  406.75  5125.5  411.50  5135.6  412.19  5146.3  412.08  5226.6  417.40
  5273.3  421.20  5278.4  420.64  5297.4  422.54  5341.9  424.22  5344.9  423.90
#Mann=3,-1,0
  4425.0    0.16       0  5006.1    0.07       0  5012.1    0.16       0
Bank Sta=5006.1,5012.1
Exp/Cntr=0.3,0.1

Type RM Length L Ch R = 1,4797,632,632,632
BEGIN DESCRIPTION:
UNT036 IN STEL 8.0
END DESCRIPTION:
XS GIS Cut Line= 4
      3499875.94     10478704.48      3499520.05     10478444.08
      3499025.26     10478565.61      3498947.47     10478807.63
#Sta/Elev= 30
  4283.4  424.78  4324.8  423.02  4331.0  422.13  4387.4  418.35  4446.1  415.06
  4487.8  411.94  4516.8  410.67  4523.6  409.64  4596.6  404.45  4676.2  397.80
  4703.2  396.67  4709.4  397.15  4719.2  396.14  4722.0  395.64  4725.2  396.14
  4732.1  396.58  4814.4  397.23  4855.9  398.61  4944.2  399.58  4979.7  400.90
  4990.9  400.78  5000.3  399.85  5020.9  400.90  5032.5  400.61  5123.9  406.76
  5258.3  412.93  5295.6  415.49  5354.5  417.69  5386.6  419.83  5488.1  419.67
#Mann=5,-1,0
  4283.4    0.16       0  4676.2    0.07       0  4719.2    0.07       0
  4725.2    0.07       0  4732.1    0.16       0
Bank Sta=4719.2,4725.2
Exp/Cntr=0.3,0.1

Type RM Length L Ch R = 1,4165,428,428,428
BEGIN DESCRIPTION:
UNT036 IN STEL 7.0
END DESCRIPTION:
XS GIS Cut Line= 3
      3499642.08     10477941.65      3499342.11     10477991.64
      3498942.10     10478441.65
#Sta/Elev= 30
  4720.1  413.02  4753.0  410.62  4829.1  402.44  4902.6  394.89  4953.2  395.03
  5035.0  394.29  5037.8  393.79  5041.0  394.29  5088.2  394.83  5102.4  395.48
  5123.3  395.15  5130.1  395.98  5180.2  397.13  5208.6  396.36  5215.3  397.02
  5237.0  396.83  5265.0  397.97  5300.6  398.11  5349.9  399.21  5371.7  398.96
  5385.5  398.07  5427.7  398.17  5435.2  399.01  5477.9  400.80  5498.8  402.62
  5519.7  403.61  5569.8  407.45  5576.5  408.60  5598.3  409.16  5626.3  411.54
#Mann=5,-1,0
  4720.1    0.16       0  4829.1    0.12       0  5035.0    0.07       0
  5041.0    0.12       0  5130.1    0.16       0
Bank Sta=5035,5041
Exp/Cntr=0.3,0.1

Type RM Length L Ch R = 1,3737,282,282,282
BEGIN DESCRIPTION:
UNT036 IN STEL 6.0
END DESCRIPTION:
XS GIS Cut Line= 3
      3499242.08     10477491.67      3498992.11     10477791.64
      3498542.09     10478391.67
#Sta/Elev= 30
  4634.6  429.98  4648.2  428.67  4656.0  427.22  4662.5  426.97  4748.5  414.20
  4769.3  412.35  4783.6  409.97  4818.8  406.52  4882.5  398.70  4904.7  396.87
  4932.4  393.55  4947.0  391.75  4968.4  392.22  4994.1  390.91  4996.8  390.41
  5000.1  390.91  5017.9  391.91  5189.2  394.30  5225.1  394.74  5288.6  393.59
  5353.2  393.48  5425.1  394.88  5546.9  401.24  5553.2  402.28  5582.4  403.10
  5588.6  404.02  5611.5  403.83  5667.8  407.18  5711.5  408.92  5775.1  413.67
#Mann=5,-1,0
  4634.6    0.16       0  4932.4    0.12       0  4994.1    0.07       0
  5000.1    0.12       0  5189.2    0.16       0
Bank Sta=4994.1,5000.1
Exp/Cntr=0.3,0.1

Type RM Length L Ch R = 1,3455,862,862,862
BEGIN DESCRIPTION:
UNT036 IN STEL 5.0
END DESCRIPTION:
XS GIS Cut Line= 3
      3499233.63     10477306.91      3498947.14     10477419.77
      3498236.23     10478373.43
#Sta/Elev= 30
  4392.8  434.13  4474.5  429.87  4620.1  413.03  4661.3  409.91  4705.0  405.47
  4813.5  398.05  4840.6  395.32  4913.6  390.40  4934.4  391.00  5014.7  390.48
  5102.4  390.18  5105.1  389.68  5108.4  390.18  5170.0  391.32  5220.1  391.10
  5278.8  394.04  5320.2  395.14  5334.8  396.52  5434.8  400.52  5520.3  400.43
  5555.8  399.05  5570.4  400.25  5591.2  399.73  5691.3  403.49  5813.1  409.32
  5820.6  410.27  5841.4  410.08  5870.6  411.53  5885.2  411.16  5890.2  409.84
#Mann=5,-1,0
  4392.8    0.16       0  5014.7    0.12       0  5102.4    0.07       0
  5108.4    0.12       0  5278.8    0.16       0
Bank Sta=5102.4,5108.4
Exp/Cntr=0.3,0.1

Type RM Length L Ch R = 1,2593,463,463,463
BEGIN DESCRIPTION:
UNT036 IN STEL 3.0
END DESCRIPTION:
XS GIS Cut Line= 3
      3498790.86     10477263.52      3498392.11     10477291.64
      3497757.91     10477680.18
#Sta/Elev= 30
  4145.9  418.85  4164.7  418.75  4244.9  416.45  4415.3  408.13  4445.4  405.84
  4495.5  405.03  4574.7  401.93  4590.1  398.04  4596.0  398.06  4611.4  394.65
  4654.0  391.76  4684.5  389.08  4727.5  385.82  4733.3  386.20  4770.1  385.78
  4785.5  386.13  4822.2  385.25  4864.8  385.37  4898.6  384.57  4901.3  384.07
  4904.6  384.57  4959.6  385.88  4975.0  385.15  5003.0  384.98  5074.0  390.32
  5097.0  392.82  5185.9  400.80  5207.2  402.29  5214.1  403.32  5289.4  409.34
#Mann=5,-1,0
  4145.9    0.16       0  4684.5    0.12       0  4898.6    0.07       0
  4904.6    0.12       0  5074.0    0.16       0
Bank Sta=4898.6,4904.6
Exp/Cntr=0.3,0.1

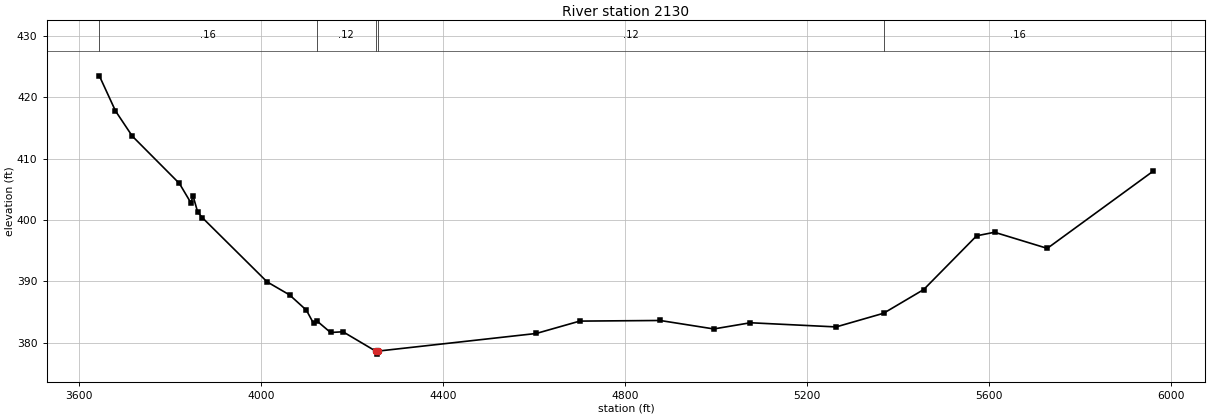
Type RM Length L Ch R = 1,2130,0,0,0
BEGIN DESCRIPTION:
UNT036 IN STEL 1.0
END DESCRIPTION:
XS GIS Cut Line= 4
      3499207.52     10476612.48      3498877.69     10476586.44
      3497488.80     10477385.05      3497575.41     10477757.44
#Sta/Elev= 30
  3644.8  423.53  3680.3  417.80  3717.2  413.69  3820.8  405.96  3845.9  402.82
  3850.9  403.89  3860.9  401.31  3870.9  400.40  4013.6  389.90  4062.8  387.78
  4099.8  385.29  4115.6  383.13  4123.2  383.52  4153.0  381.64  4180.3  381.76
  4252.0  378.61  4254.8  378.11  4258.0  378.61  4605.0  381.48  4700.7  383.50
  4877.4  383.60  4995.3  382.22  5075.8  383.23  5264.1  382.55  5368.5  384.78
  5456.7  388.65  5573.0  397.42  5612.3  398.00  5728.3  395.37  5960.1  407.92
#Mann=5,-1,0
  3644.8    0.16       0  4123.2    0.12       0  4252.0    0.07       0
  4258.0    0.12       0  5368.5    0.16       0
Bank Sta=4252,4258
Exp/Cntr=0.3,0.1

Chan Stop Cuts=-1