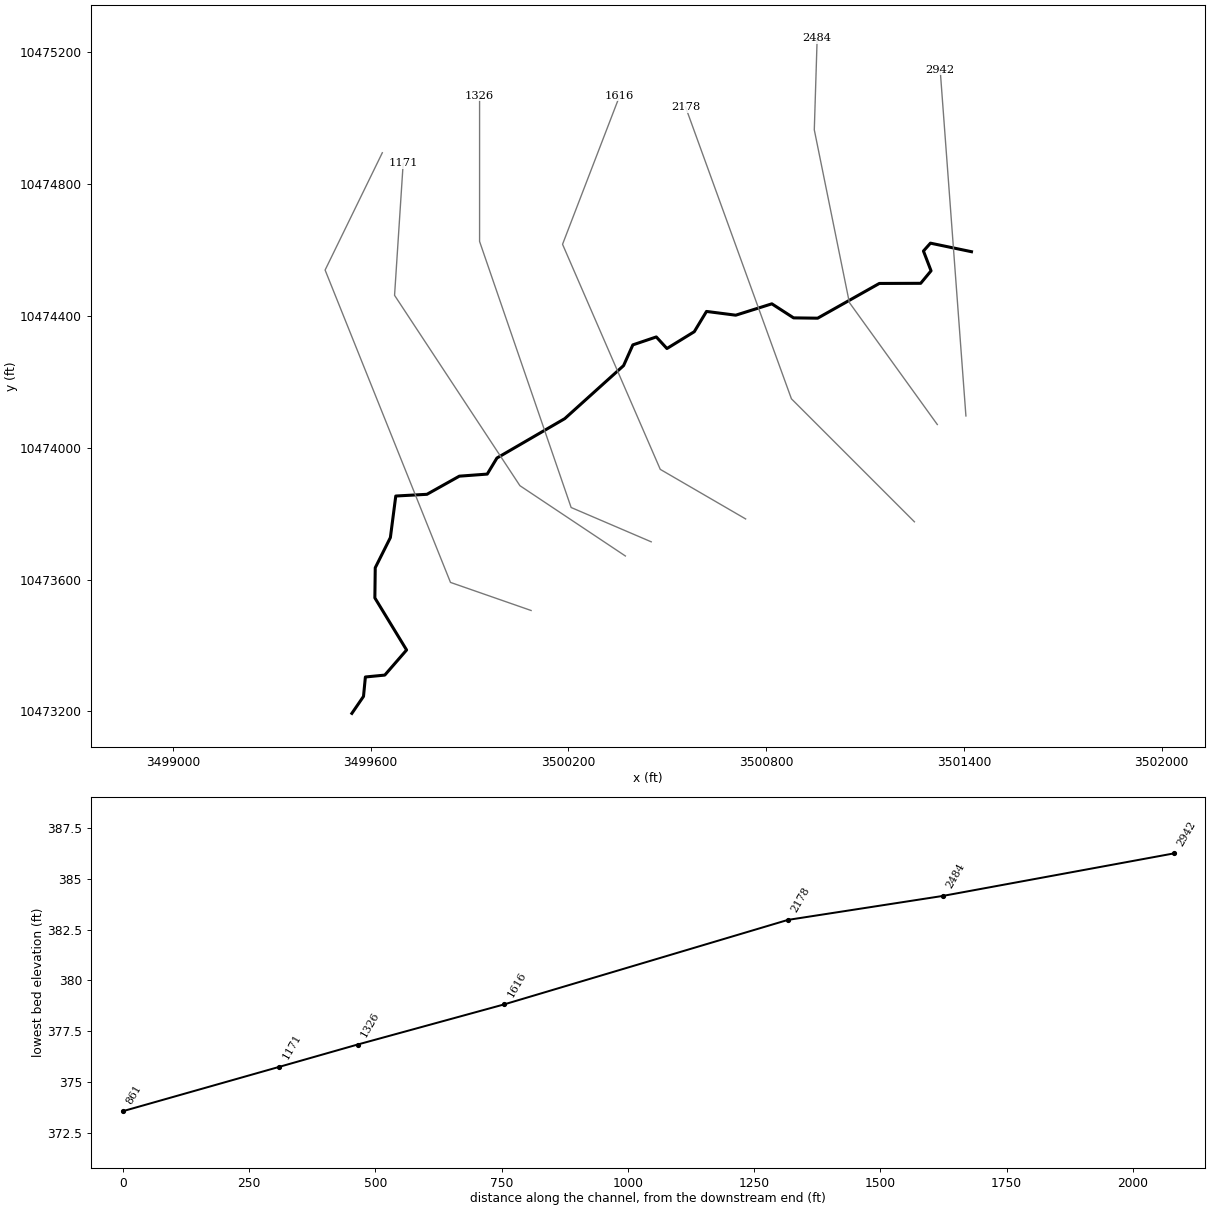
--- UNT037 IN STEL.prj (project) ---

Proj Title=UNT037 IN STEL Base Level Engineering
Current Plan=p01
Default Exp/Contr=0.3,0.1
English Units
Geom File=g01
Flow File=f01
Plan File=p01
BEGIN DESCRIPTION:
UNT037 IN STEL
END DESCRIPTION:

--- UNT037 IN STEL.p01 (plan) ---

Plan Title=Multiple Run
Short Identifier=Multiple
Geom File=g01
Flow File=f01
Subcritical Flow
K Sum by GR= 0
Std Step Tol= 0.01
Critical Tol= 0.01
Num of Std Step Trials= 20
Max Error Tol= 0.3
Flow Tol Ratio= 0.001
Split Flow NTrial= 30
Split Flow Tol= 0.02
Split Flow Ratio= 0.02
Log Output Level= 0
Friction Slope Method= 1
Unsteady Friction Slope Method= 2
Unsteady Bridges Friction Slope Method= 1
Parabolic Critical Depth
Global Vel Dist=  1 , 1 , 1
Global Log Level= 0
CheckData=True
Encroach Param= -1, 0, 0, 0
BEGIN DESCRIPTION:
Multiple Run
END DESCRIPTION:

--- UNT037 IN STEL.f01 (steady flow) ---

Flow Title=Multiple
Number of Profiles=7
Profile Names=10-year,25-year,50-year,1pct_min,100-year,1pct_plu,500-year
River Rch & RM= UNT037 IN STEL,Reach-1,2942
     931    1274    1556    1385    1873    2533    2710
Boundary for River Rch & Prof#=UNT037 IN STEL,Reach-1,1
Up Type=0
Dn Type=3
Dn Slope=0.005
Boundary for River Rch & Prof#=UNT037 IN STEL,Reach-1,2
Up Type=0
Dn Type=3
Dn Slope=0.005
Boundary for River Rch & Prof#=UNT037 IN STEL,Reach-1,3
Up Type=0
Dn Type=3
Dn Slope=0.005
Boundary for River Rch & Prof#=UNT037 IN STEL,Reach-1,4
Up Type=0
Dn Type=3
Dn Slope=0.005
Boundary for River Rch & Prof#=UNT037 IN STEL,Reach-1,5
Up Type=0
Dn Type=3
Dn Slope=0.005
Boundary for River Rch & Prof#=UNT037 IN STEL,Reach-1,6
Up Type=0
Dn Type=3
Dn Slope=0.005
Boundary for River Rch & Prof#=UNT037 IN STEL,Reach-1,7
Up Type=0
Dn Type=3
Dn Slope=0.005

--- UNT037 IN STEL.g01 (geometry) ---

Geom Title=Existing Conditions

River Reach=UNT037 IN STEL,Reach-1
Reach XY= 30
      3501422.99     10474595.09      3501298.51     10474621.03
      3501277.26     10474597.14      3501300.31     10474537.13
      3501268.85     10474499.19      3501143.37     10474498.79
      3500956.24     10474393.37      3500883.20     10474394.32
      3500817.25     10474436.94      3500707.68     10474402.46
      3500618.96     10474413.85      3500581.86     10474352.36
      3500498.90     10474301.32      3500466.63     10474336.46
      3500395.51     10474312.40      3500367.36     10474249.49
      3500188.82     10474088.55      3499983.05     10473969.02
      3499953.62     10473920.31      3499868.94     10473913.99
      3499770.69     10473858.96      3499676.11     10473853.76
      3499659.72     10473727.64      3499613.82     10473636.08
      3499612.65     10473544.60      3499708.91     10473386.56
      3499642.82     10473310.41      3499583.91     10473304.66
      3499578.17     10473245.75      3499542.90     10473194.24

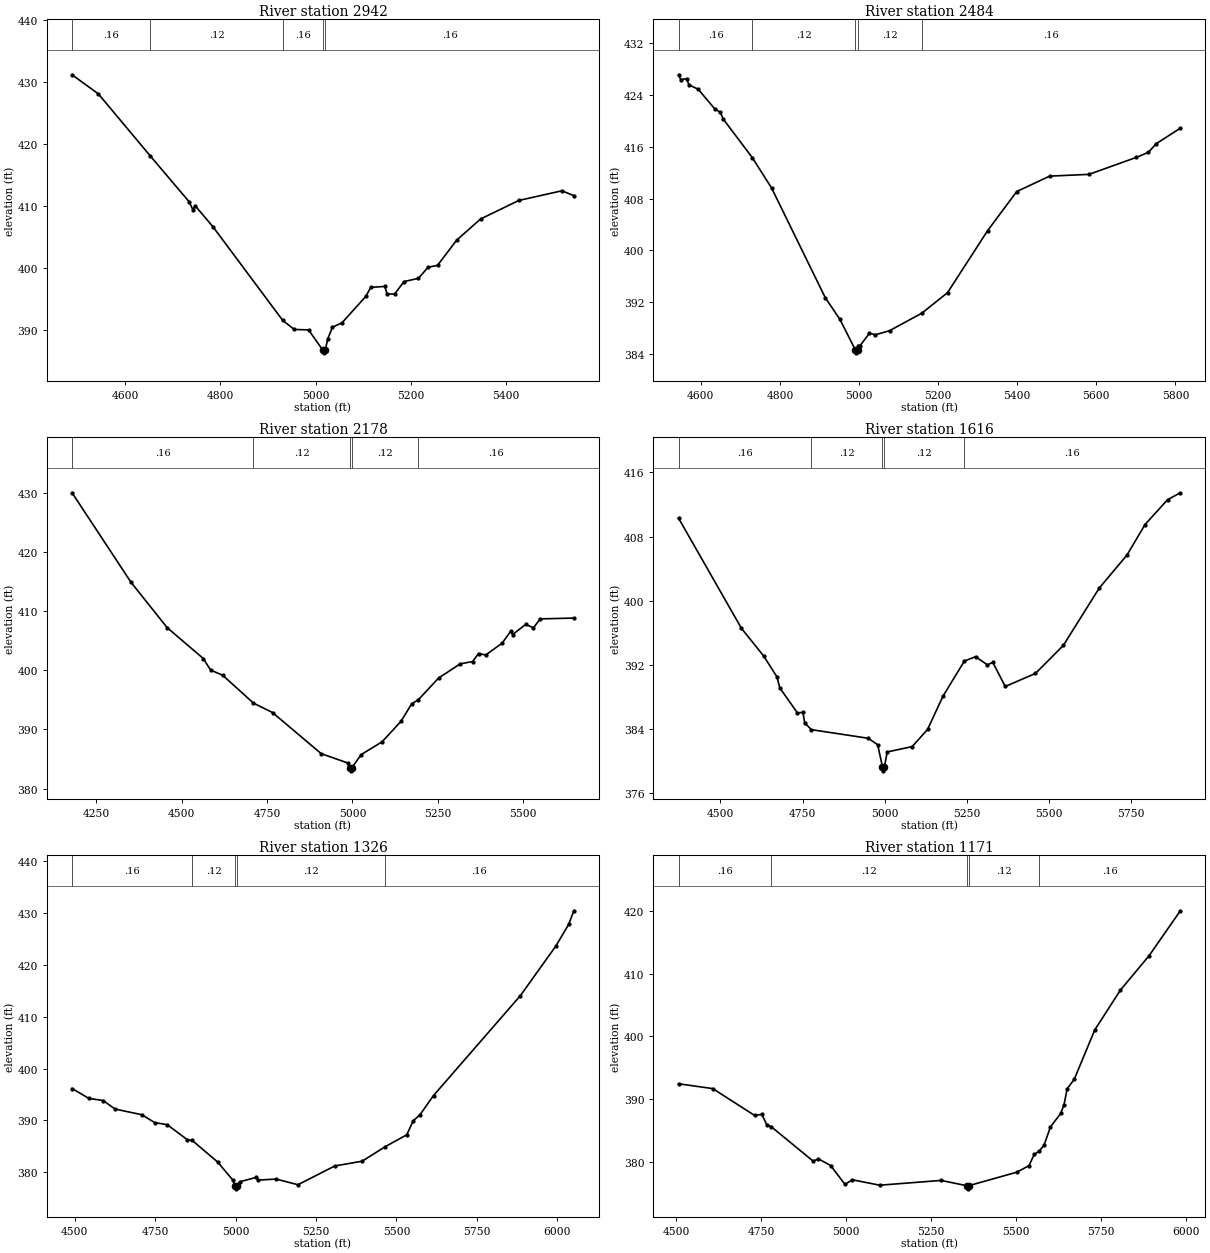
Type RM Length L Ch R = 1,2942,458,458,458
BEGIN DESCRIPTION:
UNT037 IN STEL 6.0
END DESCRIPTION:
XS GIS Cut Line= 2
      3501406.11     10474096.72      3501328.00     10475146.82
#Sta/Elev= 30
  4488.8  431.16  4543.9  428.08  4653.2  418.03  4734.4  410.67  4742.2  409.39
  4747.2  410.01  4784.5  406.62  4930.7  391.52  4955.0  390.04  4985.1  389.98
  5014.4  386.77  5017.1  386.27  5020.4  386.77  5025.2  388.49  5035.2  390.41
  5055.3  391.12  5105.4  395.40  5115.5  396.84  5145.0  396.99  5150.0  395.77
  5165.6  395.77  5185.6  397.78  5215.7  398.30  5235.8  400.08  5255.8  400.40
  5295.9  404.47  5346.1  407.88  5426.3  410.87  5516.6  412.43  5541.8  411.65
#Mann=5,-1,0
  4488.8    0.16       0  4653.2    0.12       0  4930.7    0.16       0
  5014.4    0.07       0  5020.4    0.16       0
Bank Sta=5014.4,5020.4
Exp/Cntr=0.3,0.1

Type RM Length L Ch R = 1,2484,306,306,306
BEGIN DESCRIPTION:
UNT037 IN STEL 5.0
END DESCRIPTION:
XS GIS Cut Line= 4
      3501319.28     10474070.72      3501052.43     10474440.86
      3500946.04     10474964.78      3500954.72     10475242.53
#Sta/Elev= 30
  4543.7  427.11  4549.2  426.36  4563.9  426.51  4570.1  425.55  4593.4  424.88
  4635.1  421.86  4649.8  421.29  4656.0  420.33  4730.4  414.30  4779.1  409.61
  4914.7  392.69  4951.7  389.34  4990.4  384.67  4993.2  384.17  4996.4  384.67
  4997.4  385.30  5003.0  385.30  5026.5  387.20  5041.6  386.96  5077.2  387.59
  5159.1  390.30  5224.0  393.47  5325.2  403.04  5398.8  409.08  5482.2  411.46
  5581.5  411.73  5701.6  414.36  5731.6  415.13  5751.6  416.47  5812.5  418.86
#Mann=5,-1,0
  4543.7    0.16       0  4730.4    0.12       0  4990.4    0.07       0
  4996.4    0.12       0  5159.1    0.16       0
Bank Sta=4990.4,4996.4
Exp/Cntr=0.3,0.1

Type RM Length L Ch R = 1,2178,562,562,562
BEGIN DESCRIPTION:
UNT037 IN STEL 4.0
END DESCRIPTION:
XS GIS Cut Line= 3
      3501249.83     10473775.57      3500876.59     10474148.81
      3500555.41     10475034.22
#Sta/Elev= 30
  4178.7  430.02  4351.1  414.90  4457.2  407.21  4563.2  401.98  4584.4  400.03
  4619.8  399.16  4709.9  394.45  4765.9  392.85  4908.3  385.90  4986.1  384.32
  4991.9  383.49  4994.6  382.99  4997.9  383.49  5025.5  385.74  5086.7  387.90
  5142.6  391.40  5173.3  394.32  5193.2  395.03  5252.1  398.68  5315.7  401.09
  5351.7  401.47  5369.1  402.82  5390.4  402.59  5438.2  404.58  5463.5  406.61
  5468.8  406.03  5507.4  407.76  5530.0  407.18  5549.9  408.69  5648.4  408.83
#Mann=5,-1,0
  4178.7    0.16       0  4709.9    0.12       0  4991.9    0.07       0
  4997.9    0.12       0  5193.2    0.16       0
Bank Sta=4991.9,4997.9
Exp/Cntr=0.3,0.1

Type RM Length L Ch R = 1,1616,290,290,290
BEGIN DESCRIPTION:
UNT037 IN STEL 3.0
END DESCRIPTION:
XS GIS Cut Line= 4
      3500737.67     10473784.25      3500478.69     10473934.63
      3500182.15     10474617.56      3500355.32     10475067.80
#Sta/Elev= 30
  4372.9  410.31  4564.4  396.57  4632.3  393.11  4672.4  390.52  4680.9  389.16
  4734.5  386.04  4751.3  386.10  4756.7  384.78  4777.3  383.95  4949.8  382.88
  4978.7  382.07  4993.2  379.32  4995.9  378.82  4999.2  379.32  5007.6  381.17
  5083.5  381.84  5130.4  383.98  5177.3  388.12  5242.4  392.50  5276.5  393.05
  5312.3  392.03  5328.9  392.33  5366.8  389.33  5458.7  390.96  5543.3  394.44
  5652.6  401.59  5737.2  405.72  5791.9  409.51  5860.6  412.61  5899.3  413.47
#Mann=5,-1,0
  4372.9    0.16       0  4777.3    0.12       0  4993.2    0.07       0
  4999.2    0.12       0  5242.4    0.16       0
Bank Sta=4993.2,4999.2
Exp/Cntr=0.3,0.1

Type RM Length L Ch R = 1,1326,155,155,155
BEGIN DESCRIPTION:
UNT037 IN STEL 2.0
END DESCRIPTION:
XS GIS Cut Line= 4
      3500451.20     10473714.80      3500208.19     10473818.95
      3499930.41     10474626.24      3499930.41     10475067.81
#Sta/Elev= 30
  4491.7  396.15  4543.4  394.26  4588.6  393.83  4625.0  392.20  4708.3  391.11
  4748.3  389.60  4787.8  389.18  4850.2  386.28  4865.3  386.15  4943.9  382.02
  4991.6  378.51  4998.1  377.34  5000.8  376.84  5004.1  377.34  5012.7  378.19
  5063.6  379.04  5068.8  378.52  5126.0  378.72  5193.8  377.63  5308.1  381.24
  5393.5  382.16  5464.3  384.93  5532.0  387.24  5552.1  389.93  5573.2  391.11
  5615.2  394.80  5885.2  414.03  5995.2  423.55  6035.2  427.73  6051.4  430.36
#Mann=5,-1,0
  4491.7    0.16       0  4865.3    0.12       0  4998.1    0.07       0
  5004.1    0.12       0  5464.3    0.16       0
Bank Sta=4998.1,5004.1
Exp/Cntr=0.3,0.1

Type RM Length L Ch R = 1,1171,310,310,310
BEGIN DESCRIPTION:
Mapping XS 4eac7e01
END DESCRIPTION:
XS GIS Cut Line= 4
      3500372.79     10473671.80      3500052.79     10473885.13
      3499672.42     10474462.73      3499698.58     10474863.20
#Sta/Elev= 30
  4507.0  392.47  4607.9  391.70  4731.1  387.42  4752.1  387.60  4767.2  385.92
  4779.6  385.65  4903.6  380.14  4918.7  380.52  4954.9  379.45  4997.0  376.46
  5019.1  377.18  5099.4  376.32  5280.1  377.08  5355.4  376.24  5358.2  375.74
  5361.4  376.24  5503.0  378.39  5539.1  379.44  5554.2  381.21  5567.8  381.70
  5583.2  382.67  5602.1  385.61  5632.2  387.74  5642.2  389.15  5651.1  391.65
  5672.3  393.20  5732.4  401.03  5808.0  407.38  5892.7  412.88  5984.5  420.02
#Mann=5,-1,0
  4507.0    0.16       0  4779.6    0.12       0  5355.4    0.07       0
  5361.4    0.12       0  5567.8    0.16       0
Bank Sta=5355.4,5361.4
Exp/Cntr=0.3,0.1

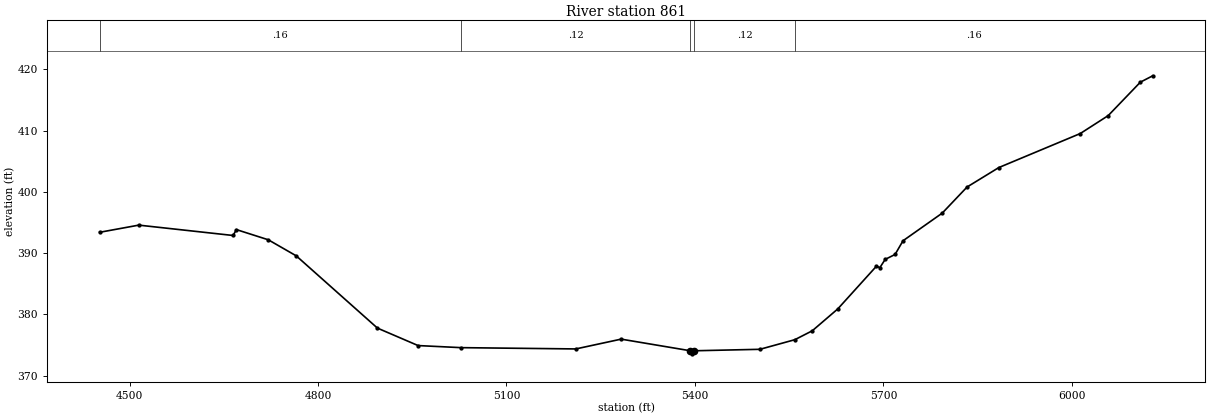
Type RM Length L Ch R = 1,861,0,0,0
BEGIN DESCRIPTION:
UNT037 IN STEL 1.0
END DESCRIPTION:
XS GIS Cut Line= 4
      3500086.70     10473506.43      3499842.11     10473591.64
      3499461.66     10474539.43      3499635.27     10474895.34
#Sta/Elev= 30
  4452.4  393.39  4514.7  394.56  4664.8  392.87  4670.1  393.83  4720.8  392.17
  4765.3  389.55  4894.6  377.75  4959.3  374.90  5027.9  374.56  5210.3  374.35
  5282.5  375.95  5392.8  374.05  5395.6  373.55  5398.8  374.05  5503.4  374.29
  5559.0  375.86  5586.7  377.31  5627.3  380.88  5688.9  387.86  5694.3  387.62
  5702.8  388.97  5718.5  389.77  5731.2  392.01  5793.6  396.52  5833.1  400.78
  5883.7  403.96  6013.3  409.51  6057.8  412.44  6109.0  417.90  6128.7  418.94
#Mann=5,-1,0
  4452.4    0.16       0  5027.9    0.12       0  5392.8    0.07       0
  5398.8    0.12       0  5559.0    0.16       0
Bank Sta=5392.8,5398.8
Exp/Cntr=0.3,0.1

Chan Stop Cuts=-1