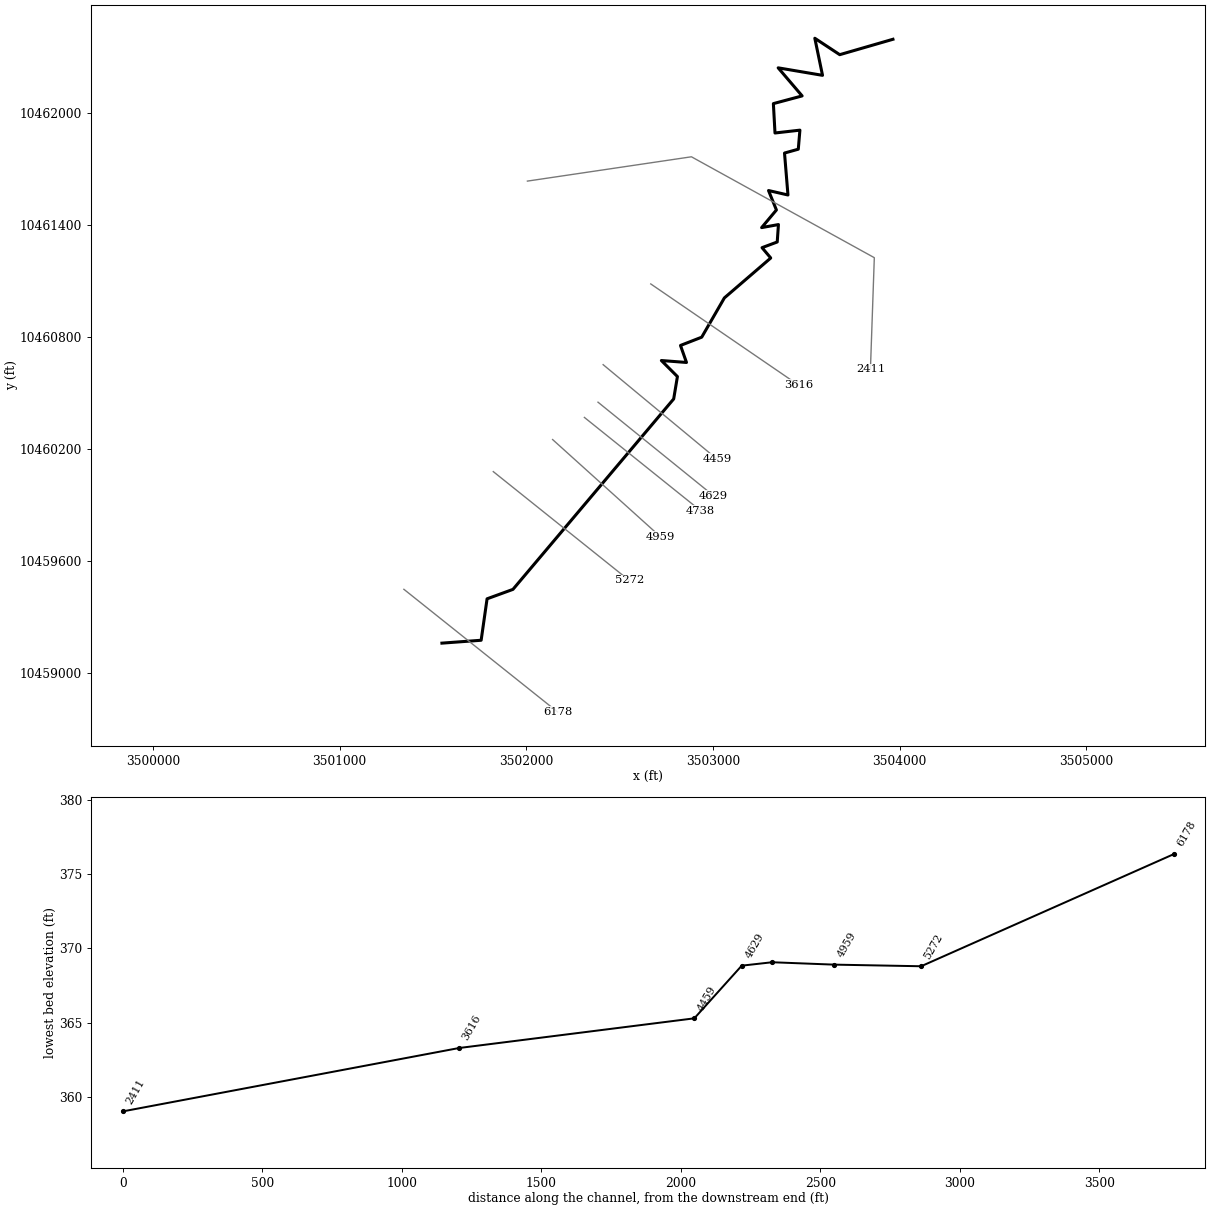
--- UNT038 IN STEL.prj (project) ---

Proj Title=UNT038 IN STEL Base Level Engineering
Current Plan=p01
Default Exp/Contr=0.3,0.1
English Units
Geom File=g01
Flow File=f01
Plan File=p01
BEGIN DESCRIPTION:
UNT038 IN STEL
END DESCRIPTION:

--- UNT038 IN STEL.p01 (plan) ---

Plan Title=Multiple Run
Short Identifier=Multiple
Geom File=g01
Flow File=f01
Subcritical Flow
K Sum by GR= 0
Std Step Tol= 0.01
Critical Tol= 0.01
Num of Std Step Trials= 20
Max Error Tol= 0.3
Flow Tol Ratio= 0.001
Split Flow NTrial= 30
Split Flow Tol= 0.02
Split Flow Ratio= 0.02
Log Output Level= 0
Friction Slope Method= 1
Unsteady Friction Slope Method= 2
Unsteady Bridges Friction Slope Method= 1
Parabolic Critical Depth
Global Vel Dist=  1 , 1 , 1
Global Log Level= 0
CheckData=True
Encroach Param= -1, 0, 0, 0
BEGIN DESCRIPTION:
Multiple Run
END DESCRIPTION:

--- UNT038 IN STEL.f01 (steady flow) ---

Flow Title=Multiple
Number of Profiles=7
Profile Names=10-year,25-year,50-year,1pct_min,100-year,1pct_plu,500-year
River Rch & RM= UNT038 IN STEL,Reach-1,6178
     626     845    1022     905    1224    1655    1747
River Rch & RM= UNT038 IN STEL,Reach-1,4629
    1505    2131    2662    2424    3278    4433    4960
Boundary for River Rch & Prof#=UNT038 IN STEL,Reach-1,1
Up Type=0
Dn Type=3
Dn Slope=0.005
Boundary for River Rch & Prof#=UNT038 IN STEL,Reach-1,2
Up Type=0
Dn Type=3
Dn Slope=0.005
Boundary for River Rch & Prof#=UNT038 IN STEL,Reach-1,3
Up Type=0
Dn Type=3
Dn Slope=0.005
Boundary for River Rch & Prof#=UNT038 IN STEL,Reach-1,4
Up Type=0
Dn Type=3
Dn Slope=0.005
Boundary for River Rch & Prof#=UNT038 IN STEL,Reach-1,5
Up Type=0
Dn Type=3
Dn Slope=0.005
Boundary for River Rch & Prof#=UNT038 IN STEL,Reach-1,6
Up Type=0
Dn Type=3
Dn Slope=0.005
Boundary for River Rch & Prof#=UNT038 IN STEL,Reach-1,7
Up Type=0
Dn Type=3
Dn Slope=0.005

--- UNT038 IN STEL.g01 (geometry) ---

Geom Title=Existing Conditions

River Reach=UNT038 IN STEL,Reach-1
Reach XY= 30
      3501547.89     10459160.25      3501758.09     10459175.70
      3501789.86     10459397.63      3501928.56     10459448.20
      3502789.86     10460468.12      3502809.83     10460587.92
      3502723.89     10460673.85      3502858.44     10460663.44
      3502826.32     10460754.58      3502940.03     10460798.85
      3503061.48     10461009.18      3503309.96     10461222.94
      3503263.30     10461278.28      3503344.68     10461308.66
      3503351.19     10461401.98      3503261.13     10461385.70
      3503340.34     10461480.10      3503298.02     10461584.27
      3503402.19     10461560.40      3503383.74     10461785.01
      3503457.53     10461805.62      3503466.21     10461907.62
      3503332.74     10461892.43      3503324.06     10462049.76
      3503478.14     10462091.00      3503349.76     10462241.34
      3503587.39     10462201.20      3503546.15     10462399.76
      3503679.62     10462311.87      3503964.77     10462394.34

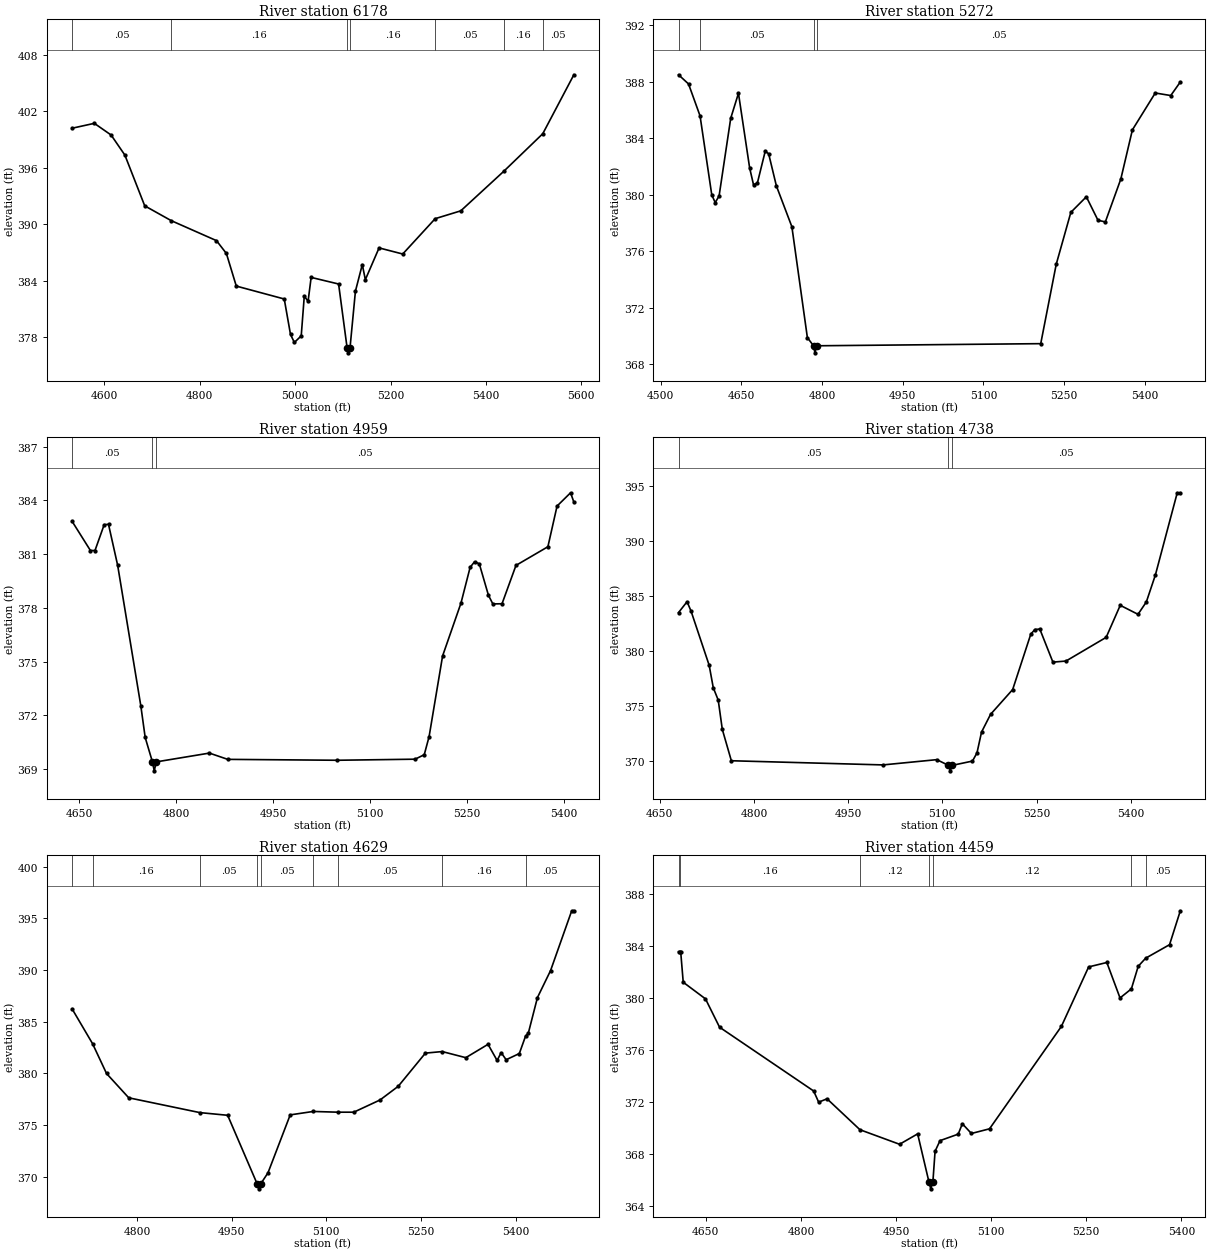
Type RM Length L Ch R = 1,6178,906,906,906
BEGIN DESCRIPTION:
UNT038 IN STEL 12.0
END DESCRIPTION:
XS GIS Cut Line= 2
      3501344.10     10459448.57      3502167.06     10458792.29
#Sta/Elev= 30
  4532.0  400.18  4578.7  400.70  4613.9  399.46  4642.8  397.33  4684.4  391.95
  4740.0  390.38  4834.9  388.26  4855.7  386.90  4876.5  383.44  4977.1  382.07
  4990.2  378.31  4998.3  377.46  5012.7  378.16  5019.1  382.37  5027.1  381.83
  5033.5  384.36  5091.1  383.66  5109.0  376.86  5111.7  376.36  5115.0  376.86
  5126.4  382.90  5140.8  385.72  5147.2  384.12  5176.0  387.49  5225.6  386.84
  5293.7  390.59  5347.4  391.42  5437.5  395.61  5519.4  399.60  5584.6  405.85
#Mann=7,-1,0
  4532.0    0.05       0  4740.0    0.16       0  5109.0    0.07       0
  5115.0    0.16       0  5293.7    0.05       0  5437.5    0.16       0
  5519.4    0.05       0
Bank Sta=5109,5115
Exp/Cntr=0.3,0.1

Type RM Length L Ch R = 1,5272,313,313,313
BEGIN DESCRIPTION:
UNT038 IN STEL 10.0
END DESCRIPTION:
XS GIS Cut Line= 2
      3501823.26     10460078.79      3502551.65     10459496.07
#Sta/Elev= 30
  4533.3  388.49  4551.9  387.84  4573.3  385.58  4595.1  379.98  4601.5  379.44
  4608.7  379.91  4630.3  385.41  4644.7  387.18  4665.5  381.89  4672.7  380.70
  4679.9  380.83  4694.4  383.07  4700.8  382.90  4715.2  380.62  4744.0  377.73
  4772.8  369.88  4784.2  369.30  4786.9  368.80  4790.2  369.30  5206.6  369.45
  5235.4  375.07  5262.6  378.75  5291.4  379.85  5313.0  378.19  5326.7  378.07
  5355.5  381.11  5377.0  384.59  5419.5  387.20  5448.3  387.02  5466.1  387.98
#Mann=4,-1,0
  4533.3    0.16       0  4573.3    0.05       0  4784.2   0.033       0
  4790.2    0.05       0
Bank Sta=4784.2,4790.2
Exp/Cntr=0.3,0.1

Type RM Length L Ch R = 1,4959,221,221,221
BEGIN DESCRIPTION:
UNT038 IN STEL 9.0
END DESCRIPTION:
XS GIS Cut Line= 2
      3502140.98     10460250.65      3502718.11     10459730.71
#Sta/Elev= 30
  4638.8  382.83  4667.2  381.20  4674.3  381.20  4688.5  382.64  4695.2  382.66
  4709.4  380.37  4745.3  372.52  4752.0  370.77  4763.2  369.41  4766.0  368.91
  4769.2  369.41  4851.4  369.90  4879.8  369.55  5049.5  369.50  5169.8  369.56
  5184.0  369.81  5191.5  370.82  5212.4  375.32  5240.8  378.26  5255.0  380.26
  5261.8  380.57  5269.2  380.46  5283.4  378.70  5290.2  378.22  5304.4  378.23
  5326.0  380.37  5375.4  381.41  5389.6  383.68  5410.5  384.42  5415.6  383.90
#Mann=3,-1,0
  4638.8    0.05       0  4763.2   0.033       0  4769.2    0.05       0
Bank Sta=4763.2,4769.2
Exp/Cntr=0.3,0.1

Type RM Length L Ch R = 1,4738,109,109,109
BEGIN DESCRIPTION:
Mapping XS 199c6956
END DESCRIPTION:
XS GIS Cut Line= 2
      3502311.37     10460369.10      3502934.68     10459869.06
#Sta/Elev= 30
  4679.9  383.50  4693.5  384.49  4699.9  383.62  4728.7  378.69  4735.2  376.65
  4743.1  375.52  4749.6  372.85  4764.0  369.99  5005.6  369.61  5091.1  370.09
  5109.8  369.57  5112.6  369.07  5115.8  369.57  5148.0  369.96  5155.2  370.71
  5162.4  372.60  5176.8  374.22  5212.0  376.48  5240.8  381.52  5247.2  381.95
  5255.2  382.00  5276.1  378.98  5296.9  379.08  5360.9  381.24  5383.3  384.16
  5411.6  383.34  5424.9  384.47  5439.3  386.93  5474.1  394.42  5479.0  394.42
#Mann=3,-1,0
  4679.9    0.05       0  5109.8    0.03       0  5115.8    0.05       0
Bank Sta=5109.8,5115.8
Exp/Cntr=0.3,0.1

Type RM Length L Ch R = 1,4629,170,170,170
BEGIN DESCRIPTION:
Mapping XS d21044ab
END DESCRIPTION:
XS GIS Cut Line= 2
      3502384.28     10460450.70      3503002.35     10459950.69
#Sta/Elev= 30
  4697.3  386.24  4729.7  382.88  4751.9  379.99  4787.1  377.64  4899.7  376.21
  4943.8  375.95  4990.4  369.34  4993.1  368.84  4996.4  369.34  5007.7  370.39
  5042.9  375.99  5079.3  376.32  5118.2  376.25  5143.6  376.25  5185.2  377.43
  5214.0  378.75  5257.1  381.96  5283.7  382.11  5321.1  381.52  5356.3  382.81
  5370.7  381.25  5377.1  382.01  5385.0  381.32  5405.9  381.92  5415.7  383.59
  5420.2  383.90  5434.6  387.33  5455.4  389.94  5488.9  395.72  5492.3  395.72
#Mann=9,-1,0
  4697.3    0.05       0  4729.7    0.16       0  4899.7    0.05       0
  4990.4    0.03       0  4996.4    0.05       0  5079.3    0.12       0
  5118.2    0.05       0  5283.7    0.16       0  5415.7    0.05       0
Bank Sta=4990.4,4996.4
Exp/Cntr=0.3,0.1

Type RM Length L Ch R = 1,4459,843,843,843
BEGIN DESCRIPTION:
UNT038 IN STEL 8.0
END DESCRIPTION:
XS GIS Cut Line= 2
      3502411.82     10460651.69      3503021.07     10460146.58
#Sta/Elev= 30
  4606.9  383.54  4608.9  383.54  4610.3  383.54  4614.3  381.19  4649.4  379.91
  4671.6  377.73  4820.0  372.82  4827.9  371.96  4841.1  372.22  4893.0  369.84
  4955.5  368.72  4984.0  369.52  5002.0  365.79  5004.7  365.29  5008.0  365.79
  5011.5  368.18  5019.3  369.00  5048.0  369.50  5054.5  370.30  5068.8  369.55
  5097.4  369.91  5210.7  377.79  5253.7  382.37  5282.4  382.71  5303.2  379.98
  5321.1  380.68  5331.9  382.42  5343.6  383.04  5381.3  384.08  5398.3  386.69
#Mann=7,-1,0
  4606.9    0.05       0  4608.9    0.16       0  4893.0    0.12       0
  5002.0    0.07       0  5008.0    0.12       0  5321.1    0.16       0
  5343.6    0.05       0
Bank Sta=5002,5008
Exp/Cntr=0.3,0.1

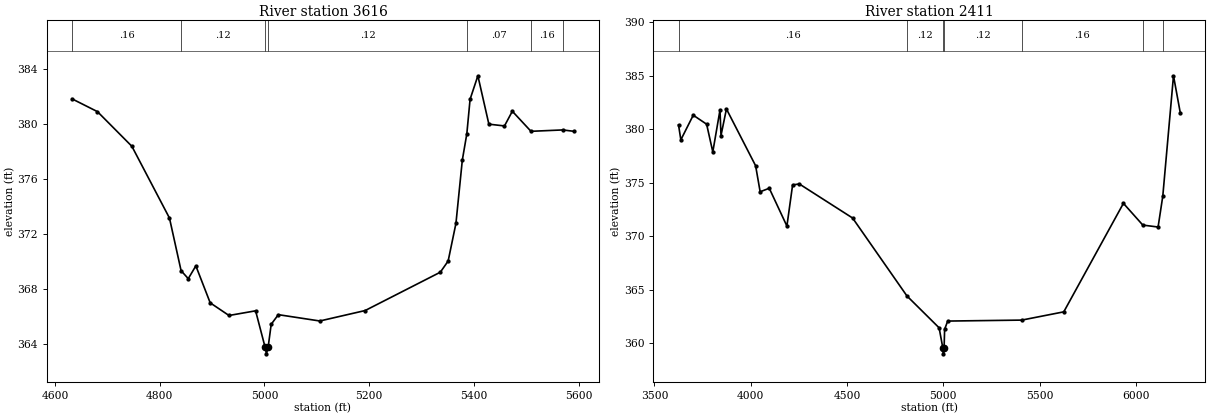
Type RM Length L Ch R = 1,3616,1205,1205,1205
BEGIN DESCRIPTION:
UNT038 IN STEL 6.0
END DESCRIPTION:
XS GIS Cut Line= 2
      3502667.01     10461083.99      3503457.90     10460542.86
#Sta/Elev= 30
  4632.6  381.84  4681.1  380.91  4746.8  378.39  4818.6  373.17  4840.8  369.34
  4854.5  368.76  4869.0  369.69  4896.4  367.00  4932.3  366.08  4983.1  366.42
  5001.1  363.79  5003.8  363.29  5007.1  363.79  5012.9  365.44  5026.5  366.14
  5105.7  365.68  5192.3  366.44  5335.9  369.23  5350.8  370.04  5365.7  372.78
  5377.9  377.39  5386.5  379.30  5392.7  381.81  5407.6  383.52  5428.6  380.00
  5458.4  379.87  5473.4  380.94  5509.0  379.48  5569.7  379.58  5590.9  379.48
#Mann=7,-1,0
  4632.6    0.16       0  4840.8    0.12       0  5001.1    0.07       0
  5007.1    0.12       0  5386.5    0.07       0  5509.0    0.16       0
  5569.7    0.07       0
Bank Sta=5001.1,5007.1
Exp/Cntr=0.3,0.1

Type RM Length L Ch R = 1,2411,0,0,0
BEGIN DESCRIPTION:
UNT038 IN STEL 1.0
END DESCRIPTION:
XS GIS Cut Line= 4
      3502006.02     10461634.77      3502884.90     10461764.98
      3503864.94     10461224.61      3503844.12     10460626.18
#Sta/Elev= 30
  3624.9  380.39  3636.9  379.00  3701.3  381.30  3770.8  380.46  3802.9  377.87
  3840.3  381.79  3845.4  379.40  3873.7  381.88  4025.3  376.58  4048.8  374.15
  4096.1  374.48  4187.8  370.95  4217.4  374.79  4252.3  374.88  4529.0  371.70
  4811.5  364.42  4978.4  361.45  4998.2  359.52  5001.0  359.02  5004.2  359.52
  5007.0  361.31  5023.0  362.08  5407.7  362.17  5625.9  362.94  5935.7  373.07
  6036.5  371.04  6115.8  370.86  6140.2  373.74  6195.8  384.98  6231.3  381.50
#Mann=7,-1,0
  3624.9    0.16       0  4811.5    0.12       0  4998.2    0.07       0
  5004.2    0.12       0  5407.7    0.16       0  6036.5    0.12       0
  6140.2    0.05       0
Bank Sta=4998.2,5004.2
Exp/Cntr=0.3,0.1

Chan Stop Cuts=-1