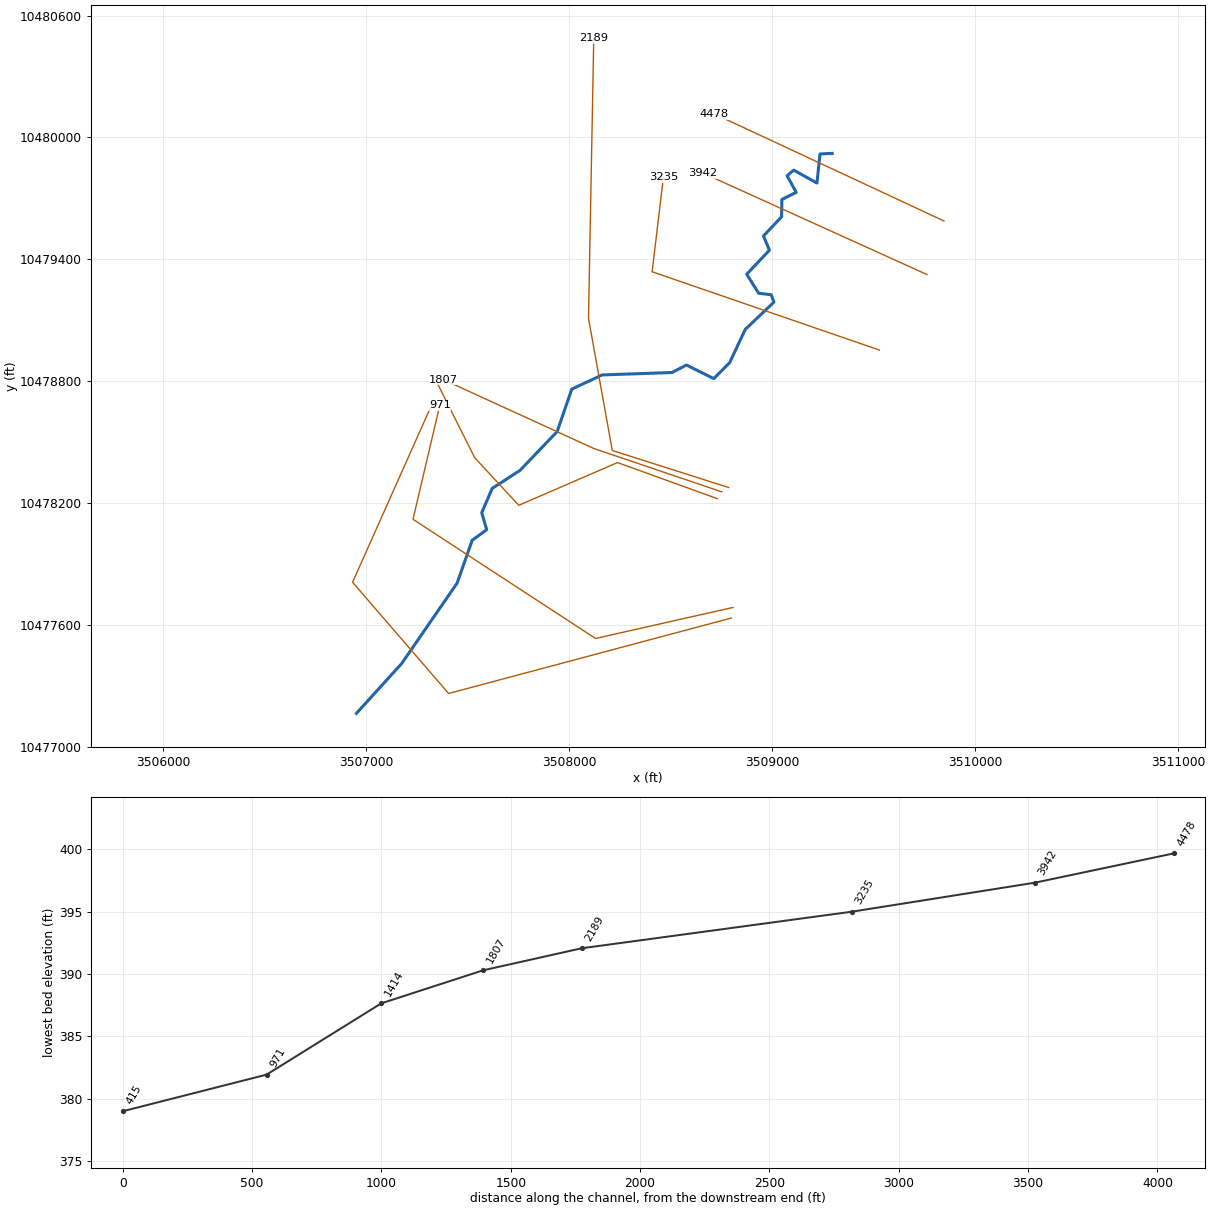
--- UNT046 IN STEL.prj (project) ---

Proj Title=UNT046 IN STEL Base Level Engineering
Current Plan=p01
Default Exp/Contr=0.3,0.1
English Units
Geom File=g01
Flow File=f01
Plan File=p01
Y Axis Title=Elevation
X Axis Title(PF)=Main Channel Distance
X Axis Title(XS)=Station
BEGIN DESCRIPTION:
UNT046 IN STEL
END DESCRIPTION:
DSS Export Rating Curves= 0
DSS Export Rating Curve Sorted= 0
DSS Export Volume Flow Curves= 0
DXF OffsetX= 0
DXF OffsetY= 0
DXF ScaleX= 1
DXF ScaleY= 10

--- UNT046 IN STEL.p01 (plan) ---

Plan Title=Multiple Run
Short Identifier=Multiple
Geom File=g01
Flow File=f01
Subcritical Flow
K Sum by GR= 0
Std Step Tol= 0.01
Critical Tol= 0.01
Num of Std Step Trials= 20
Max Error Tol= 0.3
Flow Tol Ratio= 0.001
Split Flow NTrial= 30
Split Flow Tol= 0.02
Split Flow Ratio= 0.02
Log Output Level= 0
Friction Slope Method= 1
Unsteady Friction Slope Method= 2
Unsteady Bridges Friction Slope Method= 1
Parabolic Critical Depth
Global Vel Dist=  1 , 1 , 1
Global Log Level= 0
CheckData=True
Encroach Param= -1, 0, 0, 0
BEGIN DESCRIPTION:
Multiple Run
END DESCRIPTION:

--- UNT046 IN STEL.f01 (steady flow) ---

Flow Title=Multiple
Number of Profiles=7
Profile Names=10-year,25-year,50-year,1pct_min,100-year,1pct_plu,500-year
River Rch & RM= UNT046 IN STEL,Reach-1,4478
     568     757     907     794    1074    1453    1503
Boundary for River Rch & Prof#=UNT046 IN STEL,Reach-1,1
Up Type=0
Dn Type=3
Dn Slope=0.005
Boundary for River Rch & Prof#=UNT046 IN STEL,Reach-1,2
Up Type=0
Dn Type=3
Dn Slope=0.005
Boundary for River Rch & Prof#=UNT046 IN STEL,Reach-1,3
Up Type=0
Dn Type=3
Dn Slope=0.005
Boundary for River Rch & Prof#=UNT046 IN STEL,Reach-1,4
Up Type=0
Dn Type=3
Dn Slope=0.005
Boundary for River Rch & Prof#=UNT046 IN STEL,Reach-1,5
Up Type=0
Dn Type=3
Dn Slope=0.005
Boundary for River Rch & Prof#=UNT046 IN STEL,Reach-1,6
Up Type=0
Dn Type=3
Dn Slope=0.005
Boundary for River Rch & Prof#=UNT046 IN STEL,Reach-1,7
Up Type=0
Dn Type=3
Dn Slope=0.005

--- UNT046 IN STEL.g01 (geometry) ---

Geom Title=Existing Conditions
Program Version=4.10

River Reach=UNT046 IN STEL  ,Reach-1
Reach XY= 30
      3509295.55     10479921.52      3509235.53     10479918.73
      3509220.38     10479775.71      3509106.18     10479839.13
      3509073.39     10479811.69      3509118.36     10479729.76
      3509047.61     10479694.34      3509046.42     10479609.52
      3508957.25     10479514.89      3508986.46      10479444.9
      3508874.31     10479326.29      3508933.46     10479232.81
      3508994.96     10479225.52      3509008.64     10479188.98
      3508867.15     10479054.56      3508790.81     10478891.29
      3508712.51     10478812.44      3508577.69     10478879.29
      3508506.82     10478842.42      3508162.54     10478830.52
      3508013.04     10478760.74       3507940.8     10478551.34
      3507757.53     10478360.24       3507620.7     10478271.28
      3507569.35      10478151.8      3507593.93     10478068.33
      3507522.33     10478016.19      3507447.99     10477805.07
      3507174.71     10477408.82      3506952.06     10477163.75

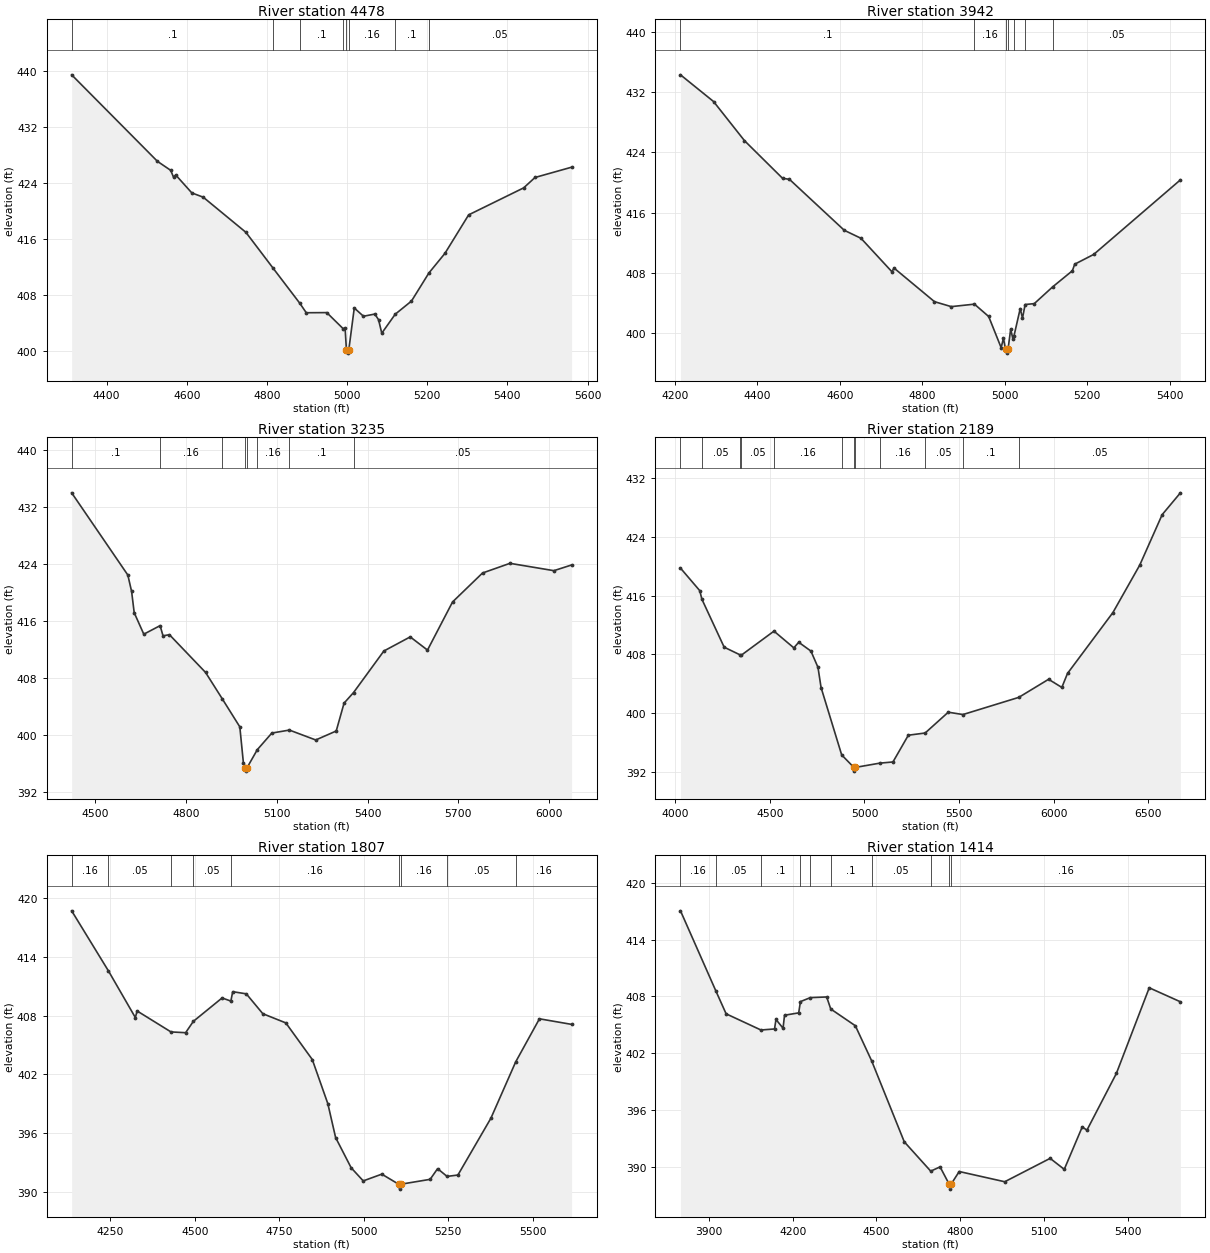
Type RM Length L Ch R = 1 ,4478    ,536,536,536
BEGIN DESCRIPTION:
UNT046 IN STEL 9.0
END DESCRIPTION:
XS GIS Cut Line= 2
      3509846.08     10479588.64      3508715.62     10480115.72
#Sta/Elev= 30
  4312.9  439.48  4526.9   427.1    4560  425.81    4567  424.84  4572.5  425.15
  4612.7  422.58  4641.1  421.97  4747.6  416.94  4815.3  411.82  4882.2  406.78
  4898.2  405.43  4949.4  405.45  4990.2  403.15  4995.1  403.25  4998.4  400.15
  5001.1  399.65  5004.4  400.15    5018  406.11  5040.9  404.93  5069.3  405.24
  5078.6  404.43  5086.6   402.5  5120.2  405.22  5160.7   407.1  5204.2  411.12
  5244.1  413.92  5303.4  419.44  5440.6   423.3    5469  424.79  5560.2  426.26
#Mann= 8 ,-1 , 0
  4312.9      .1       0  4815.3     .16       0  4882.2      .1       0
  4990.2     .16       0  4998.4     .07       0  5004.4     .16       0
  5120.2      .1       0  5204.2     .05       0
Bank Sta=4998.4,5004.4
XS Rating Curve= 0 ,0
Exp/Cntr=0.3,0.1

Type RM Length L Ch R = 1 ,3942    ,707,707,707
BEGIN DESCRIPTION:
UNT046 IN STEL 8.0
END DESCRIPTION:
XS GIS Cut Line= 2
      3509762.78     10479324.74      3508658.61     10479824.74
#Sta/Elev= 30
  4213.5   434.3  4293.7  430.75  4368.5  425.56  4460.9  420.55  4477.7  420.41
  4610.5  413.64  4651.2  412.57  4725.9  408.14  4731.4  408.61  4829.3  404.15
    4870  403.49  4926.2  403.82  4960.7  402.18    4991  398.03  4996.5   399.3
  5001.6  397.81  5004.4  397.31  5007.6  397.81  5014.1   400.5  5019.6  399.16
    5022  399.58  5037.2  403.23  5042.7  401.96  5049.1  403.77  5071.3  403.89
  5115.7  406.11  5163.7  408.26  5169.3  409.13  5215.4  410.43  5425.6  420.34
#Mann= 7 ,-1 , 0
  4213.5      .1       0  4926.2     .16       0  5001.6     .07       0
  5007.6     .16       0    5022      .1       0  5049.1     .16       0
  5115.7     .05       0
Bank Sta=5001.6,5007.6
XS Rating Curve= 0 ,0
Exp/Cntr=0.3,0.1

Type RM Length L Ch R = 1 ,3235    ,1046,1046,1046
BEGIN DESCRIPTION:
UNT046 IN STEL 7.0
END DESCRIPTION:
XS GIS Cut Line= 3
      3509527.55     10478953.21      3508408.58     10479338.64
      3508464.14     10479803.94
#Sta/Elev= 30
  4422.2  434.03  4607.8   422.5  4620.3  420.19  4628.9  417.21  4660.6   414.2
  4714.5   415.4  4724.1  413.97  4745.3  414.13  4864.8  408.83  4919.5  405.16
  4977.9   401.2  4989.6   396.2  4996.1  395.49  4998.8  394.99  5002.1  395.49
  5035.7     398  5083.7  400.33  5141.7  400.75  5228.8  399.36  5296.5  400.62
  5322.4  404.53  5353.7  406.01  5453.9  411.84    5541  413.82  5598.1  411.97
  5680.9  418.72  5779.9  422.78  5870.6  424.14  6015.8  423.11  6074.3  423.91
#Mann= 8 ,-1 , 0
  4422.2      .1       0  4714.5     .16       0  4919.5      .1       0
  4996.1     .07       0  5002.1      .1       0  5035.7     .16       0
  5141.7      .1       0  5353.7     .05       0
Bank Sta=4996.1,5002.1
XS Rating Curve= 0 ,0
Exp/Cntr=0.3,0.1

Type RM Length L Ch R = 1 ,2189    ,382,382,382
BEGIN DESCRIPTION:
UNT046 IN STEL 5.0
END DESCRIPTION:
XS GIS Cut Line= 4
      3508785.36     10478276.13       3508212.4     10478458.43
      3508095.21     10479109.47      3508121.22     10480488.16
#Sta/Elev= 30
  4027.9  419.76  4129.8  416.68  4140.9  415.52  4258.7  408.97  4344.5   407.9
  4347.8  407.85  4521.9  411.16  4626.7  408.88  4652.7  409.64  4717.1  408.44
  4754.4  406.22  4770.8  403.46  4879.7  394.27  4944.4  392.56  4947.2  392.06
  4950.4  392.56  5081.1  393.15  5150.6  393.31  5231.9  396.96  5320.7  397.26
  5442.9   400.1  5520.5  399.78  5815.2  402.12    5973  404.59    6043  403.48
    6073  405.39    6313   413.7  6454.7  420.17  6573.1  427.05  6669.6  430.03
#Mann= 12 ,-1 , 0
  4027.9     .16       0  4140.9     .05       0  4344.5      .1       0
  4347.8     .05       0  4521.9     .16       0  4879.7     .12       0
  4944.4     .07       0  4950.4     .12       0  5081.1     .16       0
  5320.7     .05       0  5520.5      .1       0  5815.2     .05       0
Bank Sta=4944.4,4950.4
XS Rating Curve= 0 ,0
Exp/Cntr=0.3,0.1

Type RM Length L Ch R = 1 ,1807    ,393,393,393
BEGIN DESCRIPTION:
Mapping XS ab9f51b1
END DESCRIPTION:
XS GIS Cut Line= 3
      3508751.31     10478254.82      3508121.08     10478468.37
      3507381.78     10478806.78
#Sta/Elev= 30
    4136  418.72  4244.8  412.58  4324.3  407.82  4329.6  408.49  4429.7  406.35
    4473  406.27  4495.9  407.43  4580.9  409.82  4606.8   409.5  4612.3  410.46
  4652.5  410.24  4701.3  408.21  4769.4  407.27  4847.6  403.53  4893.6  399.02
  4916.6  395.56  4962.6  392.47  4998.3  391.13  5053.2  391.82  5103.2  390.79
  5105.9  390.29  5109.2  390.79  5196.2  391.29  5218.2  392.38  5246.2  391.59
  5278.3  391.73  5375.8  397.53  5449.2  403.29  5519.4  407.69  5614.5  407.12
#Mann= 9 ,-1 , 0
    4136     .16       0  4244.8     .05       0  4429.7      .1       0
  4495.9     .05       0  4606.8     .16       0  5103.2     .07       0
  5109.2     .16       0  5246.2     .05       0  5449.2     .16       0
Bank Sta=5103.2,5109.2
XS Rating Curve= 0 ,0
Exp/Cntr=0.3,0.1

Type RM Length L Ch R = 1 ,1414    ,443,443,443
BEGIN DESCRIPTION:
Mapping XS 02dc515f
END DESCRIPTION:
XS GIS Cut Line= 5
      3508730.58     10478220.98      3508237.96     10478398.94
      3507751.85     10478188.43      3507534.83     10478422.81
      3507347.13     10478796.71
#Sta/Elev= 30
  3798.2  417.05  3924.6  408.61  3961.7  406.17  4086.5  404.46  4135.1  404.57
  4140.4  405.57  4165.7  404.65    4171  406.02  4221.7  406.27    4228  407.46
  4263.4  407.88    4322  407.95  4336.6  406.68  4424.7  404.91  4482.9  401.22
    4600  392.65  4694.8  389.55  4728.3     390  4761.3  388.15    4764  387.65
  4767.3  388.15  4796.9  389.51    4960  388.43  5122.7   390.9  5173.3  389.74
  5237.7  394.22  5254.5  393.88    5360  399.87  5477.8  408.92  5589.5  407.44
#Mann= 10 ,-1 , 0
  3798.2     .16       0  3924.6     .05       0  4086.5      .1       0
    4228     .05       0  4263.4     .16       0  4336.6      .1       0
  4482.9     .05       0  4694.8     .16       0  4761.3     .07       0
  4767.3     .16       0
Bank Sta=4761.3,4767.3
XS Rating Curve= 0 ,0
Exp/Cntr=0.3,0.1

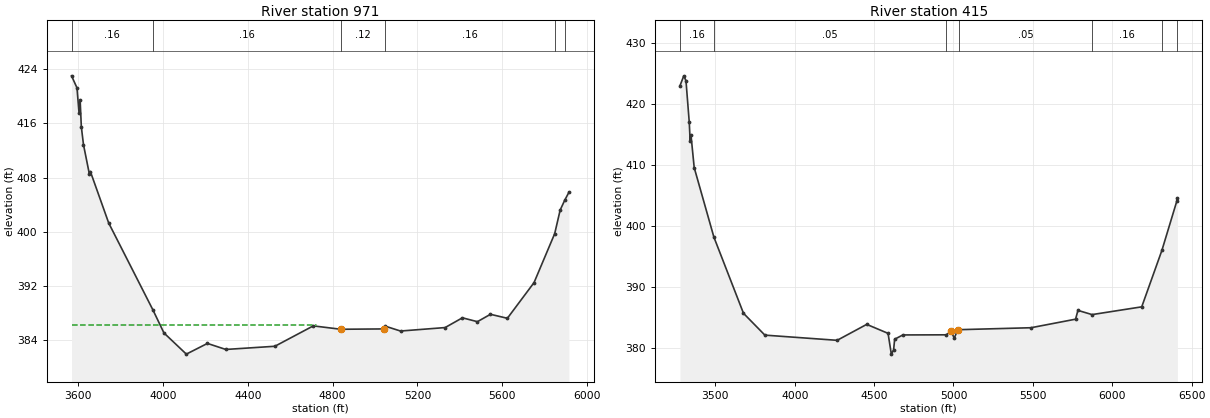
Type RM Length L Ch R = 1 ,971     ,556,556,556
BEGIN DESCRIPTION:
UNT046 IN STEL 1.1
END DESCRIPTION:
XS GIS Cut Line= 4
      3508807.15     10477685.46       3508130.1     10477532.69
       3507230.8      10478119.5      3507362.87     10478681.81
#Sta/Elev= 30
  3568.6  423.03  3594.3  421.25    3604  417.54  3609.2  419.43  3614.8   415.5
    3625  412.86  3652.4  408.58  3657.5   408.9  3743.9   401.3  3953.1  388.43
  4004.3  385.08  4109.9  381.95  4209.4  383.53  4296.1  382.64  4527.5  383.11
  4708.6  386.12  4838.3  385.62  5040.4  385.67  5048.4  386.07    5120  385.36
  5330.1  385.87  5411.8  387.31  5482.5  386.74  5544.1  387.83  5623.8  387.24
  5749.6  392.51  5846.9  399.73  5872.8  403.22  5893.7  404.63  5914.1  405.85
#Mann= 6 ,-1 , 0
  3568.6     .16       0  3953.1     .16       0  4838.3     .12       0
  5048.4     .16       0  5846.9     .05       0  5893.7     .16       0
#XS Ineff= 2 , 0
       0 4723.01   386.2               0
Permanent Ineff=
       T       F
Bank Sta=4838.3,5040.4
XS Rating Curve= 0 ,0
Exp/Cntr=0.3,0.1

Type RM Length L Ch R = 1 ,415     ,0,0,0
BEGIN DESCRIPTION:
UNT046 IN STEL 1.0
END DESCRIPTION:
XS GIS Cut Line= 4
      3508798.63     10477633.24      3507406.28     10477261.72
      3506933.19     10477809.46      3507327.65     10478693.74
#Sta/Elev= 30
  3277.1  422.94    3301  424.57  3314.9  423.77  3335.6  416.96  3341.1  413.93
  3346.3  414.91  3366.7  409.55  3490.9  398.16  3677.2   385.7  3811.9  382.13
  4267.1  381.28  4453.4  383.89  4587.9  382.42  4608.4  379.02  4622.8  379.71
  4629.3  381.46  4681.1  382.16  4955.4  382.18    4983  382.79  5004.9  381.66
  5025.7   382.9  5033.4  383.02  5488.1  383.34    5769  384.74  5783.8  386.18
  5872.8  385.49  6185.7  386.76  6312.6  395.99  6407.8  404.16  6410.2  404.54
#Mann= 7 ,-1 , 0
  3277.1     .16       0  3490.9     .05       0  4955.4     .03       0
  5033.4     .05       0  5872.8     .16       0  6312.6     .05       0
  6407.8     .16       0
#XS Ineff= 1 ,-1
 3586.87 4974.42382.5912
Permanent Ineff=
       T
Bank Sta=4983,5025.7
XS Rating Curve= 0 ,0
Exp/Cntr=0.3,0.1

Chan Stop Cuts=-1
Use User Specified Reach Order=0
Composite Channel Slope=5