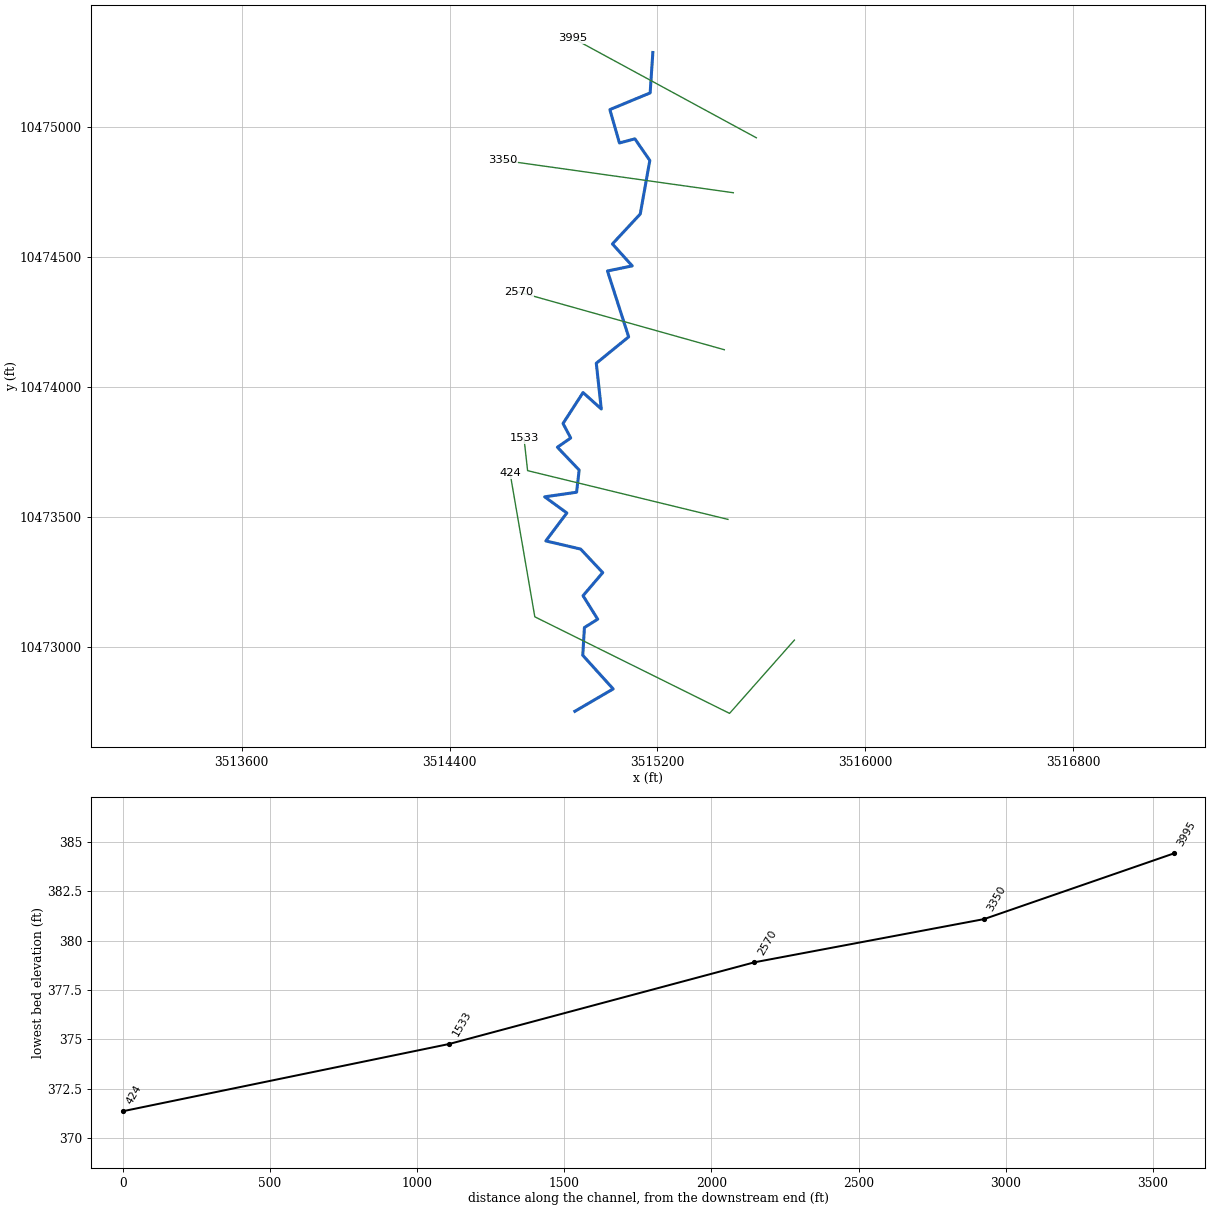
--- UNT050 IN STEL.prj (project) ---

Proj Title=UNT050 IN STEL Base Level Engineering
Current Plan=p01
Default Exp/Contr=0.3,0.1
English Units
Geom File=g01
Flow File=f01
Plan File=p01
BEGIN DESCRIPTION:
UNT050 IN STEL
END DESCRIPTION:

--- UNT050 IN STEL.p01 (plan) ---

Plan Title=Multiple Run
Short Identifier=Multiple
Geom File=g01
Flow File=f01
Subcritical Flow
K Sum by GR= 0
Std Step Tol= 0.01
Critical Tol= 0.01
Num of Std Step Trials= 20
Max Error Tol= 0.3
Flow Tol Ratio= 0.001
Split Flow NTrial= 30
Split Flow Tol= 0.02
Split Flow Ratio= 0.02
Log Output Level= 0
Friction Slope Method= 1
Unsteady Friction Slope Method= 2
Unsteady Bridges Friction Slope Method= 1
Parabolic Critical Depth
Global Vel Dist=  1 , 1 , 1
Global Log Level= 0
CheckData=True
Encroach Param= -1, 0, 0, 0
BEGIN DESCRIPTION:
Multiple Run
END DESCRIPTION:

--- UNT050 IN STEL.f01 (steady flow) ---

Flow Title=Multiple
Number of Profiles=7
Profile Names=10-year,25-year,50-year,1pct_min,100-year,1pct_plu,500-year
River Rch & RM= UNT050 IN STEL,Reach-1,3995
     702     944    1139    1004    1357    1836    1922
Boundary for River Rch & Prof#=UNT050 IN STEL,Reach-1,1
Up Type=0
Dn Type=3
Dn Slope=0.005
Boundary for River Rch & Prof#=UNT050 IN STEL,Reach-1,2
Up Type=0
Dn Type=3
Dn Slope=0.005
Boundary for River Rch & Prof#=UNT050 IN STEL,Reach-1,3
Up Type=0
Dn Type=3
Dn Slope=0.005
Boundary for River Rch & Prof#=UNT050 IN STEL,Reach-1,4
Up Type=0
Dn Type=3
Dn Slope=0.005
Boundary for River Rch & Prof#=UNT050 IN STEL,Reach-1,5
Up Type=0
Dn Type=3
Dn Slope=0.005
Boundary for River Rch & Prof#=UNT050 IN STEL,Reach-1,6
Up Type=0
Dn Type=3
Dn Slope=0.005
Boundary for River Rch & Prof#=UNT050 IN STEL,Reach-1,7
Up Type=0
Dn Type=3
Dn Slope=0.005

--- UNT050 IN STEL.g01 (geometry) ---

Geom Title=Existing Conditions

River Reach=UNT050 IN STEL,Reach-1
Reach XY= 30
      3515182.22     10475286.76      3515171.80     10475131.26
      3515016.83     10475067.07      3515053.65     10474938.74
      3515113.14     10474954.55      3515170.56     10474871.29
      3515133.74     10474665.23      3515026.68     10474550.16
      3515102.88     10474465.65      3515007.62     10474446.04
      3515089.14     10474192.62      3514964.62     10474090.96
      3514983.82     10473915.05      3514913.65     10473978.28
      3514836.61     10473859.25      3514866.17     10473803.32
      3514814.95     10473767.87      3514898.70     10473680.04
      3514888.73     10473594.62      3514766.05     10473576.97
      3514851.30     10473514.95      3514770.46     10473407.27
      3514904.24     10473376.00      3514989.42     10473285.37
      3514913.58     10473196.42      3514969.98     10473106.11
      3514918.90     10473073.92      3514912.60     10472967.06
      3515029.53     10472837.77      3514882.11     10472751.64

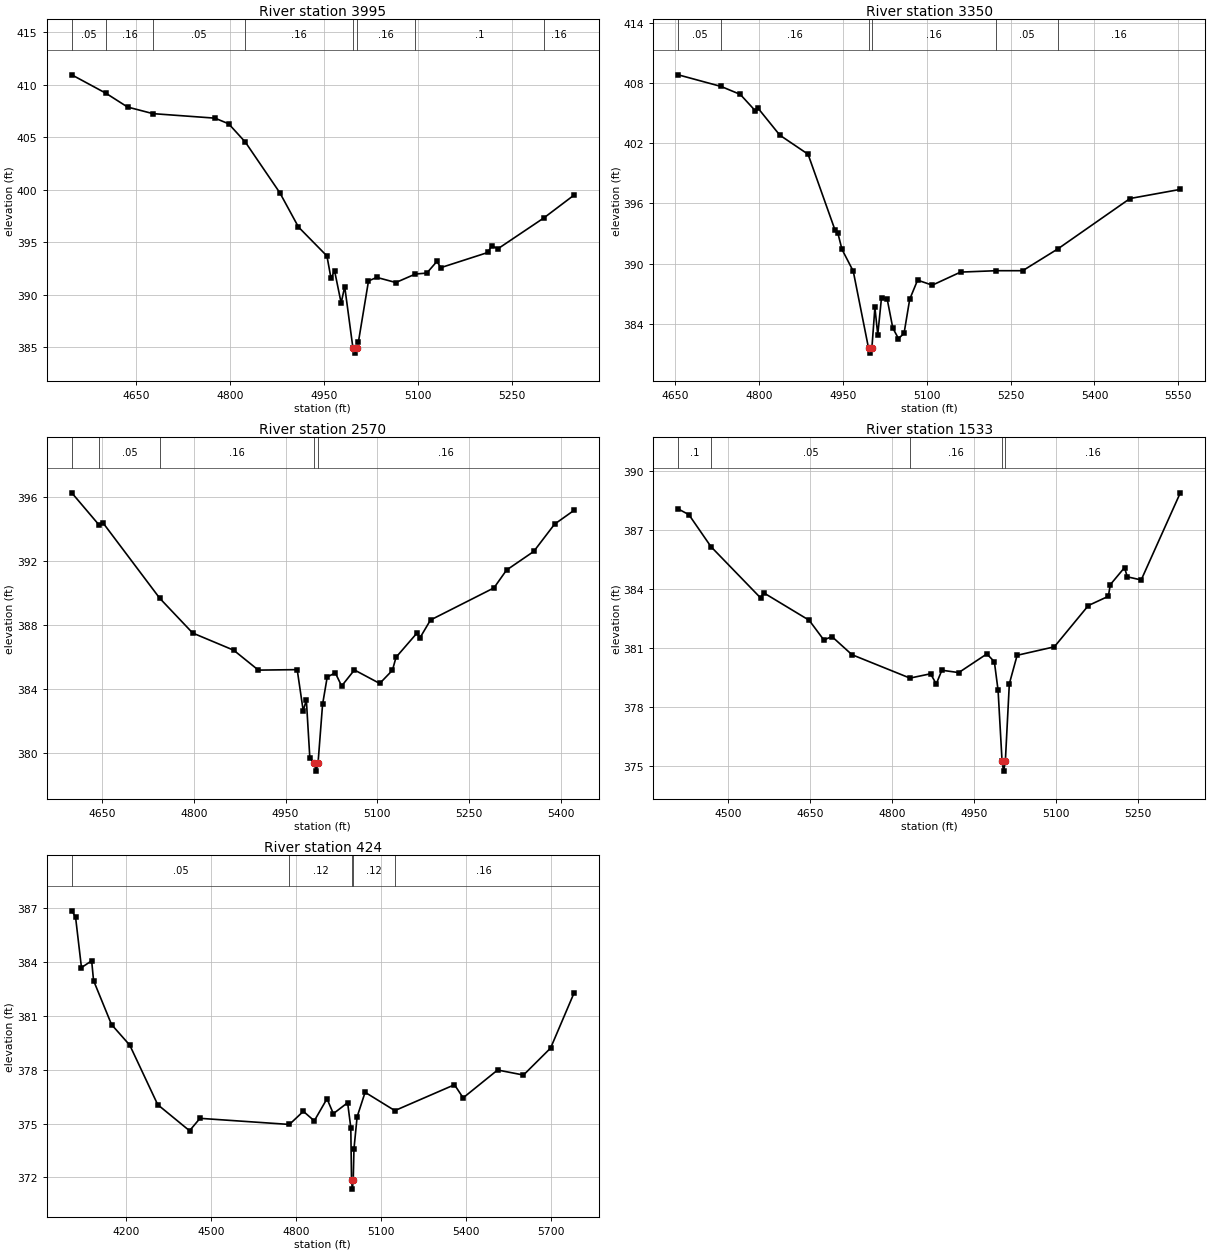
Type RM Length L Ch R = 1,3995,645,645,645
BEGIN DESCRIPTION:
UNT050 IN STEL 5.0
END DESCRIPTION:
XS GIS Cut Line= 2
      3515580.41     10474958.68      3514875.34     10475341.31
#Sta/Elev= 30
  4547.2  410.95  4601.9  409.19  4636.3  407.88  4676.9  407.25  4776.0  406.82
  4797.9  406.28  4824.6  404.53  4879.6  399.71  4909.4  396.44  4954.9  393.68
  4961.4  391.55  4967.1  392.27  4977.6  389.20  4983.3  390.76  4996.4  384.92
  4999.2  384.42  5002.4  384.92  5005.1  385.45  5021.3  391.30  5034.5  391.64
  5065.0  391.15  5096.2  391.96  5114.4  392.05  5130.6  393.16  5136.9  392.57
  5212.3  394.02  5218.0  394.67  5227.9  394.36  5301.3  397.30  5349.4  399.47
#Mann=8,-1,0
  4547.2    0.05       0  4601.9    0.16       0  4676.9    0.05       0
  4824.6    0.16       0  4996.4    0.07       0  5002.4    0.16       0
  5096.2     0.1       0  5301.3    0.16       0
Bank Sta=4996.4,5002.4
Exp/Cntr=0.3,0.1

Type RM Length L Ch R = 1,3350,780,780,780
BEGIN DESCRIPTION:
UNT050 IN STEL 4.0
END DESCRIPTION:
XS GIS Cut Line= 2
      3515491.92     10474747.20      3514603.07     10474872.20
#Sta/Elev= 30
  4655.9  408.81  4732.6  407.65  4766.8  406.86  4793.8  405.22  4798.8  405.47
  4837.5  402.80  4888.0  400.90  4936.3  393.33  4941.3  393.04  4948.6  391.43
  4968.8  389.25  4996.1  381.59  4998.8  381.09  5002.1  381.59  5007.5  385.64
  5012.6  382.92  5019.3  386.62  5029.4  386.49  5039.5  383.59  5049.6  382.54
  5059.6  383.06  5069.7  386.45  5083.8  388.36  5110.1  387.86  5160.6  389.16
  5224.1  389.30  5271.7  389.30  5334.8  391.48  5463.6  396.49  5553.5  397.40
#Mann=6,-1,0
  4655.9    0.05       0  4732.6    0.16       0  4996.1    0.07       0
  5002.1    0.16       0  5224.1    0.05       0  5334.8    0.16       0
Bank Sta=4996.1,5002.1
Exp/Cntr=0.3,0.1

Type RM Length L Ch R = 1,2570,1037,1037,1037
BEGIN DESCRIPTION:
UNT050 IN STEL 3.0
END DESCRIPTION:
XS GIS Cut Line= 2
      3515457.15     10474143.05      3514666.32     10474365.04
#Sta/Elev= 30
  4600.3  396.23  4645.1  394.22  4651.4  394.36  4744.3  389.66  4798.1  387.50
  4865.2  386.43  4905.6  385.19  4969.1  385.22  4978.9  382.67  4984.1  383.32
  4989.8  379.71  4997.2  379.40  5000.0  378.90  5003.2  379.40  5010.6  383.05
  5018.2  384.76  5031.4  385.02  5041.8  384.20  5062.7  385.20  5104.1  384.36
  5124.9  385.18  5130.8  385.99  5164.9  387.49  5170.1  387.21  5187.2  388.31
  5291.0  390.31  5311.6  391.42  5356.1  392.58  5390.2  394.28  5421.7  395.13
#Mann=5,-1,0
  4600.3    0.16       0  4645.1    0.05       0  4744.3    0.16       0
  4997.2    0.07       0  5003.2    0.16       0
Bank Sta=4997.2,5003.2
Exp/Cntr=0.3,0.1

Type RM Length L Ch R = 1,1533,1109,1109,1109
BEGIN DESCRIPTION:
UNT050 IN STEL 2.0
END DESCRIPTION:
XS GIS Cut Line= 3
      3515471.06     10473490.27      3514700.24     10473677.76
      3514686.35     10473802.80
#Sta/Elev= 30
  4408.4  388.09  4427.9  387.80  4468.4  386.17  4559.4  383.56  4564.6  383.83
  4648.1  382.43  4674.9  381.43  4689.8  381.60  4726.4  380.68  4832.6  379.49
  4870.4  379.71  4880.7  379.19  4891.0  379.89  4921.9  379.77  4973.4  380.72
  4987.1  380.32  4993.9  378.87  5001.2  375.26  5004.0  374.76  5007.2  375.26
  5014.5  379.20  5028.8  380.65  5096.9  381.08  5159.2  383.18  5195.8  383.65
  5199.3  384.24  5225.4  385.11  5230.4  384.64  5255.9  384.48  5327.5  388.91
#Mann=5,-1,0
  4408.4     0.1       0  4468.4    0.05       0  4832.6    0.16       0
  5001.2    0.07       0  5007.2    0.16       0
Bank Sta=5001.2,5007.2
Exp/Cntr=0.3,0.1

Type RM Length L Ch R = 1,424,0,0,0
BEGIN DESCRIPTION:
UNT050 IN STEL 1.0
END DESCRIPTION:
XS GIS Cut Line= 4
      3515726.81     10473025.59      3515477.47     10472743.69
      3514728.02     10473115.26      3514633.07     10473666.89
#Sta/Elev= 30
  4006.9  386.84  4020.2  386.50  4041.1  383.68  4077.1  384.06  4083.8  382.96
  4147.3  380.51  4211.8  379.36  4310.4  376.05  4422.7  374.60  4459.6  375.29
  4775.3  374.95  4824.5  375.68  4863.1  375.15  4908.0  376.38  4930.4  375.55
  4980.8  376.16  4992.0  374.78  4994.6  371.85  4997.4  371.35  5000.6  371.85
  5003.2  373.59  5014.3  375.37  5042.5  376.74  5147.5  375.72  5358.1  377.16
  5388.6  376.43  5510.3  377.98  5601.7  377.70  5697.4  379.20  5779.5  382.24
#Mann=5,-1,0
  4006.9    0.05       0  4775.3    0.12       0  4994.6    0.07       0
  5000.6    0.12       0  5147.5    0.16       0
Bank Sta=4994.6,5000.6
Exp/Cntr=0.3,0.1

Chan Stop Cuts=-1