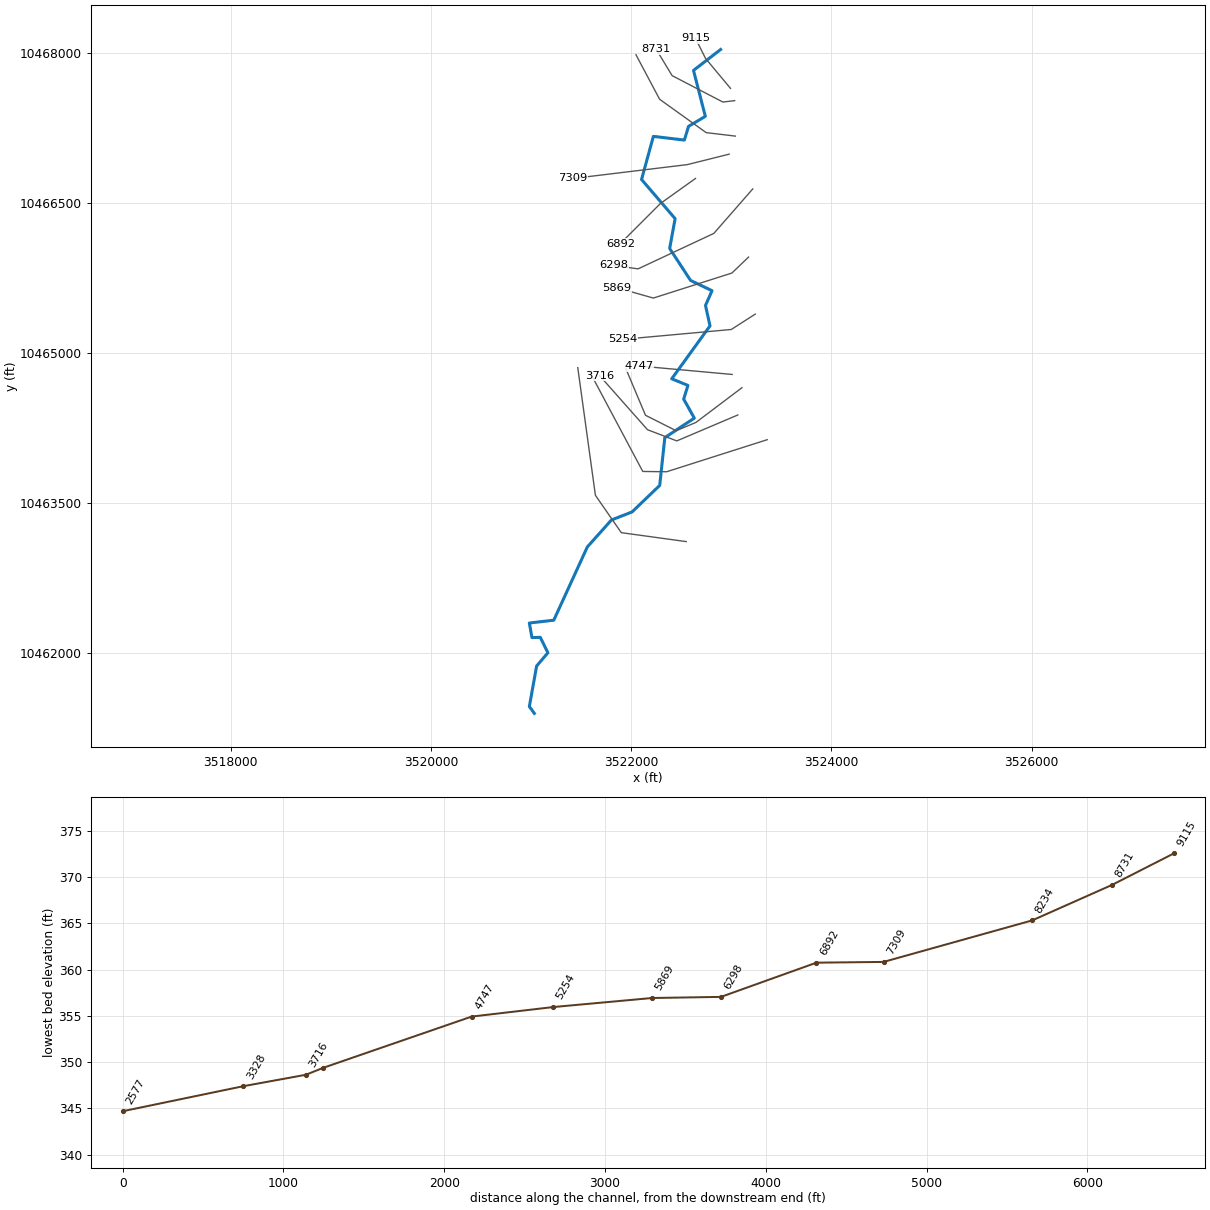
--- UNT054 IN STEL.prj (project) ---

Proj Title=UNT054 IN STEL Base Level Engineering
Current Plan=p01
Default Exp/Contr=0.3,0.1
English Units
Geom File=g01
Flow File=f01
Plan File=p01
BEGIN DESCRIPTION:
UNT054 IN STEL
END DESCRIPTION:

--- UNT054 IN STEL.p01 (plan) ---

Plan Title=Multiple Run
Short Identifier=Multiple
Geom File=g01
Flow File=f01
Subcritical Flow
K Sum by GR= 0
Std Step Tol= 0.01
Critical Tol= 0.01
Num of Std Step Trials= 20
Max Error Tol= 0.3
Flow Tol Ratio= 0.001
Split Flow NTrial= 30
Split Flow Tol= 0.02
Split Flow Ratio= 0.02
Log Output Level= 0
Friction Slope Method= 1
Unsteady Friction Slope Method= 2
Unsteady Bridges Friction Slope Method= 1
Parabolic Critical Depth
Global Vel Dist=  1 , 1 , 1
Global Log Level= 0
CheckData=True
Encroach Param= -1, 0, 0, 0
BEGIN DESCRIPTION:
Multiple Run
END DESCRIPTION:

--- UNT054 IN STEL.f01 (steady flow) ---

Flow Title=Multiple
Number of Profiles=7
Profile Names=10-year,25-year,50-year,1pct_min,100-year,1pct_plu,500-year
River Rch & RM= UNT054 IN STEL,Reach-1,9115
    1110    1533    1884    1688    2283    3087    3343
River Rch & RM= UNT054 IN STEL,Reach-1,7309
    1389    1933    2386    2145    2900    3922    4278
Boundary for River Rch & Prof#=UNT054 IN STEL,Reach-1,1
Up Type=0
Dn Type=3
Dn Slope=0.005
Boundary for River Rch & Prof#=UNT054 IN STEL,Reach-1,2
Up Type=0
Dn Type=3
Dn Slope=0.005
Boundary for River Rch & Prof#=UNT054 IN STEL,Reach-1,3
Up Type=0
Dn Type=3
Dn Slope=0.005
Boundary for River Rch & Prof#=UNT054 IN STEL,Reach-1,4
Up Type=0
Dn Type=3
Dn Slope=0.005
Boundary for River Rch & Prof#=UNT054 IN STEL,Reach-1,5
Up Type=0
Dn Type=3
Dn Slope=0.005
Boundary for River Rch & Prof#=UNT054 IN STEL,Reach-1,6
Up Type=0
Dn Type=3
Dn Slope=0.005
Boundary for River Rch & Prof#=UNT054 IN STEL,Reach-1,7
Up Type=0
Dn Type=3
Dn Slope=0.005

--- UNT054 IN STEL.g01 (geometry) ---

Geom Title=Existing Conditions

River Reach=UNT054 IN STEL,Reach-1
Reach XY= 30
      3522893.55     10468030.08      3522622.40     10467821.31
      3522740.52     10467362.41      3522572.79     10467262.30
      3522531.21     10467125.14      3522221.40     10467162.25
      3522103.37     10466731.22      3522438.81     10466340.20
      3522384.20     10466042.60      3522593.14     10465722.71
      3522807.26     10465620.30      3522742.19     10465472.73
      3522787.12     10465269.19      3522404.79     10464740.04
      3522566.67     10464674.20      3522524.15     10464537.57
      3522630.53     10464347.45      3522335.81     10464152.19
      3522284.75     10463675.14      3522008.59     10463409.80
      3521802.57     10463329.76      3521561.73     10463060.55
      3521226.48     10462328.52      3520982.34     10462300.30
      3521008.38     10462154.91      3521091.93     10462157.08
      3521167.89     10462003.00      3521055.04     10461870.62
      3520982.34     10461465.89      3521032.30     10461397.61

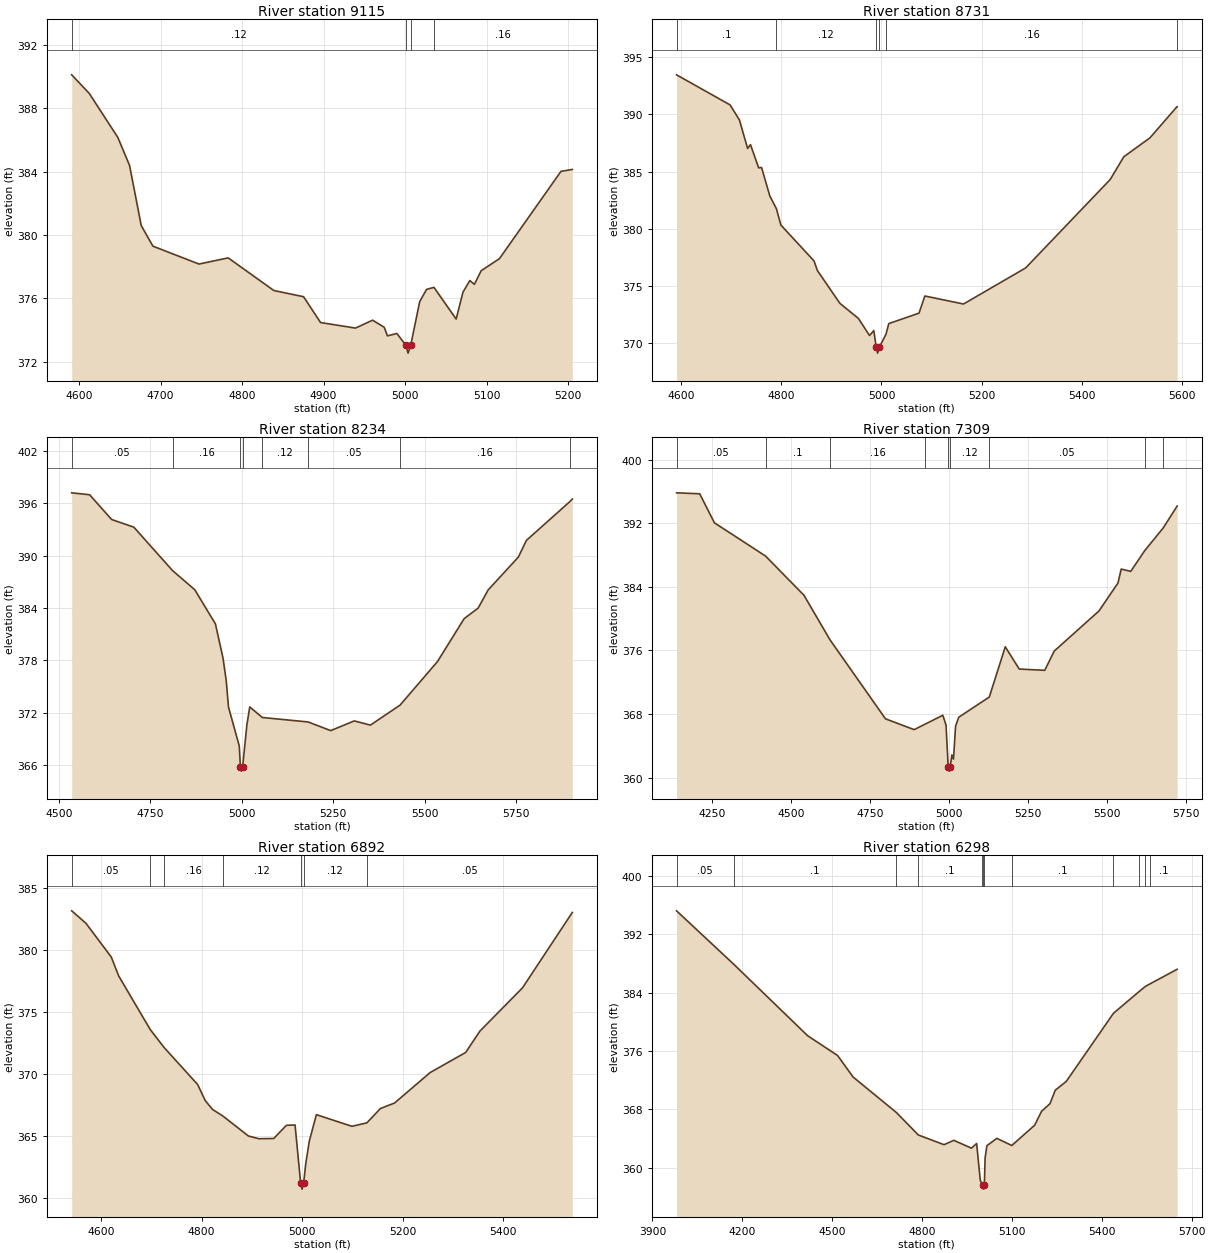
Type RM Length L Ch R = 1,9115,384,384,384
BEGIN DESCRIPTION:
UNT054 IN STEL 15.0
END DESCRIPTION:
XS GIS Cut Line= 3
      3522992.12     10467641.63      3522742.11     10467941.64
      3522642.12     10468141.61
#Sta/Elev= 30
  4591.0  390.11  4612.5  388.94  4647.6  386.16  4662.0  384.39  4676.3  380.60
  4690.6  379.30  4747.2  378.17  4783.0  378.56  4839.0  376.50  4875.4  376.11
  4896.3  374.48  4939.2  374.13  4960.1  374.63  4974.4  374.18  4978.3  373.64
  4989.9  373.79  5000.9  373.05  5003.6  372.55  5006.9  373.05  5017.9  375.80
  5026.3  376.57  5035.4  376.70  5062.6  374.70  5071.0  376.40  5079.4  377.13
  5085.0  376.89  5093.3  377.75  5115.7  378.51  5191.2  384.02  5205.1  384.14
#Mann=4,-1,0
  4591.0    0.12       0  5000.9    0.07       0  5006.9    0.12       0
  5035.4    0.16       0
Bank Sta=5000.9,5006.9
Exp/Cntr=0.3,0.1

Type RM Length L Ch R = 1,8731,497,497,497
BEGIN DESCRIPTION:
UNT054 IN STEL 14.0
END DESCRIPTION:
XS GIS Cut Line= 4
      3523033.81     10467519.06      3522915.73     10467505.17
      3522408.78     10467769.05      3522249.05     10468032.96
#Sta/Elev= 30
  4591.1  393.46  4698.0  390.83  4716.5  389.52  4732.9  387.03  4738.6  387.36
  4755.0  385.33  4760.7  385.37  4777.1  382.89  4790.5  381.75  4799.2  380.34
  4865.5  377.20  4871.9  376.38  4917.0  373.50  4954.0  372.18  4976.1  370.69
  4984.7  371.12  4989.5  369.65  4992.3  369.15  4995.5  369.65  5009.0  370.80
  5014.6  371.73  5074.8  372.64  5086.6  374.14  5163.7  373.44  5287.6  376.59
  5456.3  384.31  5483.5  386.30  5535.8  387.96  5589.5  390.67  5590.0  390.67
#Mann=6,-1,0
  4591.1     0.1       0  4790.5    0.12       0  4989.5    0.07       0
  4995.5    0.12       0  5009.0    0.16       0  5589.5     0.1       0
Bank Sta=4989.5,4995.5
Exp/Cntr=0.3,0.1

Type RM Length L Ch R = 1,8234,925,925,925
BEGIN DESCRIPTION:
UNT054 IN STEL 13.0
END DESCRIPTION:
XS GIS Cut Line= 4
      3523040.77     10467164.88      3522749.06     10467199.61
      3522283.78     10467532.94      3522047.86     10467977.03
#Sta/Elev= 30
  4535.2  397.18  4584.2  396.96  4644.6  394.12  4705.1  393.25  4810.9  388.28
  4871.8  386.08  4928.3  382.17  4949.2  378.21  4957.8  375.66  4964.0  372.64
  4993.4  368.20  4996.6  365.81  4999.3  365.31  5002.6  365.81  5014.3  370.61
  5022.1  372.66  5056.7  371.45  5181.8  370.94  5243.5  369.95  5307.9  371.06
  5352.1  370.58  5433.2  372.87  5535.7  377.87  5608.4  382.77  5646.7  383.98
  5674.3  386.07  5756.6  389.82  5778.6  391.73  5898.1  396.20  5904.2  396.47
#Mann=8,-1,0
  4535.2    0.05       0  4810.9    0.16       0  4996.6    0.07       0
  5002.6    0.16       0  5056.7    0.12       0  5181.8    0.05       0
  5433.2    0.16       0  5898.1    0.05       0
Bank Sta=4996.6,5002.6
Exp/Cntr=0.3,0.1

Type RM Length L Ch R = 1,7309,417,417,417
BEGIN DESCRIPTION:
UNT054 IN STEL 12.0
END DESCRIPTION:
XS GIS Cut Line= 3
      3522978.27     10466984.34      3522561.56     10466880.17
      3521416.37     10466741.35
#Sta/Elev= 30
  4137.9  395.83  4211.1  395.71  4257.6  392.06  4419.2  387.88  4540.9  382.94
  4623.1  377.34  4798.6  367.40  4889.2  366.04  4923.0  366.71  4979.9  367.85
  4990.0  366.63  4997.0  361.32  4999.8  360.82  5003.0  361.32  5008.6  362.86
  5013.7  362.33  5020.2  366.46  5030.2  367.60  5126.9  370.14  5177.4  376.46
  5221.6  373.66  5302.2  373.50  5332.4  375.93  5473.5  380.96  5533.9  384.49
  5544.0  386.24  5574.2  385.95  5617.9  388.53  5677.0  391.42  5721.0  394.17
#Mann=9,-1,0
  4137.9    0.05       0  4419.2     0.1       0  4623.1    0.16       0
  4923.0    0.12       0  4997.0    0.07       0  5003.0    0.12       0
  5126.9    0.05       0  5617.9     0.1       0  5677.0    0.05       0
Bank Sta=4997,5003
Exp/Cntr=0.3,0.1

Type RM Length L Ch R = 1,6892,594,594,594
BEGIN DESCRIPTION:
UNT054 IN STEL 11.0
END DESCRIPTION:
XS GIS Cut Line= 3
      3522642.12     10466741.65      3522292.11     10466491.64
      3521892.12     10466091.66
#Sta/Elev= 30
  4541.5  383.16  4569.8  382.16  4620.2  379.44  4634.9  377.92  4697.5  373.61
  4725.1  372.16  4792.2  369.16  4807.0  367.88  4821.7  367.16  4843.2  366.60
  4893.0  365.02  4913.9  364.80  4943.4  364.82  4968.6  365.88  4985.8  365.91
  4996.9  361.24  4999.7  360.74  5002.9  361.24  5007.0  362.77  5014.1  364.60
  5028.2  366.74  5098.9  365.80  5128.7  366.08  5155.5  367.23  5183.8  367.68
  5254.5  370.13  5325.2  371.75  5353.5  373.47  5438.3  376.96  5537.3  383.03
#Mann=7,-1,0
  4541.5    0.05       0  4697.5     0.1       0  4725.1    0.16       0
  4843.2    0.12       0  4996.9    0.07       0  5002.9    0.12       0
  5128.7    0.05       0
Bank Sta=4996.9,5002.9
Exp/Cntr=0.3,0.1

Type RM Length L Ch R = 1,6298,429,429,429
BEGIN DESCRIPTION:
UNT054 IN STEL 10.0
END DESCRIPTION:
XS GIS Cut Line= 4
      3523214.35     10466637.12      3522825.45     10466192.67
      3522068.50     10465838.50      3521826.25     10465873.11
#Sta/Elev= 30
  3980.7  395.24  4171.0  387.93  4418.4  378.09  4518.0  375.39  4570.0  372.43
  4714.4  367.56  4787.7  364.47  4873.6  363.14  4906.2  363.74  4965.0  362.66
  4982.3  363.30  4994.5  358.27  4998.8  357.86  5002.1  357.54  5004.9  357.04
  5008.1  357.54  5010.6  361.32  5016.6  363.00  5049.7  364.01  5099.7  363.03
  5176.0  365.81  5198.9  367.72  5227.2  368.77  5244.6  370.61  5281.6  371.83
  5438.9  381.17  5523.8  384.13  5545.4  384.86  5559.5  385.18  5651.7  387.22
#Mann=12,-1,0
  3980.7    0.05       0  4171.0     0.1       0  4714.4    0.12       0
  4787.7     0.1       0  4998.8    0.12       0  5002.1    0.07       0
  5008.1    0.12       0  5099.7     0.1       0  5438.9    0.05       0
  5523.8     0.1       0  5545.4    0.05       0  5559.5     0.1       0
Bank Sta=5002.1,5008.1
Exp/Cntr=0.3,0.1

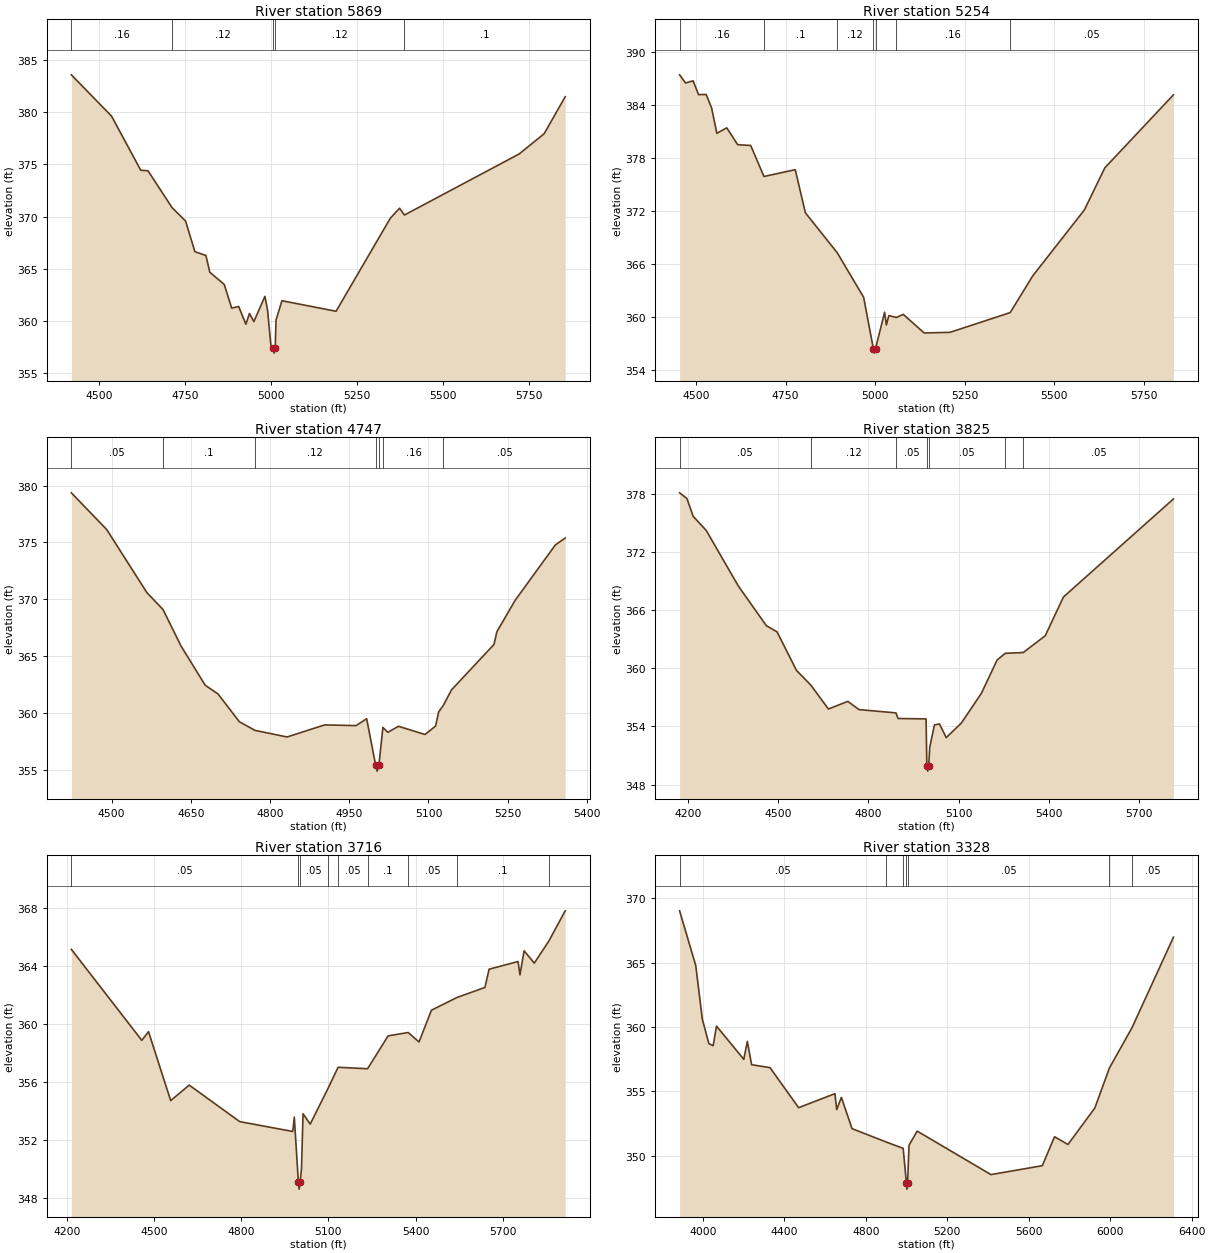
Type RM Length L Ch R = 1,5869,615,615,615
BEGIN DESCRIPTION:
UNT054 IN STEL 9.0
END DESCRIPTION:
XS GIS Cut Line= 4
      3523172.65     10465956.54      3523006.00     10465796.83
      3522221.28     10465546.83      3521853.24     10465651.00
#Sta/Elev= 30
  4419.6  383.58  4536.6  379.62  4621.5  374.44  4642.6  374.39  4712.6  370.86
  4752.0  369.57  4779.0  366.64  4811.2  366.27  4822.4  364.67  4864.4  363.50
  4886.1  361.23  4906.4  361.39  4927.4  359.69  4937.9  360.72  4950.6  359.94
  4982.8  362.36  4990.4  361.05  5000.8  357.46  5006.8  357.42  5009.5  356.92
  5012.8  357.42  5015.0  360.07  5032.3  361.94  5189.8  360.93  5347.6  369.84
  5374.6  370.80  5388.8  370.15  5722.6  376.00  5795.3  377.94  5856.5  381.48
#Mann=5,-1,0
  4419.6    0.16       0  4712.6    0.12       0  5006.8    0.07       0
  5012.8    0.12       0  5388.8     0.1       0
Bank Sta=5006.8,5012.8
Exp/Cntr=0.3,0.1

Type RM Length L Ch R = 1,5254,507,507,507
BEGIN DESCRIPTION:
UNT054 IN STEL 8.0
END DESCRIPTION:
XS GIS Cut Line= 3
      3523239.53     10465386.57      3522999.95     10465232.93
      3521911.45     10465133.97
#Sta/Elev= 30
  4454.4  387.39  4471.0  386.47  4492.1  386.71  4507.3  385.15  4528.5  385.17
  4543.7  383.65  4558.3  380.78  4586.0  381.40  4616.4  379.49  4652.7  379.41
  4689.7  375.90  4777.0  376.67  4805.3  371.80  4894.2  367.28  4967.8  362.25
  4994.9  356.44  4997.7  355.94  5000.9  356.44  5026.2  360.56  5031.2  359.13
  5038.1  360.18  5059.2  359.97  5078.3  360.32  5136.6  358.22  5208.8  358.29
  5376.6  360.52  5439.7  364.68  5583.5  372.12  5640.6  376.88  5832.0  385.13
#Mann=7,-1,0
  4454.4    0.16       0  4689.7     0.1       0  4894.2    0.12       0
  4994.9    0.07       0  5000.9    0.12       0  5059.2    0.16       0
  5376.6    0.05       0
Bank Sta=4994.9,5000.9
Exp/Cntr=0.3,0.1

Type RM Length L Ch R = 1,4747,922,922,922
BEGIN DESCRIPTION:
Mapping XS ca4fe94c
END DESCRIPTION:
XS GIS Cut Line= 2
      3523008.79     10464783.65      3522077.83     10464868.28
#Sta/Elev= 30
  4424.0  379.36  4491.0  376.13  4566.9  370.60  4597.6  369.10  4631.5  365.91
  4677.3  362.46  4701.8  361.68  4742.0  359.25  4771.6  358.49  4832.4  357.91
  4903.3  358.97  4962.9  358.91  4983.0  359.51  5000.1  355.41  5002.8  354.91
  5006.1  355.41  5013.7  358.75  5014.7  358.70  5023.1  358.32  5043.2  358.85
  5093.4  358.13  5113.5  358.87  5119.2  360.10  5128.4  360.71  5143.6  362.05
  5224.0  366.04  5229.6  367.17  5264.1  369.92  5340.1  374.78  5358.8  375.39
#Mann=7,-1,0
  4424.0    0.05       0  4597.6     0.1       0  4771.6    0.12       0
  5000.1    0.07       0  5006.1    0.12       0  5014.7    0.16       0
  5128.4    0.05       0
Bank Sta=5000.1,5006.1
Exp/Cntr=0.3,0.1

Type RM Length L Ch R = 1,3825,109,109,109
BEGIN DESCRIPTION:
Mapping XS cf99bbac
END DESCRIPTION:
XS GIS Cut Line= 5
      3523106.43     10464651.25      3522646.39     10464304.05
      3522448.91     10464221.58      3522142.92     10464375.66
      3521945.44     10464844.41
#Sta/Elev= 30
  4172.2  378.10  4196.4  377.52  4217.3  375.68  4260.9  374.21  4367.1  368.50
  4460.8  364.38  4496.2  363.75  4560.7  359.78  4608.6  358.25  4666.9  355.79
  4731.4  356.58  4768.6  355.73  4891.3  355.39  4898.5  354.81  4991.5  354.77
  4994.1  349.88  4996.9  349.38  5000.1  349.88  5003.8  351.87  5019.4  354.15
  5036.1  354.25  5058.5  352.84  5108.7  354.34  5175.6  357.42  5227.7  360.85
  5254.9  361.54  5314.7  361.62  5387.6  363.35  5448.1  367.35  5813.8  377.47
#Mann=7,-1,0
  4172.2    0.05       0  4608.6    0.12       0  4891.3    0.05       0
  4994.1    0.03       0  5000.1    0.05       0  5254.9     0.1       0
  5314.7    0.05       0
Bank Sta=4994.1,5000.1
Exp/Cntr=0.3,0.1

Type RM Length L Ch R = 1,3716,388,388,388
BEGIN DESCRIPTION:
Mapping XS 964525a0
END DESCRIPTION:
XS GIS Cut Line= 4
      3523065.13     10464378.79      3522455.29     10464119.69
      3522162.67     10464231.67      3521683.54     10464772.71
#Sta/Elev= 30
  4215.8  365.17  4458.1  358.89  4481.2  359.49  4557.5  354.73  4621.1  355.80
  4794.9  353.28  4977.3  352.60  4982.6  353.59  4996.6  349.12  4999.3  348.62
  5002.6  349.12  5007.3  350.01  5012.7  353.82  5037.4  353.11  5098.8  355.58
  5133.2  357.03  5234.7  356.93  5305.4  359.20  5374.2  359.43  5411.7  358.78
  5454.3  360.97  5542.2  361.85  5638.3  362.54  5652.6  363.80  5752.1  364.33
  5758.8  363.41  5773.0  365.07  5808.1  364.22  5858.0  365.74  5914.4  367.83
#Mann=9,-1,0
  4215.8    0.05       0  4996.6    0.03       0  5002.6    0.05       0
  5098.8     0.1       0  5133.2    0.05       0  5234.7     0.1       0
  5374.2    0.05       0  5542.2     0.1       0  5858.0    0.05       0
Bank Sta=4996.6,5002.6
Exp/Cntr=0.3,0.1

Type RM Length L Ch R = 1,3328,751,751,751
BEGIN DESCRIPTION:
Mapping XS b86d0fce
END DESCRIPTION:
XS GIS Cut Line= 4
      3523359.08     10464131.88      3522353.76     10463811.47
      3522115.66     10463814.41      3521583.61     10464813.85
#Sta/Elev= 30
  3885.1  369.02  3964.4  364.77  3996.6  360.61  4028.8  358.70  4049.9  358.54
  4066.3  360.06  4200.4  357.48  4217.8  358.87  4238.8  357.06  4329.2  356.83
  4469.7  353.72  4648.1  354.81  4656.6  353.57  4679.6  354.52  4732.1  352.09
  4898.3  351.06  4983.1  350.56  4998.9  347.89  5001.7  347.39  5004.9  347.89
  5011.9  350.80  5051.9  351.90  5414.1  348.52  5666.4  349.21  5726.6  351.46
  5792.5  350.86  5924.3  353.69  5996.3  356.81  6106.9  359.93  6310.6  366.97
#Mann=7,-1,0
  3885.1    0.05       0  4898.3     0.1       0  4983.1    0.05       0
  4998.9    0.03       0  5004.9    0.05       0  5996.3     0.1       0
  6106.9    0.05       0
Bank Sta=4998.9,5004.9
Exp/Cntr=0.3,0.1

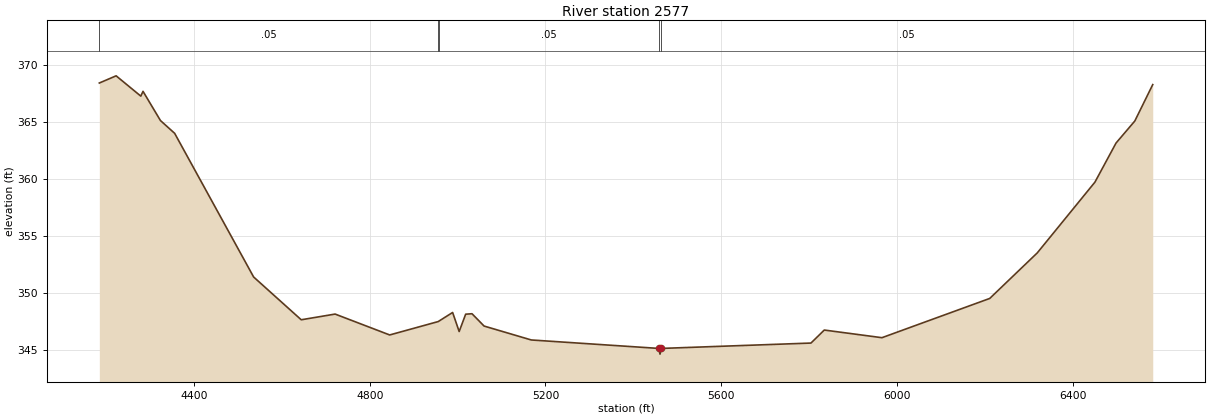
Type RM Length L Ch R = 1,2577,0,0,0
BEGIN DESCRIPTION:
UNT054 IN STEL 1.0
END DESCRIPTION:
XS GIS Cut Line= 4
      3522549.95     10463113.69      3521901.08     10463202.99
      3521642.40     10463576.31      3521466.04     10464852.01
#Sta/Elev= 30
  4184.8  368.44  4223.0  369.07  4279.2  367.29  4284.2  367.71  4323.9  365.15
  4356.2  364.03  4535.9  351.44  4644.2  347.69  4721.3  348.19  4845.5  346.36
  4956.5  347.54  4957.0  347.56  4988.7  348.33  5003.6  346.66  5018.4  348.18
  5032.8  348.22  5060.3  347.14  5167.8  345.92  5457.9  345.18  5460.6  344.68
  5463.9  345.18  5804.1  345.65  5834.4  346.79  5965.6  346.12  6210.9  349.56
  6319.0  353.55  6450.2  359.75  6498.3  363.18  6541.0  365.11  6581.8  368.30
#Mann=5,-1,0
  4184.8    0.05       0  4956.5    0.16       0  4957.0    0.05       0
  5457.9    0.03       0  5463.9    0.05       0
Bank Sta=5457.9,5463.9
Exp/Cntr=0.3,0.1

Chan Stop Cuts=-1