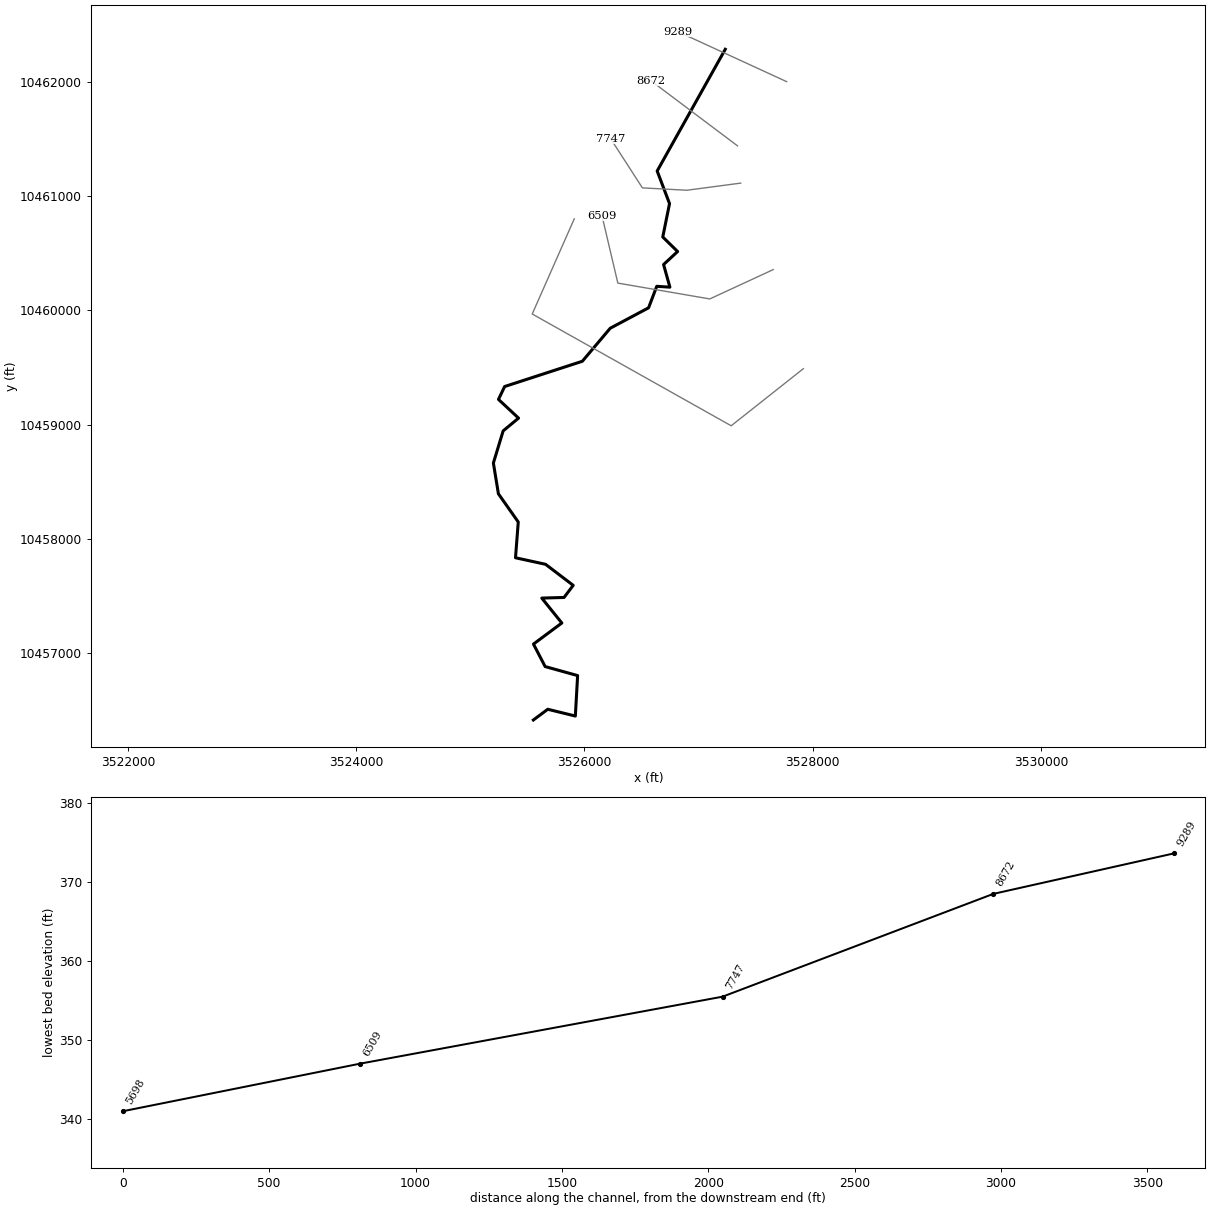
--- UNT060 IN STEL.prj (project) ---

Proj Title=UNT060 IN STEL Base Level Engineering
Current Plan=p01
Default Exp/Contr=0.3,0.1
English Units
Geom File=g01
Flow File=f01
Plan File=p01
Y Axis Title=Elevation
X Axis Title(PF)=Main Channel Distance
X Axis Title(XS)=Station
BEGIN DESCRIPTION:
UNT060 IN STEL
END DESCRIPTION:
DSS Export Rating Curves= 0
DSS Export Rating Curve Sorted= 0
DSS Export Volume Flow Curves= 0
DXF OffsetX= 0
DXF OffsetY= 0
DXF ScaleX= 1
DXF ScaleY= 10

--- UNT060 IN STEL.p01 (plan) ---

Plan Title=Multiple Run
Short Identifier=Multiple
Geom File=g01
Flow File=f01
Subcritical Flow
K Sum by GR= 0
Std Step Tol= 0.01
Critical Tol= 0.01
Num of Std Step Trials= 20
Max Error Tol= 0.3
Flow Tol Ratio= 0.001
Split Flow NTrial= 30
Split Flow Tol= 0.02
Split Flow Ratio= 0.02
Log Output Level= 0
Friction Slope Method= 1
Unsteady Friction Slope Method= 2
Unsteady Bridges Friction Slope Method= 1
Parabolic Critical Depth
Global Vel Dist=  1 , 1 , 1
Global Log Level= 0
CheckData=True
Encroach Param= -1, 0, 0, 0
BEGIN DESCRIPTION:
Multiple Run
END DESCRIPTION:

--- UNT060 IN STEL.f01 (steady flow) ---

Flow Title=Multiple
Number of Profiles=7
Profile Names=10-year,25-year,50-year,1pct_min,100-year,1pct_plu,500-year
River Rch & RM= UNT060 IN STEL,Reach-1,9289
     623     831     998     876    1185    1602    1663
Boundary for River Rch & Prof#=UNT060 IN STEL,Reach-1,1
Up Type=0
Dn Type=3
Dn Slope=0.005
Boundary for River Rch & Prof#=UNT060 IN STEL,Reach-1,2
Up Type=0
Dn Type=3
Dn Slope=0.005
Boundary for River Rch & Prof#=UNT060 IN STEL,Reach-1,3
Up Type=0
Dn Type=3
Dn Slope=0.005
Boundary for River Rch & Prof#=UNT060 IN STEL,Reach-1,4
Up Type=0
Dn Type=3
Dn Slope=0.005
Boundary for River Rch & Prof#=UNT060 IN STEL,Reach-1,5
Up Type=0
Dn Type=3
Dn Slope=0.005
Boundary for River Rch & Prof#=UNT060 IN STEL,Reach-1,6
Up Type=0
Dn Type=3
Dn Slope=0.005
Boundary for River Rch & Prof#=UNT060 IN STEL,Reach-1,7
Up Type=0
Dn Type=3
Dn Slope=0.005

--- UNT060 IN STEL.g01 (geometry) ---

Geom Title=Existing Conditions
Program Version=4.10

River Reach=UNT060 IN STEL  ,Reach-1
Reach XY= 30
      3527233.23     10462287.48      3526636.72     10461221.23
      3526744.96     10460935.47      3526685.77     10460642.98
       3526815.8      10460515.6      3526692.89     10460401.82
      3526748.08     10460203.49        3526633.       10460211.
      3526561.36     10460022.58      3526225.58     10459843.77
      3525980.96     10459554.25      3525300.43     10459332.94
      3525246.53     10459220.25      3525422.34     10459056.18
      3525287.46     10458944.45      3525201.83       10458663.
      3525245.85     10458393.19      3525419.79     10458146.13
      3525395.57     10457832.97      3525658.87     10457775.66
      3525901.15     10457591.29      3525820.68     10457485.11
      3525625.71     10457479.67      3525801.49      10457261.4
      3525552.94     10457076.76      3525655.32     10456879.68
      3525939.84     10456800.74      3525919.81     10456446.33
      3525678.15     10456505.69      3525552.11     10456411.64

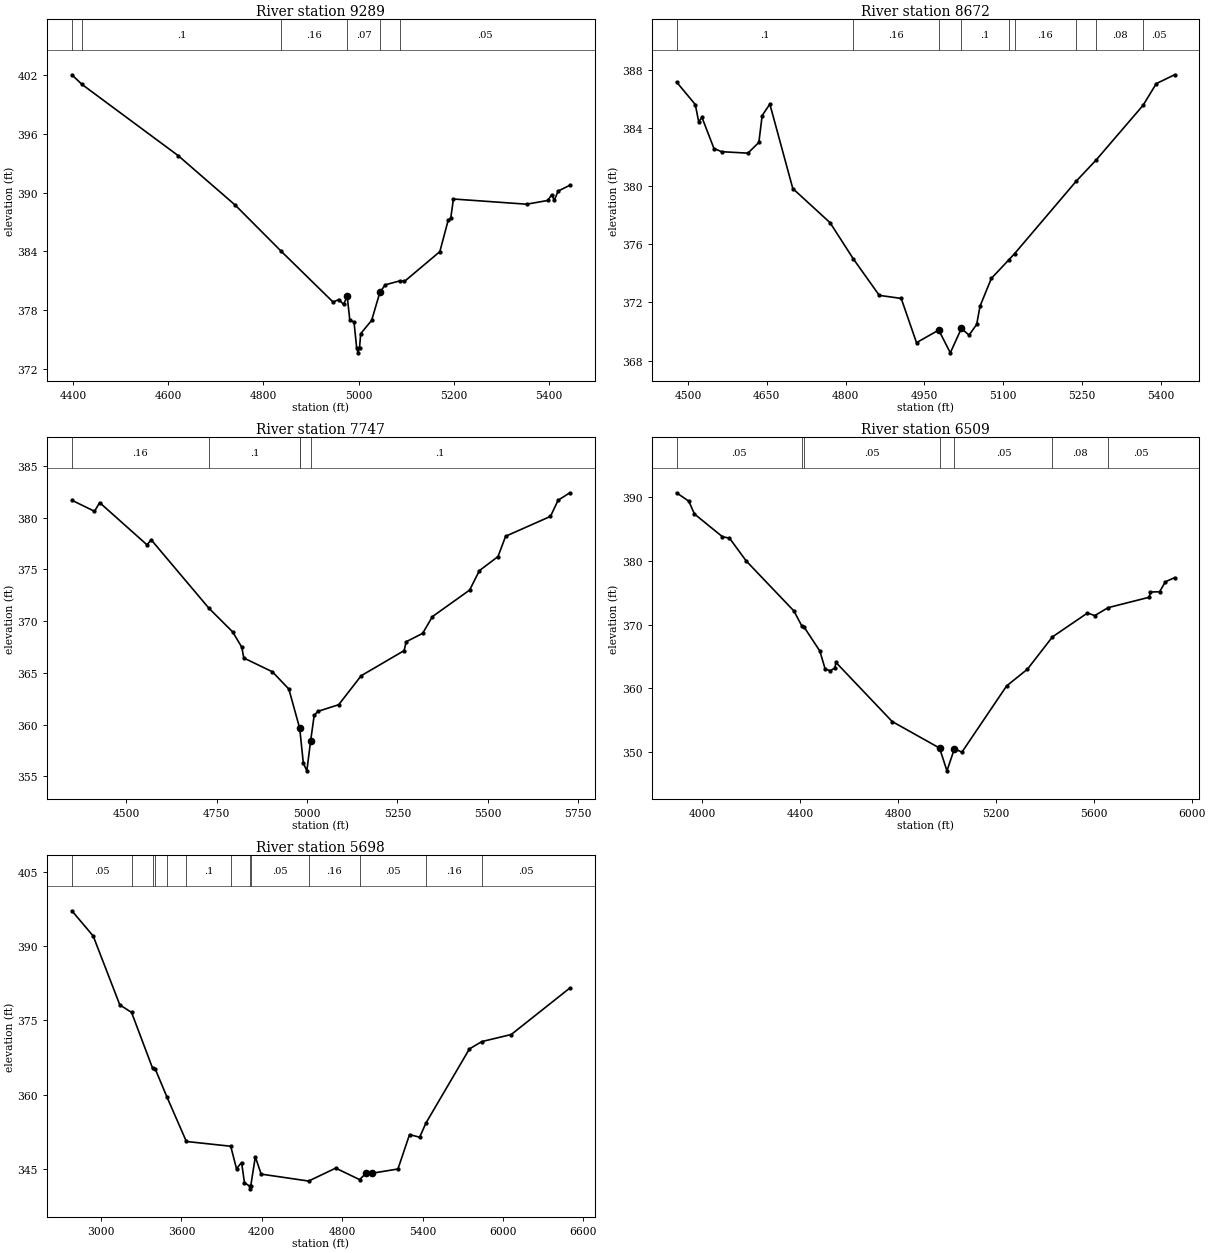
Type RM Length L Ch R = 1 ,9289    ,617,617,617
BEGIN DESCRIPTION:
UNT060 IN STEL 11.0
END DESCRIPTION:
XS GIS Cut Line= 2
      3527771.15     10462003.84      3526819.73     10462441.36
#Sta/Elev= 30
  4397.2  402.01  4418.4  401.03  4620.6  393.77  4740.9  388.71  4837.2  384.02
  4946.5  378.83  4958.7  379.09  4968.5  378.59  4976.2  379.41  4981.7  376.99
  4990.5   376.8  4996.1  374.15  4998.9  373.65  5002.1  374.15  5004.6  375.61
  5027.6  376.96  5045.1  379.85  5056.5  380.59  5086.8  380.99  5096.5  380.93
    5171  383.97  5188.4  387.15  5193.9  387.38  5199.6  389.34  5353.7  388.81
  5397.8  389.19  5406.2  389.77  5411.7  389.21  5419.8  390.15  5444.4  390.74
#Mann= 6 ,-1 , 0
  4397.2     .05       0  4418.4      .1       0  4837.2     .16       0
  4976.2     .07       0  5045.1     .16       0  5086.8     .05       0
Bank Sta=4976.2,5045.1
XS Rating Curve= 0 ,0
Exp/Cntr=0.3,0.1

Type RM Length L Ch R = 1 ,8672    ,925,925,925
BEGIN DESCRIPTION:
UNT060 IN STEL 10.0
END DESCRIPTION:
XS GIS Cut Line= 2
      3527340.59     10461441.33      3526583.59     10462010.82
#Sta/Elev= 30
  4478.5  387.19  4514.1  385.64  4520.5  384.46  4526.8  384.75  4549.6  382.61
  4564.2  382.39  4614.2  382.29    4635  383.03  4641.3  384.88  4655.9  385.67
  4699.6  379.85  4770.4   377.5  4814.8     375  4864.1  372.49  4905.8  372.28
  4934.9  369.23  4977.2   370.1  4999.2  368.53  5020.3  370.21  5034.9  369.75
  5049.4  370.49  5055.7  371.74  5077.3  373.66  5111.1  374.96  5121.6  375.37
  5238.5  380.35  5276.7  381.82    5366  385.59    5391  387.08  5425.8  387.69
#Mann= 9 ,-1 , 0
  4478.5      .1       0  4814.8     .16       0  4977.2     .05       0
  5020.3      .1       0  5111.1     .05       0  5121.6     .16       0
  5238.5     .05       0  5276.7     .08       0    5366     .05       0
Bank Sta=4977.2,5020.3
XS Rating Curve= 0 ,0
Exp/Cntr=0.3,0.1

Type RM Length L Ch R = 1 ,7747    ,1238,1238,1238
BEGIN DESCRIPTION:
UNT060 IN STEL 8.0
END DESCRIPTION:
XS GIS Cut Line= 4
      3527368.33     10461114.97      3526896.12     10461052.47
      3526507.23      10461073.3      3526229.43     10461503.89
#Sta/Elev= 30
  4349.2  381.67  4411.8   380.6  4426.1  381.44  4557.2  377.36  4568.7  377.85
  4728.7  371.23    4794  368.96  4819.5  367.47    4825  366.43  4904.1   365.1
  4949.7  363.43  4979.8  359.63  4989.8  356.27  4999.5  355.53  5009.8  358.38
  5019.8  360.88  5029.8  361.27  5087.7  361.92    5150  364.72  5268.6  367.14
  5274.5     368    5320  368.81  5347.1  370.43    5450  372.99  5477.1  374.87
  5528.6  376.23  5549.7  378.19  5673.8  380.11  5694.9  381.67  5727.4  382.39
#Mann= 5 ,-1 , 0
  4349.2     .16       0  4728.7      .1       0  4979.8     .05       0
  4979.8     .05       0  5009.8      .1       0
Bank Sta=4979.8,5009.8
XS Rating Curve= 0 ,0
Exp/Cntr=0.3,0.1

Type RM Length L Ch R = 1 ,6509    ,811,811,811
BEGIN DESCRIPTION:
UNT060 IN STEL 5.0
END DESCRIPTION:
XS GIS Cut Line= 4
      3527653.23     10460357.24      3527097.65     10460100.28
       3526292.1     10460239.17      3526153.54     10460828.03
#Sta/Elev= 30
  3895.7  390.74  3945.6  389.42  3968.6  387.41  4083.2  383.83  4111.7  383.62
  4180.4  380.02  4374.9  372.18  4406.7  369.87  4416.5  369.65  4480.9  365.89
  4502.6  363.06  4523.6  362.78    4542  363.22  4547.1  364.08  4776.4  354.81
  4970.1  350.64  5000.3  347.06    5031  350.55  5061.4  349.99  5244.1   360.4
  5329.1  363.03  5431.5  368.11  5574.4  371.85  5604.5  371.45  5658.4  372.69
  5826.7  374.33  5831.8  375.15  5869.1  375.19  5892.8  376.76  5930.2   377.4
#Mann= 7 ,-1 , 0
  3895.7     .05       0  4406.7     .16       0  4416.5     .05       0
  4970.1    .035       0    5031     .05       0  5431.5     .08       0
  5658.4     .05       0
Bank Sta=4970.1,5031
XS Rating Curve= 0 ,0
Exp/Cntr=0.3,0.1

Type RM Length L Ch R = 1 ,5698    ,0,0,0
BEGIN DESCRIPTION:
UNT060 IN STEL 1.0
END DESCRIPTION:
XS GIS Cut Line= 4
      3527917.09     10459489.17      3527285.15     10458989.17
       3525542.1     10459968.34      3525910.17      10460801.7
#Sta/Elev= 30
  2782.7  397.11  2941.8  392.02  3140.5  378.13  3228.2  376.61  3385.2  365.35
  3403.5  365.29    3492  359.57    3637  350.59  3968.1  349.63  4011.4  345.09
    4049  346.35  4070.7  342.29  4111.1  341.54  4113.8  341.04  4117.1  341.54
  4151.7  347.51    4195  344.01  4549.2  342.61  4751.7  345.22  4929.6   342.9
  4979.9  344.23  5025.7   344.2  5215.9  345.04  5302.6  351.98  5377.9  351.45
    5425  354.31  5749.3  369.25  5841.6  370.73  6061.5  372.16  6498.8  381.53
#Mann= 13 ,-1 , 0
  2782.7     .05       0  3228.2      .1       0  3385.2     .05       0
  3403.5      .1       0    3492     .05       0    3637      .1       0
  3968.1     .05       0  4111.1     .03       0  4117.1     .05       0
  4549.2     .16       0  4929.6     .05       0    5425     .16       0
  5841.6     .05       0
Bank Sta=4979.9,5025.7
XS Rating Curve= 0 ,0
Exp/Cntr=0.3,0.1

Chan Stop Cuts=-1
Use User Specified Reach Order=0
Composite Channel Slope=5