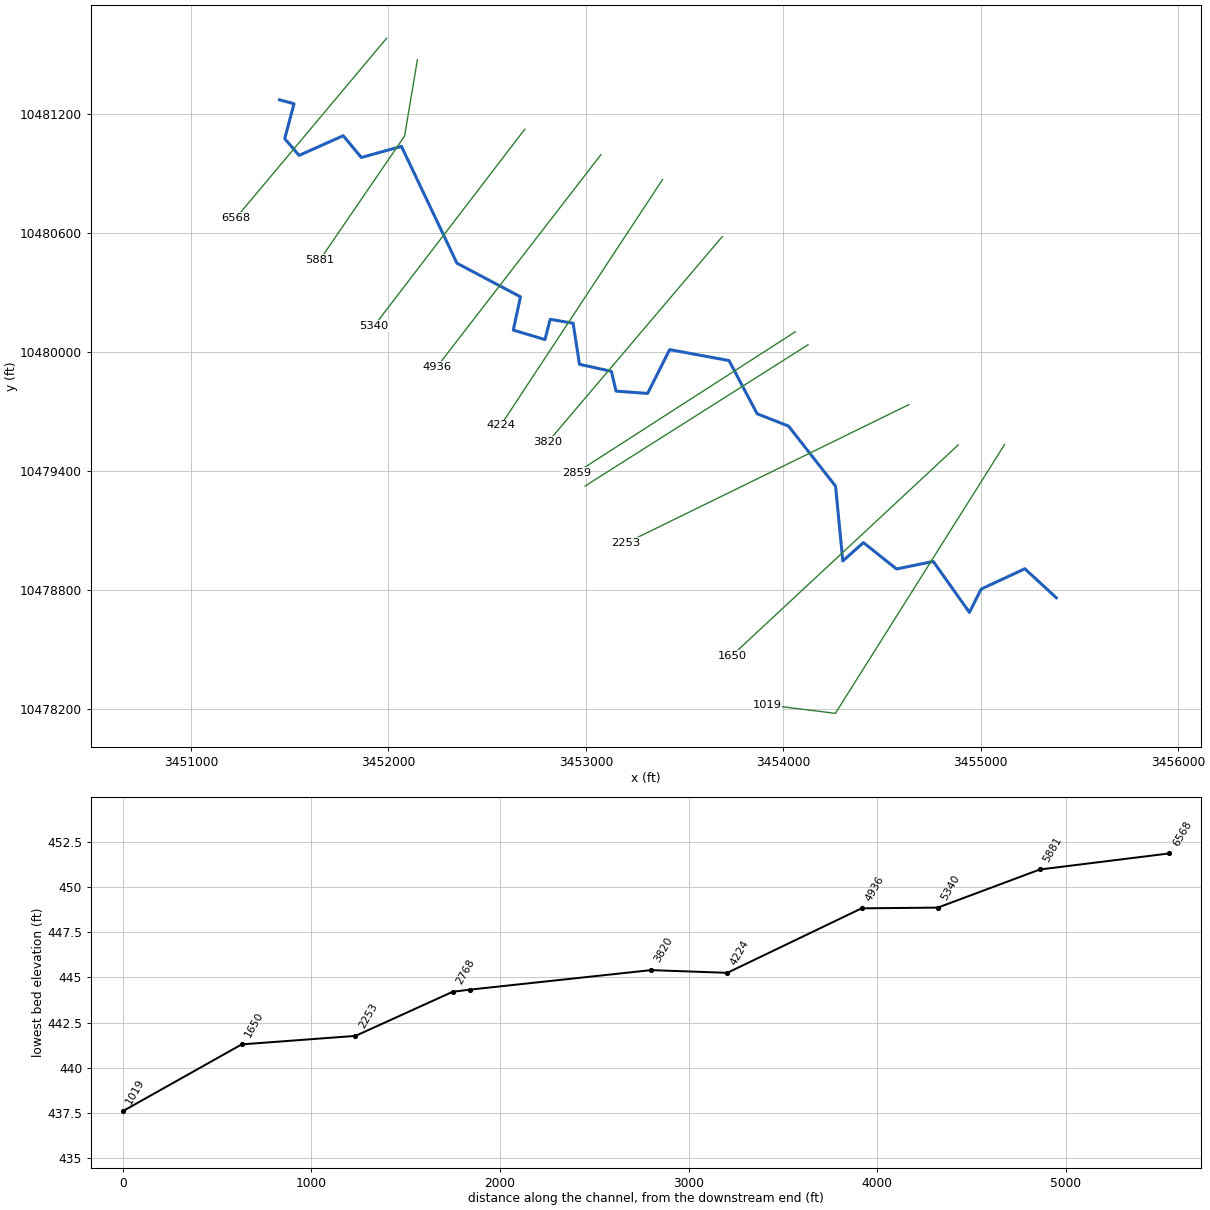
--- UNT061 IN STEL.prj (project) ---

Proj Title=UNT061 IN STEL Base Level Engineering
Current Plan=p01
Default Exp/Contr=0.3,0.1
English Units
Geom File=g01
Flow File=f01
Plan File=p01
BEGIN DESCRIPTION:
UNT061 IN STEL
END DESCRIPTION:

--- UNT061 IN STEL.p01 (plan) ---

Plan Title=Multiple Run
Short Identifier=Multiple
Geom File=g01
Flow File=f01
Subcritical Flow
K Sum by GR= 0
Std Step Tol= 0.01
Critical Tol= 0.01
Num of Std Step Trials= 20
Max Error Tol= 0.3
Flow Tol Ratio= 0.001
Split Flow NTrial= 30
Split Flow Tol= 0.02
Split Flow Ratio= 0.02
Log Output Level= 0
Friction Slope Method= 1
Unsteady Friction Slope Method= 2
Unsteady Bridges Friction Slope Method= 1
Parabolic Critical Depth
Global Vel Dist=  1 , 1 , 1
Global Log Level= 0
CheckData=True
Encroach Param= -1, 0, 0, 0
BEGIN DESCRIPTION:
Multiple Run
END DESCRIPTION:

--- UNT061 IN STEL.f01 (steady flow) ---

Flow Title=Multiple
Number of Profiles=7
Profile Names=10-year,25-year,50-year,1pct_min,100-year,1pct_plu,500-year
River Rch & RM= UNT061 IN STEL,Reach-1,6568
    1577    2220    2761    2500    3381    4573    5064
Boundary for River Rch & Prof#=UNT061 IN STEL,Reach-1,1
Up Type=0
Dn Type=3
Dn Slope=0.005
Boundary for River Rch & Prof#=UNT061 IN STEL,Reach-1,2
Up Type=0
Dn Type=3
Dn Slope=0.005
Boundary for River Rch & Prof#=UNT061 IN STEL,Reach-1,3
Up Type=0
Dn Type=3
Dn Slope=0.005
Boundary for River Rch & Prof#=UNT061 IN STEL,Reach-1,4
Up Type=0
Dn Type=3
Dn Slope=0.005
Boundary for River Rch & Prof#=UNT061 IN STEL,Reach-1,5
Up Type=0
Dn Type=3
Dn Slope=0.005
Boundary for River Rch & Prof#=UNT061 IN STEL,Reach-1,6
Up Type=0
Dn Type=3
Dn Slope=0.005
Boundary for River Rch & Prof#=UNT061 IN STEL,Reach-1,7
Up Type=0
Dn Type=3
Dn Slope=0.005

--- UNT061 IN STEL.g01 (geometry) ---

Geom Title=Existing Conditions

River Reach=UNT061 IN STEL,Reach-1
Reach XY= 30
      3451448.84     10481272.96      3451521.75     10481253.17
      3451474.62     10481077.32      3451547.54     10480992.78
      3451770.89     10481092.10      3451862.40     10480982.21
      3452065.70     10481038.37      3452346.94     10480448.97
      3452668.58     10480279.57      3452632.10     10480111.80
      3452792.55     10480063.88      3452818.96     10480166.18
      3452935.12     10480146.17      3452967.40     10479939.05
      3453128.92     10479903.85      3453152.49     10479803.90
      3453312.20     10479792.25      3453424.04     10480013.16
      3453724.56     10479957.95      3453867.00     10479689.76
      3454026.02     10479627.63      3454264.14     10479324.62
      3454300.91     10478947.25      3454405.29     10479039.73
      3454573.00     10478906.91      3454758.94     10478944.93
      3454942.17     10478687.93      3455001.44     10478805.56
      3455222.93     10478907.95      3455382.11     10478761.64

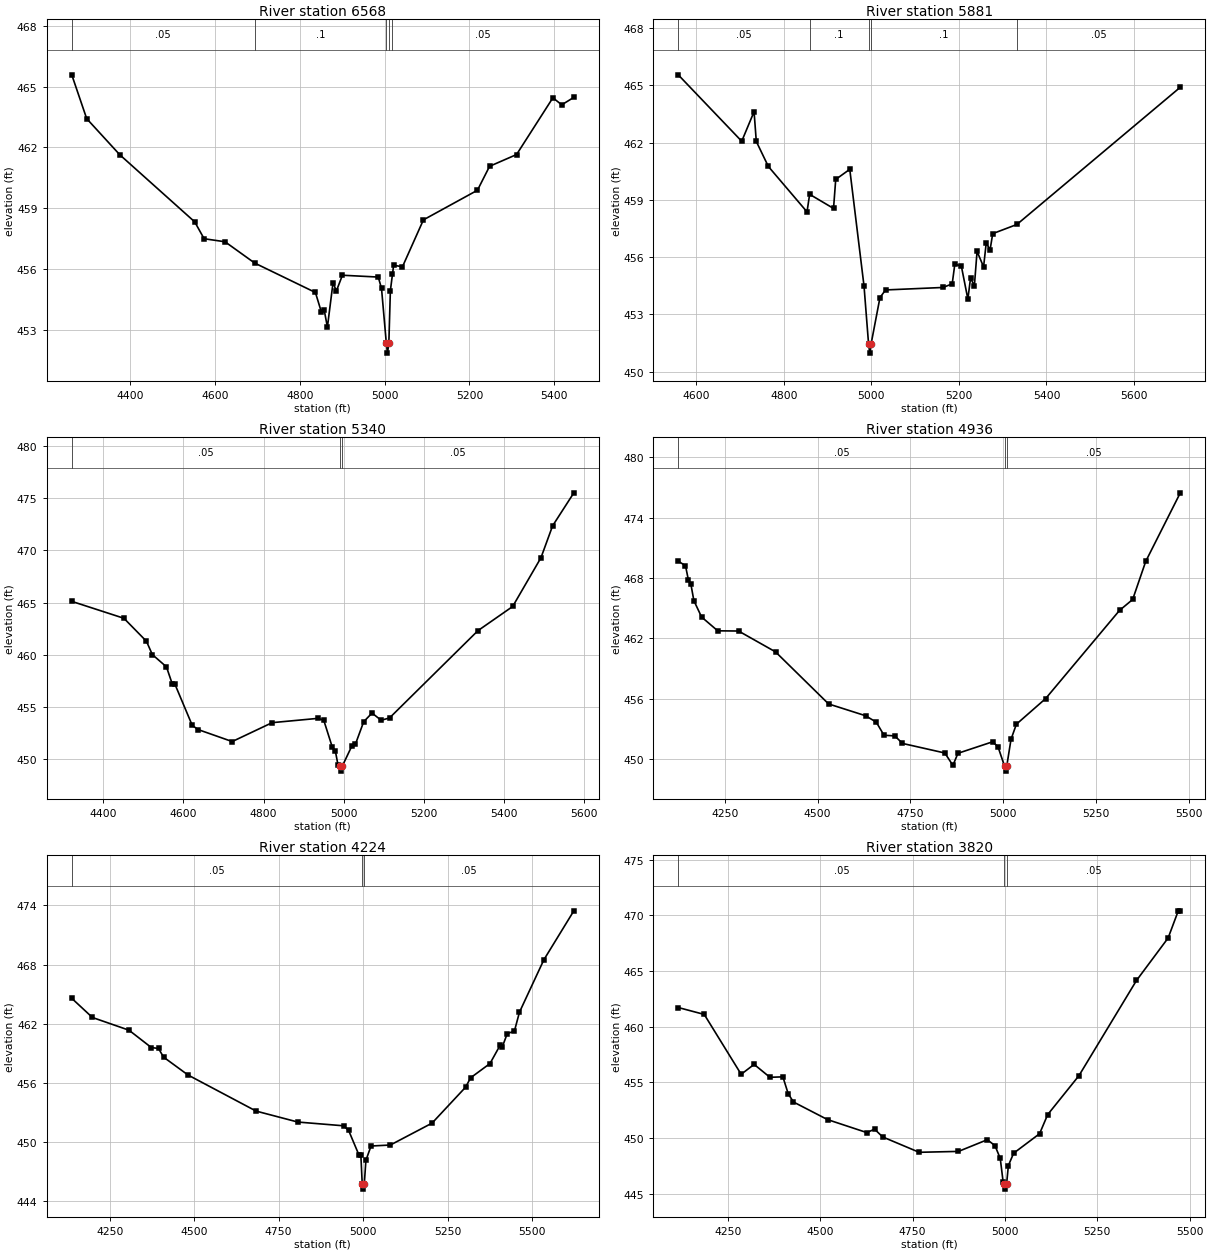
Type RM Length L Ch R = 1,6568,687,687,687
BEGIN DESCRIPTION:
UNT061 IN STEL 8.0
END DESCRIPTION:
XS GIS Cut Line= 2
      3451990.15     10481583.20      3451227.05     10480676.74
#Sta/Elev= 30
  4261.5  465.58  4296.7  463.42  4374.8  461.64  4551.7  458.33  4573.8  457.50
  4623.2  457.35  4693.2  456.30  4836.5  454.85  4850.8  453.87  4857.3  453.98
  4864.8  453.14  4878.1  455.34  4885.9  454.92  4900.2  455.70  4984.8  455.61
  4992.5  455.05  5003.8  452.36  5006.6  451.86  5009.8  452.36  5013.4  454.94
  5018.3  455.74  5021.1  456.19  5042.0  456.12  5091.4  458.43  5218.9  459.89
  5247.5  461.07  5311.2  461.65  5397.0  464.45  5417.8  464.10  5446.4  464.47
#Mann=5,-1,0
  4261.5    0.05       0  4693.2     0.1       0  5003.8    0.07       0
  5009.8     0.1       0  5018.3    0.05       0
Bank Sta=5003.8,5009.8
Exp/Cntr=0.3,0.1

Type RM Length L Ch R = 1,5881,541,541,541
BEGIN DESCRIPTION:
Mapping XS 171e2476
END DESCRIPTION:
XS GIS Cut Line= 3
      3452146.38     10481474.68      3452081.62     10481090.32
      3451652.70     10480465.81
#Sta/Elev= 30
  4558.5  465.55  4703.6  462.07  4731.8  463.62  4736.9  462.06  4764.4  460.75
  4852.8  458.37  4858.8  459.29  4913.4  458.55  4918.4  460.07  4950.5  460.60
  4983.1  454.48  4993.4  451.47  4996.2  450.97  4999.4  451.47  5019.5  453.88
  5032.3  454.28  5163.6  454.41  5184.6  454.60  5190.6  455.63  5205.5  455.53
  5220.4  453.80  5226.5  454.90  5235.3  454.50  5241.4  456.30  5256.3  455.49
  5262.3  456.73  5271.2  456.39  5277.2  457.23  5332.4  457.71  5705.9  464.90
#Mann=5,-1,0
  4558.5    0.05       0  4858.8     0.1       0  4993.4    0.07       0
  4999.4     0.1       0  5332.4    0.05       0
Bank Sta=4993.4,4999.4
Exp/Cntr=0.3,0.1

Type RM Length L Ch R = 1,5340,404,404,404
BEGIN DESCRIPTION:
Mapping XS f395925e
END DESCRIPTION:
XS GIS Cut Line= 2
      3452690.38     10481124.79      3451926.78     10480132.11
#Sta/Elev= 30
  4321.3  465.11  4451.4  463.49  4507.6  461.29  4522.2  460.02  4557.5  458.84
  4572.0  457.20  4578.3  457.21  4621.8  453.24  4636.3  452.84  4721.5  451.69
  4821.2  453.50  4935.3  453.91  4949.8  453.74  4970.7  451.21  4978.9  450.76
  4985.2  449.49  4990.4  449.36  4993.1  448.86  4996.4  449.36  5020.5  451.31
  5028.7  451.42  5049.5  453.59  5070.3  454.42  5093.0  453.73  5113.9  453.95
  5334.6  462.31  5421.1  464.62  5491.7  469.29  5520.7  472.34  5573.7  475.50
#Mann=3,-1,0
  4321.3    0.05       0  4990.4    0.03       0  4996.4    0.05       0
Bank Sta=4990.4,4996.4
Exp/Cntr=0.3,0.1

Type RM Length L Ch R = 1,4936,712,712,712
BEGIN DESCRIPTION:
Mapping XS 5eec62ac
END DESCRIPTION:
XS GIS Cut Line= 2
      3453075.76     10480996.27      3452246.49     10479927.58
#Sta/Elev= 30
  4124.7  469.66  4144.2  469.22  4152.3  467.76  4158.7  467.40  4166.8  465.75
  4187.6  464.12  4231.1  462.75  4287.2  462.73  4386.8  460.66  4529.8  455.49
  4629.4  454.32  4658.3  453.68  4679.1  452.38  4708.1  452.32  4728.9  451.57
  4843.0  450.62  4864.7  449.39  4878.3  450.59  4971.5  451.73  4986.0  451.26
  5003.8  449.32  5006.6  448.82  5009.8  449.32  5021.3  451.98  5035.8  453.48
  5114.5  456.02  5313.7  464.78  5349.0  465.86  5384.3  469.65  5477.4  476.45
#Mann=3,-1,0
  4124.7    0.05       0  5003.8    0.03       0  5009.8    0.05       0
Bank Sta=5003.8,5009.8
Exp/Cntr=0.3,0.1

Type RM Length L Ch R = 1,4224,404,404,404
BEGIN DESCRIPTION:
Mapping XS ae8c8de6
END DESCRIPTION:
XS GIS Cut Line= 2
      3453388.29     10480871.30      3452568.82     10479631.68
#Sta/Elev= 30
  4137.9  464.59  4198.9  462.65  4307.3  461.36  4373.5  459.60  4394.6  459.51
  4409.6  458.63  4481.9  456.82  4683.5  453.16  4806.9  452.05  4942.3  451.67
  4957.3  451.20  4987.5  448.74  4993.5  448.71  4997.6  445.75  5000.3  445.25
  5003.6  445.75  5008.5  448.17  5023.6  449.62  5080.8  449.72  5204.2  451.94
  5303.4  455.58  5318.5  456.54  5375.7  457.98  5405.8  459.84  5411.8  459.63
  5426.8  461.02  5447.9  461.26  5463.0  463.19  5535.2  468.50  5623.9  473.46
#Mann=3,-1,0
  4137.9    0.05       0  4997.6    0.03       0  5003.6    0.05       0
Bank Sta=4997.6,5003.6
Exp/Cntr=0.3,0.1

Type RM Length L Ch R = 1,3820,961,961,961
BEGIN DESCRIPTION:
Mapping XS 654cc113
END DESCRIPTION:
XS GIS Cut Line= 2
      3453690.36     10480583.09      3452808.40     10479548.35
#Sta/Elev= 30
  4115.2  461.72  4185.6  461.10  4285.6  455.72  4320.7  456.61  4363.5  455.45
  4398.6  455.49  4412.9  453.98  4427.2  453.23  4519.4  451.65  4626.0  450.48
  4646.8  450.79  4668.8  450.09  4767.6  448.71  4874.1  448.79  4952.1  449.84
  4972.9  449.31  4987.2  448.16  4994.9  446.07  4998.5  445.90  5001.2  445.40
  5004.5  445.90  5009.2  447.52  5023.5  448.63  5093.7  450.38  5115.7  452.10
  5200.2  455.59  5356.1  464.15  5441.8  467.97  5469.3  470.41  5474.8  470.41
#Mann=3,-1,0
  4115.2    0.05       0  4998.5    0.03       0  5004.5    0.05       0
Bank Sta=4998.5,5004.5
Exp/Cntr=0.3,0.1

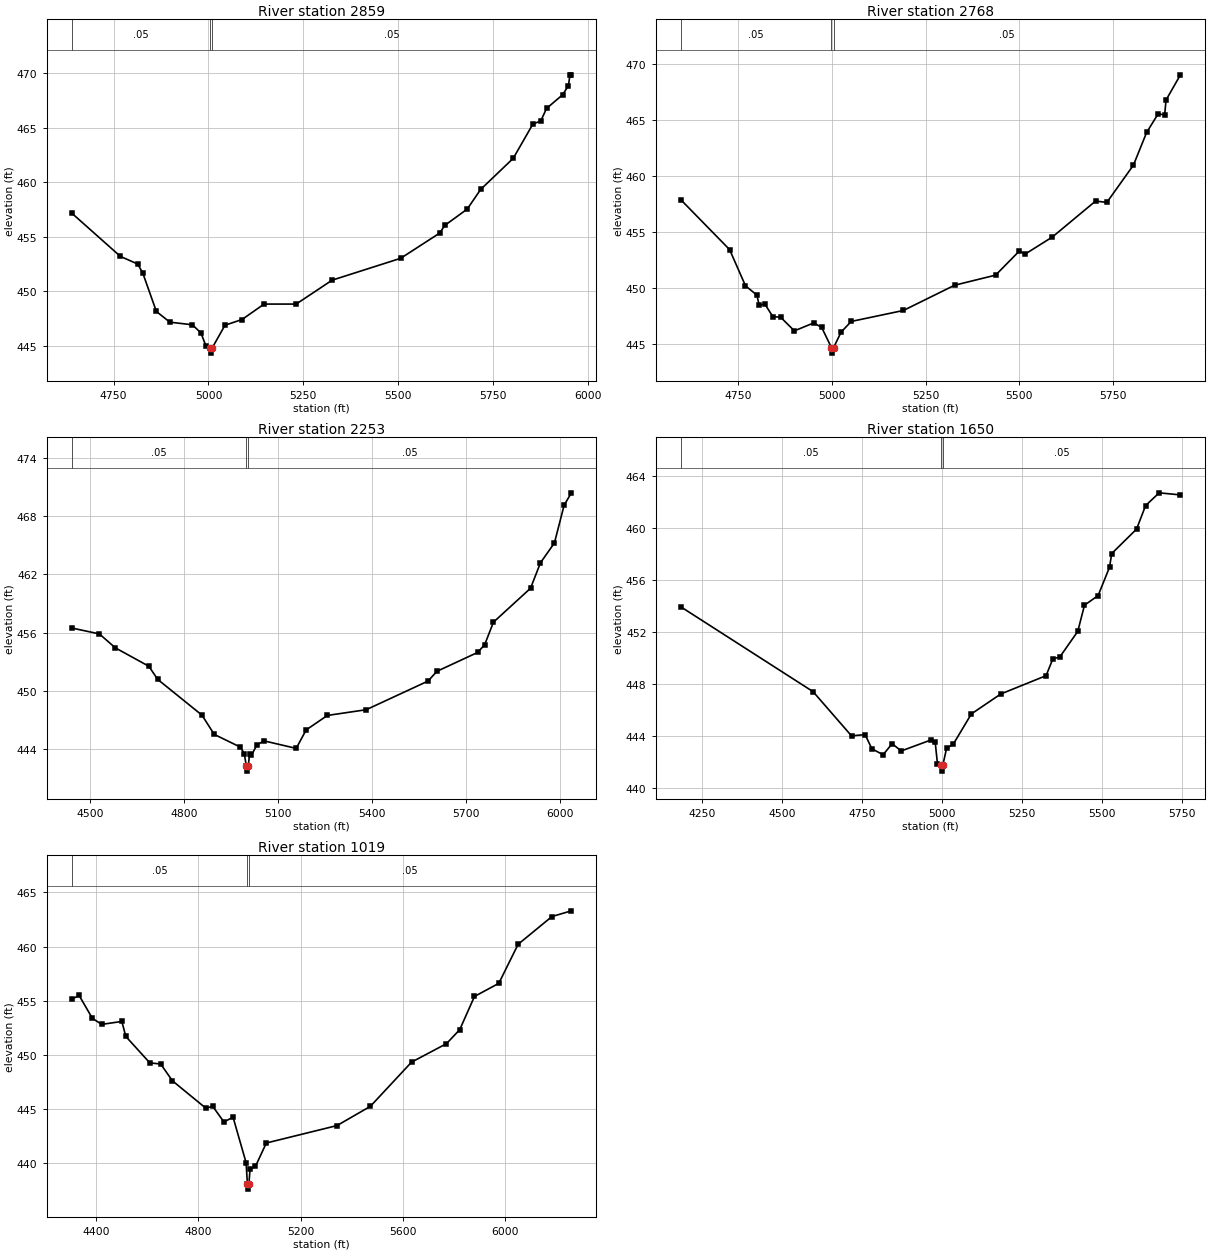
Type RM Length L Ch R = 1,2859,91,91,91
BEGIN DESCRIPTION:
Mapping XS 52d4bdca
END DESCRIPTION:
XS GIS Cut Line= 2
      3454060.17     10480103.07      3452950.82     10479392.15
#Sta/Elev= 30
  4639.2  457.17  4767.9  453.19  4813.5  452.49  4826.9  451.65  4862.6  448.14
  4898.2  447.16  4957.6  446.92  4980.1  446.17  4993.2  444.98  5004.1  444.82
  5006.9  444.32  5010.1  444.82  5043.5  446.88  5088.2  447.40  5146.6  448.82
  5231.2  448.82  5325.8  451.01  5506.8  453.02  5609.9  455.34  5622.7  456.03
  5682.1  457.53  5717.7  459.34  5803.5  462.19  5855.1  465.32  5876.2  465.63
  5891.4  466.77  5933.7  468.02  5948.9  468.85  5953.1  469.85  5956.8  469.85
#Mann=3,-1,0
  4639.2    0.05       0  5004.1    0.03       0  5010.1    0.05       0
Bank Sta=5004.1,5010.1
Exp/Cntr=0.3,0.1

Type RM Length L Ch R = 1,2768,515,515,515
BEGIN DESCRIPTION:
Mapping XS 8306738b
END DESCRIPTION:
XS GIS Cut Line= 3
      3454125.24     10480037.95      3453031.51     10479347.86
      3452996.05     10479325.06
#Sta/Elev= 30
  4595.6  457.92  4726.3  453.45  4768.7  450.22  4799.3  449.38  4805.2  448.49
  4820.5  448.58  4841.7  447.47  4862.9  447.40  4899.4  446.19  4951.1  446.90
  4972.3  446.50  4998.3  444.70  5001.1  444.20  5004.3  444.70  5024.1  446.07
  5051.2  447.03  5190.5  448.01  5327.7  450.27  5437.1  451.17  5500.7  453.33
  5516.0  453.05  5588.9  454.58  5704.3  457.79  5734.4  457.67  5805.4  461.00
  5840.8  463.93  5871.4  465.58  5888.8  465.49  5892.6  466.82  5931.0  469.07
#Mann=3,-1,0
  4595.6    0.05       0  4998.3    0.04       0  5004.3    0.05       0
Bank Sta=4998.3,5004.3
Exp/Cntr=0.3,0.1

Type RM Length L Ch R = 1,2253,603,603,603
BEGIN DESCRIPTION:
Mapping XS fd94b155
END DESCRIPTION:
XS GIS Cut Line= 2
      3454635.64     10479735.86      3453203.43     10479037.98
#Sta/Elev= 30
  4442.0  456.49  4530.4  455.88  4581.1  454.45  4688.2  452.55  4716.3  451.20
  4857.5  447.52  4896.6  445.54  4979.9  444.23  4992.3  443.56  4999.1  442.26
  5001.9  441.76  5005.1  442.26  5009.3  443.54  5014.9  443.37  5031.9  444.42
  5054.4  444.88  5157.9  444.10  5189.6  446.00  5257.2  447.49  5381.1  448.08
  5578.3  451.03  5606.4  452.03  5736.1  453.97  5758.6  454.76  5786.8  457.09
  5905.0  460.58  5936.6  463.20  5981.1  465.24  6012.1  469.13  6035.2  470.40
#Mann=3,-1,0
  4442.0    0.05       0  4999.1    0.03       0  5005.1    0.05       0
Bank Sta=4999.1,5005.1
Exp/Cntr=0.3,0.1

Type RM Length L Ch R = 1,1650,631,631,631
BEGIN DESCRIPTION:
Mapping XS ff1bc948
END DESCRIPTION:
XS GIS Cut Line= 2
      3454885.69     10479532.76      3453739.81     10478470.22
#Sta/Elev= 30
  4182.5  453.93  4596.5  447.40  4716.7  444.00  4759.2  444.10  4780.2  443.01
  4815.4  442.55  4843.7  443.40  4872.1  442.84  4964.4  443.68  4978.4  443.50
  4985.4  441.86  4996.6  441.79  4999.4  441.29  5002.6  441.79  5013.8  443.04
  5034.8  443.36  5091.5  445.69  5183.3  447.22  5325.0  448.63  5346.6  449.94
  5367.6  450.05  5424.2  452.04  5445.2  454.05  5487.8  454.79  5523.5  456.97
  5530.3  458.02  5608.0  459.90  5636.3  461.71  5678.8  462.69  5745.2  462.53
#Mann=3,-1,0
  4182.5    0.05       0  4996.6    0.03       0  5002.6    0.05       0
Bank Sta=4996.6,5002.6
Exp/Cntr=0.3,0.1

Type RM Length L Ch R = 1,1019,0,0,0
BEGIN DESCRIPTION:
UNT061 IN STEL 1.0
END DESCRIPTION:
XS GIS Cut Line= 3
      3455120.43     10479535.02      3454263.20     10478178.64
      3453916.55     10478221.98
#Sta/Elev= 30
  4304.3  455.13  4333.5  455.48  4385.3  453.37  4421.7  452.81  4500.6  453.08
  4515.9  451.70  4610.0  449.25  4652.4  449.15  4698.2  447.60  4828.8  445.07
  4855.9  445.24  4899.8  443.79  4935.3  444.24  4986.4  440.03  4991.4  438.09
  4994.2  437.59  4997.4  438.09  5001.7  439.42  5022.9  439.69  5065.4  441.85
  5341.7  443.46  5472.3  445.24  5633.2  449.32  5769.9  451.03  5821.6  452.32
  5879.3  455.39  5974.4  456.60  6050.0  460.21  6182.1  462.77  6258.2  463.30
#Mann=3,-1,0
  4304.3    0.05       0  4991.4    0.03       0  4997.4    0.05       0
Bank Sta=4991.4,4997.4
Exp/Cntr=0.3,0.1

Chan Stop Cuts=-1