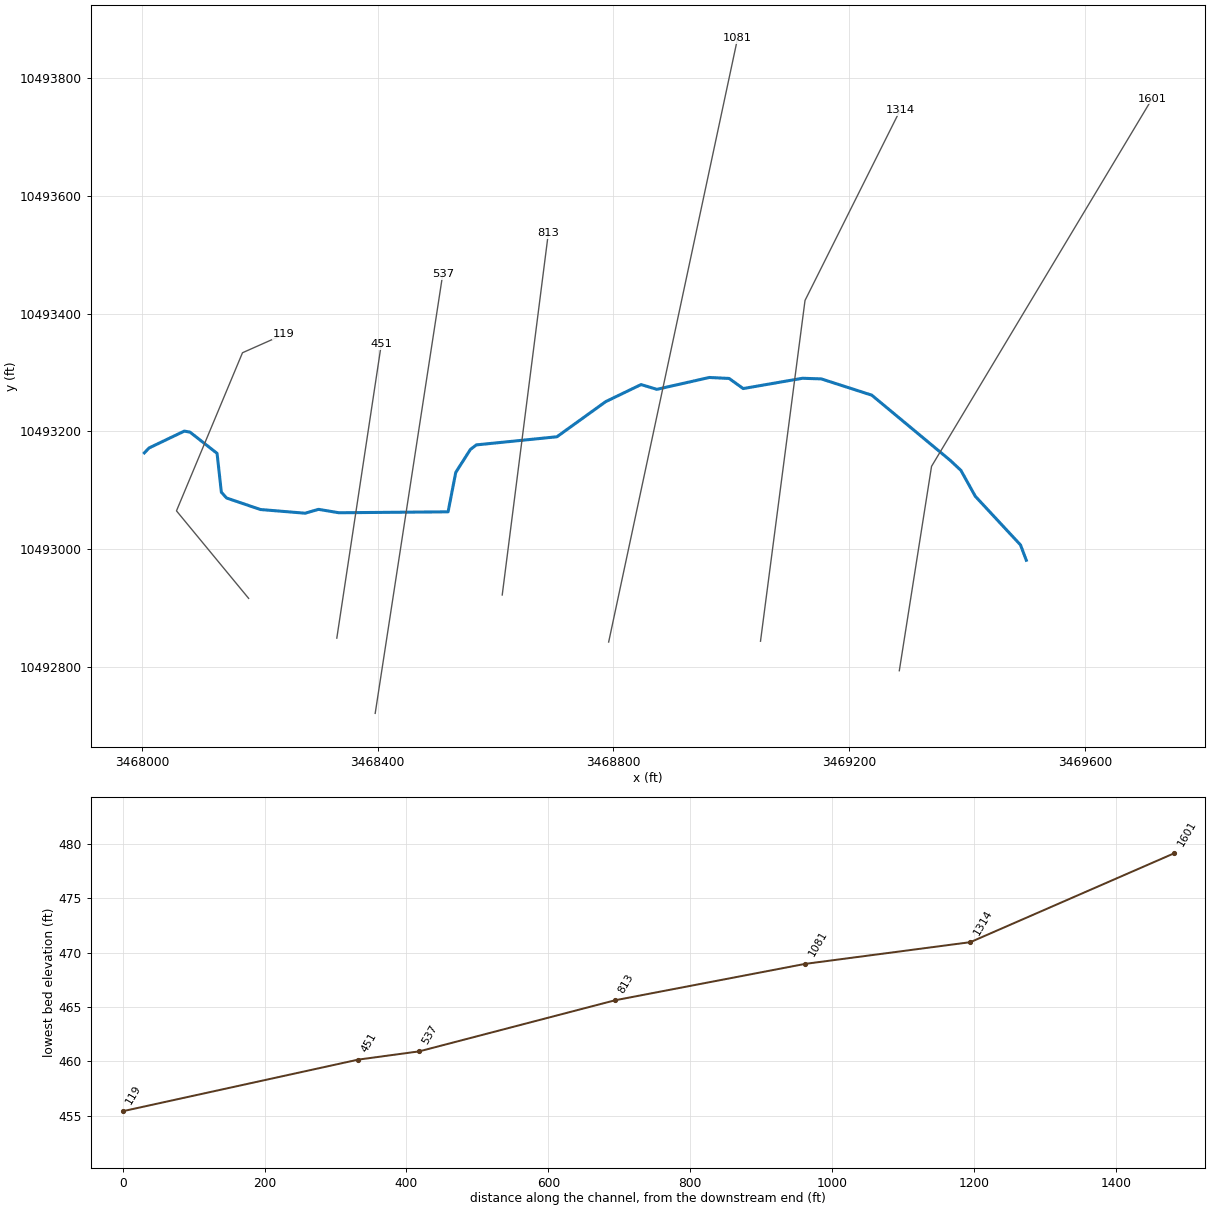
--- UNT062 IN STEL.prj (project) ---

Proj Title=UNT062 IN STEL Base Level Engineering
Current Plan=p01
Default Exp/Contr=0.3,0.1
English Units
Geom File=g01
Flow File=f01
Plan File=p01
Y Axis Title=Elevation
X Axis Title(PF)=Main Channel Distance
X Axis Title(XS)=Station
BEGIN DESCRIPTION:
UNT062 IN STEL
END DESCRIPTION:
DSS Export Rating Curves= 0
DSS Export Rating Curve Sorted= 0
DSS Export Volume Flow Curves= 0
DXF OffsetX= 0
DXF OffsetY= 0
DXF ScaleX= 1
DXF ScaleY= 10

--- UNT062 IN STEL.p01 (plan) ---

Plan Title=Multiple Run
Short Identifier=Multiple
Geom File=g01
Flow File=f01
Subcritical Flow
K Sum by GR= 0
Std Step Tol= 0.01
Critical Tol= 0.01
Num of Std Step Trials= 20
Max Error Tol= 0.3
Flow Tol Ratio= 0.001
Split Flow NTrial= 30
Split Flow Tol= 0.02
Split Flow Ratio= 0.02
Log Output Level= 0
Friction Slope Method= 1
Unsteady Friction Slope Method= 2
Unsteady Bridges Friction Slope Method= 1
Parabolic Critical Depth
Global Vel Dist=  1 , 1 , 1
Global Log Level= 0
CheckData=True
Encroach Param= -1, 0, 0, 0
BEGIN DESCRIPTION:
Multiple Run
END DESCRIPTION:

--- UNT062 IN STEL.f01 (steady flow) ---

Flow Title=Multiple
Number of Profiles=7
Profile Names=10-year,25-year,50-year,1pct_min,100-year,1pct_plu,500-year
River Rch & RM= UNT062 IN STEL,Reach-1,1601
     118     141     157     128     174     235     211
Boundary for River Rch & Prof#=UNT062 IN STEL,Reach-1,1
Up Type=0
Dn Type=3
Dn Slope=0.005
Boundary for River Rch & Prof#=UNT062 IN STEL,Reach-1,2
Up Type=0
Dn Type=3
Dn Slope=0.005
Boundary for River Rch & Prof#=UNT062 IN STEL,Reach-1,3
Up Type=0
Dn Type=3
Dn Slope=0.005
Boundary for River Rch & Prof#=UNT062 IN STEL,Reach-1,4
Up Type=0
Dn Type=3
Dn Slope=0.005
Boundary for River Rch & Prof#=UNT062 IN STEL,Reach-1,5
Up Type=0
Dn Type=3
Dn Slope=0.005
Boundary for River Rch & Prof#=UNT062 IN STEL,Reach-1,6
Up Type=0
Dn Type=3
Dn Slope=0.005
Boundary for River Rch & Prof#=UNT062 IN STEL,Reach-1,7
Up Type=0
Dn Type=3
Dn Slope=0.005

--- UNT062 IN STEL.g01 (geometry) ---

Geom Title=Existing Conditions
Program Version=4.10

River Reach=UNT062 IN STEL  ,Reach-1
Reach XY= 30
      3469500.37     10492981.46       3469490.6     10493007.37
      3469413.91     10493089.92      3469389.43     10493133.93
       3469371.2     10493150.99      3469238.26     10493261.49
      3469152.58      10493289.1      3469120.55     10493290.14
      3469020.03     10493272.69      3468996.31     10493289.83
      3468962.73     10493291.51      3468873.67     10493271.39
      3468846.85     10493279.46      3468786.96     10493250.56
      3468704.14     10493190.92      3468567.42     10493177.12
      3468557.27     10493169.31      3468532.53     10493130.51
      3468519.51     10493063.58      3468334.09     10493062.02
      3468299.68     10493067.81      3468277.06     10493061.23
      3468201.28     10493067.48      3468143.73     10493087.02
      3468134.87     10493096.91      3468127.58      10493162.8
      3468081.75     10493198.73      3468072.11     10493200.56
      3468012.22     10493171.91      3468004.26      10493163.6

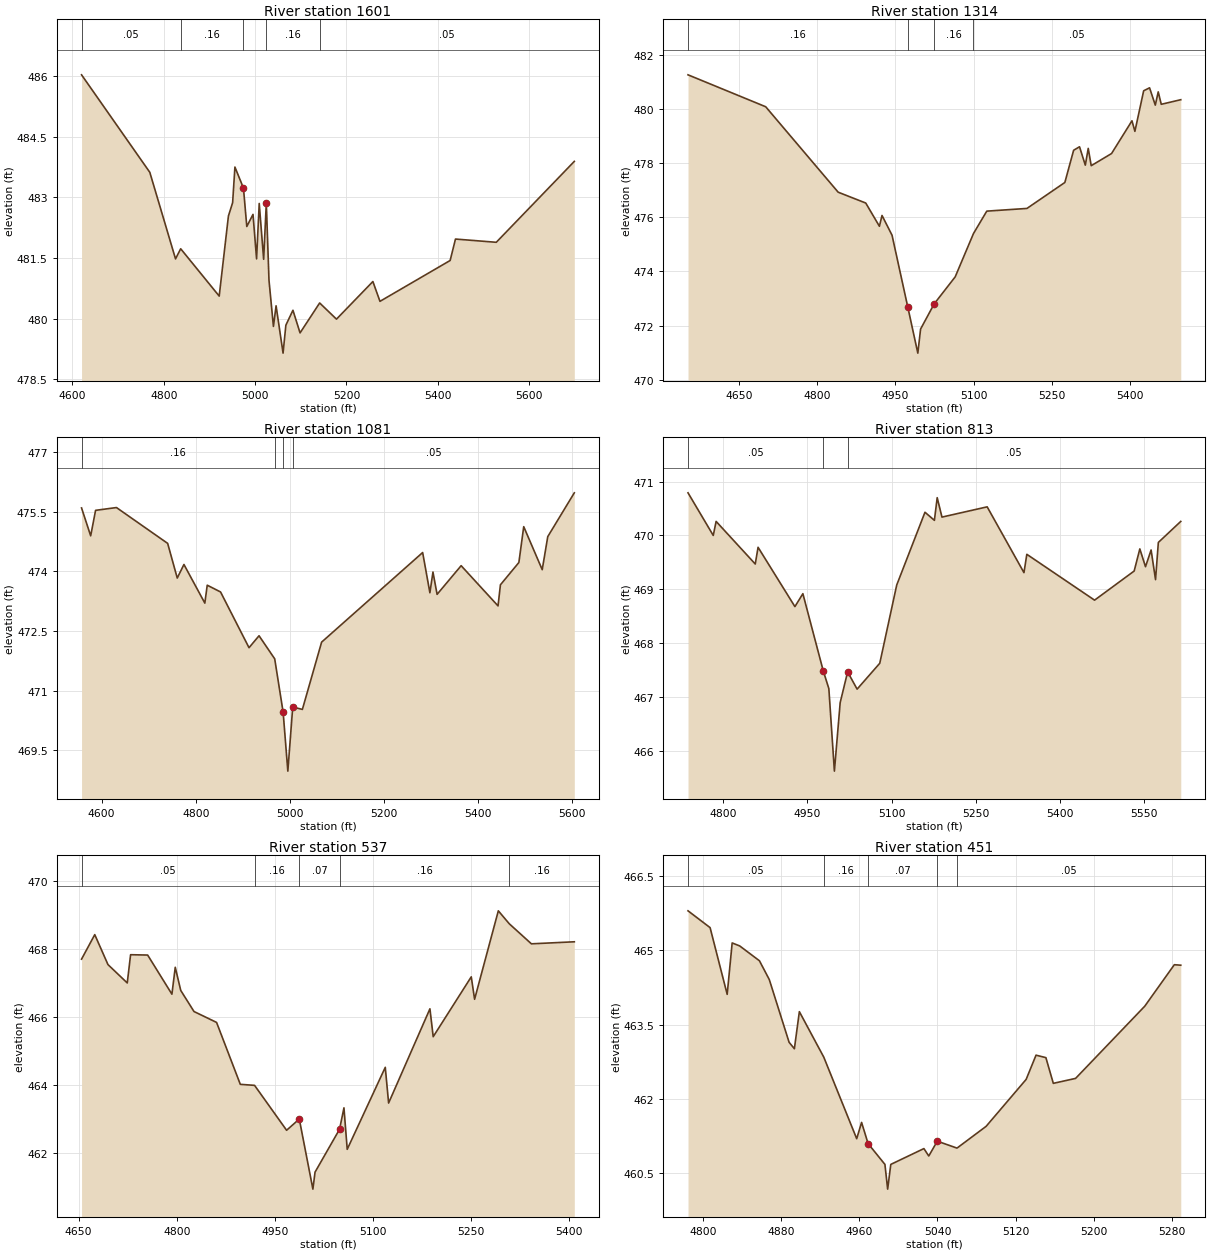
Type RM Length L Ch R = 1 ,1601    ,287,287,287
BEGIN DESCRIPTION:
UNT062 IN STEL 5.0
END DESCRIPTION:
XS GIS Cut Line= 3
      3469284.95     10492794.06      3469339.64     10493140.74
        3469714.     10493764.68
#Sta/Elev= 30
  4620.2  486.03  4769.6  483.62  4825.9  481.48  4837.2  481.73  4921.5  480.56
  4941.7  482.54  4950.9  482.87  4955.9  483.75  4974.6  483.23  4981.9  482.28
  4995.5  482.58  5003.3  481.48  5009.1  482.85  5018.8  481.47  5024.6  482.86
  5030.5  480.95  5040.2  479.81    5046  480.32  5061.3  479.15  5067.4  479.84
  5082.9  480.21  5098.5  479.65  5141.4  480.39  5178.2  479.99  5257.9  480.92
  5273.4  480.43    5427  481.44  5438.7  481.97    5528  481.89  5698.8  483.89
#Mann= 5 ,-1 , 0
  4620.2     .05       0  4837.2     .16       0  4974.6     .07       0
  5024.6     .16       0  5141.4     .05       0
Bank Sta=4974.6,5024.6
XS Rating Curve= 0 ,0
Exp/Cntr=0.3,0.1

Type RM Length L Ch R = 1 ,1314    ,233,233,233
BEGIN DESCRIPTION:
Mapping XS 6f921eb4
END DESCRIPTION:
XS GIS Cut Line= 3
      3469049.48     10492844.06      3469125.01     10493422.21
      3469286.47     10493745.13
#Sta/Elev= 30
  4552.9  481.27  4701.7  480.09  4840.6  476.93  4893.4  476.53  4919.6  475.67
  4924.6  476.07  4943.8  475.34    4974  472.68  4993.2  470.98  4998.5  471.87
  5024.5   472.8  5064.8   473.8  5099.8   475.4  5125.3  476.23  5202.3  476.33
  5274.9  477.29  5291.7  478.48    5303  478.61  5314.1  477.93  5319.7  478.55
  5325.4  477.91  5364.4  478.36  5403.5  479.57  5409.1  479.18  5425.9  480.68
  5437.2  480.79  5448.2  480.15  5453.8  480.64  5459.6  480.18    5497  480.35
#Mann= 4 ,-1 , 0
  4552.9     .16       0    4974     .07       0  5024.5     .16       0
  5099.8     .05       0
Bank Sta=4974,5024.5
XS Rating Curve= 0 ,0
Exp/Cntr=0.3,0.1

Type RM Length L Ch R = 1 ,1081    ,268,268,268
BEGIN DESCRIPTION:
UNT062 IN STEL 2.0
END DESCRIPTION:
XS GIS Cut Line= 2
       3468791.9     10492842.71      3469010.61     10493866.82
#Sta/Elev= 30
  4557.4  475.59  4576.8  474.89  4587.2  475.53  4631.6   475.6  4740.4   474.7
  4760.8  473.83    4775  474.17  4819.4   473.2  4824.5  473.65  4852.8  473.48
  4913.3  472.08  4934.6  472.38  4967.9   471.8  4985.8  470.46  4995.8  468.98
  5006.2  470.59  5026.7  470.53  5067.6  472.22  5282.3  474.47  5297.7  473.46
  5304.2  473.98    5313  473.42  5364.1  474.14  5442.5  473.13  5447.6  473.66
  5486.8  474.22  5497.1  475.12  5536.4  474.04  5548.2  474.87  5604.6  475.97
#Mann= 4 ,-1 , 0
  4557.4     .16       0  4967.9     .05       0  4985.8    .035       0
  5006.2     .05       0
Bank Sta=4985.8,5006.2
XS Rating Curve= 0 ,0
Exp/Cntr=0.3,0.1

Type RM Length L Ch R = 1 ,813     ,276,276,276
BEGIN DESCRIPTION:
UNT062 IN STEL 4.0
END DESCRIPTION:
XS GIS Cut Line= 2
      3468611.34     10492922.52     3468689.604    10493536.422
#Sta/Elev= 30
    4737  470.79    4782     470  4787.1  470.26  4856.9  469.47  4861.9  469.78
  4927.6  468.68  4941.8  468.92  4978.1  467.49  4988.1  467.16    4998  465.63
  5008.3   466.9  5021.6  467.47  5038.5  467.15  5078.9  467.63  5109.1  469.08
  5159.5  470.43  5176.3  470.28  5181.3   470.7  5189.8  470.34  5270.4  470.53
    5336  469.31  5341.1  469.65  5461.9   468.8  5532.5  469.34  5542.6  469.75
  5552.7  469.42  5562.7  469.73  5570.6  469.18  5575.6  469.87  5615.6  470.26
#Mann= 3 , 0 , 0
    4737     .05       0  4978.1     .04       0  5021.6     .05       0
Bank Sta=4978.1,5021.6
XS Rating Curve= 0 ,0
Exp/Cntr=0.3,0.1

Type RM Length L Ch R = 1 ,537     ,86,86,86
BEGIN DESCRIPTION:
Mapping XS 40560741
END DESCRIPTION:
XS GIS Cut Line= 2
      3468395.84     10492721.68      3468510.43     10493466.52
#Sta/Elev= 30
  4654.5  467.69  4674.7  468.41  4694.9  467.53  4724.4  466.99  4729.5  467.82
  4755.6  467.81  4792.7  466.66  4797.8  467.45  4806.2  466.77  4826.5  466.15
    4861  465.83  4897.3  464.01  4919.1  463.98  4968.1  462.66  4987.5  462.99
  5008.3  460.93  5011.6  461.43  5049.1  462.69  5055.8  463.32  5060.8   462.1
    5119  464.51  5124.1  463.46  5187.3  466.23  5192.3  465.41  5250.5  467.17
  5255.6  466.51  5291.9  469.11  5308.6  468.73  5342.5  468.14  5408.1   468.2
#Mann= 5 ,-1 , 0
  4654.5     .05       0  4919.1     .16       0  4987.5     .07       0
  5049.1     .16       0  5308.6     .16       0
Bank Sta=4987.5,5049.1
XS Rating Curve= 0 ,0
Exp/Cntr=0.3,0.1

Type RM Length L Ch R = 1 ,451     ,332,332,332
BEGIN DESCRIPTION:
UNT062 IN STEL 3.0
END DESCRIPTION:
XS GIS Cut Line= 2
      3468330.74     10492849.33      3468406.25     10493348.15
#Sta/Elev= 30
  4784.6   465.8  4807.2  465.46  4824.7  464.11  4829.8  465.15  4837.5  465.09
  4857.7  464.79  4867.8  464.41  4888.1  463.14  4893.5  463.01  4898.6  463.76
  4923.6  462.84  4957.3  461.19  4962.3  461.52    4969  461.09  4986.2  460.67
    4989  460.17  4992.2  460.67  5026.1  460.99  5031.1  460.84  5039.8  461.14
    5060     461  5089.8  461.44  5130.8  462.39  5140.9  462.88    5151  462.83
  5158.6  462.31  5181.4  462.41  5252.2  463.87  5282.5  464.71  5289.1   464.7
#Mann= 5 ,-1 , 0
  4784.6     .05       0  4923.6     .16       0    4969     .07       0
  5039.8     .16       0    5060     .05       0
Bank Sta=4969,5039.8
XS Rating Curve= 0 ,0
Exp/Cntr=0.3,0.1

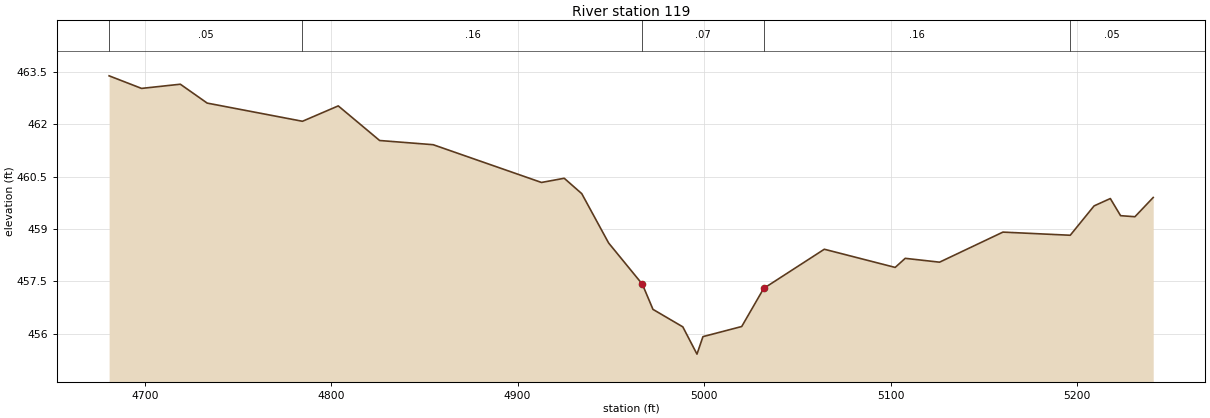
Type RM Length L Ch R = 1 ,119     ,0,0,0
BEGIN DESCRIPTION:
UNT062 IN STEL 1.0
END DESCRIPTION:
XS GIS Cut Line= 4
      3468181.13     10492916.79      3468058.74     10493065.22
      3468170.72     10493333.45      3468241.04      10493364.7
#Sta/Elev= 30
  4680.9  463.38  4698.3  463.02  4719.1  463.14  4733.5   462.6  4784.6  462.08
  4803.8  462.52    4826  461.53  4854.7  461.41  4912.8  460.33    4925  460.45
  4934.4  460.01  4948.8   458.6  4966.9  457.42  4972.6   456.7  4988.6   456.2
  4996.2  455.42  4999.4  455.92  5020.2  456.21    5032   457.3  5064.5  458.42
  5102.5   457.9  5107.9  458.16  5126.3  458.05  5160.3  458.91  5196.4  458.82
  5209.2  459.66  5217.9  459.87  5223.4  459.38  5231.1  459.35  5240.9   459.9
#Mann= 5 ,-1 , 0
  4680.9     .05       0  4784.6     .16       0  4966.9     .07       0
    5032     .16       0  5196.4     .05       0
Bank Sta=4966.9,5032
XS Rating Curve= 0 ,0
Exp/Cntr=0.3,0.1

Chan Stop Cuts=-1
Use User Specified Reach Order=0
Composite Channel Slope=5