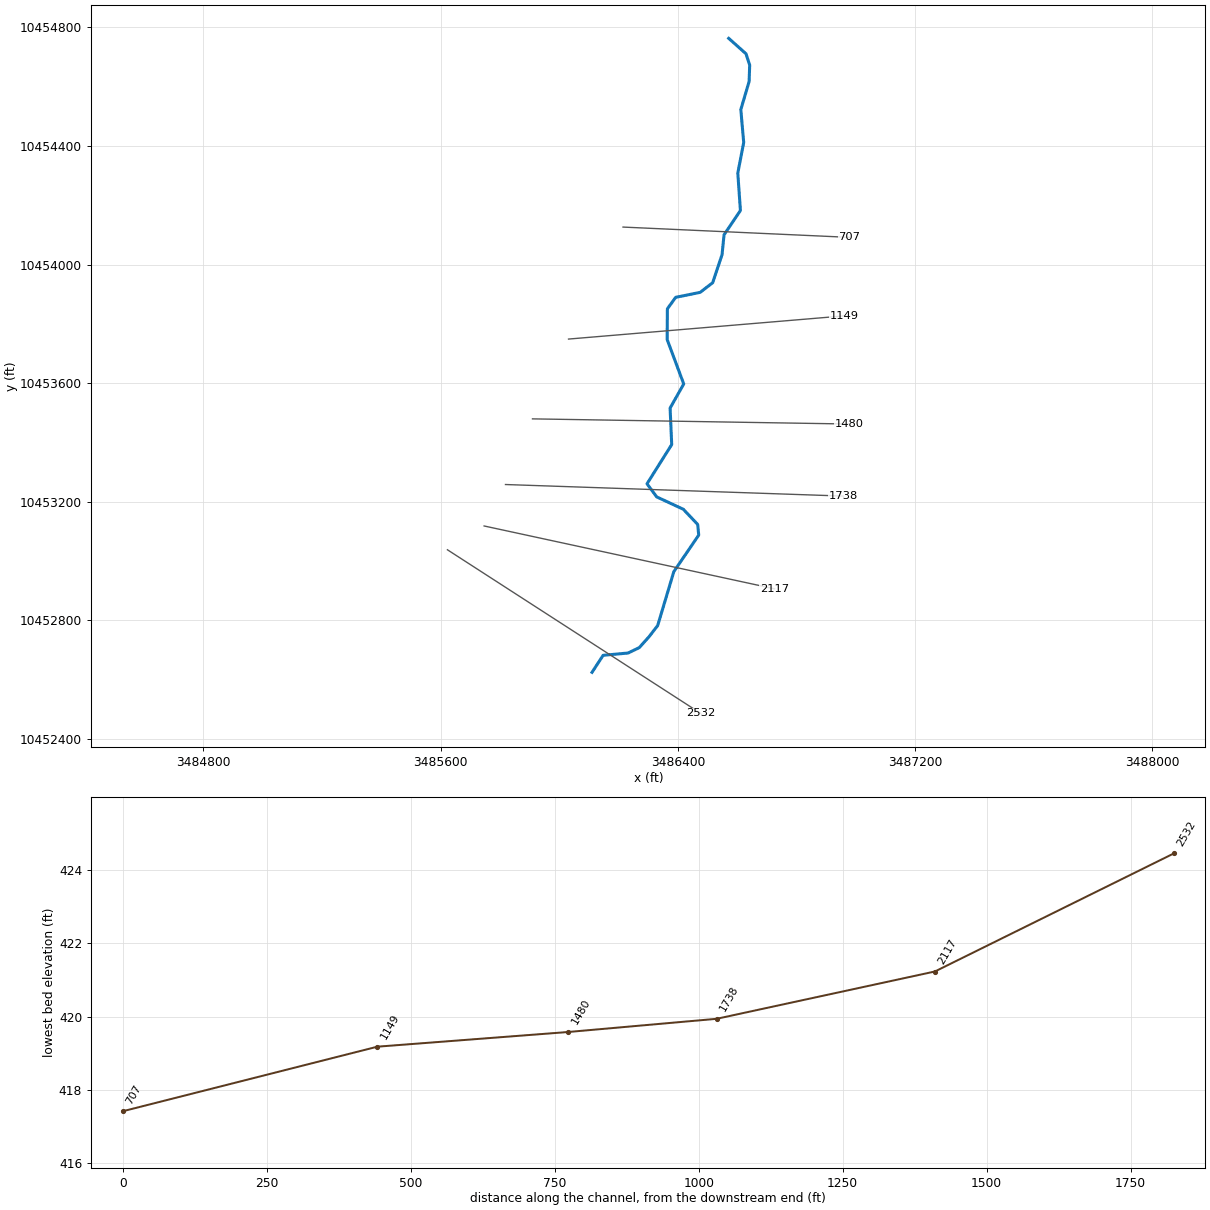
--- UNT063 IN STEL.prj (project) ---

Proj Title=UNT063 IN STEL Base Level Engineering
Current Plan=p01
Default Exp/Contr=0.3,0.1
English Units
Geom File=g01
Flow File=f01
Plan File=p01
BEGIN DESCRIPTION:
UNT063 IN STEL
END DESCRIPTION:

--- UNT063 IN STEL.p01 (plan) ---

Plan Title=Multiple Run
Short Identifier=Multiple
Geom File=g01
Flow File=f01
Subcritical Flow
K Sum by GR= 0
Std Step Tol= 0.01
Critical Tol= 0.01
Num of Std Step Trials= 20
Max Error Tol= 0.3
Flow Tol Ratio= 0.001
Split Flow NTrial= 30
Split Flow Tol= 0.02
Split Flow Ratio= 0.02
Log Output Level= 0
Friction Slope Method= 1
Unsteady Friction Slope Method= 2
Unsteady Bridges Friction Slope Method= 1
Parabolic Critical Depth
Global Vel Dist=  1 , 1 , 1
Global Log Level= 0
CheckData=True
Encroach Param= -1, 0, 0, 0
BEGIN DESCRIPTION:
Multiple Run
END DESCRIPTION:

--- UNT063 IN STEL.f01 (steady flow) ---

Flow Title=Multiple
Number of Profiles=7
Profile Names=10-year,25-year,50-year,1pct_min,100-year,1pct_plu,500-year
River Rch & RM= UNT063 IN STEL,Reach-1,2532
    1052    1456    1791    1607    2173    2939    3194
Boundary for River Rch & Prof#=UNT063 IN STEL,Reach-1,1
Up Type=0
Dn Type=3
Dn Slope=0.005
Boundary for River Rch & Prof#=UNT063 IN STEL,Reach-1,2
Up Type=0
Dn Type=3
Dn Slope=0.005
Boundary for River Rch & Prof#=UNT063 IN STEL,Reach-1,3
Up Type=0
Dn Type=3
Dn Slope=0.005
Boundary for River Rch & Prof#=UNT063 IN STEL,Reach-1,4
Up Type=0
Dn Type=3
Dn Slope=0.005
Boundary for River Rch & Prof#=UNT063 IN STEL,Reach-1,5
Up Type=0
Dn Type=3
Dn Slope=0.005
Boundary for River Rch & Prof#=UNT063 IN STEL,Reach-1,6
Up Type=0
Dn Type=3
Dn Slope=0.005
Boundary for River Rch & Prof#=UNT063 IN STEL,Reach-1,7
Up Type=0
Dn Type=3
Dn Slope=0.005

--- UNT063 IN STEL.g01 (geometry) ---

Geom Title=Existing Conditions

River Reach=UNT063 IN STEL,Reach-1
Reach XY= 30
      3486110.60     10452625.05      3486148.10     10452682.34
      3486232.47     10452690.15      3486269.97     10452708.38
      3486302.26     10452744.32      3486331.98     10452782.64
      3486386.49     10452964.54      3486470.47     10453087.80
      3486466.86     10453123.70      3486418.51     10453174.83
      3486328.77     10453216.49      3486296.03     10453260.69
      3486379.32     10453392.91      3486373.90     10453516.16
      3486419.87     10453597.20      3486363.95     10453747.23
      3486364.76     10453850.76      3486392.77     10453889.42
      3486475.12     10453906.12      3486517.43     10453938.58
      3486549.01     10454032.92      3486555.77     10454100.12
      3486611.01     10454182.18      3486602.16     10454308.18
      3486622.08     10454411.61      3486612.33     10454522.52
      3486640.36     10454617.21      3486642.23     10454672.72
      3486629.77     10454710.64      3486571.50     10454762.69

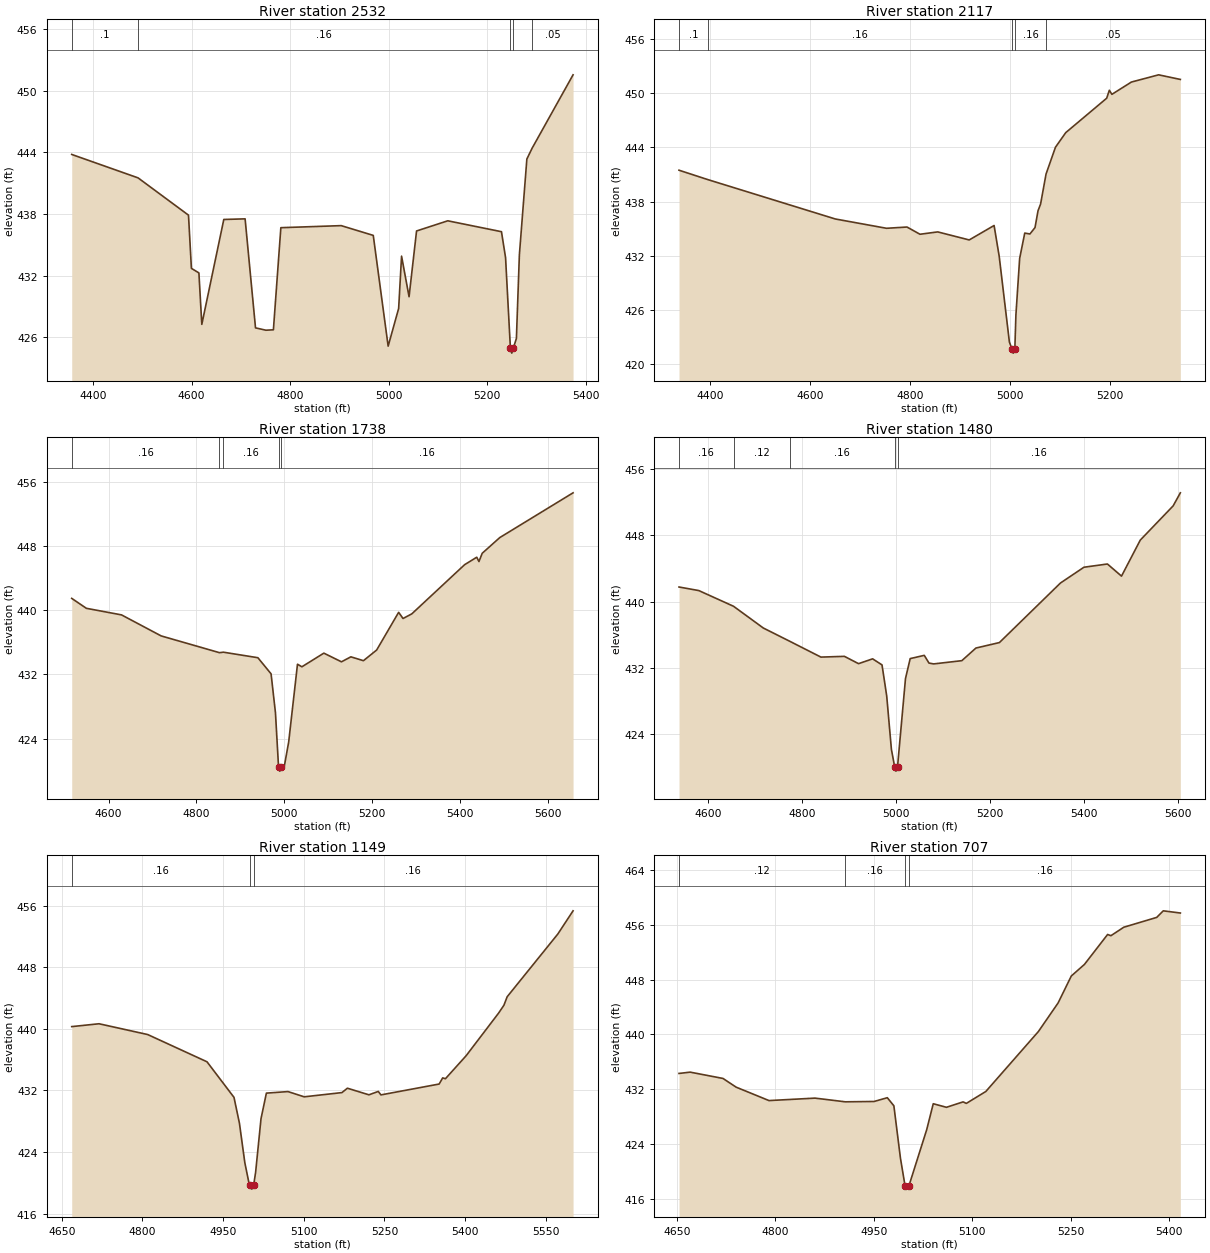
Type RM Length L Ch R = 1,2532,415,415,415
BEGIN DESCRIPTION:
UNT063 IN STEL 2.0
END DESCRIPTION:
XS GIS Cut Line= 2
      3485623.06     10453038.21      3486477.10     10452486.59
#Sta/Elev= 30
  4357.1  443.79  4491.6  441.51  4593.9  437.88  4599.8  432.70  4615.0  432.26
  4620.9  427.25  4665.5  437.46  4708.7  437.52  4729.8  426.91  4750.9  426.68
  4766.1  426.72  4781.2  436.66  4903.6  436.86  4968.6  435.91  4998.8  425.13
  5020.1  428.80  5026.0  433.89  5041.2  429.94  5056.4  436.34  5119.7  437.33
  5228.6  436.27  5236.9  433.75  5246.7  424.95  5249.5  424.45  5252.7  424.95
  5258.9  425.88  5264.9  434.00  5280.1  443.34  5290.8  444.40  5373.8  451.54
#Mann=5,-1,0
  4357.1     0.1       0  4491.6    0.16       0  5246.7    0.07       0
  5252.7    0.16       0  5290.8    0.05       0
Bank Sta=5246.7,5252.7
Exp/Cntr=0.3,0.1

Type RM Length L Ch R = 1,2117,379,379,379
BEGIN DESCRIPTION:
Mapping XS 298ef2c7
END DESCRIPTION:
XS GIS Cut Line= 2
      3485746.79     10453118.50      3486725.94     10452906.68
#Sta/Elev= 30
  4338.2  441.48  4395.2  440.45  4650.6  436.08  4752.9  435.05  4793.8  435.19
  4819.7  434.39  4855.2  434.65  4918.1  433.76  4967.8  435.36  4978.0  431.96
  4998.4  422.45  5003.3  421.73  5006.1  421.23  5009.3  421.73  5011.4  425.44
  5018.9  431.72  5029.1  434.52  5039.4  434.42  5049.6  435.13  5055.6  436.99
  5060.7  437.73  5071.6  441.05  5090.5  444.03  5111.0  445.64  5192.8  449.45
  5198.1  450.33  5203.2  449.88  5242.2  451.24  5296.6  452.04  5340.0  451.53
#Mann=5,-1,0
  4338.2     0.1       0  4395.2    0.16       0  5003.3    0.07       0
  5009.3    0.16       0  5071.6    0.05       0
Bank Sta=5003.3,5009.3
Exp/Cntr=0.3,0.1

Type RM Length L Ch R = 1,1738,258,258,258
BEGIN DESCRIPTION:
Mapping XS 43ac413d
END DESCRIPTION:
XS GIS Cut Line= 2
      3485818.85     10453258.24      3486958.69     10453219.24
#Sta/Elev= 30
  4516.3  441.48  4549.6  440.24  4629.6  439.42  4719.7  436.80  4852.4  434.71
  4861.3  434.77  4939.8  434.08  4969.8  432.07  4979.8  427.20  4986.8  420.44
  4989.6  419.94  4992.8  420.44  4999.8  420.53  5009.8  423.55  5029.9  433.27
  5039.9  432.95  5089.9  434.65  5129.9  433.57  5151.4  434.19  5179.9  433.71
  5210.0  435.04  5260.0  439.74  5270.0  438.97  5290.0  439.55  5410.1  445.68
  5437.7  446.61  5442.7  446.07  5450.1  447.10  5490.1  449.06  5656.8  454.64
#Mann=5,-1,0
  4516.3    0.16       0  4852.4    0.12       0  4861.3    0.16       0
  4986.8    0.07       0  4992.8    0.16       0
Bank Sta=4986.8,4992.8
Exp/Cntr=0.3,0.1

Type RM Length L Ch R = 1,1480,331,331,331
BEGIN DESCRIPTION:
Mapping XS 7c8f98d7
END DESCRIPTION:
XS GIS Cut Line= 2
      3485909.90     10453479.60      3486977.36     10453462.24
#Sta/Elev= 30
  4537.5  441.75  4579.7  441.32  4653.6  439.43  4717.1  436.81  4772.8  435.23
  4839.7  433.31  4889.7  433.40  4919.8  432.52  4949.8  433.10  4969.8  432.37
  4979.8  428.63  4989.8  422.20  4996.8  420.08  4999.5  419.58  5002.8  420.08
  5019.8  430.73  5029.8  433.13  5059.8  433.52  5069.8  432.59  5079.8  432.49
  5139.8  432.88  5169.8  434.40  5219.8  435.06  5349.8  442.23  5399.8  444.13
  5449.8  444.52  5479.8  443.06  5519.8  447.40  5589.8  451.52  5605.1  453.09
#Mann=5,-1,0
  4537.5    0.16       0  4653.6    0.12       0  4772.8    0.16       0
  4996.8    0.07       0  5002.8    0.16       0
Bank Sta=4996.8,5002.8
Exp/Cntr=0.3,0.1

Type RM Length L Ch R = 1,1149,442,442,442
BEGIN DESCRIPTION:
Mapping XS e5402044
END DESCRIPTION:
XS GIS Cut Line= 2
      3486031.44     10453748.69      3486960.26     10453826.82
#Sta/Elev= 30
  4668.5  440.29  4719.3  440.66  4809.7  439.26  4920.0  435.72  4970.2  431.10
  4980.3  427.74  4990.3  422.63  4998.6  419.77  5000.7  419.68  5003.4  419.18
  5006.7  419.68  5010.4  421.37  5020.4  428.32  5030.4  431.65  5070.6  431.85
  5100.7  431.17  5170.9  431.72  5181.0  432.29  5221.1  431.43  5238.4  431.87
  5243.4  431.42  5351.6  432.83  5358.2  433.63  5363.3  433.52  5401.7  436.50
  5462.0  442.03  5472.0  443.06  5478.1  444.17  5572.3  452.32  5600.6  455.33
#Mann=3,-1,0
  4668.5    0.16       0  5000.7    0.07       0  5006.7    0.16       0
Bank Sta=5000.7,5006.7
Exp/Cntr=0.3,0.1

Type RM Length L Ch R = 1,707,0,0,0
BEGIN DESCRIPTION:
UNT063 IN STEL 1.0
END DESCRIPTION:
XS GIS Cut Line= 2
      3486215.17     10454126.30      3486978.08     10454091.62
#Sta/Elev= 30
  4653.4  434.30  4670.4  434.49  4720.4  433.57  4740.4  432.30  4790.5  430.34
  4860.6  430.70  4906.7  430.16  4950.6  430.21  4970.7  430.76  4980.7  429.58
  4990.7  421.95  4997.7  417.92  5000.4  417.42  5003.7  417.92  5030.7  426.09
  5040.7  429.88  5060.8  429.36  5086.1  430.15  5091.1  429.93  5120.8  431.67
  5200.9  440.42  5230.9  444.59  5251.0  448.52  5271.0  450.21  5306.3  454.58
  5311.3  454.40  5331.0  455.64  5381.1  457.07  5391.1  458.03  5417.1  457.71
#Mann=4,-1,0
  4653.4    0.12       0  4906.7    0.16       0  4997.7    0.07       0
  5003.7    0.16       0
Bank Sta=4997.7,5003.7
Exp/Cntr=0.3,0.1

Chan Stop Cuts=-1