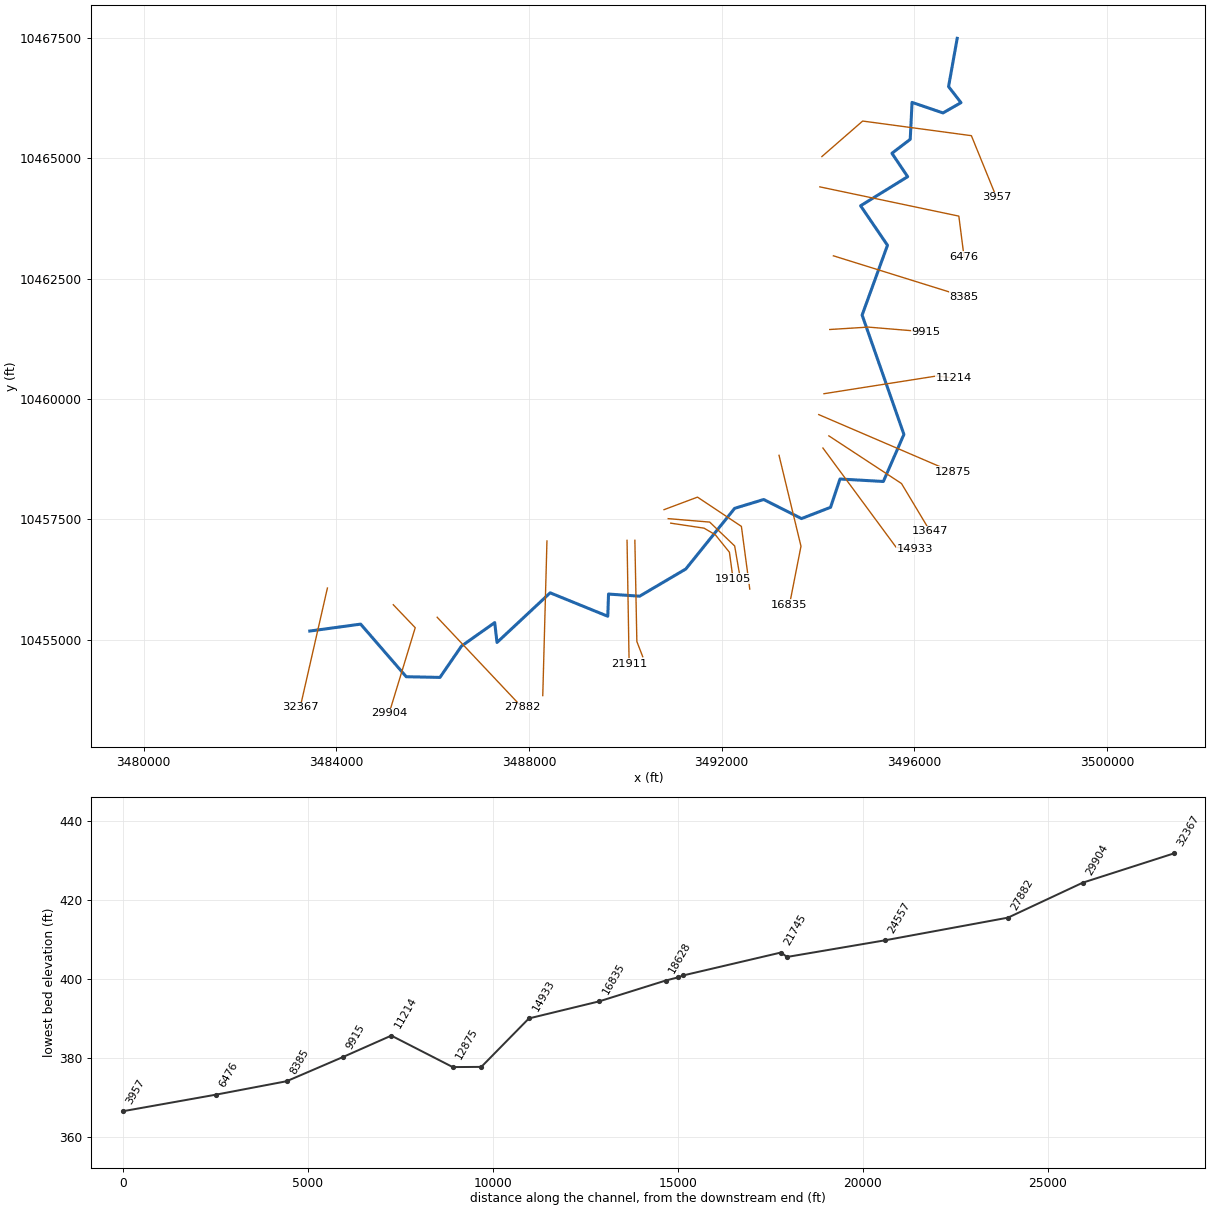
--- WHITE BRANCH.prj (project) ---

Proj Title=WHITE BRANCH Base Level Engineering
Current Plan=p01
Default Exp/Contr=0.3,0.1
English Units
Geom File=g01
Flow File=f01
Plan File=p01
Y Axis Title=Elevation
X Axis Title(PF)=Main Channel Distance
X Axis Title(XS)=Station
BEGIN DESCRIPTION:
WHITE BRANCH
END DESCRIPTION:
DSS Export Rating Curves= 0
DSS Export Rating Curve Sorted= 0
DSS Export Volume Flow Curves= 0
DXF OffsetX= 0
DXF OffsetY= 0
DXF ScaleX= 1
DXF ScaleY= 10

--- WHITE BRANCH.p01 (plan) ---

Plan Title=Multiple Run
Short Identifier=Multiple
Geom File=g01
Flow File=f01
Subcritical Flow
K Sum by GR= 0
Std Step Tol= 0.01
Critical Tol= 0.01
Num of Std Step Trials= 20
Max Error Tol= 0.3
Flow Tol Ratio= 0.001
Split Flow NTrial= 30
Split Flow Tol= 0.02
Split Flow Ratio= 0.02
Log Output Level= 0
Friction Slope Method= 1
Unsteady Friction Slope Method= 2
Unsteady Bridges Friction Slope Method= 1
Parabolic Critical Depth
Global Vel Dist=  1 , 1 , 1
Global Log Level= 0
CheckData=True
Encroach Param= -1, 0, 0, 0
BEGIN DESCRIPTION:
Multiple Run
END DESCRIPTION:

--- WHITE BRANCH.f01 (steady flow) ---

Flow Title=Multiple
Program Version=4.10
Number of Profiles= 7
Profile Names=10-year,25-year,50-year,1pct_min,100-year,1pct_plu,500-year
River Rch & RM=WHITE BRANCH,Reach-1         ,32367
    1073    1489    1834    1649    2230    3016    3289
River Rch & RM=WHITE BRANCH,Reach-1         ,27882
    2063    2946    3698    3378    4568    6178    6960
River Rch & RM=WHITE BRANCH,Reach-1         ,18628
    2375    3404    4286    3923    5305    7174    8118
River Rch & RM=WHITE BRANCH,Reach-1         ,12875
    2640    3792    4779    4376    5918    8003    9065
Boundary for River Rch & Prof#=WHITE BRANCH,Reach-1         , 1
Up Type= 0
Dn Type= 3
Dn Slope=0.002
Boundary for River Rch & Prof#=WHITE BRANCH,Reach-1         , 2
Up Type= 0
Dn Type= 3
Dn Slope=0.002
Boundary for River Rch & Prof#=WHITE BRANCH,Reach-1         , 3
Up Type= 0
Dn Type= 3
Dn Slope=0.002
Boundary for River Rch & Prof#=WHITE BRANCH,Reach-1         , 4
Up Type= 0
Dn Type= 3
Dn Slope=0.002
Boundary for River Rch & Prof#=WHITE BRANCH,Reach-1         , 5
Up Type= 0
Dn Type= 3
Dn Slope=0.002
Boundary for River Rch & Prof#=WHITE BRANCH,Reach-1         , 6
Up Type= 0
Dn Type= 3
Dn Slope=0.002
Boundary for River Rch & Prof#=WHITE BRANCH,Reach-1         , 7
Up Type= 0
Dn Type= 3
Dn Slope=0.002
DSS Import GetInterval= 0
DSS Import GetPeak= 0
DSS Import FillOption= 0

--- WHITE BRANCH.g01 (geometry) ---

Geom Title=Existing Conditions
Program Version=4.10

River Reach=WHITE BRANCH    ,Reach-1
Reach XY= 30
      3483449.12     10455177.47      3484504.63     10455321.26
      3485450.59     10454228.56      3486150.76     10454214.45
      3486597.74     10454865.29      3487287.58     10455352.97
      3487334.92     10454940.24      3488438.32     10455971.68
      3489634.76     10455484.48      3489650.12     10455945.64
       3490295.8     10455901.58      3491254.29     10456466.47
      3492269.27      10457727.1      3492871.19     10457909.81
      3493656.34     10457513.88      3494259.25     10457747.86
      3494455.17     10458335.72      3495355.36     10458284.52
      3495782.09     10459262.39      3494914.51     10461741.71
      3495440.97     10463191.55      3494883.03     10464011.81
      3495859.74     10464616.21      3495533.52      10465101.8
      3495913.21     10465392.43      3495950.71     10466159.44
      3496593.15     10465940.42      3496966.84     10466153.96
      3496709.03     10466487.29      3496888.43      10467490.1

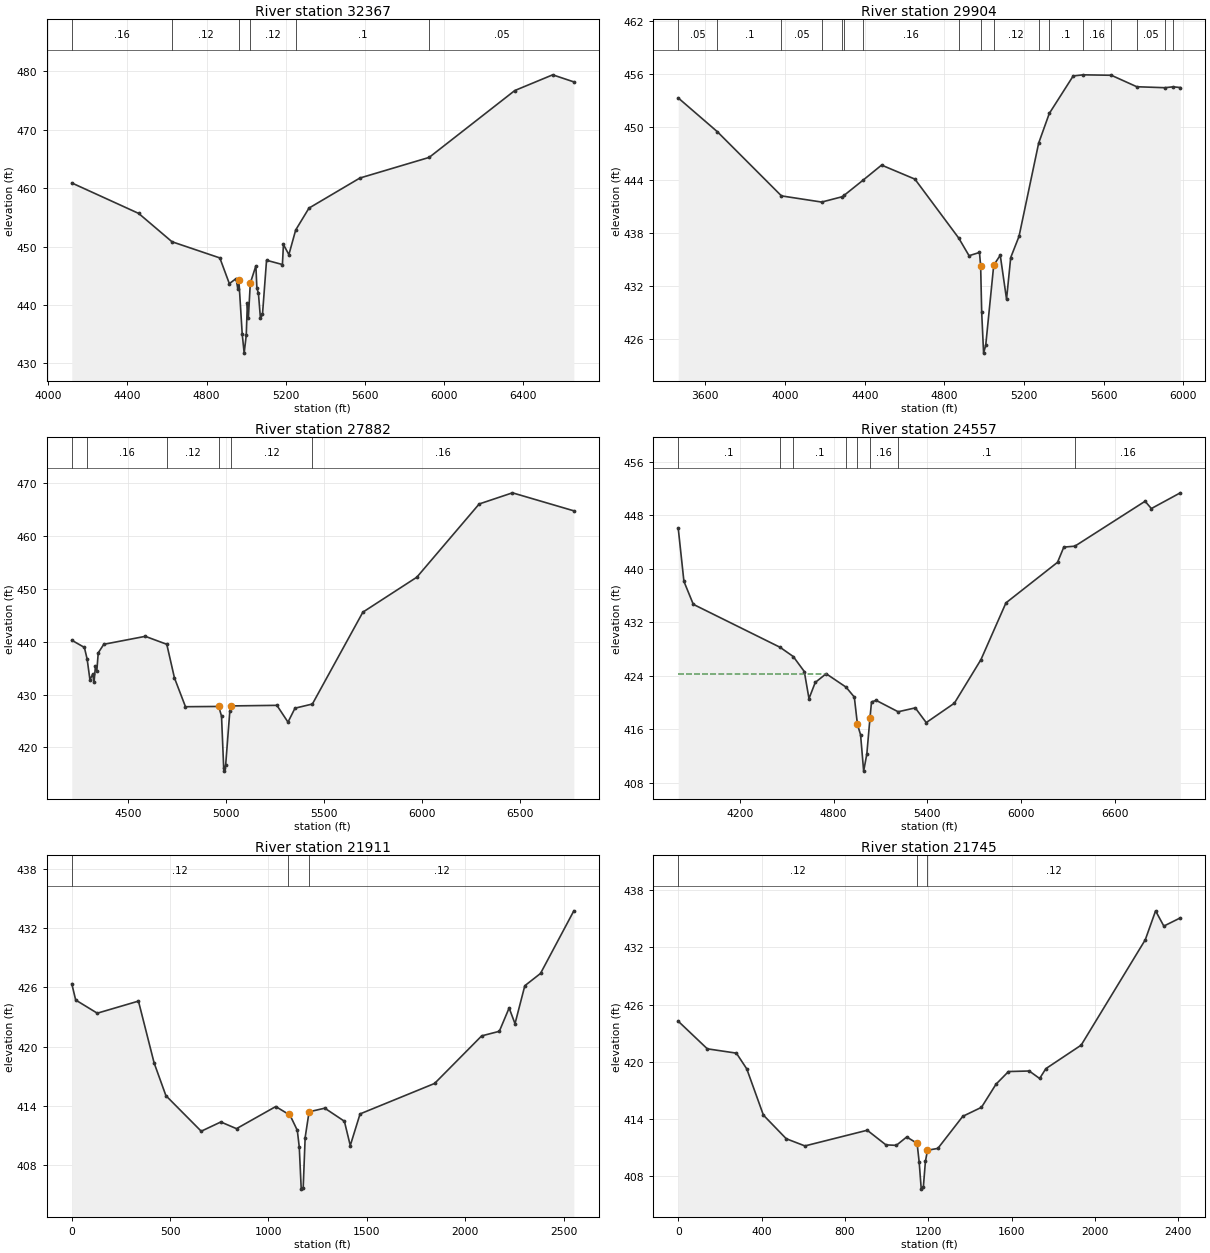
Type RM Length L Ch R = 1 ,32367   ,2463,2463,2463
BEGIN DESCRIPTION:
WHITE BRANCH 45.0
END DESCRIPTION:
XS GIS Cut Line= 2
      3483814.58     10456071.37      3483250.34      10453597.4
#Sta/Elev= 30
  4118.8  460.91    4457  455.69  4625.3  450.84  4867.1  448.07  4915.2  443.67
  4949.3  444.53  4958.2  442.72  4963.3  444.24  4980.1   435.1  4990.1  431.77
  5000.6  434.82  5006.3  440.37  5011.4  437.84  5021.1  443.75  5049.3  446.72
  5054.4  442.88  5062.1  442.04  5072.4  437.71  5082.7  438.41  5103.2  447.67
  5183.4  446.94  5188.6  450.37    5216  448.63  5250.5  452.85  5317.6   456.6
    5575  461.75    5925  465.28  6357.8  476.73  6549.4  479.42  6656.3  478.21
#Mann= 6 ,-1 , 0
  4118.8     .16       0  4625.3     .12       0  4963.3     .07       0
  5021.1     .12       0  5250.5      .1       0    5925     .05       0
Bank Sta=4963.3,5021.1
XS Rating Curve= 0 ,0
Exp/Cntr=0.3,0.1

Type RM Length L Ch R = 1 ,29904   ,2022,2022,2022
BEGIN DESCRIPTION:
WHITE BRANCH 44.0
END DESCRIPTION:
XS GIS Cut Line= 3
      3485181.75      10455724.2      3485637.51     10455246.75
      3485094.98     10453467.27
#Sta/Elev= 30
  3463.7  453.28  3659.7  449.46  3981.9  442.18  4183.8  441.48  4287.7  442.09
  4296.9  442.25  4391.5  443.96  4484.5  445.67  4651.8  444.08  4871.7   437.4
  4923.6   435.4  4975.9  435.77  4981.8  434.24    4987     429  4996.6  424.36
  5007.3  425.25  5047.4  434.32  5080.2  435.46  5111.8  430.47  5132.7  435.19
  5174.5   437.6  5272.9  448.15  5326.3  451.52  5446.3  455.77    5496   455.9
  5637.8  455.85  5765.7  454.55  5906.4  454.44  5947.8  454.54  5984.1  454.46
#Mann= 17 ,-1 , 0
  3463.7     .05       0  3659.7      .1       0  3981.9     .05       0
  4183.8      .1       0  4287.7     .16       0  4296.9      .1       0
  4391.5     .16       0  4871.7     .12       0  4981.8     .07       0
  5047.4     .12       0  5272.9     .16       0  5326.3      .1       0
    5496     .16       0  5637.8      .1       0  5765.7     .05       0
  5906.4      .1       0  5947.8     .05       0
Bank Sta=4981.8,5047.4
XS Rating Curve= 0 ,0
Exp/Cntr=0.3,0.1

Type RM Length L Ch R = 1 ,27882   ,3325,3325,3325
BEGIN DESCRIPTION:
WHITE BRANCH 43.0
END DESCRIPTION:
XS GIS Cut Line= 2
      3486093.24     10455463.76      3487851.05     10453597.44
#Sta/Elev= 30
  4211.2  440.29  4275.6  438.93  4289.8   436.7  4303.9  432.82    4318  433.85
  4324.9  432.31  4332.2  435.44  4339.1   434.5  4346.4   437.9  4374.7  439.52
  4586.7  441.03  4696.4  439.52  4735.6  433.15  4791.8   427.7  4961.7  427.75
  4975.9  425.91  4987.1     416  4989.8   415.5  4997.1  416.69  5018.4  426.92
  5025.2  427.85  5258.7  427.96  5315.3  424.78    5351  427.42  5439.9  428.21
  5697.7  445.61  5973.2  452.23  6291.6   466.1  6461.5  468.21    6775   464.8
#Mann= 6 ,-1 , 0
  4211.2      .1       0  4289.8     .16       0  4696.4     .12       0
  4961.7     .07       0  5025.2     .12       0  5439.9     .16       0
Bank Sta=4961.7,5025.2
XS Rating Curve= 0 ,0
Exp/Cntr=0.3,0.1

Type RM Length L Ch R = 1 ,24557   ,2646,2646,2646
BEGIN DESCRIPTION:
WHITE BRANCH 40.0
END DESCRIPTION:
XS GIS Cut Line= 2
      3488371.88       10457048.      3488285.08     10453836.37
#Sta/Elev= 30
  3806.4  446.04  3842.8  438.11  3902.8  434.68  4458.2  428.26  4542.5  426.88
  4613.1  424.64  4643.1  420.59  4683.1  423.01  4753.1  424.31  4880.2  422.31
  4933.2  420.82  4953.2  416.73  4973.2  415.19  4992.9  409.76  5013.2  412.32
  5033.2  417.65  5043.2   420.1  5073.2  420.33  5213.6  418.63  5323.3  419.21
  5393.3  417.01  5573.4  419.91  5743.5  426.42  5903.5   434.9  6233.6  440.96
  6273.7  443.23  6344.5  443.37  6793.8  450.08  6833.9  448.99  7019.2  451.34
#Mann= 8 ,-1 , 0
  3806.4      .1       0  4458.2     .16       0  4542.5      .1       0
  4880.2     .16       0  4953.2     .07       0  5033.2     .16       0
  5213.6      .1       0  6344.5     .16       0
#XS Ineff= 2 , 0
         4756.82  424.33
Permanent Ineff=
       F       F
Bank Sta=4953.2,5033.2
XS Rating Curve= 0 ,0
Exp/Cntr=0.3,0.1

Type RM Length L Ch R = 1 ,21911   ,166,166,166
XS GIS Cut Line= 2
     3490034.542    10457061.597     3490077.945    10454492.153
#Sta/Elev= 30
       0426.371819.94081424.7163129.6152423.3818338.9937424.6071 418.757418.3355
478.5794415.0249658.0467411.4186757.7507412.3563837.5139411.67851036.922413.9199
1096.745413.20191106.715413.16961146.596411.50551156.567409.80651166.537405.5501
1176.508405.68711186.478410.78211206.419413.38661286.182413.75491385.886412.4326
1415.797409.96671465.649 413.1741844.525416.26112083.814421.08312173.548421.5463
  2223.4423.91142253.311422.31742303.163426.16562382.927427.41012552.423433.7575
#Mann= 3 ,-1 , 0
       0     .12       01096.745     .07       01206.419     .12       0
Bank Sta=1106.715,1206.419
XS Rating Curve= 0 ,0
Exp/Cntr=0.3,0.1

Type RM Length L Ch R = 1 ,21745   ,2640,2640,2640
XS GIS Cut Line= 3
     3490196.869    10457063.044     3490238.101    10454961.048
     3490360.063    10454644.063
#Sta/Elev= 30
       0 424.255139.5862421.3634279.1724420.9105329.0246419.2592408.7881414.4211
 518.463411.9466 608.197411.1928907.3102 412.835997.0441411.30181046.896411.2537
1096.749412.12861146.601411.46711156.571409.51131166.542406.66751176.512406.8427
1186.483409.56181196.453410.74221246.305410.9326 1365.95414.29351455.684415.2363
1525.478417.6587  1585.3418.98321685.005419.04041734.857418.25521764.768419.2873
1934.266421.74952242.045 432.7882291.489435.81662331.045434.21792410.156435.0767
#Mann= 3 , 0 , 0
       0     .12       01146.601     .07       01196.453     .12       0
Bank Sta=1146.601,1196.453
XS Rating Curve= 0 ,0
Exp/Cntr=0.3,0.1

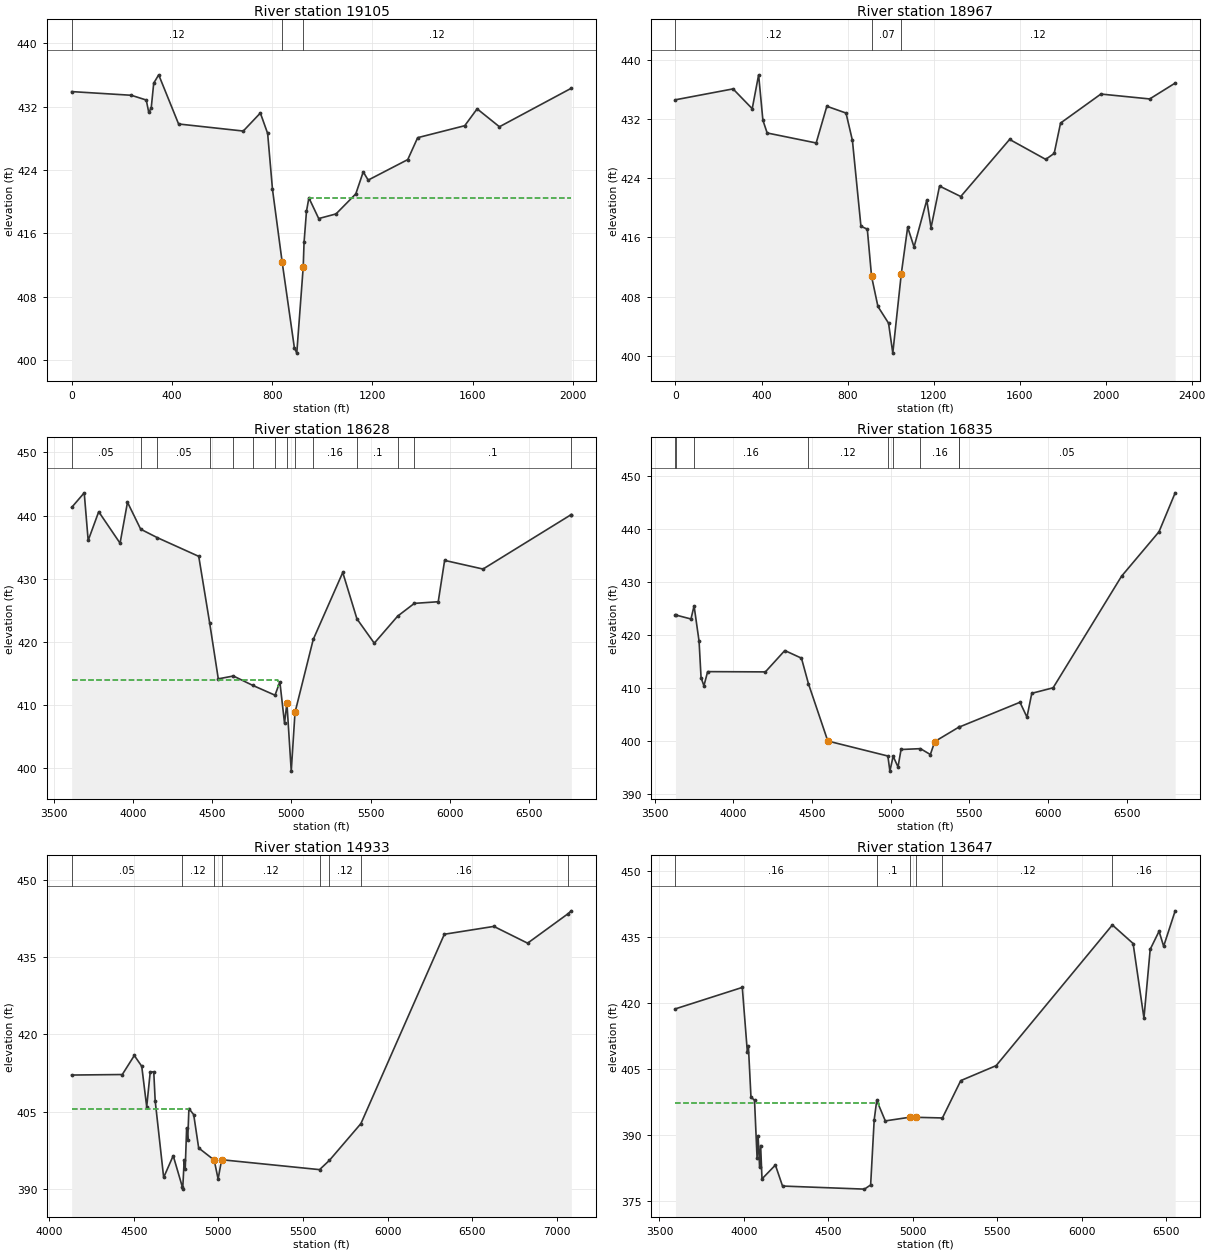
Type RM Length L Ch R = 1 ,19105   ,138,138,138
XS GIS Cut Line= 5
     3490940.914    10457418.794     3491633.622    10457314.627
     3491867.997    10457176.606     3492159.664    10456814.627
     3492235.184    10456262.544
#Sta/Elev= 30
       0433.9161238.1248433.4515 297.656432.8502307.5779 431.296317.4998431.8566
327.4216434.9838347.2654 436.035426.6403429.8246684.6089428.9322752.8661431.2097
781.9143428.6292801.2797421.5505840.0106412.3317888.4241401.5739898.1069400.8722
  923.86  411.76 927.155 414.859936.8377418.7931946.5204  420.49985.6236417.8748
1054.706418.46041133.657420.99751163.264423.77431183.002422.73551340.904425.3249
 1380.38428.09291568.178429.60611617.633431.73631706.654 429.4731993.497434.3422
#Mann= 3 , 0 , 0
       0     .12       0840.0106     .07       0  923.86     .12       0
#XS Ineff= 2 , 0
                          947.73          420.43
Permanent Ineff=
       F       F
Bank Sta=840.0106,923.86
XS Rating Curve= 0 ,0
Exp/Cntr=0.3,0.1

Type RM Length L Ch R = 1 ,18967   ,339,339,339
XS GIS Cut Line= 4
      3490888.83    10457512.544     3491750.158    10457440.821
     3492268.822    10456944.944     3492394.039    10456215.669
#Sta/Elev= 30
       0 434.591 267.572436.0596356.7626433.3856386.4928437.9582 406.313431.8387
426.1331430.1087654.0648  428.76703.6151433.7159792.8058432.7986 822.536429.1036
862.1763  417.52   891.8417.1197911.5493410.7519941.1731406.6839990.5461404.4333
1010.295400.38911049.794411.10491079.417417.38731109.041414.71941168.289 421.043
1188.038 417.3111227.536422.94131326.282421.53221553.398429.23961721.174426.5458
1760.646427.3519 1790.25431.44751977.741435.36322204.705434.70232323.121436.8451
#Mann= 3 , 0 , 0
       0     .12       0911.5493     .07       01049.794     .12       0
Bank Sta=911.5493,1049.794
XS Rating Curve= 0 ,0
Exp/Cntr=0.3,0.1

Type RM Length L Ch R = 1 ,18628   ,1793,1793,1793
BEGIN DESCRIPTION:
WHITE BRANCH 28.0
END DESCRIPTION:
XS GIS Cut Line= 4
      3490802.39     10457698.99      3491496.88     10457959.42
      3492408.34     10457351.78      3492581.96     10456049.66
#Sta/Elev= 30
  3614.3  441.29  3693.6   443.6  3718.5  436.06  3784.9  440.61  3919.6  435.63
  3966.4  442.11  4049.5  437.85  4153.5  436.52  4415.7  433.55  4484.5  423.02
  4538.9  414.17  4634.2  414.62  4755.9  413.14  4896.7  411.58  4927.2   413.7
  4956.6  407.15  4971.6  410.36    4999  399.57  5022.7  408.85  5137.7  420.41
  5323.8     431  5413.2  423.66  5522.5  419.81  5670.3   424.1  5775.2  426.11
  5925.8  426.37  5966.1  432.91  6208.2  431.54  6763.3  440.14  6765.1  440.14
#Mann= 14 ,-1 , 0
  3614.3     .05       0  4049.5      .1       0  4153.5     .05       0
  4484.5      .1       0  4634.2     .07       0  4755.9      .1       0
  4896.7     .12       0  4971.6     .07       0  5022.7     .12       0
  5137.7     .16       0  5413.2      .1       0  5670.3     .16       0
  5775.2      .1       0  6763.3     .05       0
#XS Ineff= 2 , 0
         4916.23  414.06
Permanent Ineff=
       F       F
Bank Sta=4971.6,5022.7
XS Rating Curve= 0 ,0
Exp/Cntr=0.3,0.1

Type RM Length L Ch R = 1 ,16835   ,1902,1902,1902
BEGIN DESCRIPTION:
WHITE BRANCH 24.0
END DESCRIPTION:
XS GIS Cut Line= 3
       3493189.6     10458827.43      3493645.32     10456939.46
       3493407.1     10455726.73
#Sta/Elev= 30
  3631.5   423.8  3632.2  423.77    3730  423.01  3749.7  425.49  3781.5   418.8
  3794.1  411.95  3812.3   410.4    3836  413.08  4203.3  413.03  4326.7  417.06
  4432.7  415.62  4477.2  410.79  4600.2  399.99  4982.3  397.16  4995.1  394.31
  5015.9  397.12  5046.8  395.09  5066.1  398.39  5189.5  398.55  5252.5  397.44
  5280.6  399.89  5432.6  402.59  5434.2   402.6  5822.5   407.3    5867  404.49
  5897.6  408.99  6033.3  410.03  6468.3  431.07  6706.8  439.47  6809.6  446.81
#Mann= 9 ,-1 , 0
  3631.5     .05       0  3632.2      .1       0  3749.7     .16       0
  4477.2     .12       0  4982.3     .07       0  5015.9     .12       0
  5189.5     .16       0  5432.6      .1       0  5434.2     .05       0
Bank Sta=4600.2,5280.6
XS Rating Curve= 0 ,0
Exp/Cntr=0.3,0.1

Type RM Length L Ch R = 1 ,14933   ,1286,1286,1286
BEGIN DESCRIPTION:
WHITE BRANCH 21.0
END DESCRIPTION:
XS GIS Cut Line= 3
      3494101.02     10458979.42      3495620.14     10456917.75
      3496008.95     10456874.55
#Sta/Elev= 30
  4133.3   412.1  4432.5   412.2  4503.5  415.89  4547.4   413.8  4576.7  405.94
  4597.5  412.68  4618.4  412.72  4626.8  407.11  4676.9  392.24  4733.3  396.46
  4786.6  390.48  4789.4  389.98  4798.1  395.57  4804.3  393.95  4812.7  401.88
  4818.9  399.41  4826.1   405.6  4854.4  404.42  4883.7  397.96  4975.5  395.61
  4998.6  391.93  5019.4  395.68  5597.9  393.76  5656.5  395.57  5842.3  402.69
  6335.2   439.4  6627.6  440.92    6827  437.67  7064.3  443.34  7085.4  443.94
#Mann= 8 ,-1 , 0
  4133.3     .05       0  4786.6     .12       0  4975.5     .07       0
  5019.4     .12       0  5597.9     .16       0  5656.5     .12       0
  5842.3     .16       0  7064.3     .05       0
#XS Ineff= 2 , 0
          4825.9  405.56
Permanent Ineff=
       F       F
Bank Sta=4975.5,5019.4
XS Rating Curve= 0 ,0
Exp/Cntr=0.3,0.1

Type RM Length L Ch R = 1 ,13647   ,772,772,772
BEGIN DESCRIPTION:
Mapping XS b3bf79dc
END DESCRIPTION:
XS GIS Cut Line= 3
      3494224.26     10459232.07      3495731.23     10458242.47
      3496324.98     10457252.88
#Sta/Elev= 30
  3594.9  418.65  3990.2  423.51  4020.4  408.74  4026.4  410.11  4041.5  398.61
  4062.6  397.89  4077.6  384.84  4083.6  389.86  4092.7  382.63  4098.7  387.61
  4106.8  380.03  4186.1  383.18  4228.3  378.41  4713.2  377.71  4749.7  378.66
  4770.7  393.42  4785.8  397.85  4836.5   393.2  4980.1  394.03    5016  394.02
  5174.5  393.87    5283  402.35  5492.4  405.75  6180.1  437.69  6302.9  433.48
    6367  416.54    6404  432.16  6456.4  436.26  6483.6  432.85  6551.8   440.9
#Mann= 6 ,-1 , 0
  3594.9     .16       0  4785.8      .1       0  4980.1     .07       0
    5016      .1       0  5174.5     .12       0  6180.1     .16       0
#XS Ineff= 2 , 0
       0 4800.57  397.25               0
Permanent Ineff=
       F       F
Bank Sta=4980.1,5016
XS Rating Curve= 0 ,0
Exp/Cntr=0.3,0.1

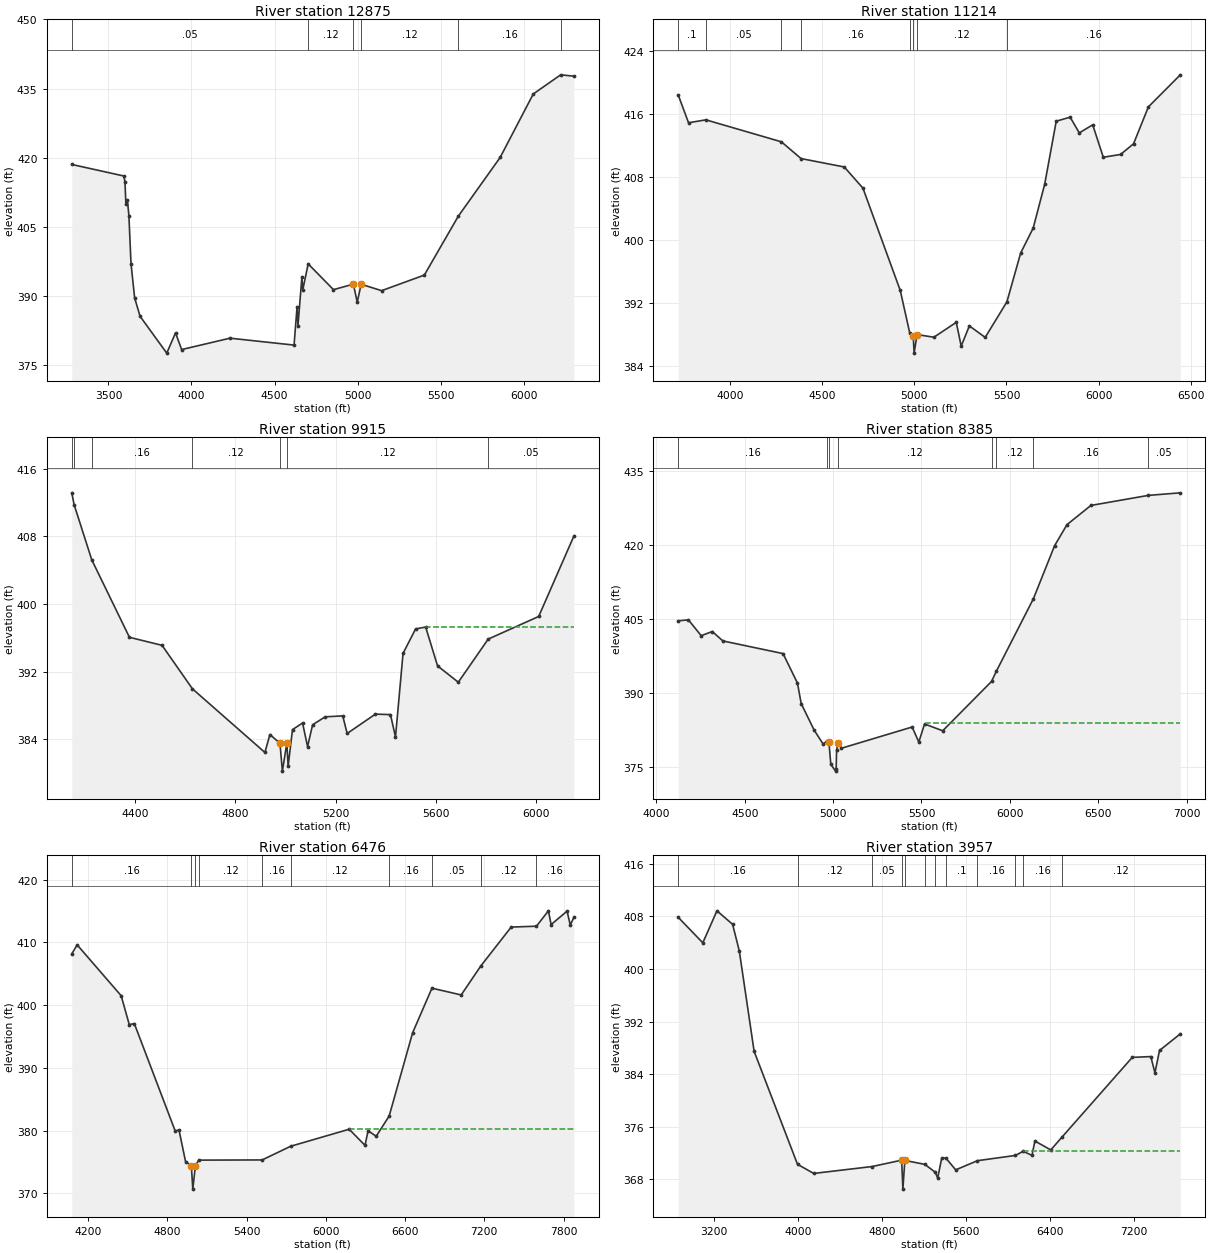
Type RM Length L Ch R = 1 ,12875   ,1661,1661,1661
BEGIN DESCRIPTION:
WHITE BRANCH 16.0
END DESCRIPTION:
XS GIS Cut Line= 2
      3494014.26     10459673.82      3496791.99     10458480.27
#Sta/Elev= 30
  3279.1  418.56  3592.4  416.06  3599.5   414.8    3605   409.9  3614.2  410.81
  3623.1  407.46  3635.9  397.03  3657.7  389.63  3690.3  385.65  3851.1  377.66
  3903.9  382.05  3940.7  378.43  4231.8   380.9  4617.7   379.4  4635.8  387.73
  4641.2  383.63  4664.8  394.13  4670.2   391.4  4702.6  397.01  4854.9  391.42
  4974.7  392.61  4998.1  388.71  5021.7  392.59  5144.9   391.2  5402.1  394.58
  5606.9  407.36  5858.7  420.08    6058  433.84    6223  437.99  6302.4   437.7
#Mann= 6 ,-1 , 0
  3279.1     .05       0  4702.6     .12       0  4974.7     .07       0
  5021.7     .12       0  5606.9     .16       0    6223     .05       0
#XS Ineff= 2 , 0
       0 4711.54   395.5               0
Permanent Ineff=
       F       F
Bank Sta=4974.7,5021.7
XS Rating Curve= 0 ,0
Exp/Cntr=0.3,0.1

Type RM Length L Ch R = 1 ,11214   ,1299,1299,1299
BEGIN DESCRIPTION:
WHITE BRANCH 12.0
END DESCRIPTION:
XS GIS Cut Line= 3
      3494122.71     10460107.85       3496466.5     10460476.78
      3496813.75     10460433.38
#Sta/Elev= 30
  3720.1  418.43  3775.9   414.9  3870.1  415.27  4279.4  412.48  4386.2  410.35
  4620.5  409.28  4721.7  406.59  4924.1  393.59  4975.5  388.19  4994.3  387.86
  4999.1  385.63  5015.3  387.99  5106.4  387.65  5227.8  389.54  5254.5  386.52
  5298.7  389.09  5384.6  387.63  5502.3  392.14  5577.2  398.36  5644.8  401.51
  5707.3  407.09  5769.9   415.1  5845.3  415.61  5894.9  413.61  5967.6  414.64
    6025  410.52  6118.6  410.87  6189.1  412.23  6269.7  416.92  6442.7  420.99
#Mann= 8 ,-1 , 0
  3720.1      .1       0  3870.1     .05       0  4279.4      .1       0
  4386.2     .16       0  4975.5     .12       0  4994.3     .07       0
  5015.3     .12       0  5502.3     .16       0
Bank Sta=4994.3,5015.3
XS Rating Curve= 0 ,0
Exp/Cntr=0.3,0.1

Type RM Length L Ch R = 1 ,9915    ,1530,1530,1530
BEGIN DESCRIPTION:
WHITE BRANCH 11.0
END DESCRIPTION:
XS GIS Cut Line= 3
      3494242.12     10461441.64      3495042.11     10461491.64
       3496242.1     10461391.64
#Sta/Elev= 30
  4146.4  413.14  4155.7  411.75  4226.1  405.23  4376.8  396.06  4507.1  395.11
  4628.4  389.97  4917.9  382.45  4937.9  384.57  4978.1  383.53  4987.8  380.24
  5005.6  383.58  5010.7  380.83  5028.2  385.15  5068.4  385.93  5088.4  383.14
  5108.5  385.72  5158.7  386.66  5228.9  386.77  5246.5  384.69  5359.4  386.98
  5419.6  386.92  5439.6  384.27  5469.8  394.16  5519.9  397.05  5560.1  397.27
  5607.7  392.68  5690.5  390.75    5810  395.85  6011.6  398.52  6152.1  408.02
#Mann= 7 ,-1 , 0
  4146.4     .16       0  4155.7     .05       0  4226.1     .16       0
  4628.4     .12       0  4978.1     .07       0  5005.6     .12       0
    5810     .05       0
#XS Ineff= 2 , 0
                         5558.24          397.26
Permanent Ineff=
       F       F
Bank Sta=4978.1,5005.6
XS Rating Curve= 0 ,0
Exp/Cntr=0.3,0.1

Type RM Length L Ch R = 1 ,8385    ,1909,1909,1909
BEGIN DESCRIPTION:
WHITE BRANCH 8.0
END DESCRIPTION:
XS GIS Cut Line= 2
      3494318.03     10462972.45      3497030.77     10462126.08
#Sta/Elev= 30
  4123.2  404.57  4180.7  404.78  4253.2  401.56    4316  402.41  4375.7   400.5
  4716.4  397.93  4797.9  391.95  4819.1  387.79  4892.2  382.41  4943.9  379.54
  4965.5  380.25    4976     380  4986.9  375.43  5013.9  374.08  5017.1  374.58
  5019.4  378.37  5028.4  379.88  5046.6  378.72  5447.1  383.03  5484.9  379.98
  5517.4  383.65  5620.1  382.27  5896.3  392.27  5923.9  394.37  6133.4  409.06
  6253.3  419.82  6323.6   424.1  6458.8  427.99  6783.7  430.03  6964.9  430.55
#Mann= 8 ,-1 , 0
  4123.2     .16       0  4965.5     .12       0    4976     .07       0
  5028.4     .12       0  5896.3     .16       0  5923.9     .12       0
  6133.4     .16       0  6783.7     .05       0
#XS Ineff= 2 , 0
                          5522.9          383.82
Permanent Ineff=
       F       F
Bank Sta=4976,5028.4
XS Rating Curve= 0 ,0
Exp/Cntr=0.3,0.1

Type RM Length L Ch R = 1 ,6476    ,2519,2519,2519
BEGIN DESCRIPTION:
WHITE BRANCH 6.0
END DESCRIPTION:
XS GIS Cut Line= 3
       3494035.9     10464404.74      3496922.23     10463797.09
      3497030.74     10462950.72
#Sta/Elev= 30
  4075.1  408.15  4115.8  409.59  4449.2  401.49  4510.6  396.89  4548.9  397.05
  4858.1  379.96  4887.4  380.09  4937.2  375.05  4980.7  374.44  4991.9  370.68
  5011.4   374.4  5036.8   375.3  5517.2  375.33  5733.1  377.51  6176.4  380.22
  6296.3  377.65  6319.4  379.98  6380.8   379.1  6479.1  382.32  6656.7  395.58
  6803.2  402.69  7024.7  401.61  7173.1  406.22  7403.2  412.42  7594.6  412.56
  7685.5  415.01  7705.7  412.82  7826.7  414.96  7850.7  412.76    7878  413.95
#Mann= 10 ,-1 , 0
  4075.1     .16       0  4980.7     .07       0  5011.4     .16       0
  5036.8     .12       0  5517.2     .16       0  5733.1     .12       0
  6479.1     .16       0  6803.2     .05       0  7173.1     .12       0
  7594.6     .16       0
#XS Ineff= 2 , 0
                         6175.81          380.24
Permanent Ineff=
       F       F
Bank Sta=4980.7,5011.4
XS Rating Curve= 0 ,0
Exp/Cntr=0.3,0.1

Type RM Length L Ch R = 1 ,3957    ,0,0,0
BEGIN DESCRIPTION:
WHITE BRANCH 1.0
END DESCRIPTION:
XS GIS Cut Line= 4
      3494079.37     10465034.09       3494925.7     10465771.92
      3497182.64      10465468.1      3497703.49     10464187.68
#Sta/Elev= 30
  2861.5  407.86  3095.5  403.98  3230.3  408.85  3379.3   406.8  3442.9  402.76
  3584.4  387.46  3997.6  370.26  4152.2  368.87  4708.5  369.92  4989.7  370.89
  5001.3  366.48    5020  370.85  5209.9  370.25  5310.1  369.05  5332.8  368.17
  5370.6  371.15  5410.4  371.22  5504.3  369.41  5711.3  370.81  6073.6  371.61
  6146.6  372.24  6230.8  371.62  6258.8   373.8  6410.2  372.45  6517.3  374.41
  7186.2  386.54  7362.9  386.66  7402.1  384.19  7445.9  387.59  7643.9  390.12
#Mann= 12 ,-1 , 0
  2861.5     .16       0  3997.6     .12       0  4708.5     .05       0
  4989.7    .035       0    5020     .05       0  5209.9      .1       0
  5310.1     .05       0  5410.4      .1       0  5711.3     .16       0
  6073.6     .12       0  6146.6     .16       0  6517.3     .12       0
#XS Ineff= 2 , 0
                         6149.86          372.31
Permanent Ineff=
       F       F
Bank Sta=4989.7,5020
XS Rating Curve= 0 ,0
Exp/Cntr=0.3,0.1
Stream Node=WHITE BRANCH    ,Reach-1         , 0 , 0 ,Upstream end
Stream Node=WHITE BRANCH    ,Reach-1         , 0 , 1 ,Downstream end

Chan Stop Cuts=-1
Use User Specified Reach Order=0
Composite Channel Slope=5