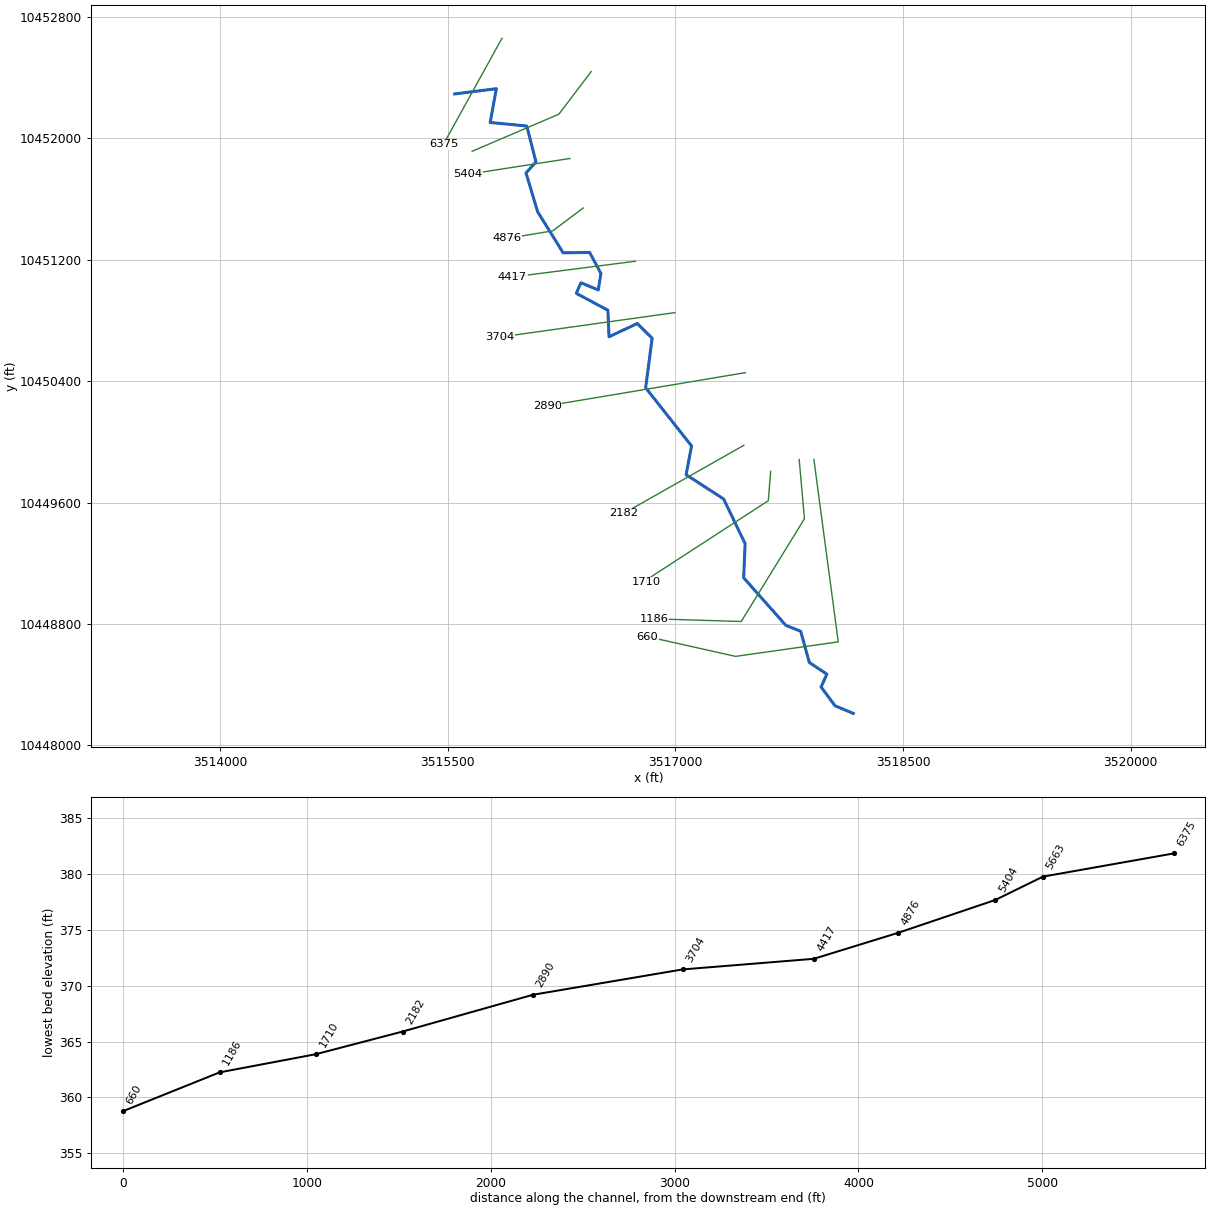
--- WILLOW CREEK TRIB 10.prj (project) ---

Proj Title=WILLOW CREEK TRIB 10 Base Level Engineering
Current Plan=p01
Default Exp/Contr=0.3,0.1
English Units
Geom File=g01
Flow File=f01
Plan File=p01
Y Axis Title=Elevation
X Axis Title(PF)=Main Channel Distance
X Axis Title(XS)=Station
BEGIN DESCRIPTION:
WILLOW CREEK TRIB 10
END DESCRIPTION:
DSS Export Rating Curves= 0
DSS Export Rating Curve Sorted= 0
DSS Export Volume Flow Curves= 0
DXF OffsetX= 0
DXF OffsetY= 0
DXF ScaleX= 1
DXF ScaleY= 10

--- WILLOW CREEK TRIB 10.p01 (plan) ---

Plan Title=Multiple Run
Short Identifier=Multiple
Geom File=g01
Flow File=f01
Subcritical Flow
K Sum by GR= 0
Std Step Tol= 0.01
Critical Tol= 0.01
Num of Std Step Trials= 20
Max Error Tol= 0.3
Flow Tol Ratio= 0.001
Split Flow NTrial= 30
Split Flow Tol= 0.02
Split Flow Ratio= 0.02
Log Output Level= 0
Friction Slope Method= 1
Unsteady Friction Slope Method= 2
Unsteady Bridges Friction Slope Method= 1
Parabolic Critical Depth
Global Vel Dist=  1 , 1 , 1
Global Log Level= 0
CheckData=True
Encroach Param= -1, 0, 0, 0
BEGIN DESCRIPTION:
Multiple Run
END DESCRIPTION:

--- WILLOW CREEK TRIB 10.f01 (steady flow) ---

Flow Title=Multiple
Number of Profiles=7
Profile Names=10-year,25-year,50-year,1pct_min,100-year,1pct_plu,500-year
River Rch & RM= WILLOW CREEK TRI,Reach-1,6375
     638     856    1031     907    1227    1660    1733
Boundary for River Rch & Prof#=WILLOW CREEK TRI,Reach-1,1
Up Type=0
Dn Type=3
Dn Slope=0.005
Boundary for River Rch & Prof#=WILLOW CREEK TRI,Reach-1,2
Up Type=0
Dn Type=3
Dn Slope=0.005
Boundary for River Rch & Prof#=WILLOW CREEK TRI,Reach-1,3
Up Type=0
Dn Type=3
Dn Slope=0.005
Boundary for River Rch & Prof#=WILLOW CREEK TRI,Reach-1,4
Up Type=0
Dn Type=3
Dn Slope=0.005
Boundary for River Rch & Prof#=WILLOW CREEK TRI,Reach-1,5
Up Type=0
Dn Type=3
Dn Slope=0.005
Boundary for River Rch & Prof#=WILLOW CREEK TRI,Reach-1,6
Up Type=0
Dn Type=3
Dn Slope=0.005
Boundary for River Rch & Prof#=WILLOW CREEK TRI,Reach-1,7
Up Type=0
Dn Type=3
Dn Slope=0.005

--- WILLOW CREEK TRIB 10.g01 (geometry) ---

Geom Title=Existing Conditions
Program Version=4.10

River Reach=WILLOW CREEK TRI,Reach-1
Reach XY= 30
      3515546.06     10452293.64      3515820.05     10452328.09
      3515779.56     10452105.64      3516020.42      10452082.2
      3516081.24     10451846.39      3516015.81      10451772.7
      3516092.37     10451516.86      3516260.33     10451246.65
      3516434.97     10451249.01      3516509.33     10451110.35
      3516491.62     10451002.06      3516377.32     10451049.28
      3516347.15     10450979.58      3516555.11     10450868.21
      3516562.57     10450693.58      3516749.18     10450780.79
      3516846.83     10450684.15      3516804.04     10450357.28
      3517106.53     10449973.91      3517070.78     10449784.47
      3517317.61     10449624.53      3517459.39     10449330.48
      3517449.99     10449105.09      3517728.33     10448791.25
      3517825.78     10448752.66      3517882.47     10448547.08
      3517998.38     10448470.25      3517960.19     10448385.49
      3518052.11     10448261.64      3518172.11     10448211.64

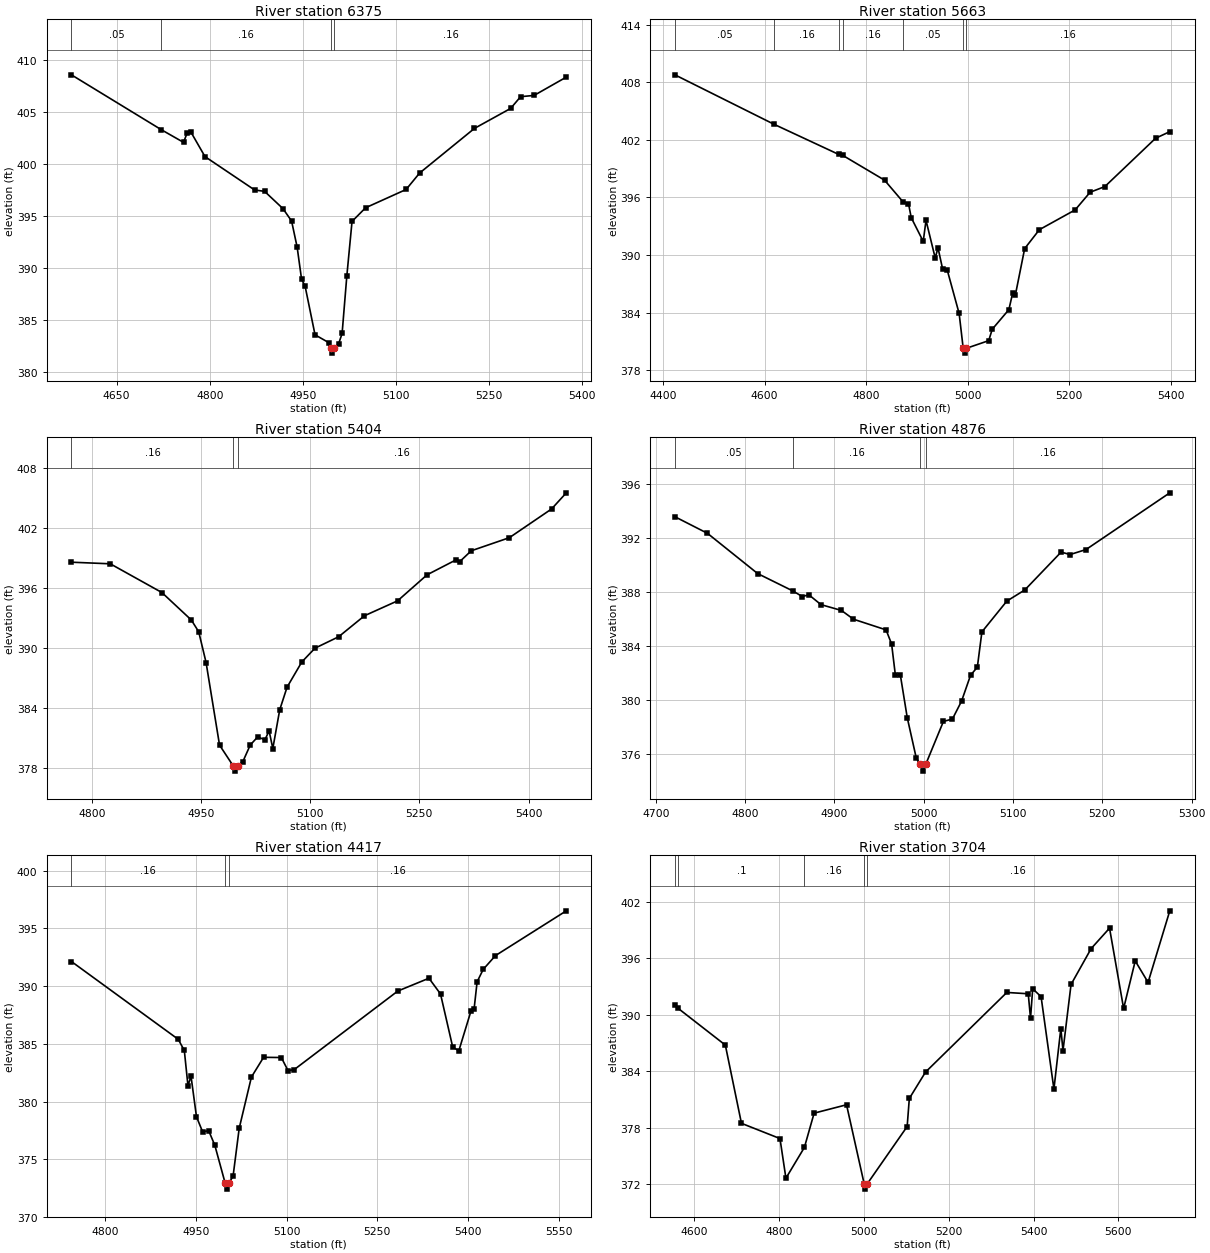
Type RM Length L Ch R = 1 ,6375    ,712,712,712
BEGIN DESCRIPTION:
WILLOW CREEK TRIB 10 13.0
END DESCRIPTION:
XS GIS Cut Line= 2
        3515857.     10452660.02      3515471.57     10451962.07
#Sta/Elev= 30
  4577.1   408.6  4721.8  403.33  4757.7  402.11  4763.4  402.98  4769.4  403.12
  4792.3  400.74  4872.3  397.53  4888.3   397.4  4917.9  395.74  4931.8  394.55
  4940.8  392.03  4947.9  388.95  4953.6  388.28  4969.6  383.61  4991.4  382.87
  4994.9  382.35  4997.7  381.85  5000.9  382.35  5007.5  382.73  5013.2  383.74
  5020.8  389.26  5029.2  394.51    5051  395.82  5116.3  397.58  5138.1  399.16
  5226.4  403.45  5284.7  405.37  5300.8   406.5  5322.5  406.62  5374.4  408.38
#Mann= 4 ,-1 , 0
  4577.1     .05       0  4721.8     .16       0  4994.9     .07       0
  5000.9     .16       0
Bank Sta=4994.9,5000.9
XS Rating Curve= 0 ,0
Exp/Cntr=0.3,0.1

Type RM Length L Ch R = 1 ,5663    ,259,259,259
BEGIN DESCRIPTION:
WILLOW CREEK TRIB 10 12.0
END DESCRIPTION:
XS GIS Cut Line= 3
      3516445.51     10452441.23        3516232.     10452160.02
      3515660.74     10451915.94
#Sta/Elev= 30
  4423.4  408.76  4618.9   403.6  4745.9  400.47  4754.2  400.36  4836.1  397.79
  4872.5  395.53  4883.3  395.35  4888.7  393.88  4912.3  391.41  4917.8   393.6
  4935.9  389.68  4941.4  390.74  4950.4  388.55  4959.5  388.44    4983   383.9
    4991  380.27  4993.7  379.77    4997  380.27  5041.2  381.07  5048.2  382.26
  5080.9   384.3  5088.4  386.03  5093.8  385.85    5112  390.66    5141  392.63
  5211.4  394.69  5240.9  396.53  5269.9  397.12  5369.7  402.15  5397.7  402.84
#Mann= 7 ,-1 , 0
  4423.4     .05       0  4618.9     .16       0  4745.9     .05       0
  4754.2     .16       0  4872.5     .05       0    4991     .07       0
    4997     .16       0
Bank Sta=4991,4997
XS Rating Curve= 0 ,0
Exp/Cntr=0.3,0.1

Type RM Length L Ch R = 1 ,5404    ,528,528,528
BEGIN DESCRIPTION:
WILLOW CREEK TRIB 10 11.0
END DESCRIPTION:
XS GIS Cut Line= 2
      3516304.89     10451868.35      3515633.02     10451764.18
#Sta/Elev= 30
    4772  398.55  4825.4  398.39  4896.3  395.52  4936.7  392.78  4946.9   391.6
    4957  388.53  4975.5  380.28  4994.5  378.18  4997.2  377.68  5000.5  378.18
  5007.6  378.64  5017.7  380.29  5027.8  381.09  5037.9  380.82  5043.6   381.7
  5048.7  379.94  5058.2  383.81  5068.3  386.07  5088.5  388.58  5106.6  389.96
  5139.1   391.1  5174.6   393.2  5220.1  394.69  5260.6  397.29  5300.6  398.79
  5305.7  398.62  5321.3  399.69  5373.7     401  5431.7  403.87  5451.9  405.48
#Mann= 3 ,-1 , 0
    4772     .16       0  4994.5     .07       0  5000.5     .16       0
Bank Sta=4994.5,5000.5
XS Rating Curve= 0 ,0
Exp/Cntr=0.3,0.1

Type RM Length L Ch R = 1 ,4876    ,459,459,459
BEGIN DESCRIPTION:
WILLOW CREEK TRIB 10 10.0
END DESCRIPTION:
XS GIS Cut Line= 3
      3516392.12     10451541.65      3516192.11     10451391.64
      3515892.06     10451341.63
#Sta/Elev= 30
  4721.3  393.58  4757.8  392.35    4814  389.37  4853.2  388.09    4864  387.67
  4871.3   387.8  4884.9  387.07  4907.8  386.64  4921.3  385.99  4957.8   385.2
    4964  384.15  4968.2  381.85  4973.8  381.85  4981.5   378.7  4991.6  375.71
  4996.2  375.24  4998.9  374.74  5002.2  375.24    5022  378.42  5032.1   378.6
  5042.3  379.92  5052.4  381.84    5060  382.44  5065.1  385.05    5093  387.33
  5113.2  388.16  5153.8  390.96  5163.9  390.78  5181.7  391.15  5275.5  395.35
#Mann= 4 ,-1 , 0
  4721.3     .05       0  4853.2     .16       0  4996.2     .07       0
  5002.2     .16       0
Bank Sta=4996.2,5002.2
XS Rating Curve= 0 ,0
Exp/Cntr=0.3,0.1

Type RM Length L Ch R = 1 ,4417    ,713,713,713
BEGIN DESCRIPTION:
WILLOW CREEK TRIB 10 9.0
END DESCRIPTION:
XS GIS Cut Line= 2
      3516737.18     10451191.26      3515925.92     10451087.26
#Sta/Elev= 30
  4744.5  392.13    4921  385.39  4931.1  384.42  4937.1  381.38  4942.2  382.18
  4951.2  378.68  4961.3  377.38  4971.4  377.47  4981.5  376.21  4998.7  372.91
  5001.4  372.41  5004.7  372.91  5011.7  373.54  5021.8  377.68    5042  382.12
  5062.1  383.83  5091.4  383.81  5102.5  382.68  5112.6  382.76  5283.9  389.57
  5335.4  390.68  5354.5  389.32  5374.7  384.71  5384.8   384.4  5404.9  387.85
    5410  388.01    5415  390.37  5425.1  391.45  5445.3  392.64  5562.4  396.52
#Mann= 3 ,-1 , 0
  4744.5     .16       0  4998.7     .07       0  5004.7     .16       0
Bank Sta=4998.7,5004.7
XS Rating Curve= 0 ,0
Exp/Cntr=0.3,0.1

Type RM Length L Ch R = 1 ,3704    ,814,814,814
BEGIN DESCRIPTION:
WILLOW CREEK TRIB 10 7.0
END DESCRIPTION:
XS GIS Cut Line= 2
      3516997.59     10450852.72       3515841.4     10450691.27
#Sta/Elev= 30
  4553.9  391.01  4561.6  390.66  4672.9  386.76  4710.9  378.45  4801.8  376.83
  4815.8  372.62  4859.4  375.89  4882.3  379.53  4958.8  380.42  5000.7  371.96
  5003.5  371.46  5006.7  371.96  5101.8  378.11  5106.9  381.09  5145.1  383.89
  5336.9  392.35  5387.4  392.21  5392.8  389.61  5397.9  392.74  5417.7   391.9
    5448  382.08  5464.3  388.52  5469.4  386.18  5488.4   393.2  5535.8  397.01
  5579.2  399.18  5612.4  390.65  5639.8   395.7  5670.1  393.42  5721.3  401.02
#Mann= 5 ,-1 , 0
  4553.9     .16       0  4561.6      .1       0  4859.4     .16       0
  5000.7     .07       0  5006.7     .16       0
Bank Sta=5000.7,5006.7
XS Rating Curve= 0 ,0
Exp/Cntr=0.3,0.1

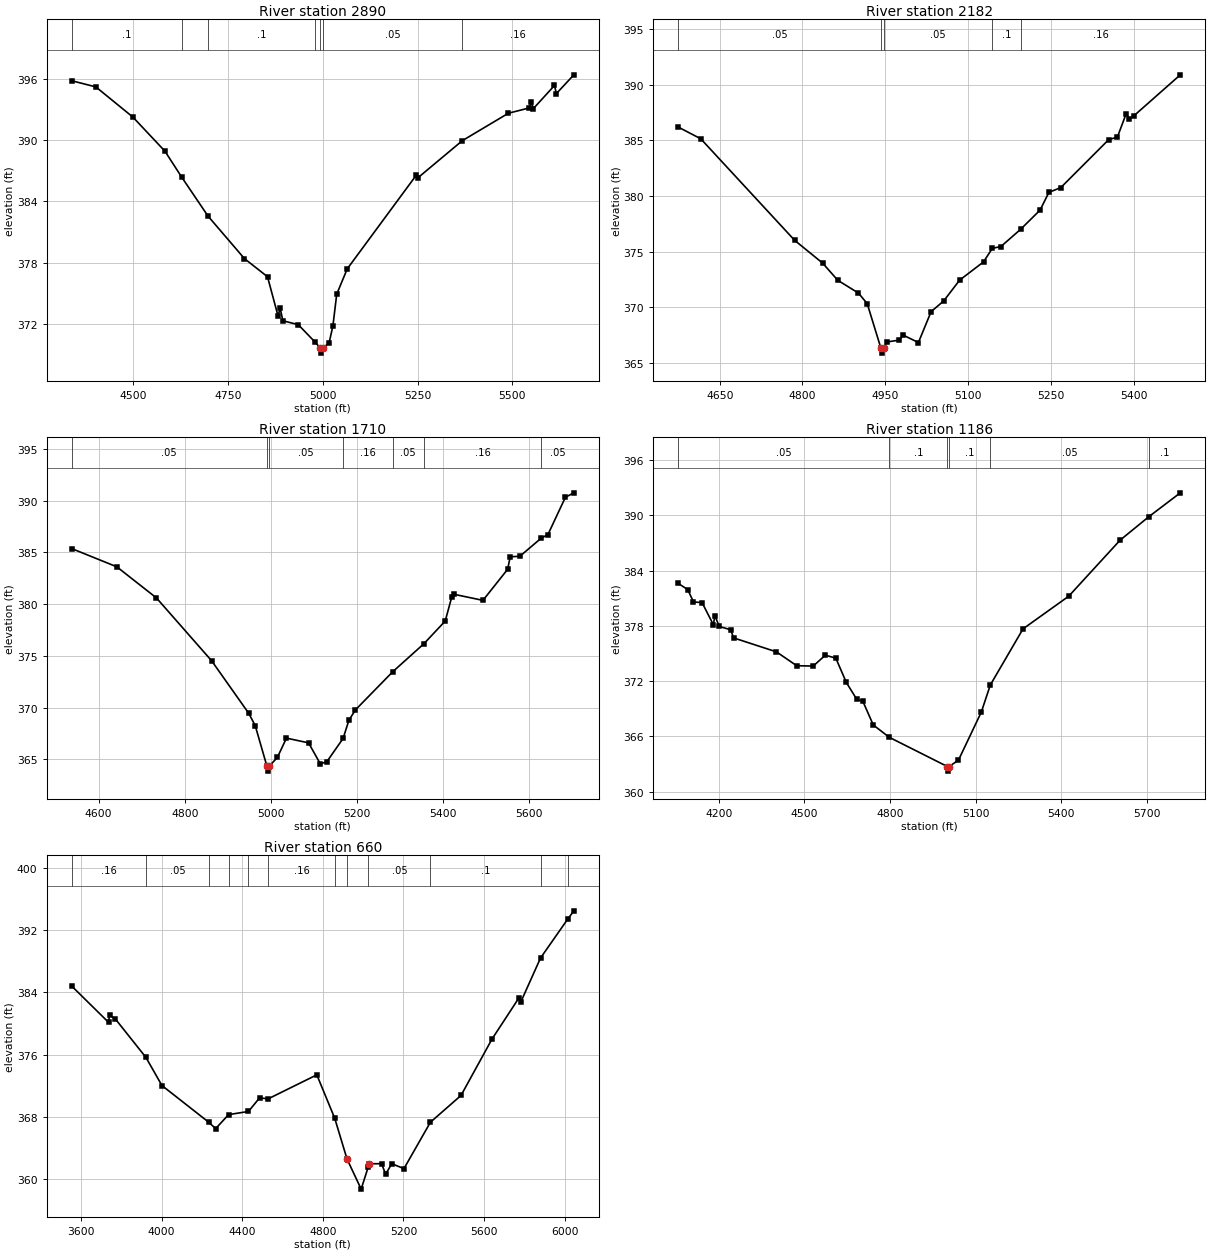
Type RM Length L Ch R = 1 ,2890    ,708,708,708
BEGIN DESCRIPTION:
WILLOW CREEK TRIB 10 5.0
END DESCRIPTION:
XS GIS Cut Line= 2
      3517461.14     10450456.89       3516155.5     10450238.41
#Sta/Elev= 30
  4338.2  395.79  4401.7  395.19  4499.4  392.24  4583.9  388.91  4627.8  386.39
  4697.5  382.57  4793.5  378.42  4854.3  376.65  4882.3  372.79  4887.4   373.6
  4894.9  372.35  4935.4  371.97  4980.1  370.25  4993.3  369.69    4996  369.19
  4999.3  369.69  5016.5  370.16  5026.7  371.84  5036.8  374.95  5064.5  377.42
  5246.6  386.57  5251.7  386.34    5368  389.94  5489.5  392.62  5543.8  393.13
  5550.2  393.69  5555.3  393.07  5610.9  395.33    5616  394.54    5662  396.37
#Mann= 7 ,-1 , 0
  4338.2      .1       0  4627.8     .05       0  4697.5      .1       0
  4980.1     .05       0  4993.3     .03       0  4999.3     .05       0
    5368     .16       0
Bank Sta=4993.3,4999.3
XS Rating Curve= 0 ,0
Exp/Cntr=0.3,0.1

Type RM Length L Ch R = 1 ,2182    ,472,472,472
BEGIN DESCRIPTION:
WILLOW CREEK TRIB 10 4.0
END DESCRIPTION:
XS GIS Cut Line= 2
      3517450.77     10449977.74       3516659.1     10449529.82
#Sta/Elev= 30
  4574.9  386.19  4615.7  385.14  4785.9  376.02  4836.5  373.98  4863.9  372.44
  4901.4  371.29  4917.3  370.34  4941.7   366.4  4944.5   365.9  4947.7   366.4
  4952.5   366.9  4975.5  367.07  4982.3  367.52    5010  366.85    5033  369.62
  5055.9  370.59  5084.7  372.45    5128  374.09    5144  375.31  5159.3  375.46
  5195.1  377.01  5230.5  378.74  5246.4  380.33    5268  380.76  5354.7  385.06
  5370.5  385.29  5386.4  387.39  5392.1  386.93  5400.6  387.21  5484.5  390.88
#Mann= 5 ,-1 , 0
  4574.9     .05       0  4941.7     .03       0  4947.7     .05       0
    5144      .1       0  5195.1     .16       0
Bank Sta=4941.7,4947.7
XS Rating Curve= 0 ,0
Exp/Cntr=0.3,0.1

Type RM Length L Ch R = 1 ,1710    ,524,524,524
BEGIN DESCRIPTION:
WILLOW CREEK TRIB 10 3.0
END DESCRIPTION:
XS GIS Cut Line= 5
      3517627.84     10449805.89      3517612.21     10449613.14
      3516810.13     10449092.31      3516810.13      10449087.1
      3516810.13     10449076.64
#Sta/Elev= 30
  4537.7  385.37  4642.3  383.61  4734.1  380.61  4862.4  374.53  4948.4  369.46
  4963.5  368.27  4990.5  364.37  4993.3  363.87  4996.5  364.37  5014.9  365.19
    5036  367.06  5087.4   366.6  5114.5  364.58  5129.6  364.77  5167.5  367.03
    5181  368.79  5196.2  369.79  5282.4  373.46  5355.1  376.18  5404.5  378.37
  5419.6  380.68  5425.6  380.95  5492.1  380.37  5549.4  383.37  5555.4  384.58
  5577.8  384.63  5627.1  386.37    5643  386.73  5683.5  390.33  5703.1  390.76
#Mann= 7 ,-1 , 0
  4537.7     .05       0  4990.5    .035       0  4996.5     .05       0
  5167.5     .16       0  5282.4     .05       0  5355.1     .16       0
  5627.1     .05       0
Bank Sta=4990.5,4996.5
XS Rating Curve= 0 ,0
Exp/Cntr=0.3,0.1

Type RM Length L Ch R = 1 ,1186    ,526,526,526
BEGIN DESCRIPTION:
WILLOW CREEK TRIB 10 1.1
END DESCRIPTION:
XS GIS Cut Line= 4
      3517815.77     10449884.83      3517850.49     10449494.22
      3517433.83     10448817.14      3516860.96      10448834.5
#Sta/Elev= 30
  4057.4  382.61  4090.7  381.94  4110.8   380.6  4140.9  380.53  4180.7  378.12
  4185.8  379.12  4201.2  377.94  4241.3  377.58  4251.4   376.7  4401.9  375.18
  4472.6  373.68  4530.6  373.64  4573.2  374.82  4609.9   374.5  4646.6  371.87
  4683.3  370.03  4704.5  369.83  4741.2  367.25  4797.3  365.91    5001  362.74
  5003.7  362.24    5007  362.74  5039.7  363.42  5119.9  368.64  5151.6  371.59
  5266.3  377.68  5426.4  381.22  5606.5   387.3  5707.4  389.85  5817.7  392.44
#Mann= 6 ,-1 , 0
  4057.4     .05       0  4797.3      .1       0    5001     .07       0
    5007      .1       0  5151.6     .05       0  5707.4      .1       0
Bank Sta=5001,5007
XS Rating Curve= 0 ,0
Exp/Cntr=0.3,0.1

Type RM Length L Ch R = 1 ,660     ,0,0,0
BEGIN DESCRIPTION:
WILLOW CREEK TRIB 10 1.0
END DESCRIPTION:
XS GIS Cut Line= 4
      3517912.66     10449885.07      3518073.26      10448682.8
      3517396.17     10448587.32      3516815.86     10448717.24
#Sta/Elev= 30
  3554.3   384.8  3736.6  380.16  3741.6  381.08  3769.6  380.62  3922.4  375.65
  4001.7  372.05    4234  367.34  4268.3  366.52  4332.5  368.32    4431  368.72
  4485.9  370.46  4529.5  370.35  4770.3  373.42  4859.3  367.84  4919.9  362.64
  4990.3  358.76  5026.1  361.66  5031.1  362.02  5091.6  362.02  5111.8  360.67
  5142.1  362.02  5202.7  361.39  5333.9  367.34  5485.9  370.78  5639.6  378.01
  5773.2  383.29  5783.1   382.8  5880.4  388.41  6015.4   393.4  6045.7  394.46
#Mann= 12 ,-1 , 0
  3554.3     .16       0  3922.4     .05       0    4234      .1       0
  4332.5     .05       0    4431      .1       0  4529.5     .16       0
  4859.3     .05       0  4919.9     .03       0  5026.1     .05       0
  5333.9      .1       0  5880.4     .05       0  6015.4     .08       0
Bank Sta=4919.9,5031.1
XS Rating Curve= 0 ,0
Exp/Cntr=0.3,0.1

Chan Stop Cuts=-1
Use User Specified Reach Order=0
Composite Channel Slope=5