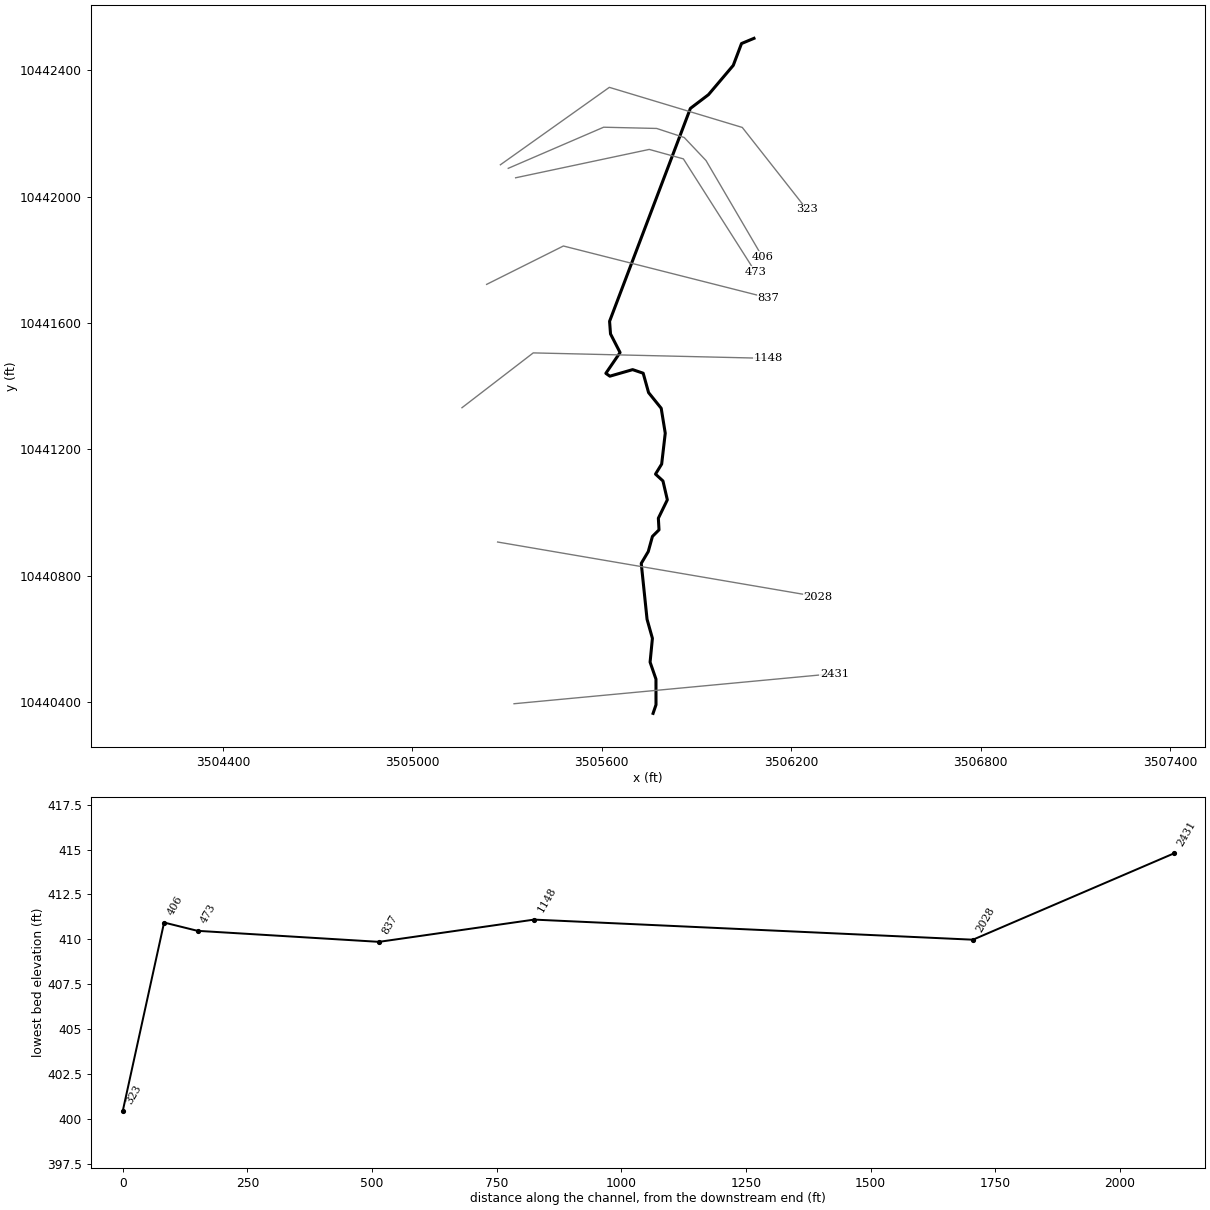
--- WILLOW CREEK TRIB 12.prj (project) ---

Proj Title=WILLOW CREEK TRIB 12 Base Level Engineering
Current Plan=p01
Default Exp/Contr=0.3,0.1
English Units
Geom File=g01
Flow File=f01
Plan File=p01
Y Axis Title=Elevation
X Axis Title(PF)=Main Channel Distance
X Axis Title(XS)=Station
BEGIN DESCRIPTION:
WILLOW CREEK TRIB 12
END DESCRIPTION:
DSS Export Rating Curves= 0
DSS Export Rating Curve Sorted= 0
DSS Export Volume Flow Curves= 0
DXF OffsetX= 0
DXF OffsetY= 0
DXF ScaleX= 1
DXF ScaleY= 10

--- WILLOW CREEK TRIB 12.p01 (plan) ---

Plan Title=Multiple Run
Short Identifier=Multiple
Geom File=g01
Flow File=f01
Subcritical Flow
K Sum by GR= 0
Std Step Tol= 0.01
Critical Tol= 0.01
Num of Std Step Trials= 20
Max Error Tol= 0.3
Flow Tol Ratio= 0.001
Split Flow NTrial= 30
Split Flow Tol= 0.02
Split Flow Ratio= 0.02
Log Output Level= 0
Friction Slope Method= 1
Unsteady Friction Slope Method= 2
Unsteady Bridges Friction Slope Method= 1
Parabolic Critical Depth
Global Vel Dist=  1 , 1 , 1
Global Log Level= 0
CheckData=True
Encroach Param= -1, 0, 0, 0
BEGIN DESCRIPTION:
Multiple Run
END DESCRIPTION:

--- WILLOW CREEK TRIB 12.f01 (steady flow) ---

Flow Title=Multiple
Number of Profiles=7
Profile Names=10-year,25-year,50-year,1pct_min,100-year,1pct_plu,500-year
River Rch & RM= WILLOW CREEK TRI,Reach-1,2431
     574     772     933     826    1117    1511    1593
Boundary for River Rch & Prof#=WILLOW CREEK TRI,Reach-1,1
Up Type=0
Dn Type=3
Dn Slope=0.005
Boundary for River Rch & Prof#=WILLOW CREEK TRI,Reach-1,2
Up Type=0
Dn Type=3
Dn Slope=0.005
Boundary for River Rch & Prof#=WILLOW CREEK TRI,Reach-1,3
Up Type=0
Dn Type=3
Dn Slope=0.005
Boundary for River Rch & Prof#=WILLOW CREEK TRI,Reach-1,4
Up Type=0
Dn Type=3
Dn Slope=0.005
Boundary for River Rch & Prof#=WILLOW CREEK TRI,Reach-1,5
Up Type=0
Dn Type=3
Dn Slope=0.005
Boundary for River Rch & Prof#=WILLOW CREEK TRI,Reach-1,6
Up Type=0
Dn Type=3
Dn Slope=0.005
Boundary for River Rch & Prof#=WILLOW CREEK TRI,Reach-1,7
Up Type=0
Dn Type=3
Dn Slope=0.005

--- WILLOW CREEK TRIB 12.g01 (geometry) ---

Geom Title=Existing Conditions
Program Version=4.10

River Reach=WILLOW CREEK TRI,Reach-1
Reach XY= 30
      3505762.53     10440363.76      3505771.78     10440390.96
      3505771.67     10440472.23      3505753.05     10440525.98
      3505760.41     10440601.31      3505743.46     10440661.68
      3505725.05     10440838.73      3505747.27     10440876.23
      3505760.47     10440924.15       3505781.3     10440944.98
      3505779.22     10440981.78      3505807.69     10441040.12
       3505793.8     10441099.84      3505770.21     10441121.54
       3505789.7     10441153.28      3505801.07     10441251.09
      3505788.25     10441330.04      3505748.28     10441379.62
      3505731.17     10441441.07      3505697.77     10441452.41
      3505625.68     10441431.67      3505612.88     10441440.62
        3505658.     10441506.59      3505627.73      10441565.5
      3505624.75     10441605.44      3505880.64     10442279.68
      3505937.93     10442323.19      3506016.47     10442416.01
      3506042.62     10442485.17      3506082.11     10442501.64

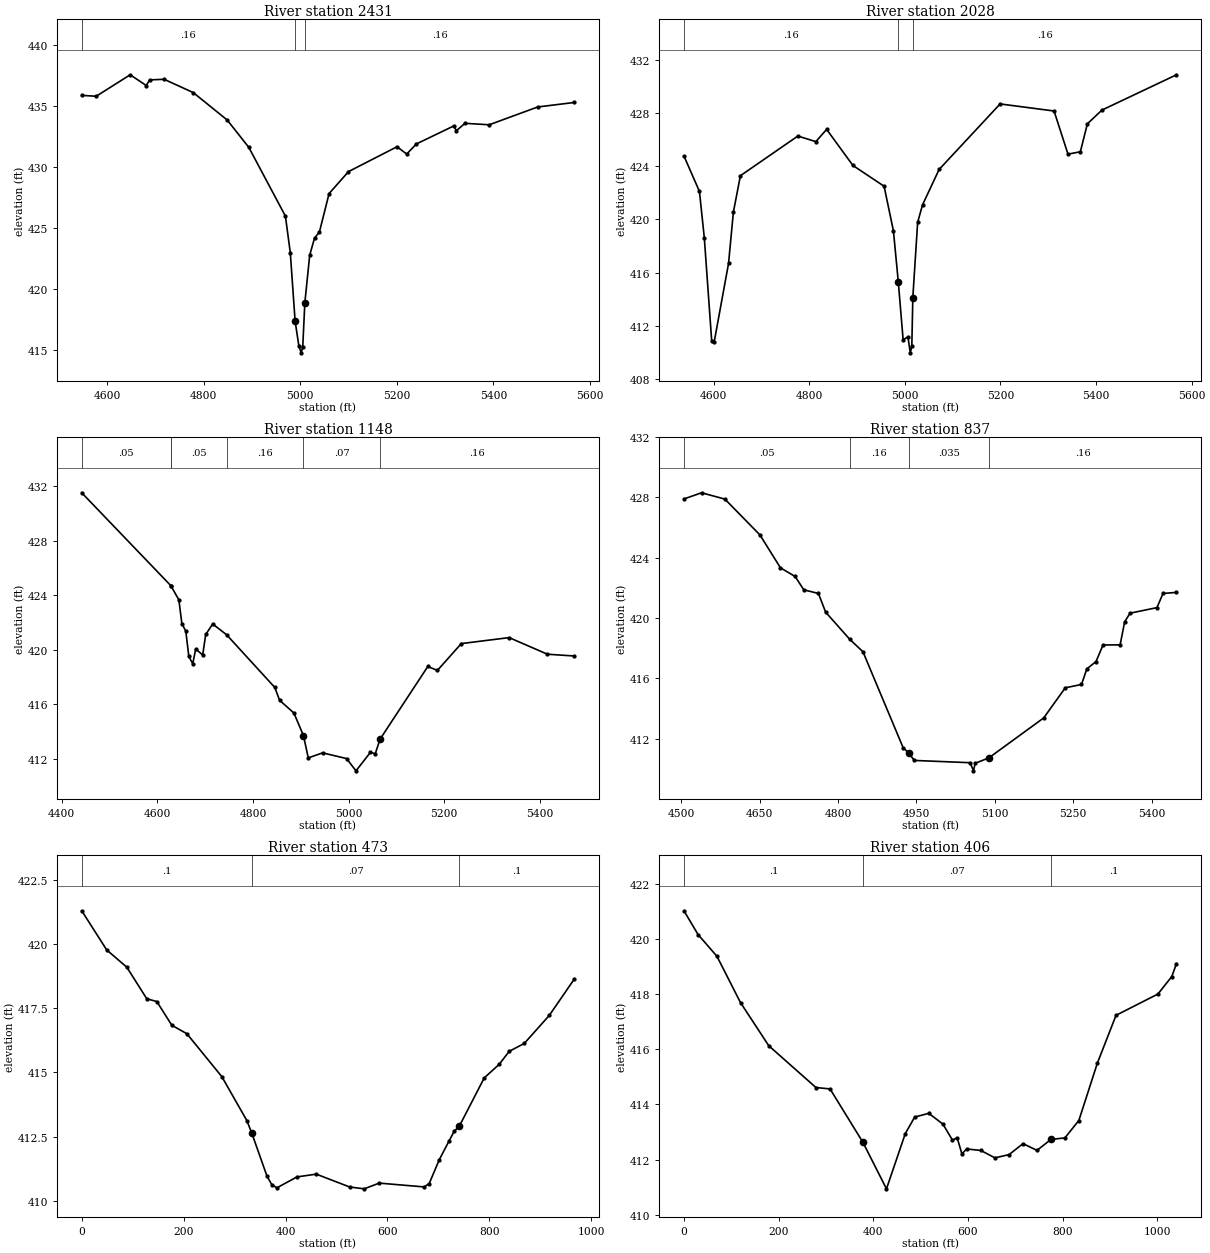
Type RM Length L Ch R = 1 ,2431    ,403,403,403
BEGIN DESCRIPTION:
WILLOW CREEK TRIB 12 2.0
END DESCRIPTION:
XS GIS Cut Line= 2
      3505322.21      10440394.3      3506337.44     10440489.75
#Sta/Elev= 30
  4547.7   435.9  4577.7  435.83    4648  437.59  4681.3  436.71  4688.2  437.17
  4718.3  437.22  4778.6  436.13  4848.9  433.88  4893.6  431.64  4969.4     426
  4979.5     423  4989.5  417.38  4997.3  415.34  5002.1  414.79  5005.3  415.29
  5009.6  418.89  5019.7   422.8  5029.7   424.2  5039.8   424.7  5059.8  427.85
    5100  429.65  5200.5  431.69  5220.5  431.09  5240.6  431.92  5318.2   433.4
  5323.3     433  5341.1  433.61  5391.3  433.49  5491.7  434.95  5567.4  435.32
#Mann= 3 , 0 , 0
  4547.7     .16       0  4989.5     .07       0  5009.6     .16       0
Bank Sta=4989.5,5009.6
XS Rating Curve= 0 ,0
Exp/Cntr=0.3,0.1

Type RM Length L Ch R = 1 ,2028    ,880,880,880
BEGIN DESCRIPTION:
WILLOW CREEK TRIB 12 3.0
END DESCRIPTION:
XS GIS Cut Line= 2
      3505270.16     10440906.46      3506285.82     10440732.84
#Sta/Elev= 30
  4537.9  424.76  4570.3   422.1  4580.5  418.61  4595.9  410.89    4601  410.77
  4631.2   416.7  4641.3  420.55    4656  423.28  4776.2  426.26  4813.8  425.84
  4836.4  426.76  4891.4  424.05  4956.6  422.49  4976.1  419.14  4986.3  415.32
  4996.4  410.97  5006.5  411.17  5011.4  409.98  5014.6  410.48  5016.7  414.13
  5026.8  419.78    5037  421.09  5071.7  423.75  5199.3  428.67  5312.2  428.14
  5341.3   424.9  5367.2  425.08  5381.9  427.18  5412.4  428.21  5568.3  430.86
#Mann= 3 , 0 , 0
  4537.9     .16       0  4986.3     .07       0  5016.7     .16       0
Bank Sta=4986.3,5016.7
XS Rating Curve= 0 ,0
Exp/Cntr=0.3,0.1

Type RM Length L Ch R = 1 ,1148    ,311,311,311
BEGIN DESCRIPTION:
WILLOW CREEK TRIB 12 4.0
END DESCRIPTION:
XS GIS Cut Line= 3
      3505157.28     10441331.78        3505383.     10441505.42
      3506128.32     10441488.08
#Sta/Elev= 30
  4441.9  431.51  4628.1   424.7  4628.5  424.68  4645.1  423.65  4651.4   421.9
  4659.6  421.36  4665.9   419.5  4674.1  418.96  4680.4  420.05  4694.9   419.6
  4701.3  421.11  4715.8  421.88  4744.9  421.09  4845.8  417.22  4855.8  416.28
  4885.8  415.34  4905.8  413.68  4915.8  412.05  4945.8  412.42  4995.9     412
  5015.6   411.1  5045.9  412.46  5055.9  412.35  5065.9  413.42  5165.9  418.76
  5185.9  418.47  5235.9  420.44    5336  420.88    5416  419.66  5472.2  419.53
#Mann= 6 ,-1 , 0
  4441.9     .05       0  4628.1     .16       0  4628.5     .05       0
  4744.9     .16       0  4905.8     .07       0  5065.9     .16       0
Bank Sta=4905.8,5065.9
XS Rating Curve= 0 ,0
Exp/Cntr=0.3,0.1

Type RM Length L Ch R = 1 ,837     ,364,364,364
BEGIN DESCRIPTION:
WILLOW CREEK TRIB 12 5.0
END DESCRIPTION:
XS GIS Cut Line= 3
      3505235.41     10441722.42      3505478.49     10441843.96
      3506128.29     10441679.34
#Sta/Elev= 30
  4505.4   427.9    4539  428.31  4583.7  427.89  4650.8  425.51    4690  423.33
  4717.9  422.76  4734.7  421.87  4762.6  421.63  4776.4  420.39  4822.2   418.6
  4847.8  417.76  4924.6   411.4  4935.6  411.03    4946  410.55  5052.8   410.4
  5059.2  409.86  5062.4  410.36  5088.6  410.72  5193.5  413.37  5234.8  415.37
  5265.8  415.59  5276.1  416.63  5293.6  417.11    5307  418.21  5339.7  418.22
  5348.3  419.74  5358.6  420.32  5410.2  420.69  5421.7  421.63  5447.5   421.7
#Mann= 4 ,-1 , 0
  4505.4     .05       0  4822.2     .16       0  4935.6    .035       0
  5088.6     .16       0
Bank Sta=4935.6,5088.6
XS Rating Curve= 0 ,0
Exp/Cntr=0.3,0.1

Type RM Length L Ch R = 1 ,473     ,67,67,67
XS GIS Cut Line= 4
     3505327.243     10442059.99      3505750.42    10442149.833
     3505858.493    10442119.885     3506086.358    10441761.812
#Sta/Elev= 30
       0421.284249.12505419.759988.42509419.0927127.7251417.8621147.3752417.7567
176.8502416.8333206.3252416.5056275.1003414.8333324.2253413.1232334.0504412.6266
363.5254410.9735373.3504410.6264383.1754 410.515422.4754410.9376460.3938411.0455
 525.945410.5464554.4901410.4743583.9388 410.697672.2847410.5486682.1009410.6818
701.7333 411.603721.3657412.3487731.1819412.7142740.9982412.9035790.0792414.7874
819.5279415.3164839.1603415.8208868.6089416.1257  917.69 417.215966.7711418.6275
#Mann= 3 , 0 , 0
       0      .1       0334.0504     .07       0740.9982      .1       0
Bank Sta=334.0504,740.9982
XS Rating Curve= 0 ,0
Exp/Cntr=0.3,0.1

Type RM Length L Ch R = 1 ,406     ,83,83,83
XS GIS Cut Line= 6
     3505303.806    10442089.937     3505605.889    10442220.146
     3505773.858     10442216.24     3505861.097    10442187.594
     3505930.108    10442114.677     3506108.493     10441809.99
#Sta/Elev= 30
       0421.020629.86725420.156769.69025419.3702 119.469417.6898179.2035416.1261
 278.761414.6113308.6283414.5598378.1826412.6197427.8255410.9368467.5398412.9385
487.3969413.5399517.2855413.6749547.2254 413.281567.1854412.7033577.1653412.7907
587.1454412.2036597.1166412.3825627.0304412.3296656.9442412.0607 686.858412.1785
716.3256412.5759745.7932412.3302775.2609412.7294804.7285412.7839 834.196413.4149
873.4862415.5024912.7764417.22981001.179418.00021030.647418.63711040.469419.1077
#Mann= 3 , 0 , 0
       0      .1       0378.1826     .07       0775.2609      .1       0
Bank Sta=378.1826,775.2609
XS Rating Curve= 0 ,0
Exp/Cntr=0.3,0.1

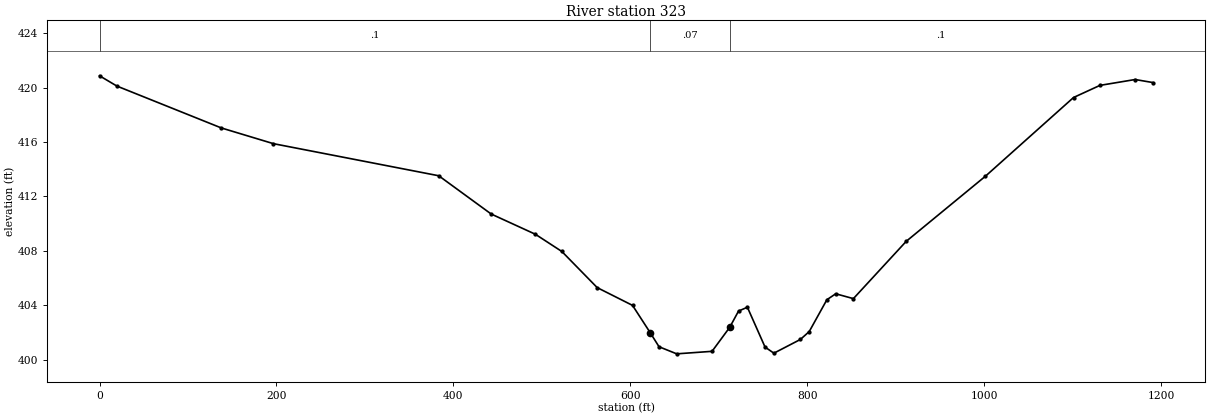
Type RM Length L Ch R = 1 ,323     ,0,0,0
XS GIS Cut Line= 4
     3505278.957    10442101.181      3505624.01    10442346.406
     3506045.017    10442219.453      3506249.01    10441960.122
#Sta/Elev= 30
       0420.883319.66375420.1252137.6463 417.045196.6375415.8858383.4432413.5251
442.7435410.7085492.6757  409.22522.6349407.9506562.5807405.2925602.5264403.9841
622.4993401.9749632.4857 400.939652.4585400.4178692.4042400.6024712.3771402.3685
722.3635403.5662  732.35403.8491752.3228400.9156762.3092400.4655792.2685 401.477
802.2549402.0562822.2278404.4009832.2142404.8381852.1871404.4817 911.933408.7001
  1001.5413.49461101.019419.28361130.875 420.1761170.682 420.6081190.586420.3867
#Mann= 3 , 0 , 0
       0      .1       0622.4993     .07       0712.3771      .1       0
Bank Sta=622.4993,712.3771
XS Rating Curve= 0 ,0
Exp/Cntr=0.3,0.1

Chan Stop Cuts=-1
Use User Specified Reach Order=0
Composite Channel Slope=5