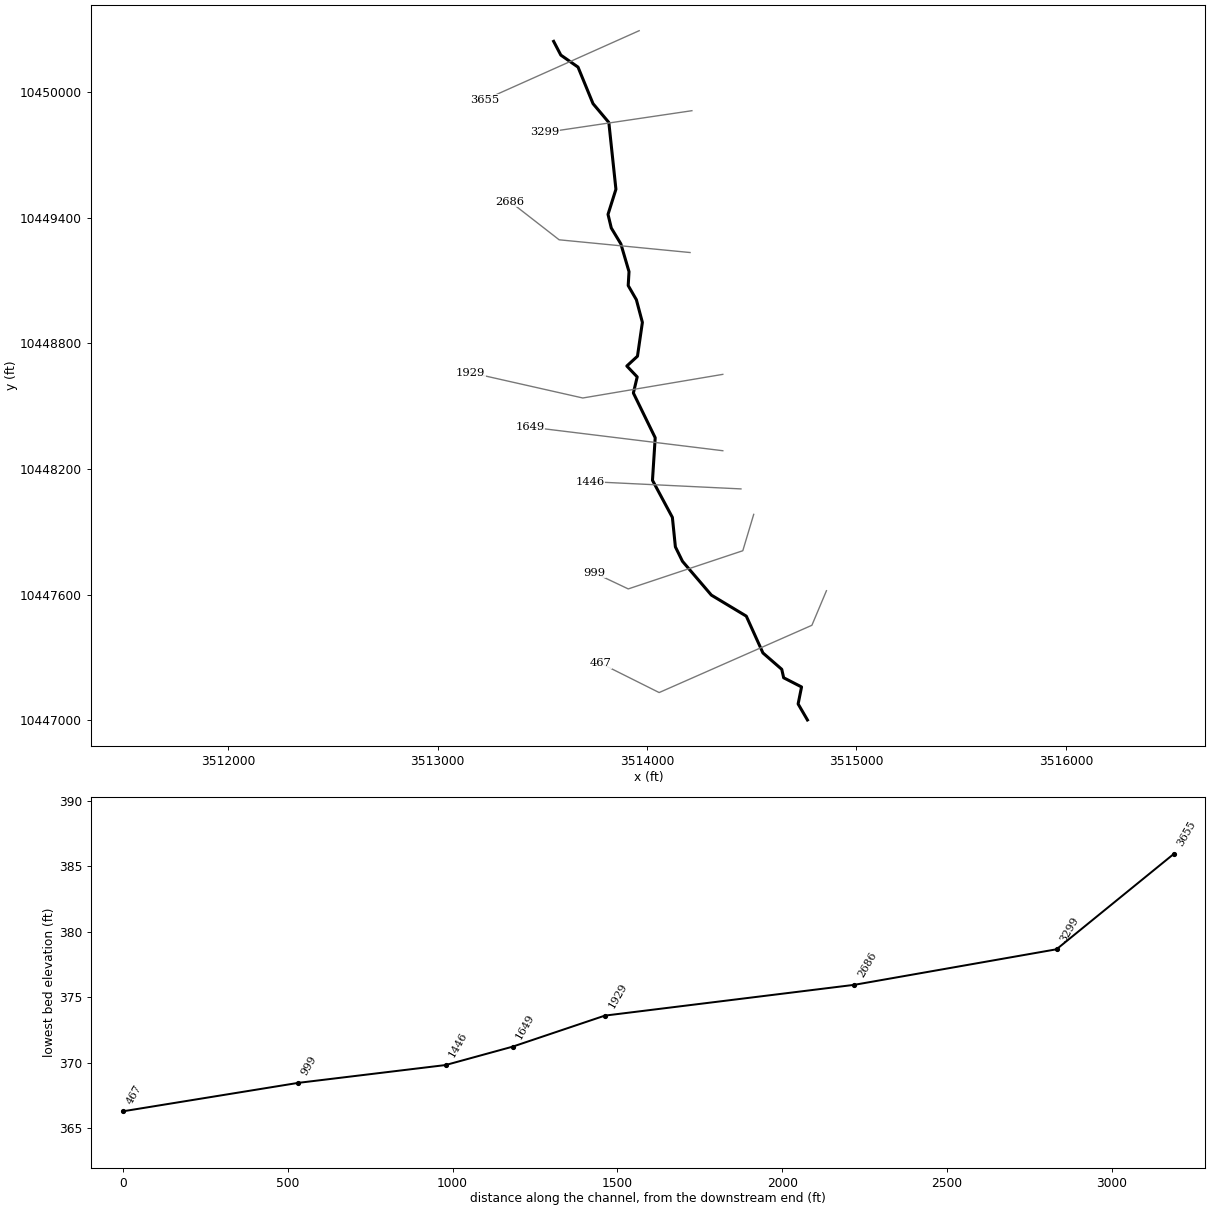
--- WILLOW CREEK TRIB 14.prj (project) ---

Proj Title=WILLOW CREEK TRIB 14 Base Level Engineering
Current Plan=p01
Default Exp/Contr=0.3,0.1
English Units
Geom File=g01
Flow File=f01
Plan File=p01
BEGIN DESCRIPTION:
WILLOW CREEK TRIB 14
END DESCRIPTION:

--- WILLOW CREEK TRIB 14.p01 (plan) ---

Plan Title=Multiple Run
Short Identifier=Multiple
Geom File=g01
Flow File=f01
Subcritical Flow
K Sum by GR= 0
Std Step Tol= 0.01
Critical Tol= 0.01
Num of Std Step Trials= 20
Max Error Tol= 0.3
Flow Tol Ratio= 0.001
Split Flow NTrial= 30
Split Flow Tol= 0.02
Split Flow Ratio= 0.02
Log Output Level= 0
Friction Slope Method= 1
Unsteady Friction Slope Method= 2
Unsteady Bridges Friction Slope Method= 1
Parabolic Critical Depth
Global Vel Dist=  1 , 1 , 1
Global Log Level= 0
CheckData=True
Encroach Param= -1, 0, 0, 0
BEGIN DESCRIPTION:
Multiple Run
END DESCRIPTION:

--- WILLOW CREEK TRIB 14.f01 (steady flow) ---

Flow Title=Multiple
Number of Profiles=7
Profile Names=10-year,25-year,50-year,1pct_min,100-year,1pct_plu,500-year
River Rch & RM= WILLOW CREEK TRI,Reach-1,3655
     576     771     927     816    1103    1492    1556
Boundary for River Rch & Prof#=WILLOW CREEK TRI,Reach-1,1
Up Type=0
Dn Type=3
Dn Slope=0.005
Boundary for River Rch & Prof#=WILLOW CREEK TRI,Reach-1,2
Up Type=0
Dn Type=3
Dn Slope=0.005
Boundary for River Rch & Prof#=WILLOW CREEK TRI,Reach-1,3
Up Type=0
Dn Type=3
Dn Slope=0.005
Boundary for River Rch & Prof#=WILLOW CREEK TRI,Reach-1,4
Up Type=0
Dn Type=3
Dn Slope=0.005
Boundary for River Rch & Prof#=WILLOW CREEK TRI,Reach-1,5
Up Type=0
Dn Type=3
Dn Slope=0.005
Boundary for River Rch & Prof#=WILLOW CREEK TRI,Reach-1,6
Up Type=0
Dn Type=3
Dn Slope=0.005
Boundary for River Rch & Prof#=WILLOW CREEK TRI,Reach-1,7
Up Type=0
Dn Type=3
Dn Slope=0.005

--- WILLOW CREEK TRIB 14.g01 (geometry) ---

Geom Title=Existing Conditions

River Reach=WILLOW CREEK TRI,Reach-1
Reach XY= 30
      3513554.14     10450241.41      3513588.48     10450175.84
      3513670.51     10450118.55      3513742.12     10449944.07
      3513817.64     10449854.23      3513851.50     10449535.22
      3513813.74     10449415.43      3513829.36     10449350.32
      3513874.94     10449274.80      3513914.00     10449141.99
      3513910.09     10449075.58      3513949.16     10449007.88
      3513977.80     10448899.80      3513954.36     10448738.34
      3513903.58     10448691.47      3513953.06     10448639.39
      3513934.83     10448562.56      3514039.00     10448349.02
      3514025.98     10448145.90      3514121.03     10447968.81
      3514135.35     10447828.19      3514169.21     10447759.18
      3514307.23     10447597.72      3514473.89     10447497.46
      3514553.32     10447321.68      3514643.17     10447243.55
      3514652.28     10447203.19      3514737.70     10447159.35
      3514721.29     10447078.19      3514765.82     10447001.77

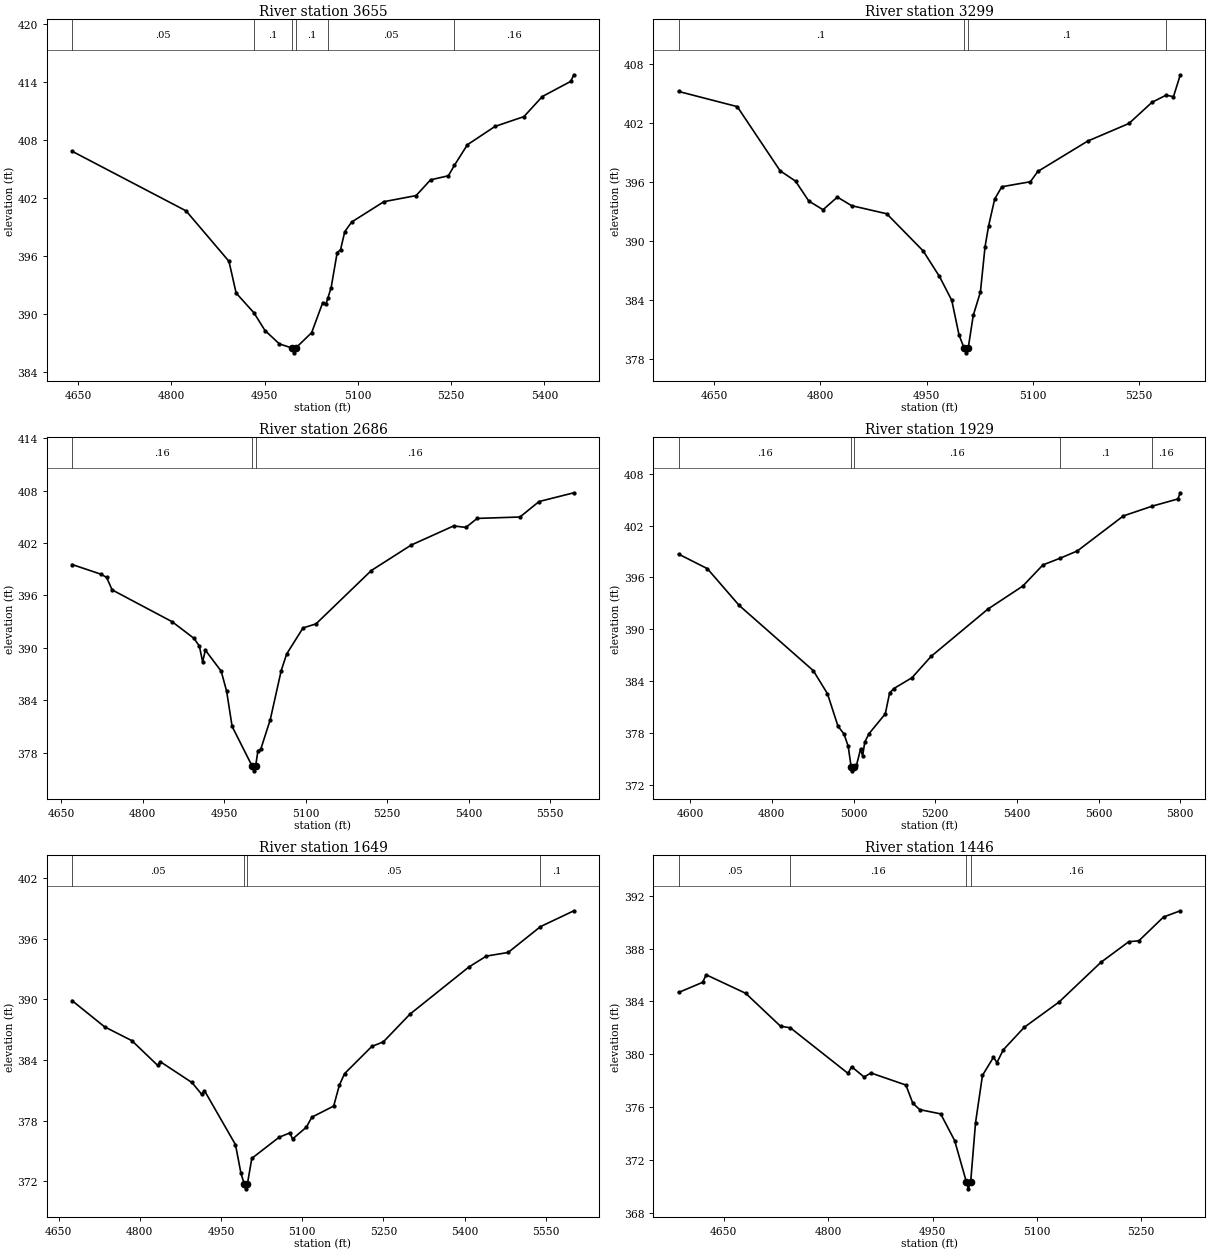
Type RM Length L Ch R = 1,3655,356,356,356
BEGIN DESCRIPTION:
WILLOW CREEK TRIB 14 8.0
END DESCRIPTION:
XS GIS Cut Line= 2
      3513962.45     10450292.32      3513225.81     10449963.00
#Sta/Elev= 30
  4640.4  406.80  4823.7  400.63  4892.7  395.41  4904.2  392.13  4933.0  390.07
  4950.6  388.25  4973.9  386.86  4994.1  386.44  4996.8  385.94  5000.1  386.44
  5025.7  388.03  5043.5  391.14  5048.9  391.02  5052.0  391.66  5057.0  392.69
  5066.7  396.32  5072.1  396.61  5078.9  398.47  5089.9  399.47  5141.8  401.58
  5193.6  402.21  5216.9  403.84  5245.5  404.26  5255.2  405.34  5276.1  407.47
  5320.6  409.37  5367.0  410.38  5396.6  412.46  5442.1  414.02  5447.3  414.71
#Mann=6,-1,0
  4640.4    0.05       0  4933.0     0.1       0  4994.1    0.07       0
  5000.1     0.1       0  5052.0    0.05       0  5255.2    0.16       0
Bank Sta=4994.1,5000.1
Exp/Cntr=0.3,0.1

Type RM Length L Ch R = 1,3299,613,613,613
BEGIN DESCRIPTION:
WILLOW CREEK TRIB 14 7.0
END DESCRIPTION:
XS GIS Cut Line= 2
      3514214.18     10449910.37      3513512.54     10449806.42
#Sta/Elev= 30
  4599.4  405.18  4682.4  403.64  4743.0  397.13  4764.8  396.08  4783.5  394.06
  4803.7  393.18  4823.9  394.46  4844.1  393.59  4893.7  392.77  4945.2  389.00
  4968.2  386.41  4985.6  383.99  4995.8  380.50  5002.9  379.16  5005.6  378.66
  5008.9  379.16  5016.0  382.46  5026.1  384.83  5032.7  389.44  5037.7  391.54
  5046.3  394.27  5056.4  395.51  5096.8  396.02  5107.2  397.06  5177.7  400.14
  5236.1  401.93  5268.7  404.08  5288.6  404.80  5299.0  404.65  5308.7  406.87
#Mann=4,-1,0
  4599.4     0.1       0  5002.9    0.07       0  5008.9     0.1       0
  5288.6    0.16       0
Bank Sta=5002.9,5008.9
Exp/Cntr=0.3,0.1

Type RM Length L Ch R = 1,2686,757,757,757
BEGIN DESCRIPTION:
WILLOW CREEK TRIB 14 6.0
END DESCRIPTION:
XS GIS Cut Line= 3
      3514205.51     10449233.28      3513580.48     10449294.05
      3513346.58     10449475.97
#Sta/Elev= 30
  4669.7  399.54  4723.4  398.42  4733.4  398.06  4743.4  396.64  4854.0  393.00
  4894.2  391.10  4904.2  390.21  4910.2  388.40  4915.2  389.75  4944.4  387.34
  4954.4  385.05  4964.5  381.03  5001.7  376.45  5004.4  375.95  5007.7  376.45
  5012.1  378.26  5017.1  378.39  5034.8  381.81  5054.9  387.40  5065.0  389.31
  5095.1  392.29  5119.0  392.75  5220.9  398.85  5294.3  401.76  5372.5  403.95
  5395.1  403.78  5415.9  404.81  5494.7  404.97  5530.0  406.74  5594.0  407.74
#Mann=3,-1,0
  4669.7    0.16       0  5001.7    0.07       0  5007.7    0.16       0
Bank Sta=5001.7,5007.7
Exp/Cntr=0.3,0.1

Type RM Length L Ch R = 1,1929,280,280,280
BEGIN DESCRIPTION:
WILLOW CREEK TRIB 14 5.0
END DESCRIPTION:
XS GIS Cut Line= 3
      3514361.70     10448651.68      3513693.33     10448538.84
      3513156.09     10448660.15
#Sta/Elev= 30
  4571.6  398.71  4642.2  397.02  4720.1  392.76  4901.5  385.21  4936.3  382.53
  4962.0  378.77  4976.9  377.86  4987.0  376.44  4994.1  374.10  4996.9  373.60
  5000.1  374.10  5007.3  374.24  5017.3  376.12  5022.4  375.34  5027.6  376.93
  5037.7  377.89  5077.8  380.20  5088.4  382.62  5098.6  383.13  5143.3  384.39
  5189.8  386.85  5328.9  392.33  5414.7  395.01  5463.7  397.45  5505.3  398.22
  5548.0  399.07  5660.8  403.13  5732.0  404.27  5794.0  405.09  5800.2  405.81
#Mann=5,-1,0
  4571.6    0.16       0  4994.1    0.07       0  5000.1    0.16       0
  5505.3     0.1       0  5732.0    0.16       0
Bank Sta=4994.1,5000.1
Exp/Cntr=0.3,0.1

Type RM Length L Ch R = 1,1649,203,203,203
BEGIN DESCRIPTION:
WILLOW CREEK TRIB 14 4.0
END DESCRIPTION:
XS GIS Cut Line= 2
      3514361.78     10448287.10      3513441.57     10448399.95
#Sta/Elev= 30
  4674.8  389.88  4734.9  387.28  4785.3  385.91  4833.0  383.46  4838.0  383.82
  4896.1  381.77  4914.4  380.59  4919.4  380.96  4976.7  375.61  4986.8  372.78
  4992.8  371.73  4995.5  371.23  4998.8  371.73  5006.9  374.25  5057.3  376.34
  5077.1  376.77  5082.2  376.17  5107.7  377.34  5117.8  378.33  5158.1  379.43
  5168.6  381.49  5178.2  382.64  5228.6  385.34  5249.9  385.79  5299.1  388.54
  5407.7  393.20  5440.2  394.29  5480.5  394.65  5540.2  397.21  5601.9  398.78
#Mann=4,-1,0
  4674.8    0.05       0  4992.8    0.04       0  4998.8    0.05       0
  5540.2     0.1       0
Bank Sta=4992.8,4998.8
Exp/Cntr=0.3,0.1

Type RM Length L Ch R = 1,1446,447,447,447
BEGIN DESCRIPTION:
WILLOW CREEK TRIB 14 3.0
END DESCRIPTION:
XS GIS Cut Line= 2
      3514448.51     10448104.81      3513728.05     10448139.53
#Sta/Elev= 30
  4584.9  384.68  4619.6  385.45  4624.6  386.02  4681.4  384.62  4731.5  382.13
  4745.6  382.01  4828.6  378.56  4833.6  379.07  4851.6  378.29  4861.6  378.59
  4911.7  377.68  4921.7  376.30  4931.7  375.82  4961.7  375.50  4981.8  373.48
  4998.8  370.33  5001.5  369.83  5004.8  370.33  5011.8  374.82  5021.8  378.41
  5037.6  379.78  5042.6  379.38  5051.8  380.35  5081.9  382.05  5131.9  383.96
  5192.0  386.96  5232.1  388.52  5246.6  388.59  5282.1  390.39  5306.2  390.86
#Mann=4,-1,0
  4584.9    0.05       0  4745.6    0.16       0  4998.8    0.07       0
  5004.8    0.16       0
Bank Sta=4998.8,5004.8
Exp/Cntr=0.3,0.1

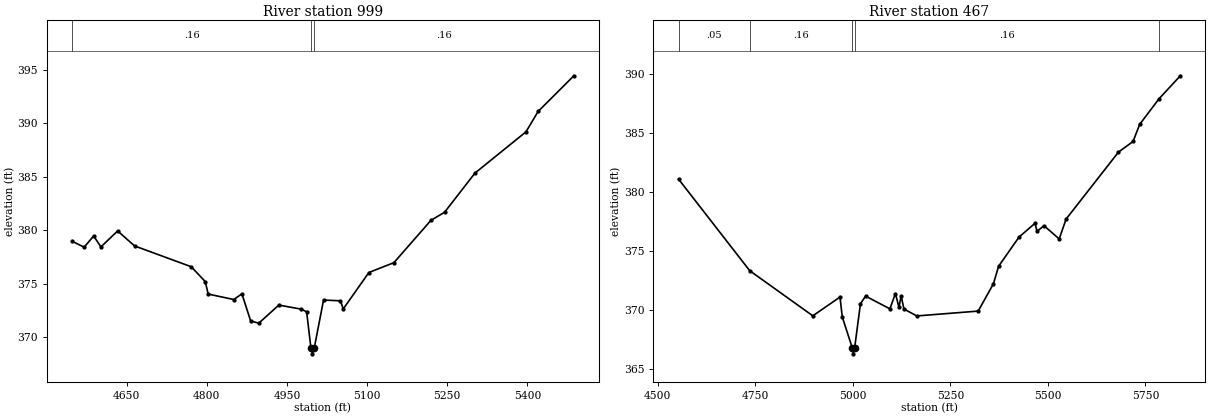
Type RM Length L Ch R = 1,999,532,532,532
BEGIN DESCRIPTION:
WILLOW CREEK TRIB 14 2.0
END DESCRIPTION:
XS GIS Cut Line= 4
      3514509.31     10447983.32      3514457.22     10447809.67
      3513910.34     10447627.38      3513746.27     10447705.10
#Sta/Elev= 30
  4547.8  378.98  4570.4  378.42  4588.2  379.47  4601.8  378.45  4633.1  379.94
  4664.8  378.54  4770.8  376.60  4797.2  375.21  4802.5  374.05  4850.4  373.54
  4865.7  374.07  4882.1  371.54  4897.3  371.33  4934.8  373.02  4976.9  372.64
  4986.9  372.39  4995.0  368.97  4997.8  368.47  5001.0  368.97  5018.5  373.49
  5050.2  373.42  5055.4  372.66  5103.4  376.06  5150.3  376.98  5219.4  380.92
  5245.2  381.69  5302.0  385.34  5397.5  389.19  5420.2  391.09  5487.1  394.42
#Mann=3,-1,0
  4547.8    0.16       0  4995.0    0.07       0  5001.0    0.16       0
Bank Sta=4995,5001
Exp/Cntr=0.3,0.1

Type RM Length L Ch R = 1,467,0,0,0
BEGIN DESCRIPTION:
WILLOW CREEK TRIB 14 1.0
END DESCRIPTION:
XS GIS Cut Line= 4
      3514856.54     10447618.74      3514787.08     10447453.77
      3514057.91     10447132.59      3513780.16     10447271.46
#Sta/Elev= 30
  4553.1  381.10  4735.6  373.34  4897.3  369.52  4967.0  371.11  4972.8  369.43
  4998.5  366.80  5001.3  366.30  5004.5  366.80  5019.4  370.54  5032.6  371.19
  5094.9  370.11  5109.1  371.41  5118.2  370.23  5123.7  371.21  5130.9  370.10
  5163.7  369.51  5321.2  369.92  5360.4  372.24  5373.4  373.71  5425.9  376.19
  5466.7  377.35  5472.2  376.68  5490.0  377.15  5528.9  376.03  5546.5  377.71
  5680.7  383.38  5718.3  384.29  5735.1  385.73  5784.5  387.89  5839.4  389.85
#Mann=5,-1,0
  4553.1    0.05       0  4735.6    0.16       0  4998.5    0.07       0
  5004.5    0.16       0  5784.5    0.05       0
Bank Sta=4998.5,5004.5
Exp/Cntr=0.3,0.1

Chan Stop Cuts=-1