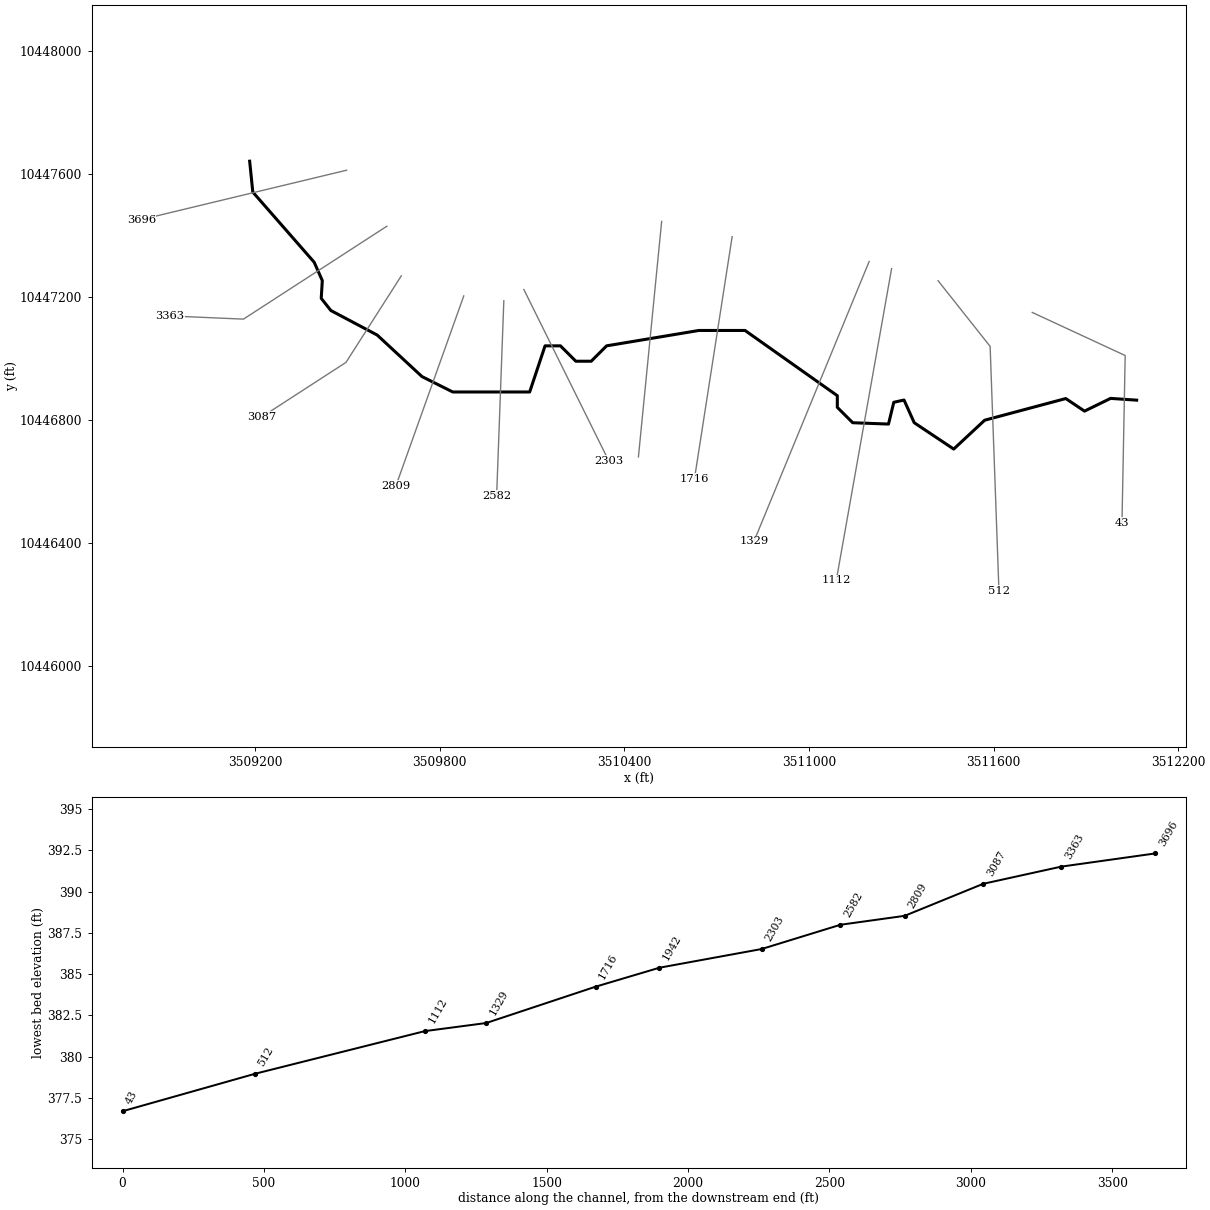
--- WILLOW CREEK TRIB 15 1.prj (project) ---

Proj Title=WILLOW CREEK TRIB 15 1 Base Level Engineering
Current Plan=p01
Default Exp/Contr=0.3,0.1
English Units
Geom File=g01
Flow File=f01
Plan File=p01
BEGIN DESCRIPTION:
WILLOW CREEK TRIB 15 1
END DESCRIPTION:

--- WILLOW CREEK TRIB 15 1.p01 (plan) ---

Plan Title=Multiple Run
Short Identifier=Multiple
Geom File=g01
Flow File=f01
Subcritical Flow
K Sum by GR= 0
Std Step Tol= 0.01
Critical Tol= 0.01
Num of Std Step Trials= 20
Max Error Tol= 0.3
Flow Tol Ratio= 0.001
Split Flow NTrial= 30
Split Flow Tol= 0.02
Split Flow Ratio= 0.02
Log Output Level= 0
Friction Slope Method= 1
Unsteady Friction Slope Method= 2
Unsteady Bridges Friction Slope Method= 1
Parabolic Critical Depth
Global Vel Dist=  1 , 1 , 1
Global Log Level= 0
CheckData=True
Encroach Param= -1, 0, 0, 0
BEGIN DESCRIPTION:
Multiple Run
END DESCRIPTION:

--- WILLOW CREEK TRIB 15 1.f01 (steady flow) ---

Flow Title=Multiple
Number of Profiles=7
Profile Names=10-year,25-year,50-year,1pct_min,100-year,1pct_plu,500-year
River Rch & RM= WILLOW CREEK TRI,Reach-1,3696
     661     891    1078     953    1289    1743    1835
Boundary for River Rch & Prof#=WILLOW CREEK TRI,Reach-1,1
Up Type=0
Dn Type=3
Dn Slope=0.005
Boundary for River Rch & Prof#=WILLOW CREEK TRI,Reach-1,2
Up Type=0
Dn Type=3
Dn Slope=0.005
Boundary for River Rch & Prof#=WILLOW CREEK TRI,Reach-1,3
Up Type=0
Dn Type=3
Dn Slope=0.005
Boundary for River Rch & Prof#=WILLOW CREEK TRI,Reach-1,4
Up Type=0
Dn Type=3
Dn Slope=0.005
Boundary for River Rch & Prof#=WILLOW CREEK TRI,Reach-1,5
Up Type=0
Dn Type=3
Dn Slope=0.005
Boundary for River Rch & Prof#=WILLOW CREEK TRI,Reach-1,6
Up Type=0
Dn Type=3
Dn Slope=0.005
Boundary for River Rch & Prof#=WILLOW CREEK TRI,Reach-1,7
Up Type=0
Dn Type=3
Dn Slope=0.005

--- WILLOW CREEK TRIB 15 1.g01 (geometry) ---

Geom Title=Existing Conditions

River Reach=WILLOW CREEK TRI,Reach-1
Reach XY= 30
      3509181.90     10447641.98      3509192.11     10447541.64
      3509391.62     10447313.50      3509418.01     10447253.78
      3509414.54     10447196.14      3509445.79     10447156.56
      3509596.48     10447076.70      3509742.11     10446941.64
      3509842.11     10446891.64      3510092.11     10446891.64
      3510142.11     10447041.64      3510192.11     10447041.64
      3510242.11     10446991.64      3510292.11     10446991.64
      3510342.11     10447041.64      3510642.11     10447091.64
      3510792.11     10447091.64      3511092.11     10446879.56
      3511092.11     10446841.64      3511142.11     10446791.64
      3511258.46     10446787.29      3511275.65     10446858.12
      3511308.98     10446865.41      3511342.11     10446791.64
      3511470.44     10446706.04      3511570.96     10446799.79
      3511834.69     10446870.28      3511895.63     10446829.40
      3511980.43     10446870.80      3512065.11     10446865.03

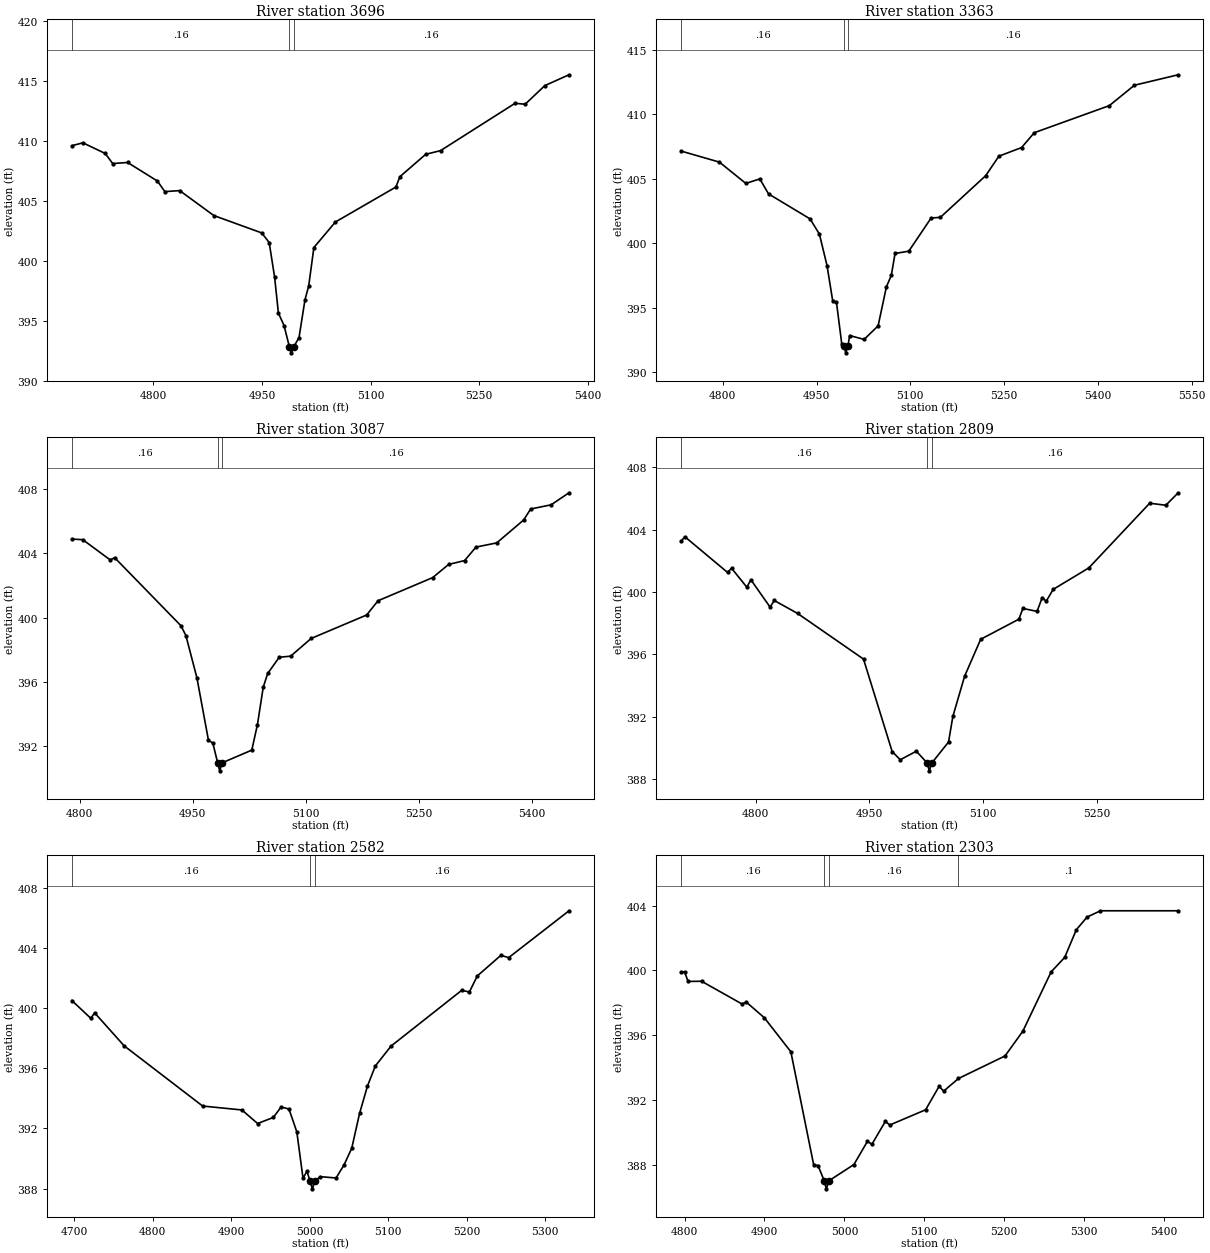
Type RM Length L Ch R = 1,3696,333,333,333
BEGIN DESCRIPTION:
WILLOW CREEK TRIB 15 1 11.0
END DESCRIPTION:
XS GIS Cut Line= 2
      3509496.95     10447612.68      3508829.70     10447452.11
#Sta/Elev= 30
  4687.6  409.60  4702.9  409.84  4733.7  408.95  4744.0  408.11  4764.6  408.20
  4805.7  406.65  4816.0  405.77  4836.5  405.85  4883.6  403.77  4949.7  402.32
  4960.0  401.52  4967.5  398.63  4972.7  395.64  4980.6  394.57  4987.9  392.81
  4990.6  392.31  4993.9  392.81  5001.2  393.59  5009.4  396.73  5014.6  397.91
  5021.7  401.10  5051.4  403.23  5134.9  406.15  5140.4  407.01  5176.0  408.88
  5196.6  409.19  5299.4  413.14  5313.3  413.06  5340.6  414.62  5373.9  415.52
#Mann=3,-1,0
  4687.6    0.16       0  4987.9    0.07       0  4993.9    0.16       0
Bank Sta=4987.9,4993.9
Exp/Cntr=0.3,0.1

Type RM Length L Ch R = 1,3363,276,276,276
BEGIN DESCRIPTION:
WILLOW CREEK TRIB 15 1 10.1
END DESCRIPTION:
XS GIS Cut Line= 3
      3509627.90     10447430.59      3509161.73     10447128.49
      3508922.15     10447138.90
#Sta/Elev= 30
  4733.2  407.15  4794.7  406.29  4836.9  404.64  4859.3  404.99  4873.2  403.83
  4939.7  401.89  4954.6  400.71  4966.8  398.27  4976.0  395.50  4981.9  395.43
  4990.3  392.22  4994.1  392.01  4996.8  391.51  5000.1  392.01  5003.0  392.85
  5026.1  392.55  5048.5  393.60  5061.8  396.63  5069.6  397.51  5075.6  399.21
  5097.6  399.39  5133.3  401.96  5148.1  402.01  5220.6  405.24  5241.7  406.75
  5278.0  407.42  5298.3  408.57  5418.4  410.67  5458.5  412.25  5528.5  413.06
#Mann=3,-1,0
  4733.2    0.16       0  4994.1    0.07       0  5000.1    0.16       0
Bank Sta=4994.1,5000.1
Exp/Cntr=0.3,0.1

Type RM Length L Ch R = 1,3087,278,278,278
BEGIN DESCRIPTION:
WILLOW CREEK TRIB 15 1 10
END DESCRIPTION:
XS GIS Cut Line= 3
      3509674.75     10447269.12      3509495.06     10446987.86
      3509221.65     10446810.79
#Sta/Elev= 30
  4789.8  404.90  4804.3  404.86  4840.7  403.60  4846.6  403.74  4934.6  399.50
  4941.1  398.89  4955.7  396.26  4971.0  392.38  4976.9  392.19  4983.2  390.97
  4985.9  390.47  4989.2  390.97  5028.5  391.76  5036.0  393.35  5043.7  395.68
  5049.6  396.53  5064.9  397.54  5080.1  397.61  5107.2  398.71  5180.8  400.17
  5196.0  401.06  5268.5  402.50  5289.6  403.32  5310.8  403.56  5325.9  404.40
  5353.4  404.66  5389.2  406.09  5398.4  406.77  5425.5  407.03  5449.3  407.78
#Mann=3,-1,0
  4789.8    0.16       0  4983.2    0.07       0  4989.2    0.16       0
Bank Sta=4983.2,4989.2
Exp/Cntr=0.3,0.1

Type RM Length L Ch R = 1,2809,227,227,227
BEGIN DESCRIPTION:
WILLOW CREEK TRIB 15 1 9
END DESCRIPTION:
XS GIS Cut Line= 2
      3509877.89     10447204.04      3509657.25     10446586.26
#Sta/Elev= 30
  4701.5  403.26  4706.6  403.55  4762.9  401.26  4768.2  401.53  4788.4  400.31
  4793.7  400.79  4819.1  399.03  4824.5  399.46  4855.3  398.63  4942.3  395.70
  4980.1  389.77  4990.8  389.24  5012.0  389.79  5026.4  389.03  5029.1  388.53
  5032.4  389.03  5054.5  390.38  5060.2  392.02  5075.7  394.60  5096.9  396.97
  5147.3  398.26  5152.6  398.95  5171.3  398.76  5178.1  399.65  5183.4  399.41
  5192.5  400.17  5239.6  401.55  5319.9  405.70  5341.2  405.57  5357.5  406.37
#Mann=3,-1,0
  4701.5    0.16       0  5026.4    0.07       0  5032.4    0.16       0
Bank Sta=5026.4,5032.4
Exp/Cntr=0.3,0.1

Type RM Length L Ch R = 1,2582,279,279,279
BEGIN DESCRIPTION:
WILLOW CREEK TRIB 15 1 8
END DESCRIPTION:
XS GIS Cut Line= 2
      3510008.08     10447188.34      3509984.71     10446554.77
#Sta/Elev= 30
  4696.7  400.50  4720.8  399.32  4725.8  399.68  4763.4  397.49  4863.5  393.49
  4913.5  393.23  4933.6  392.33  4953.6  392.73  4963.6  393.43  4973.6  393.29
  4983.6  391.77  4991.5  388.69  4996.5  389.16  5000.6  388.49  5003.4  387.99
  5006.6  388.49  5013.6  388.80  5033.6  388.71  5043.6  389.56  5053.6  390.68
  5063.6  393.00  5073.7  394.82  5083.7  396.15  5103.7  397.47  5193.7  401.17
  5203.7  401.07  5213.7  402.13  5243.8  403.50  5253.8  403.35  5330.7  406.46
#Mann=3,-1,0
  4696.7    0.16       0  5000.6    0.07       0  5006.6    0.16       0
Bank Sta=5000.6,5006.6
Exp/Cntr=0.3,0.1

Type RM Length L Ch R = 1,2303,361,361,361
BEGIN DESCRIPTION:
WILLOW CREEK TRIB 15 1 7
END DESCRIPTION:
XS GIS Cut Line= 2
      3510073.20     10447224.80      3510349.24     10446667.52
#Sta/Elev= 30
  4795.6  399.91  4800.0  399.91  4804.5  399.32  4821.4  399.33  4871.8  397.93
  4877.4  398.04  4899.8  397.08  4933.0  394.98  4961.5  388.02  4967.1  387.95
  4974.7  387.02  4977.4  386.52  4980.7  387.02  5011.9  388.02  5028.8  389.45
  5034.4  389.27  5051.2  390.68  5056.8  390.46  5101.6  391.40  5118.5  392.85
  5124.1  392.55  5142.7  393.33  5200.9  394.72  5223.2  396.25  5258.6  399.91
  5275.5  400.80  5290.1  402.51  5303.5  403.29  5320.3  403.68  5417.5  403.68
#Mann=4,-1,0
  4795.6    0.16       0  4974.7    0.07       0  4980.7    0.16       0
  5142.7     0.1       0
Bank Sta=4974.7,4980.7
Exp/Cntr=0.3,0.1

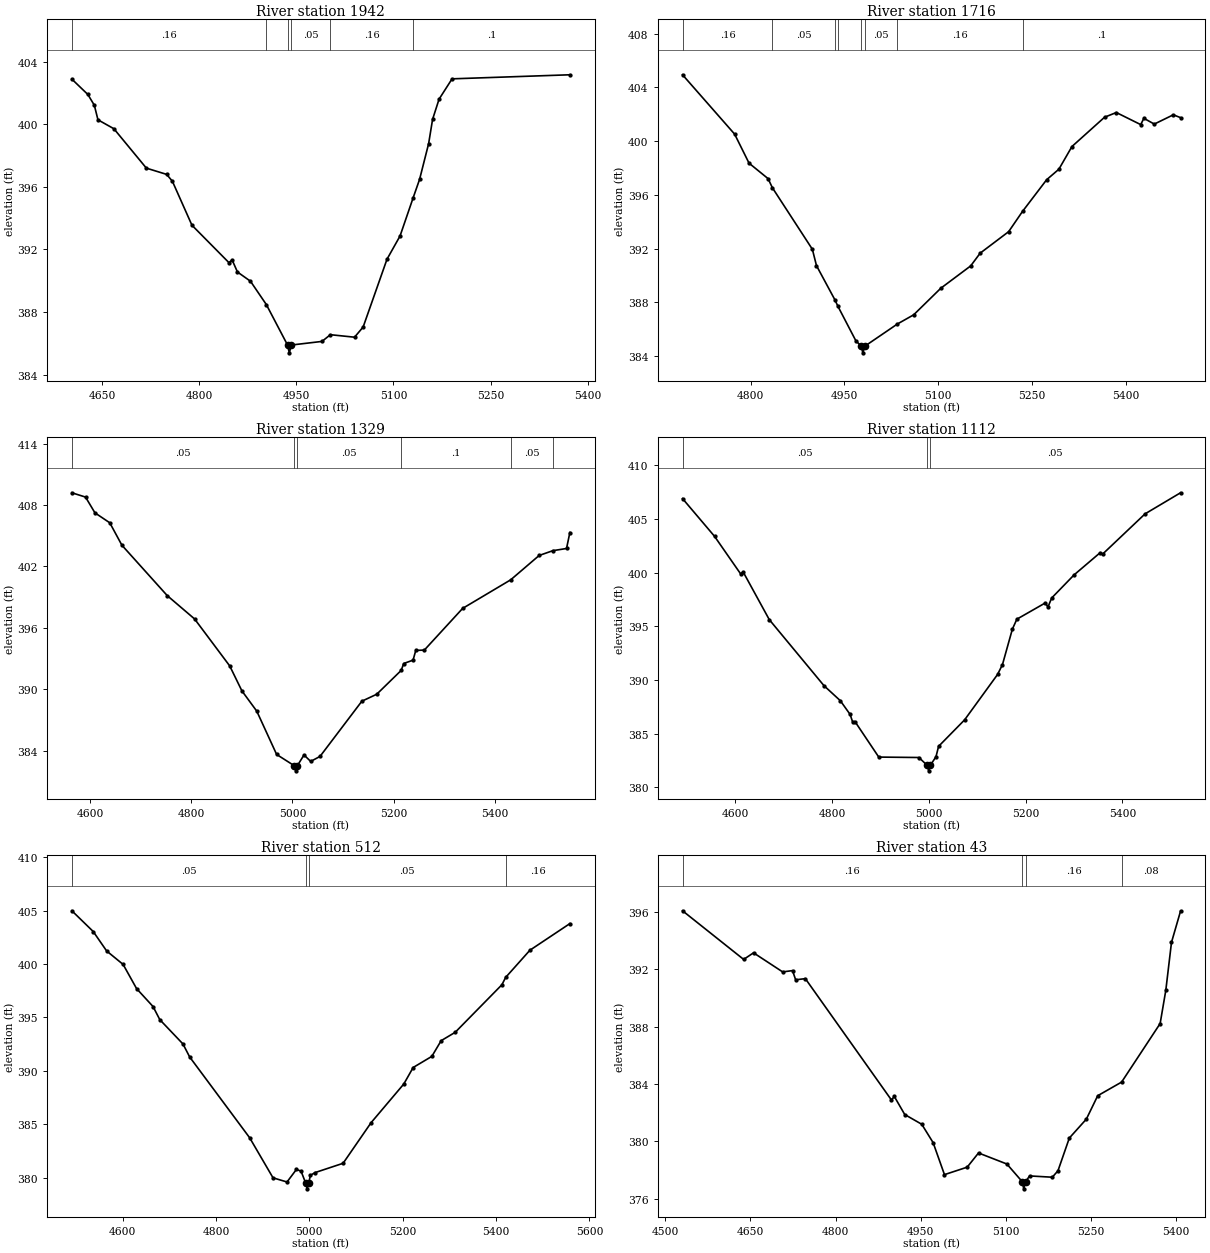
Type RM Length L Ch R = 1,1942,226,226,226
BEGIN DESCRIPTION:
WILLOW CREEK TRIB 15 1 6
END DESCRIPTION:
XS GIS Cut Line= 2
      3510521.10     10447446.21      3510445.58     10446680.53
#Sta/Elev= 30
  4603.2  402.89  4627.9  401.91  4637.9  401.22  4643.5  400.29  4668.1  399.72
  4718.3  397.20  4749.7  396.80  4758.5  396.36  4788.7  393.55  4845.8  391.16
  4850.8  391.33  4859.0  390.56  4879.1  389.97  4903.6  388.48  4936.4  385.89
  4939.1  385.39  4942.4  385.89  4989.6  386.12  5002.6  386.55  5039.9  386.39
  5053.2  387.04  5090.1  391.38  5110.2  392.86  5130.6  395.32  5140.4  396.48
  5154.4  398.77  5160.5  400.32  5170.5  401.61  5190.6  402.91  5372.6  403.17
#Mann=6,-1,0
  4603.2    0.16       0  4903.6    0.05       0  4936.4   0.035       0
  4942.4    0.05       0  5002.6    0.16       0  5130.6     0.1       0
Bank Sta=4936.4,4942.4
Exp/Cntr=0.3,0.1

Type RM Length L Ch R = 1,1716,387,387,387
BEGIN DESCRIPTION:
WILLOW CREEK TRIB 15 1 5
END DESCRIPTION:
XS GIS Cut Line= 2
      3510750.26     10447396.67      3510627.87     10446610.24
#Sta/Elev= 30
  4691.3  404.94  4774.6  400.52  4797.6  398.36  4828.0  397.21  4834.9  396.53
  4898.8  391.95  4905.4  390.73  4934.9  388.18  4939.8  387.69  4968.3  385.14
  4976.8  384.74  4979.5  384.24  4982.8  384.74  5034.8  386.39  5060.7  387.07
  5104.1  389.05  5151.8  390.71  5167.0  391.66  5212.5  393.26  5234.7  394.77
  5273.3  397.13  5292.8  397.91  5313.7  399.60  5365.8  401.78  5384.6  402.13
  5423.6  401.23  5428.6  401.70  5445.3  401.27  5475.7  401.96  5487.2  401.75
#Mann=8,-1,0
  4691.3    0.16       0  4834.9    0.05       0  4934.9    0.16       0
  4939.8    0.05       0  4976.8   0.035       0  4982.8    0.05       0
  5034.8    0.16       0  5234.7     0.1       0
Bank Sta=4976.8,4982.8
Exp/Cntr=0.3,0.1

Type RM Length L Ch R = 1,1329,217,217,217
BEGIN DESCRIPTION:
WILLOW CREEK TRIB 15 1 4
END DESCRIPTION:
XS GIS Cut Line= 2
      3511195.59     10447316.00      3510821.00     10446405.54
#Sta/Elev= 30
  4563.9  409.19  4590.9  408.77  4609.5  407.23  4638.8  406.26  4662.8  404.07
  4752.4  399.15  4806.5  396.87  4876.0  392.28  4900.0  389.85  4929.4  387.87
  4968.7  383.64  5003.6  382.54  5006.4  382.04  5009.6  382.54  5022.8  383.59
  5036.0  382.96  5054.5  383.45  5137.2  388.84  5166.6  389.52  5215.0  391.85
  5219.9  392.52  5238.4  392.85  5243.8  393.80  5260.7  393.83  5336.4  397.90
  5431.4  400.69  5487.7  403.07  5515.0  403.54  5541.8  403.75  5548.4  405.31
#Mann=6,-1,0
  4563.9    0.05       0  5003.6    0.03       0  5009.6    0.05       0
  5215.0     0.1       0  5431.4    0.05       0  5515.0     0.1       0
Bank Sta=5003.6,5009.6
Exp/Cntr=0.3,0.1

Type RM Length L Ch R = 1,1112,600,600,600
BEGIN DESCRIPTION:
WILLOW CREEK TRIB 15 1 3
END DESCRIPTION:
XS GIS Cut Line= 2
      3511268.49     10447292.52      3511088.81     10446279.54
#Sta/Elev= 30
  4491.3  406.88  4557.4  403.37  4611.4  399.87  4616.5  400.06  4670.5  395.62
  4783.6  389.47  4817.2  388.08  4837.5  386.80  4842.7  386.10  4847.8  386.12
  4896.7  382.83  4979.7  382.79  4997.0  382.05  4999.8  381.55  5003.0  382.05
  5014.9  382.86  5020.3  383.83  5074.0  386.29  5142.2  390.52  5152.3  391.44
  5172.7  394.73  5182.0  395.66  5241.1  397.18  5246.2  396.78  5253.9  397.63
  5300.2  399.78  5354.2  401.85  5359.3  401.72  5446.9  405.46  5520.1  407.42
#Mann=3,-1,0
  4491.3    0.05       0  4997.0    0.03       0  5003.0    0.05       0
Bank Sta=4997,5003
Exp/Cntr=0.3,0.1

Type RM Length L Ch R = 1,512,469,469,469
BEGIN DESCRIPTION:
WILLOW CREEK TRIB 15 1 2
END DESCRIPTION:
XS GIS Cut Line= 3
      3511419.56     10447253.46      3511588.81     10447039.95
      3511617.44     10446246.13
#Sta/Elev= 30
  4491.4  404.98  4537.1  403.04  4565.9  401.22  4601.2  399.96  4630.0  397.70
  4665.3  396.02  4679.7  394.80  4729.4  392.52  4743.8  391.30  4872.2  383.75
  4922.3  380.00  4952.3  379.61  4972.3  380.78  4982.3  380.63  4992.6  379.47
  4995.4  378.97  4998.6  379.47  5002.3  380.23  5012.3  380.49  5072.4  381.36
  5132.4  385.16  5202.5  388.78  5222.5  390.32  5262.5  391.36  5282.5  392.83
  5312.5  393.61  5412.6  398.06  5420.7  398.75  5472.6  401.29  5558.2  403.78
#Mann=4,-1,0
  4491.4    0.05       0  4992.6    0.03       0  4998.6    0.05       0
  5420.7    0.16       0
Bank Sta=4992.6,4998.6
Exp/Cntr=0.3,0.1

Type RM Length L Ch R = 1,43,0,0,0
BEGIN DESCRIPTION:
WILLOW CREEK TRIB 15 1 1.0
END DESCRIPTION:
XS GIS Cut Line= 3
      3511725.77     10447150.25      3512027.81     10447010.13
      3512017.41     10446465.79
#Sta/Elev= 30
  4530.3  396.08  4638.0  392.69  4655.4  393.15  4706.7  391.82  4724.1  391.91
  4729.6  391.27  4746.7  391.35  4898.4  382.89  4903.4  383.14  4921.8  381.88
  4951.8  381.20  4971.8  379.92  4991.8  377.69  5031.8  378.21  5051.8  379.20
  5101.8  378.43  5128.8  377.20  5131.5  376.70  5134.8  377.20  5141.8  377.60
  5181.8  377.51  5191.8  377.96  5211.8  380.24  5241.8  381.56  5261.8  383.19
  5303.9  384.14  5371.8  388.22  5381.8  390.54  5391.8  393.88  5407.7  396.05
#Mann=4,-1,0
  4530.3    0.16       0  5128.8    0.07       0  5134.8    0.16       0
  5303.9    0.08       0
Bank Sta=5128.8,5134.8
Exp/Cntr=0.3,0.1

Chan Stop Cuts=-1