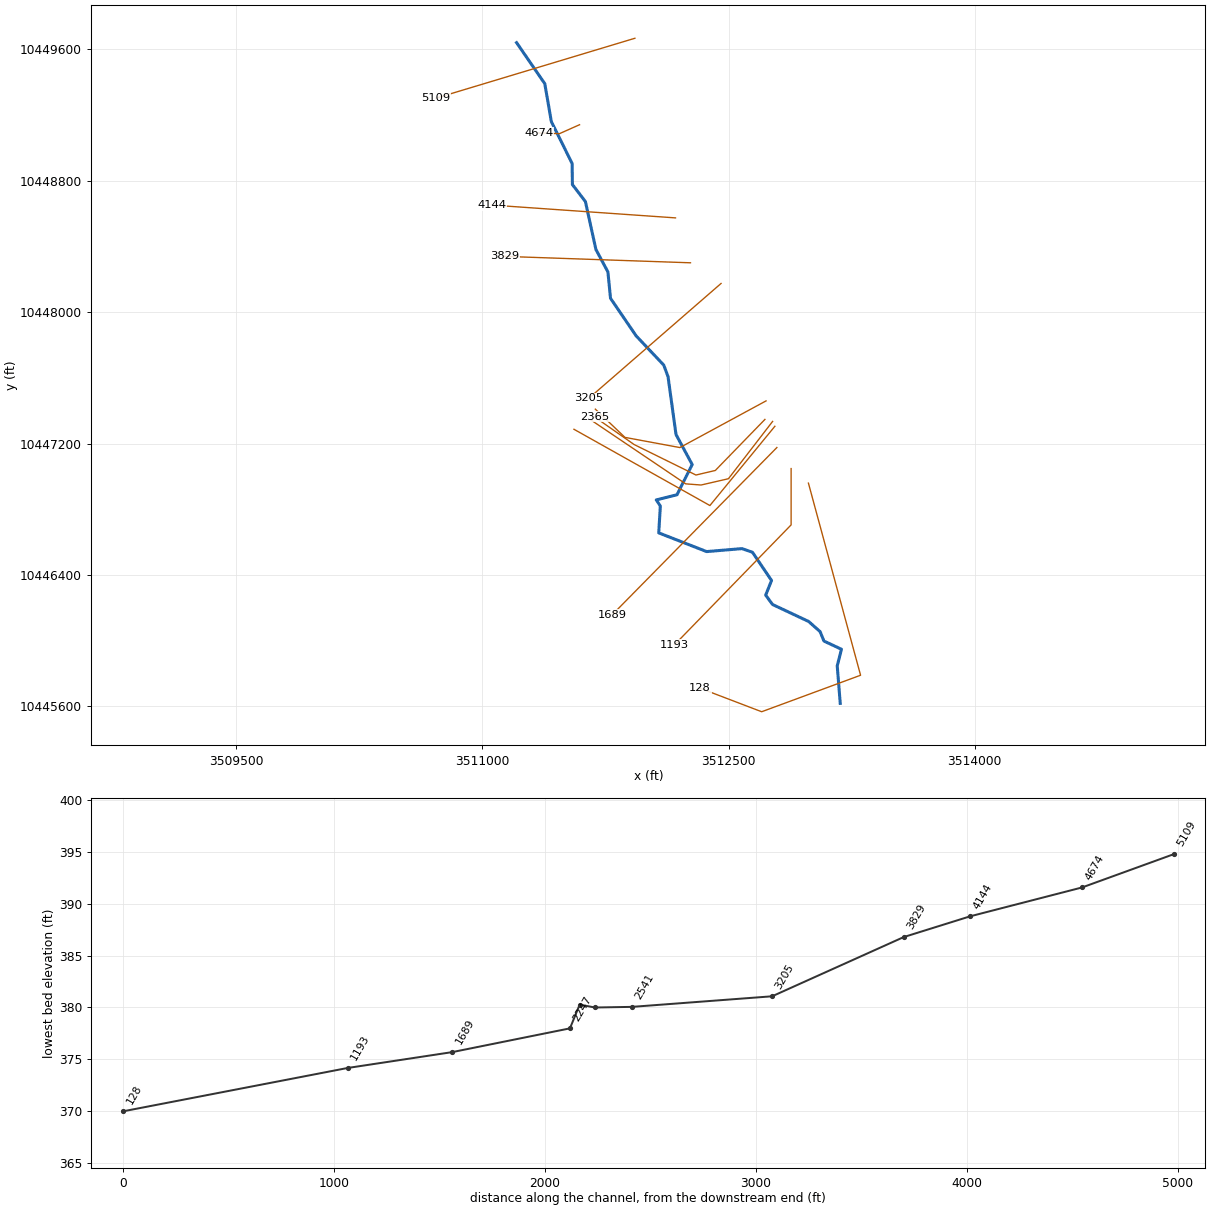
--- WILLOW CREEK TRIB 15.prj (project) ---

Proj Title=WILLOW CREEK TRIB 15 Base Level Engineering
Current Plan=p01
Default Exp/Contr=0.3,0.1
English Units
Geom File=g01
Flow File=f01
Plan File=p01
Y Axis Title=Elevation
X Axis Title(PF)=Main Channel Distance
X Axis Title(XS)=Station
BEGIN DESCRIPTION:
WILLOW CREEK TRIB 15
END DESCRIPTION:
DSS Export Rating Curves= 0
DSS Export Rating Curve Sorted= 0
DSS Export Volume Flow Curves= 0
DXF OffsetX= 0
DXF OffsetY= 0
DXF ScaleX= 1
DXF ScaleY= 10

--- WILLOW CREEK TRIB 15.p01 (plan) ---

Plan Title=Multiple Run
Short Identifier=Multiple
Geom File=g01
Flow File=f01
Subcritical Flow
K Sum by GR= 0
Std Step Tol= 0.01
Critical Tol= 0.01
Num of Std Step Trials= 20
Max Error Tol= 0.3
Flow Tol Ratio= 0.001
Split Flow NTrial= 30
Split Flow Tol= 0.02
Split Flow Ratio= 0.02
Log Output Level= 0
Friction Slope Method= 1
Unsteady Friction Slope Method= 2
Unsteady Bridges Friction Slope Method= 1
Parabolic Critical Depth
Global Vel Dist=  1 , 1 , 1
Global Log Level= 0
CheckData=True
Encroach Param= -1, 0, 0, 0
BEGIN DESCRIPTION:
Multiple Run
END DESCRIPTION:

--- WILLOW CREEK TRIB 15.f01 (steady flow) ---

Flow Title=Multiple
Program Version=4.10
Number of Profiles= 7
Profile Names=10-year,25-year,50-year,1pct_min,100-year,1pct_plu,500-year
River Rch & RM=WILLOW CREEK TRI,Reach-1         ,5109
     379     496     588     512     692     936     954
River Rch & RM=WILLOW CREEK TRI,Reach-1         ,1689
     942    1302    1601    1438    1945    2630    2861
Boundary for River Rch & Prof#=WILLOW CREEK TRI,Reach-1         , 1
Up Type= 0
Dn Type= 3
Dn Slope=0.0039
Boundary for River Rch & Prof#=WILLOW CREEK TRI,Reach-1         , 2
Up Type= 0
Dn Type= 3
Dn Slope=0.0039
Boundary for River Rch & Prof#=WILLOW CREEK TRI,Reach-1         , 3
Up Type= 0
Dn Type= 3
Dn Slope=0.0039
Boundary for River Rch & Prof#=WILLOW CREEK TRI,Reach-1         , 4
Up Type= 0
Dn Type= 3
Dn Slope=0.0039
Boundary for River Rch & Prof#=WILLOW CREEK TRI,Reach-1         , 5
Up Type= 0
Dn Type= 3
Dn Slope=0.0039
Boundary for River Rch & Prof#=WILLOW CREEK TRI,Reach-1         , 6
Up Type= 0
Dn Type= 3
Dn Slope=0.0039
Boundary for River Rch & Prof#=WILLOW CREEK TRI,Reach-1         , 7
Up Type= 0
Dn Type= 3
Dn Slope=0.0039
DSS Import GetInterval= 0
DSS Import GetPeak= 0
DSS Import FillOption= 0

--- WILLOW CREEK TRIB 15.g01 (geometry) ---

Geom Title=Existing Conditions
Program Version=4.10

River Reach=WILLOW CREEK TRI,Reach-1
Reach XY= 30
       3511208.6     10449641.48      3511380.48     10449391.48
      3511420.41     10449160.57      3511547.14     10448905.37
      3511548.66     10448777.11      3511627.87     10448674.03
      3511691.89     10448382.15      3511765.01     10448245.37
      3511780.87     10448084.84      3511937.12     10447855.89
       3512105.3     10447677.94      3512131.35     10447607.41
      3512179.83     10447255.41      3512278.44     10447072.77
      3512186.08     10446888.74      3512059.43     10446857.15
      3512084.43     10446820.34       3512074.7     10446656.45
      3512366.37     10446542.56      3512581.77     10446560.66
      3512645.55     10446538.47       3512761.8     10446366.66
       3512726.2     10446277.29      3512768.02     10446220.33
      3512988.17     10446116.88      3513057.83     10446055.05
        3513081.     10445997.78       3513187.8     10445947.92
      3513162.01     10445846.63      3513180.41     10445618.36

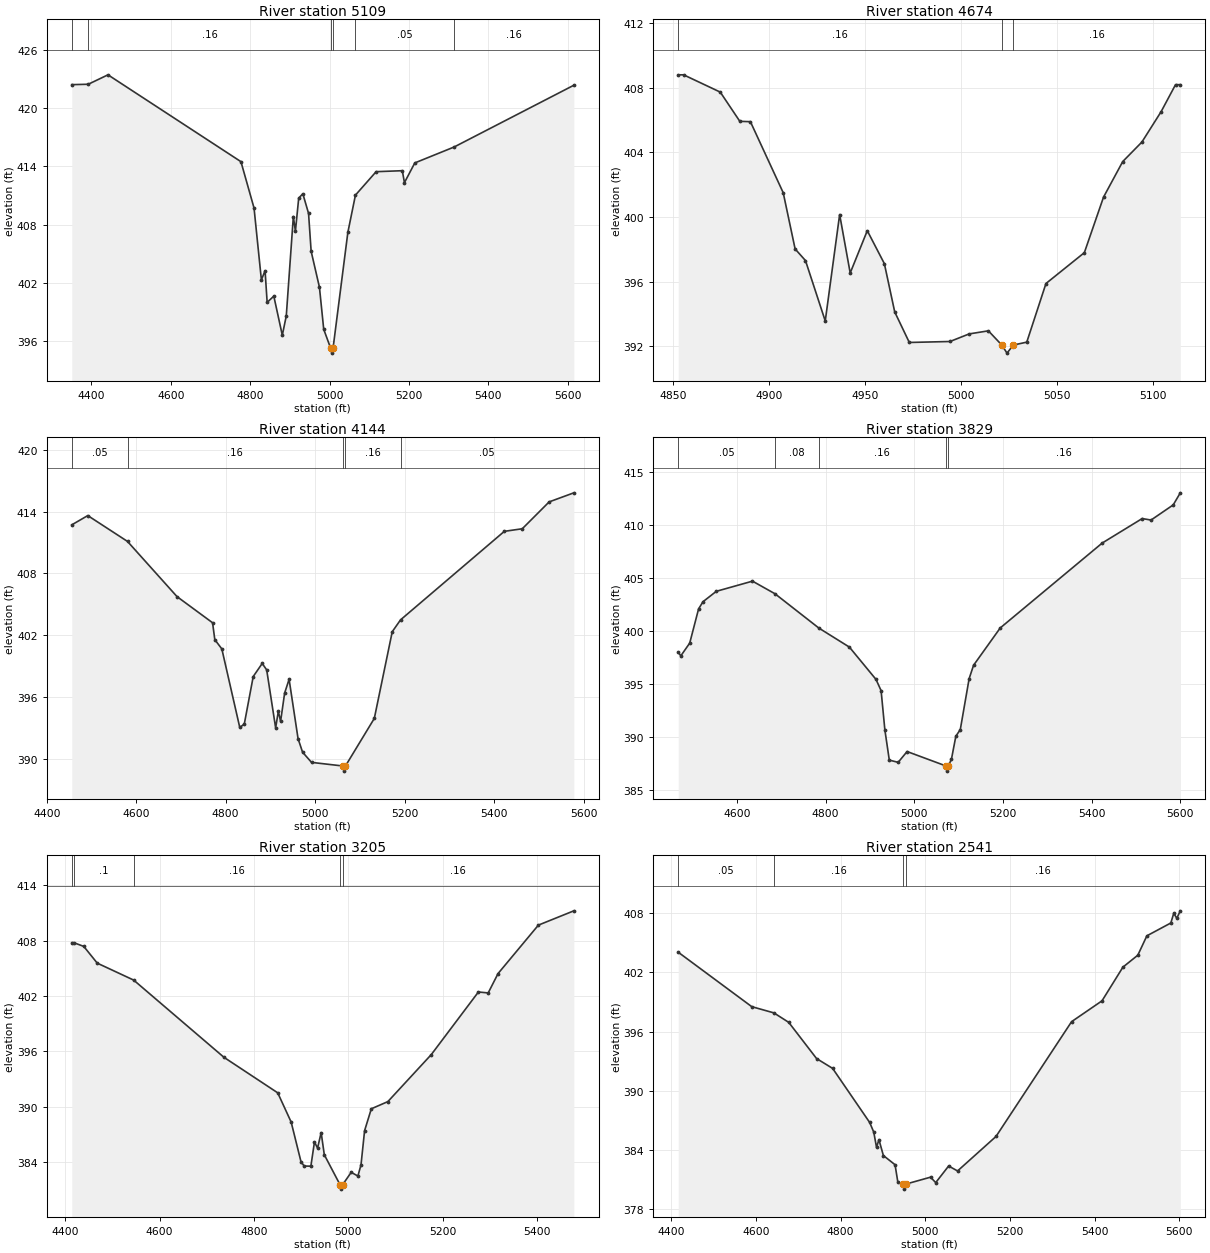
Type RM Length L Ch R = 1 ,5109    ,435,435,435
BEGIN DESCRIPTION:
WILLOW CREEK TRIB 15 11.0
END DESCRIPTION:
XS GIS Cut Line= 2
      3511929.43     10449668.18      3510718.52      10449303.6
#Sta/Elev= 30
  4350.7  422.39  4392.2  422.43  4441.9   423.4  4776.8  414.47  4809.8   409.7
  4828.3  402.31  4837.6  403.26  4842.8     400  4859.6  400.64    4881  396.62
    4891  398.61  4908.8  408.83    4914  407.32  4922.3  410.72  4932.7  411.17
  4947.1  409.15  4953.6  405.26  4974.5  401.56  4985.3  397.23  5002.8  395.28
  5005.6  394.78  5008.8  395.28  5046.1   407.2  5065.2  411.03  5117.3  413.44
  5183.3  413.54  5188.6  412.31  5214.7  414.34  5313.9  415.98  5615.3  422.33
#Mann= 6 ,-1 , 0
  4350.7     .05       0  4392.2     .16       0  5002.8     .07       0
  5008.8     .16       0  5065.2     .05       0  5313.9     .16       0
Bank Sta=5002.8,5008.8
XS Rating Curve= 0 ,0
Exp/Cntr=0.3,0.1

Type RM Length L Ch R = 1 ,4674    ,530,530,530
BEGIN DESCRIPTION:
WILLOW CREEK TRIB 15 10.0
END DESCRIPTION:
XS GIS Cut Line= 3
      3511592.12     10449141.65      3511469.89     10449087.26
      3511342.15     10449091.64
#Sta/Elev= 30
  4852.7   408.8  4855.5   408.8  4874.6  407.73  4884.8  405.92  4890.3   405.9
  4907.4   401.5  4913.6  398.02    4919   397.3  4929.3  393.56  4936.8  400.15
  4942.3  396.53  4951.2  399.15  4960.1  397.11  4965.5  394.12  4973.1  392.23
  4994.3  392.29  5004.3  392.76  5014.3  392.95  5021.3  392.07    5024  391.57
  5027.3  392.07  5034.3  392.25  5044.3  395.88  5064.3  397.79  5074.3  401.23
  5084.3  403.43  5094.3  404.64  5104.3  406.52  5111.8  408.19  5114.3  408.19
#Mann= 3 ,-1 , 0
  4852.7     .16       0  5021.3     .07       0  5027.3     .16       0
Bank Sta=5021.3,5027.3
XS Rating Curve= 0 ,0
Exp/Cntr=0.3,0.1

Type RM Length L Ch R = 1 ,4144    ,315,315,315
BEGIN DESCRIPTION:
WILLOW CREEK TRIB 15 9.0
END DESCRIPTION:
XS GIS Cut Line= 2
      3512176.82     10448574.43      3511057.05     10448652.55
#Sta/Elev= 30
  4455.9  412.71  4491.7  413.61  4580.5   411.1  4691.2  405.74  4770.7   403.2
  4775.7  401.56  4791.4  400.66  4831.5  393.03  4841.6  393.36  4861.6  397.98
  4881.7  399.25  4891.7  398.62  4911.7  392.99  4917.7   394.6  4922.8  393.63
  4931.8  396.37  4941.8  397.71  4961.8  391.95  4971.9  390.63  4991.9  389.64
  5061.8  389.29  5064.5  388.79  5067.8  389.29  5132.3  393.91  5172.4  402.33
  5190.9  403.48    5423  412.08  5463.1  412.33  5523.2  414.94  5578.4  415.82
#Mann= 5 ,-1 , 0
  4455.9     .05       0  4580.5     .16       0  5061.8     .07       0
  5067.8     .16       0  5190.9     .05       0
Bank Sta=5061.8,5067.8
XS Rating Curve= 0 ,0
Exp/Cntr=0.3,0.1

Type RM Length L Ch R = 1 ,3829    ,624,624,624
BEGIN DESCRIPTION:
WILLOW CREEK TRIB 15 8.0
END DESCRIPTION:
XS GIS Cut Line= 2
      3512267.95     10448300.99      3511136.12     10448340.02
#Sta/Elev= 30
  4467.5     398  4473.4  397.68  4493.4  398.88  4513.4  402.11  4523.4  402.79
  4553.4  403.77    4635  404.73  4685.7  403.54  4784.7   400.3  4853.6   398.5
  4913.6  395.45  4925.1  394.39  4933.6  390.68  4943.6  387.83  4963.6  387.62
  4983.7  388.64  5070.7  387.29  5073.5  386.79  5076.7  387.29  5083.7   387.9
  5093.7  390.09  5103.7  390.71  5123.7  395.53  5133.7  396.79  5193.8  400.31
  5423.9  408.33    5514  410.64    5534   410.5    5584  411.93    5600  413.07
#Mann= 5 ,-1 , 0
  4467.5     .05       0  4685.7     .08       0  4784.7     .16       0
  5070.7     .07       0  5076.7     .16       0
Bank Sta=5070.7,5076.7
XS Rating Curve= 0 ,0
Exp/Cntr=0.3,0.1

Type RM Length L Ch R = 1 ,3205    ,664,664,664
BEGIN DESCRIPTION:
WILLOW CREEK TRIB 15 7.0
END DESCRIPTION:
XS GIS Cut Line= 2
      3512454.29     10448175.21      3511650.42     10447477.25
#Sta/Elev= 30
  4413.7  407.79  4418.5  407.79  4439.2  407.39  4467.7  405.58    4545  403.74
  4736.4  395.37  4850.4  391.52  4878.9  388.35  4899.8  384.04  4906.6  383.58
  4920.7  383.57  4928.3  386.19  4934.9  385.53  4942.5  387.21  4949.2   384.8
  4982.3  381.58    4985  381.08  4988.3  381.58  5006.2   382.9  5020.4   382.5
    5027  383.71  5034.6  387.42  5048.9  389.79    5084  390.57  5176.1  395.67
  5275.9  402.45  5296.7  402.35  5317.6  404.45  5403.1   409.7  5478.3  411.25
#Mann= 5 ,-1 , 0
  4413.7     .05       0  4418.5      .1       0    4545     .16       0
  4982.3     .07       0  4988.3     .16       0
Bank Sta=4982.3,4988.3
XS Rating Curve= 0 ,0
Exp/Cntr=0.3,0.1

Type RM Length L Ch R = 1 ,2541    ,176,176,176
BEGIN DESCRIPTION:
WILLOW CREEK TRIB 15 6.0
END DESCRIPTION:
XS GIS Cut Line= 4
      3512728.35     10447460.11      3512203.47     10447175.95
      3511869.01     10447237.91      3511688.45     10447409.78
#Sta/Elev= 30
  4416.4  404.04  4590.1  398.53  4642.4   397.9  4677.5  396.94  4743.2  393.28
  4781.2  392.28  4868.7  386.81  4878.4  385.83  4884.9  384.29  4890.6  385.07
  4901.1  383.46  4928.7  382.53  4935.2  380.79  4947.5  380.56  4950.3  380.06
  4953.5  380.56  5012.5  381.27  5024.8  380.72  5055.3   382.4  5076.4   381.9
  5167.2  385.39  5345.8  397.01  5417.7  399.12  5467.1  402.53  5502.3  403.74
  5523.7   405.7  5580.3     407  5587.2  407.98  5594.4  407.48  5602.7  408.23
#Mann= 4 ,-1 , 0
  4416.4     .05       0  4642.4     .16       0  4947.5     .07       0
  4953.5     .16       0
Bank Sta=4947.5,4953.5
XS Rating Curve= 0 ,0
Exp/Cntr=0.3,0.1

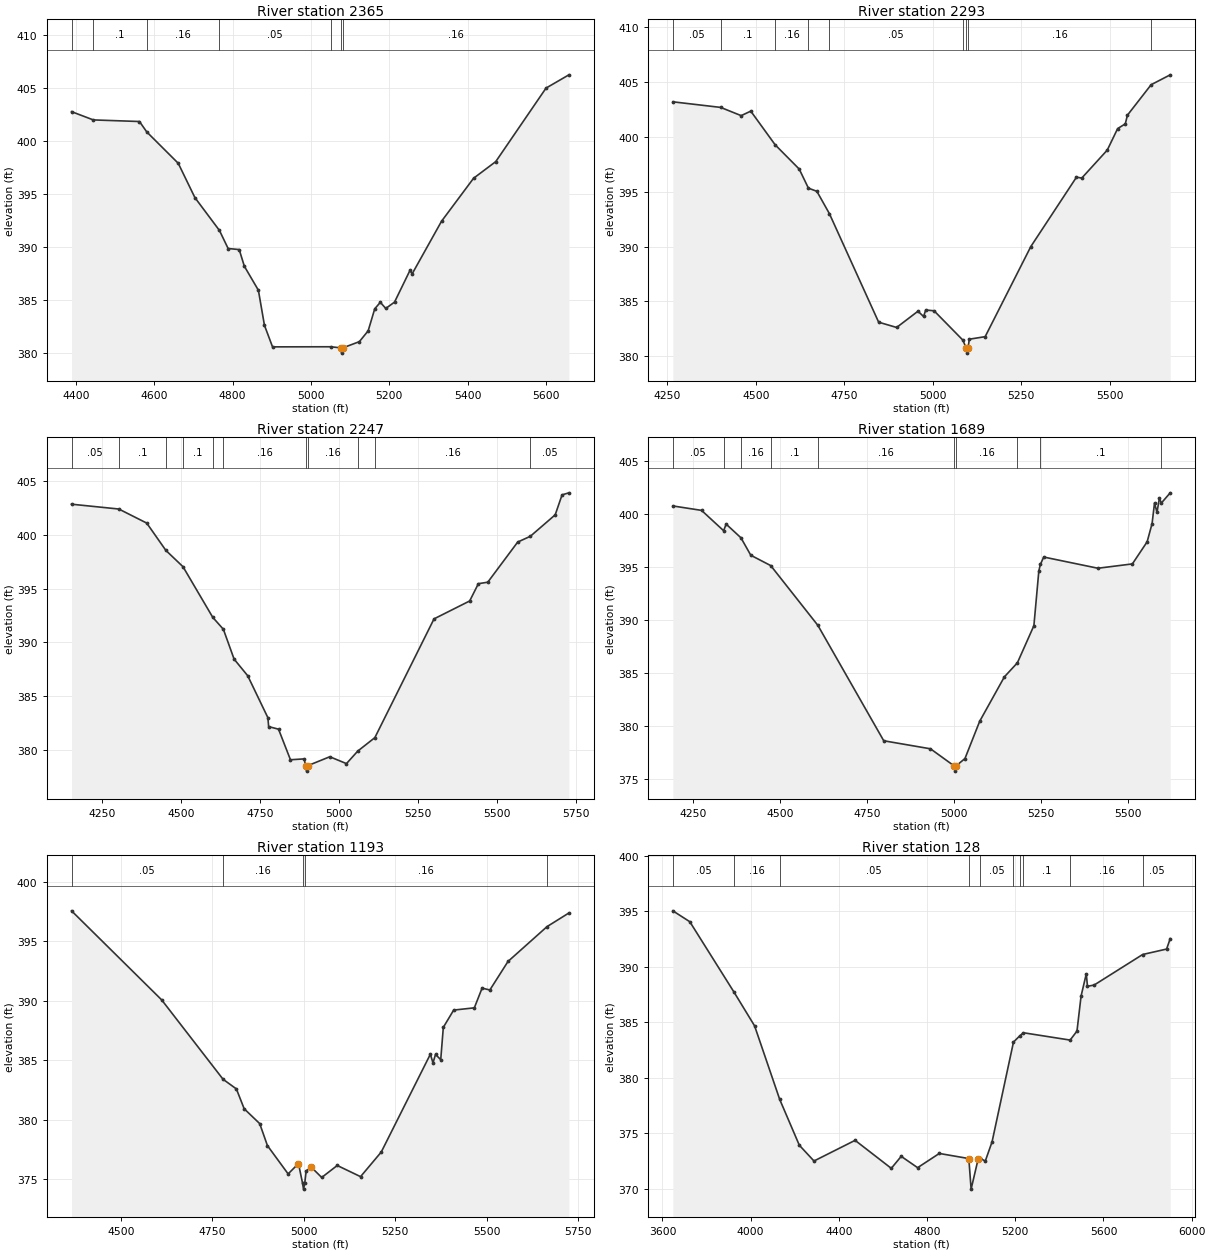
Type RM Length L Ch R = 1 ,2365    ,72,72,72
BEGIN DESCRIPTION:
Mapping XS b6dc3a9a
END DESCRIPTION:
XS GIS Cut Line= 5
      3512721.45     10447347.29      3512419.36     10447036.52
      3512301.31     10447008.74      3511924.57      10447194.5
      3511683.25     10447362.91
#Sta/Elev= 30
  4389.1  402.76  4444.7  401.98  4562.4  401.83    4581  400.85  4661.4  397.89
  4703.8  394.66  4766.5  391.56  4788.6  389.86  4816.9  389.76    4830  388.19
  4865.8  385.93  4881.3  382.62  4901.9  380.59  5050.1   380.6  5075.5   380.5
  5078.2     380  5081.5   380.5  5123.4  381.08  5145.9   382.1  5162.7  384.18
    5177  384.79  5190.8  384.21  5213.2  384.81  5252.6   387.8  5258.1  387.47
  5333.1  392.43  5414.8  396.48  5471.4  398.05  5599.7  404.98  5658.1  406.23
#Mann= 7 ,-1 , 0
  4389.1     .05       0  4444.7      .1       0    4581     .16       0
  4766.5     .05       0  5050.1     .16       0  5075.5    .035       0
  5081.5     .16       0
Bank Sta=5075.5,5081.5
XS Rating Curve= 0 ,0
Exp/Cntr=0.3,0.1

Type RM Length L Ch R = 1 ,2293    ,46,46,46
BEGIN DESCRIPTION:
Mapping XS b3caa67d
END DESCRIPTION:
XS GIS Cut Line= 5
       3512768.3      10447335.1      3512499.22     10446986.17
      3512332.56     10446947.97      3512238.81     10446954.92
      3511658.94     10447345.55
#Sta/Elev= 30
  4265.7  403.19  4400.8  402.68  4458.7  401.93  4485.8  402.34  4554.7  399.27
  4622.6  397.06  4648.6  395.32  4672.5  395.03  4707.8     393    4847   383.1
  4897.8  382.62    4958   384.1  4973.9  383.62  4979.9  384.21  5003.5  384.14
  5084.7  381.47  5093.8  380.78  5096.6  380.28  5099.8  380.78  5102.9  381.55
  5147.8  381.78  5276.7  389.99  5405.7  396.32  5420.7  396.24  5492.7  398.79
    5522  400.75  5543.6  401.18  5549.6  401.97  5616.6  404.75  5670.5  405.65
#Mann= 9 ,-1 , 0
  4265.7     .05       0  4400.8      .1       0  4554.7     .16       0
  4648.6      .1       0  4707.8     .05       0  5084.7     .16       0
  5093.8    .035       0  5099.8     .16       0  5616.6     .05       0
Bank Sta=5093.8,5099.8
XS Rating Curve= 0 ,0
Exp/Cntr=0.3,0.1

Type RM Length L Ch R = 1 ,2247    ,558,558,558
BEGIN DESCRIPTION:
Mapping XS 0ec6019c
END DESCRIPTION:
XS GIS Cut Line= 3
       3512782.2      10447305.6      3512386.37     10446822.97
      3511558.24     10447287.29
#Sta/Elev= 30
  4153.6  402.87  4303.2  402.42  4391.5  401.11  4451.9  398.57  4506.3  397.04
  4600.5  392.32    4634  391.21  4667.9  388.43    4711  386.88  4774.8  382.97
  4777.2  382.14  4808.5   381.9  4846.2  379.05  4889.6  379.13  4894.3  378.49
  4897.1  377.99  4900.3  378.49  4970.6  379.33  5023.4  378.69  5059.2  379.86
  5113.2  381.11  5300.4  392.18  5413.2  393.85  5440.7  395.46  5470.5   395.6
  5565.1  399.34  5605.2  399.88  5683.8  401.88  5705.5  403.74  5727.2  403.93
#Mann= 11 ,-1 , 0
  4153.6     .05       0  4303.2      .1       0  4451.9     .16       0
  4506.3      .1       0  4600.5     .05       0    4634     .16       0
  4894.3     .07       0  4900.3     .16       0  5059.2     .05       0
  5113.2     .16       0  5605.2     .05       0
Bank Sta=4894.3,4900.3
XS Rating Curve= 0 ,0
Exp/Cntr=0.3,0.1

Type RM Length L Ch R = 1 ,1689    ,496,496,496
BEGIN DESCRIPTION:
Mapping XS bf8278df
END DESCRIPTION:
XS GIS Cut Line= 2
      3512794.32      10447176.1       3511791.7     10446158.29
#Sta/Elev= 30
  4191.8  400.77  4274.3  400.35  4337.6  398.43    4345  399.05  4387.4  397.76
  4415.7  396.11    4473  395.13  4608.4  389.48  4797.6  378.57  4931.9  377.81
  4999.6   376.2  5002.4   375.7  5005.6   376.2  5030.9  376.89  5073.3  380.42
  5144.1  384.61  5181.5  385.94  5228.9  389.45  5243.1  394.63  5247.5  395.24
  5257.2  395.94  5412.8  394.88  5511.8  395.29  5554.2  397.38  5568.4  399.11
  5575.4  401.05  5582.5  400.17  5589.5  401.52  5594.9  401.04  5620.5  402.01
#Mann= 10 ,-1 , 0
  4191.8     .05       0  4337.6      .1       0  4387.4     .16       0
    4473      .1       0  4608.4     .16       0  4999.6     .07       0
  5005.6     .16       0  5181.5     .08       0  5247.5      .1       0
  5594.9     .16       0
Bank Sta=4999.6,5005.6
XS Rating Curve= 0 ,0
Exp/Cntr=0.3,0.1

Type RM Length L Ch R = 1 ,1193    ,1065,1065,1065
BEGIN DESCRIPTION:
WILLOW CREEK TRIB 15 4.0
END DESCRIPTION:
XS GIS Cut Line= 3
       3512881.1     10447048.03       3512881.1     10446705.16
      3512171.78     10445976.31
#Sta/Elev= 30
  4364.7  397.58  4611.1  390.09    4779  383.41  4815.4   382.6  4836.7  380.93
  4879.2  379.68  4900.3  377.83  4956.9  375.45  4985.2  376.32  4996.3  374.67
    4999  374.17  5002.3  374.67  5006.3  375.71  5020.4  376.01  5048.7  375.15
  5091.2  376.16  5154.9  375.22  5211.5  377.29  5345.8  385.52  5352.9  384.79
  5359.9   385.5  5374.1  385.06  5381.2  387.78  5409.5  389.23    5466  389.42
  5487.2  391.08  5508.4  390.92    5558  393.32  5664.7  396.25  5724.6   397.4
#Mann= 5 ,-1 , 0
  4364.7     .05       0    4779     .16       0  4996.3     .07       0
  5002.3     .16       0  5664.7     .05       0
Bank Sta=4985.2,5020.4
XS Rating Curve= 0 ,0
Exp/Cntr=0.3,0.1

Type RM Length L Ch R = 1 ,128     ,0,0,0
BEGIN DESCRIPTION:
WILLOW CREEK TRIB 15 1.0
END DESCRIPTION:
XS GIS Cut Line= 4
      3512986.53     10446959.38      3513304.24     10445789.65
      3512701.81     10445567.43      3512326.71     10445710.53
#Sta/Elev= 30
  3647.1  395.03    3724  394.05  3925.3  387.69  4017.8  384.68  4131.8  378.06
  4220.7  373.94  4287.2  372.52  4473.7  374.38  4637.8  371.86  4682.8  372.94
  4757.2  371.92  4855.6   373.2  4989.4  372.74  4999.8  369.99    5032  372.72
  5039.3  372.79    5064  372.51  5094.9  374.25  5191.9  383.22  5219.8  383.77
  5237.1  384.06  5448.9   383.4  5479.9  384.21  5498.5  387.36  5522.1  389.36
  5527.5  388.24  5557.6  388.35  5777.7   391.1  5886.3  391.59  5902.8  392.53
#Mann= 10 ,-1 , 0
  3647.1     .05       0  3925.3     .16       0  4131.8     .05       0
  4989.4     .03       0  5039.3     .05       0  5191.9     .16       0
  5219.8     .12       0  5237.1      .1       0  5448.9     .16       0
  5777.7     .05       0
Bank Sta=4989.4,5032
XS Rating Curve= 0 ,0
Exp/Cntr=0.3,0.1

Chan Stop Cuts=-1
Use User Specified Reach Order=0
Composite Channel Slope=5