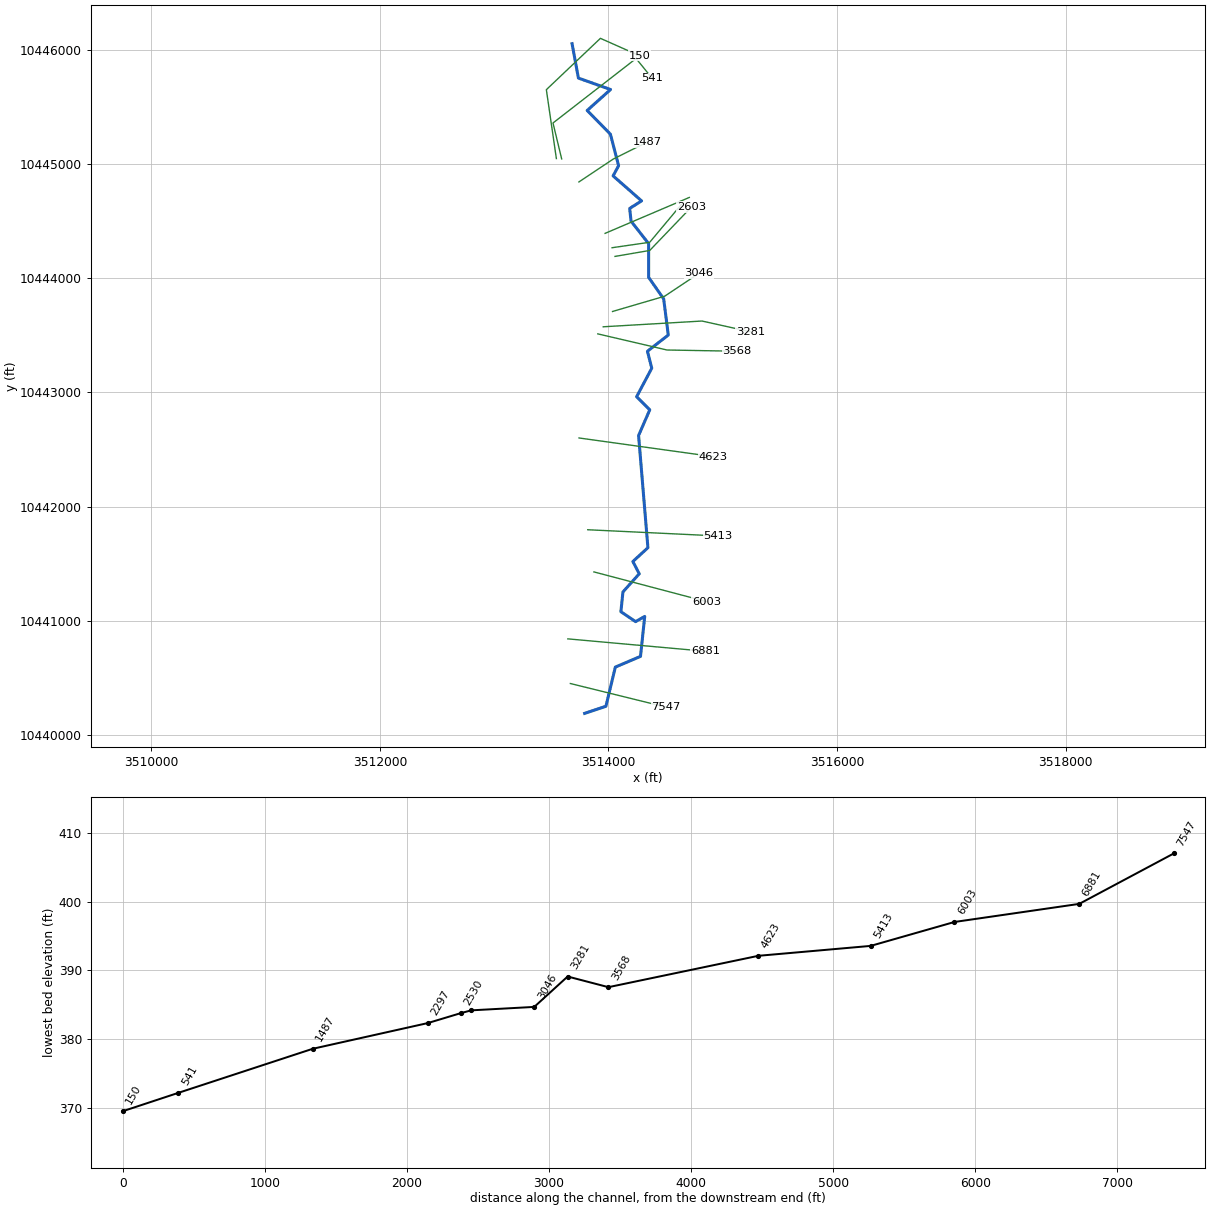
--- WILLOW CREEK TRIB 16.prj (project) ---

Proj Title=WILLOW CREEK TRIB 16 Base Level Engineering
Current Plan=p01
Default Exp/Contr=0.3,0.1
English Units
Geom File=g01
Flow File=f01
Plan File=p01
BEGIN DESCRIPTION:
WILLOW CREEK TRIB 16
END DESCRIPTION:

--- WILLOW CREEK TRIB 16.p01 (plan) ---

Plan Title=Multiple Run
Short Identifier=Multiple
Geom File=g01
Flow File=f01
Subcritical Flow
K Sum by GR= 0
Std Step Tol= 0.01
Critical Tol= 0.01
Num of Std Step Trials= 20
Max Error Tol= 0.3
Flow Tol Ratio= 0.001
Split Flow NTrial= 30
Split Flow Tol= 0.02
Split Flow Ratio= 0.02
Log Output Level= 0
Friction Slope Method= 1
Unsteady Friction Slope Method= 2
Unsteady Bridges Friction Slope Method= 1
Parabolic Critical Depth
Global Vel Dist=  1 , 1 , 1
Global Log Level= 0
CheckData=True
Encroach Param= -1, 0, 0, 0
BEGIN DESCRIPTION:
Multiple Run
END DESCRIPTION:

--- WILLOW CREEK TRIB 16.f01 (steady flow) ---

Flow Title=Multiple
Number of Profiles=7
Profile Names=10-year,25-year,50-year,1pct_min,100-year,1pct_plu,500-year
River Rch & RM= WILLOW CREEK TRI,Reach-1,7547
     648     870    1048     923    1248    1687    1763
Boundary for River Rch & Prof#=WILLOW CREEK TRI,Reach-1,1
Up Type=0
Dn Type=3
Dn Slope=0.005
Boundary for River Rch & Prof#=WILLOW CREEK TRI,Reach-1,2
Up Type=0
Dn Type=3
Dn Slope=0.005
Boundary for River Rch & Prof#=WILLOW CREEK TRI,Reach-1,3
Up Type=0
Dn Type=3
Dn Slope=0.005
Boundary for River Rch & Prof#=WILLOW CREEK TRI,Reach-1,4
Up Type=0
Dn Type=3
Dn Slope=0.005
Boundary for River Rch & Prof#=WILLOW CREEK TRI,Reach-1,5
Up Type=0
Dn Type=3
Dn Slope=0.005
Boundary for River Rch & Prof#=WILLOW CREEK TRI,Reach-1,6
Up Type=0
Dn Type=3
Dn Slope=0.005
Boundary for River Rch & Prof#=WILLOW CREEK TRI,Reach-1,7
Up Type=0
Dn Type=3
Dn Slope=0.005

--- WILLOW CREEK TRIB 16.g01 (geometry) ---

Geom Title=Existing Conditions

River Reach=WILLOW CREEK TRI,Reach-1
Reach XY= 30
      3513792.51     10440191.64      3513978.44     10440253.77
      3514060.74     10440596.53      3514281.08     10440690.33
      3514318.02     10441040.18      3514238.34     10440994.39
      3514109.43     10441081.07      3514127.37     10441254.23
      3514270.11     10441413.12      3514214.17     10441520.26
      3514345.80     10441641.34      3514264.26     10442622.92
      3514361.90     10442847.35      3514246.89     10442962.11
      3514379.49     10443211.65      3514341.73     10443360.09
      3514524.03     10443502.02      3514483.66     10443818.42
      3514352.19     10444006.61      3514352.06     10444301.86
      3514198.54     10444498.09      3514186.23     10444609.69
      3514290.51     10444675.84      3514041.14     10444894.71
      3514089.48     10444983.54      3514017.60     10445259.57
      3513814.50     10445467.05      3514018.87     10445650.28
      3513737.74     10445750.27      3513682.11     10446051.64

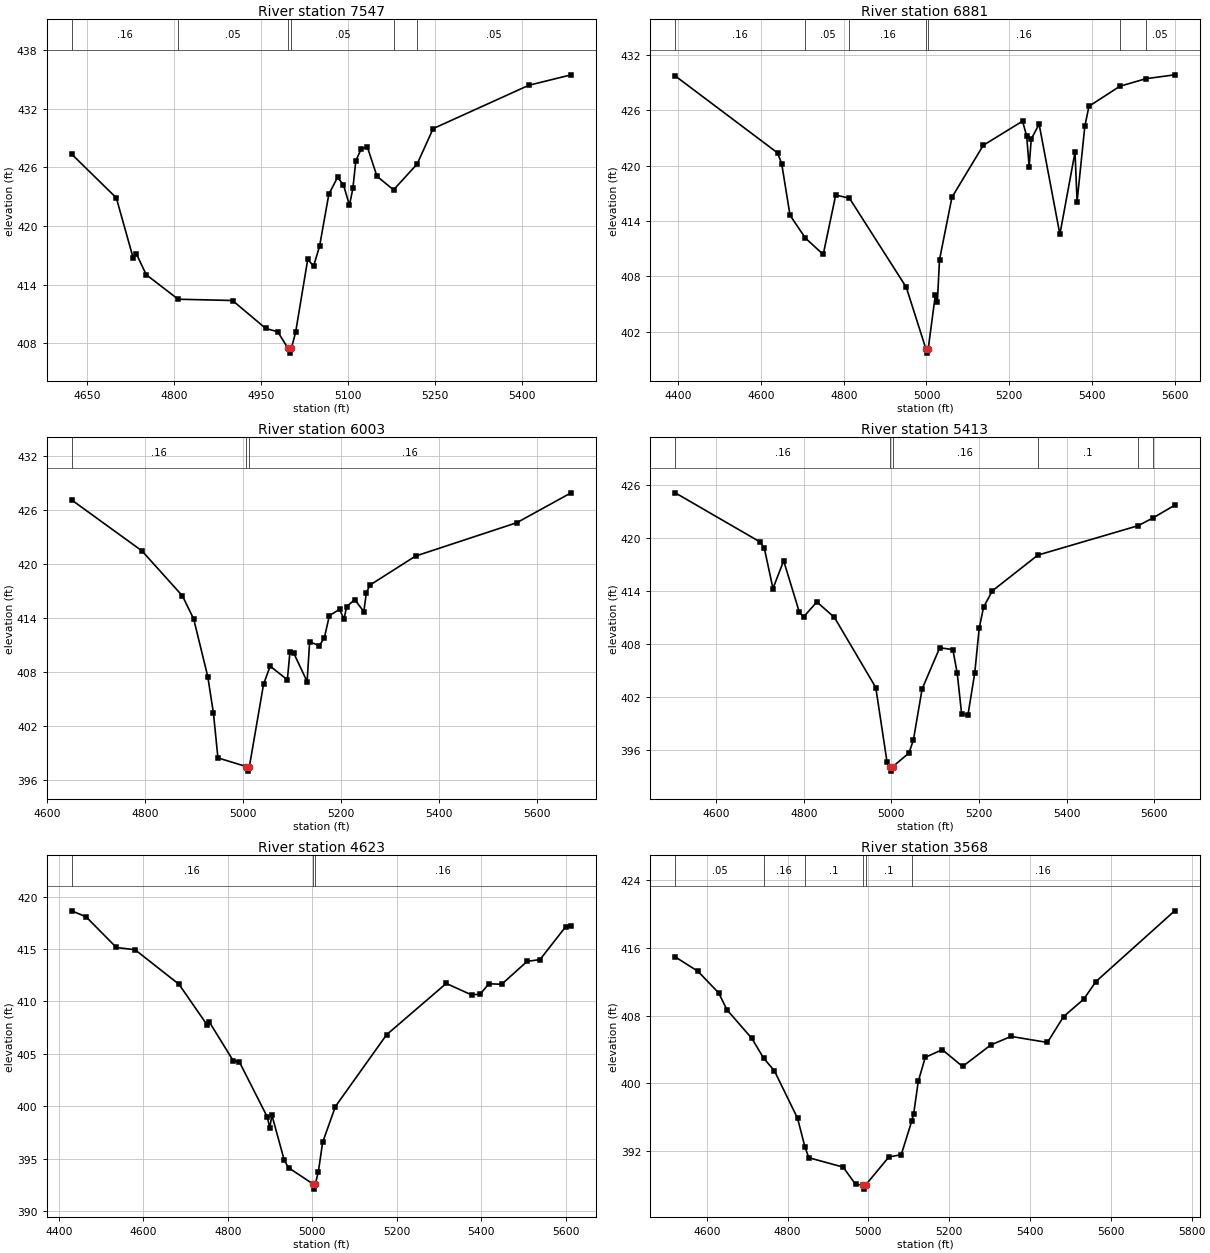
Type RM Length L Ch R = 1,7547,666,666,666
BEGIN DESCRIPTION:
WILLOW CREEK TRIB 16 15.0
END DESCRIPTION:
XS GIS Cut Line= 2
      3513667.30     10440452.90      3514502.84     10440246.73
#Sta/Elev= 30
  4623.9  427.36  4700.9  422.88  4730.1  416.70  4735.2  417.19  4752.4  415.03
  4807.4  412.52  4901.1  412.39  4958.4  409.53  4978.9  409.20  4996.6  407.51
  4999.4  407.01  5002.6  407.51  5009.9  409.16  5030.7  416.59  5040.8  415.91
  5051.1  417.94  5067.0  423.23  5082.0  424.98  5092.3  424.21  5102.6  422.13
  5108.5  423.85  5113.6  426.69  5123.2  427.92  5133.5  428.07  5150.0  425.09
  5178.6  423.70  5219.2  426.34  5246.8  429.96  5411.6  434.39  5484.5  435.46
#Mann=6,-1,0
  4623.9    0.16       0  4807.4    0.05       0  4996.6    0.03       0
  5002.6    0.05       0  5178.6    0.16       0  5219.2    0.05       0
Bank Sta=4996.6,5002.6
Exp/Cntr=0.3,0.1

Type RM Length L Ch R = 1,6881,878,878,878
BEGIN DESCRIPTION:
WILLOW CREEK TRIB 16 14.0
END DESCRIPTION:
XS GIS Cut Line= 2
      3513645.62     10440843.52      3514848.55     10440735.15
#Sta/Elev= 30
  4392.5  429.71  4640.0  421.37  4650.0  420.19  4670.1  414.61  4707.4  412.13
  4750.4  410.36  4780.6  416.80  4813.8  416.46  4951.2  406.81  4998.4  400.17
  5001.2  399.67  5004.4  400.17  5021.5  405.96  5026.5  405.25  5031.6  409.79
  5061.7  416.56  5137.4  422.19  5232.4  424.81  5242.4  423.19  5248.4  419.86
  5253.4  422.87  5272.5  424.48  5322.7  412.54  5359.3  421.45  5364.3  416.10
  5383.0  424.25  5393.0  426.42  5467.6  428.59  5530.8  429.41  5600.3  429.83
#Mann=7,-1,0
  4392.5    0.16       0  4707.4    0.05       0  4813.8    0.16       0
  4998.4    0.07       0  5004.4    0.16       0  5467.6     0.1       0
  5530.8    0.05       0
Bank Sta=4998.4,5004.4
Exp/Cntr=0.3,0.1

Type RM Length L Ch R = 1,6003,590,590,590
BEGIN DESCRIPTION:
WILLOW CREEK TRIB 16 12.0
END DESCRIPTION:
XS GIS Cut Line= 2
      3513873.48     10441429.45      3514858.99     10441169.54
#Sta/Elev= 30
  4650.7  427.14  4794.1  421.49  4876.8  416.49  4899.8  413.92  4928.5  407.53
  4940.1  403.46  4949.2  398.51  5007.4  397.54  5010.1  397.04  5013.4  397.54
  5042.3  406.68  5055.8  408.69  5090.9  407.18  5096.1  410.21  5104.3  410.10
  5131.2  406.98  5136.4  411.40  5156.0  410.96  5166.3  411.82  5176.7  414.31
  5197.4  414.99  5206.6  413.91  5211.8  415.30  5228.4  416.08  5246.9  414.74
  5252.1  416.84  5259.4  417.69  5352.5  420.91  5558.9  424.61  5669.9  427.93
#Mann=3,-1,0
  4650.7    0.16       0  5007.4    0.07       0  5013.4    0.16       0
Bank Sta=5007.4,5013.4
Exp/Cntr=0.3,0.1

Type RM Length L Ch R = 1,5413,790,790,790
BEGIN DESCRIPTION:
WILLOW CREEK TRIB 16 11.0
END DESCRIPTION:
XS GIS Cut Line= 2
      3513819.23     10441798.38      3514957.84     10441744.17
#Sta/Elev= 30
  4506.8  425.15  4699.9  419.59  4709.9  418.92  4729.9  414.29  4754.3  417.44
  4790.0  411.61  4800.0  411.07  4830.0  412.77  4870.1  411.01  4964.5  403.05
  4990.2  394.61  4997.2  394.06  5000.0  393.56  5003.2  394.06  5040.3  395.62
  5050.3  397.08  5070.3  402.89  5110.4  407.56  5140.4  407.36  5150.4  404.67
  5160.4  400.09  5174.8  399.91  5190.4  404.70  5200.5  409.76  5210.5  412.17
  5230.5  414.02  5334.4  418.08  5563.3  421.42  5597.2  422.30  5646.7  423.74
#Mann=6,-1,0
  4506.8    0.16       0  4997.2    0.07       0  5003.2    0.16       0
  5334.4     0.1       0  5563.3    0.16       0  5597.2     0.1       0
Bank Sta=4997.2,5003.2
Exp/Cntr=0.3,0.1

Type RM Length L Ch R = 1,4623,1055,1055,1055
BEGIN DESCRIPTION:
WILLOW CREEK TRIB 16 9.0
END DESCRIPTION:
XS GIS Cut Line= 2
      3513743.22     10442601.34      3514915.08     10442438.58
#Sta/Elev= 30
  4430.1  418.64  4464.3  418.07  4536.0  415.15  4580.4  414.93  4684.4  411.64
  4751.0  407.77  4756.1  408.06  4812.6  404.37  4827.7  404.22  4893.4  399.01
  4899.4  397.96  4904.5  399.17  4933.8  394.86  4943.9  394.16  5001.4  392.62
  5004.2  392.12  5007.4  392.62  5014.5  393.76  5024.6  396.57  5054.9  399.99
  5176.1  406.83  5317.4  411.72  5378.0  410.62  5398.2  410.72  5418.4  411.69
  5448.7  411.64  5509.2  413.83  5539.5  413.99  5600.1  417.11  5613.2  417.18
#Mann=3,-1,0
  4430.1    0.16       0  5001.4    0.07       0  5007.4    0.16       0
Bank Sta=5001.4,5007.4
Exp/Cntr=0.3,0.1

Type RM Length L Ch R = 1,3568,287,287,287
BEGIN DESCRIPTION:
WILLOW CREEK TRIB 16 7.0
END DESCRIPTION:
XS GIS Cut Line= 3
      3513907.38     10443512.15      3514512.83     10443371.09
      3515126.97     10443360.24
#Sta/Elev= 30
  4522.1  414.90  4578.3  413.21  4629.5  410.67  4650.2  408.67  4711.8  405.30
  4740.6  403.00  4767.5  401.49  4824.7  395.92  4843.0  392.54  4852.6  391.26
  4937.7  390.15  4968.5  388.11  4987.6  388.06  4990.4  387.56  4993.6  388.06
  5050.6  391.34  5081.4  391.62  5107.3  395.56  5112.2  396.46  5123.5  400.24
  5140.8  403.08  5183.0  403.98  5233.1  402.00  5303.1  404.54  5353.1  405.54
  5443.1  404.83  5483.1  407.88  5533.1  409.93  5563.1  412.00  5758.0  420.33
#Mann=6,-1,0
  4522.1    0.05       0  4740.6    0.16       0  4843.0     0.1       0
  4987.6    0.07       0  4993.6     0.1       0  5107.3    0.16       0
Bank Sta=4987.6,4993.6
Exp/Cntr=0.3,0.1

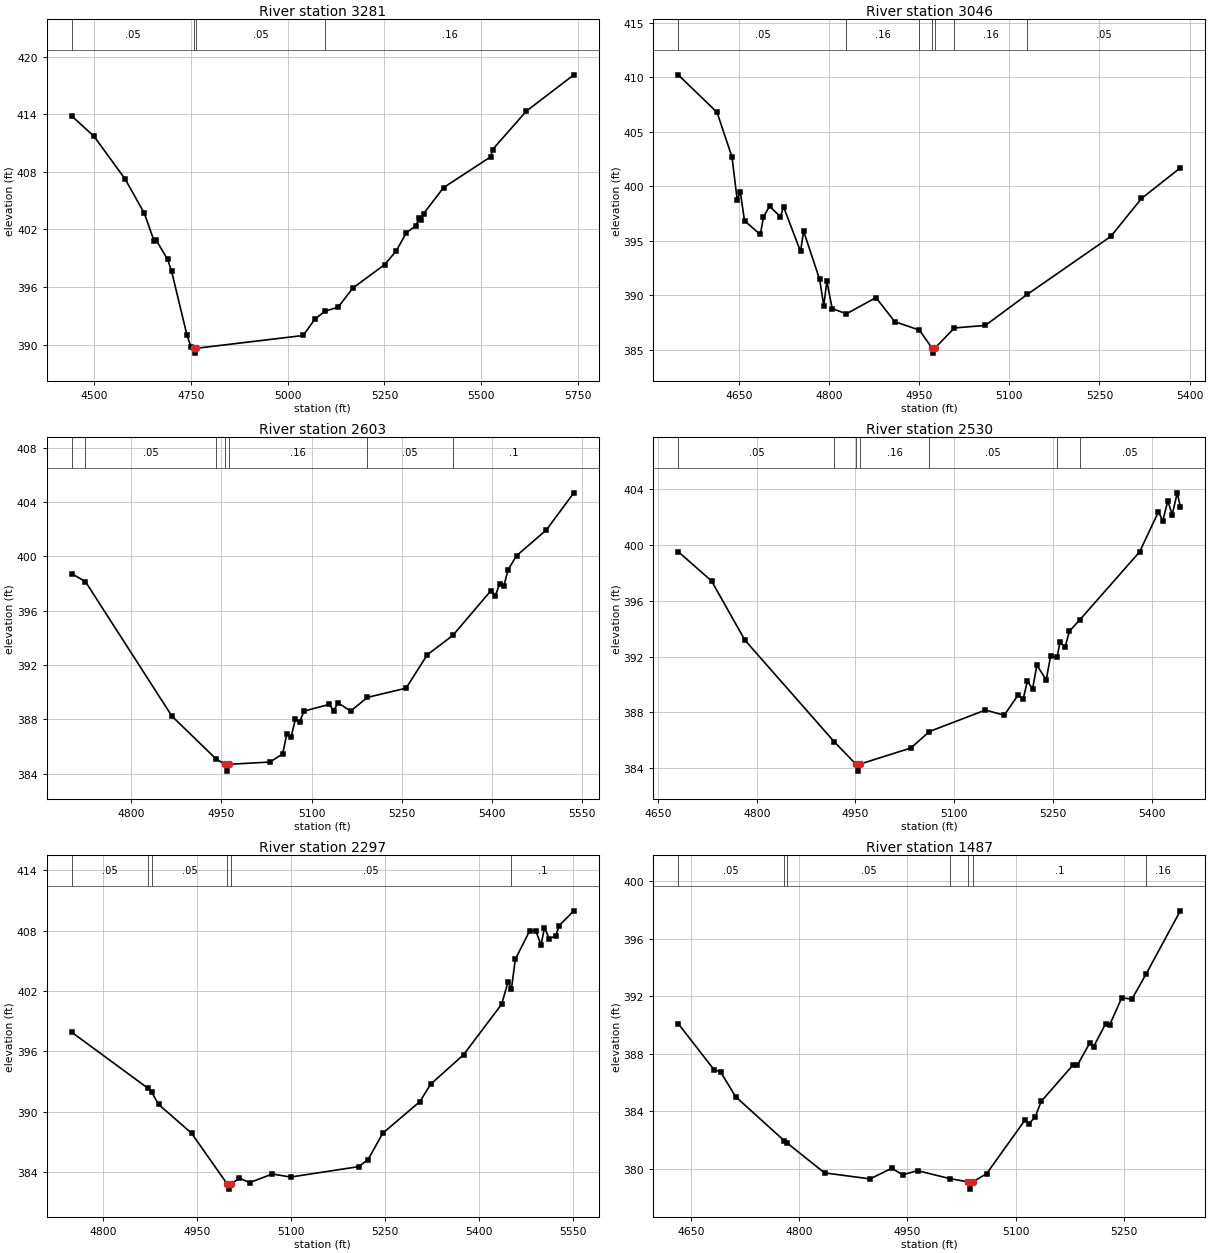
Type RM Length L Ch R = 1,3281,235,235,235
BEGIN DESCRIPTION:
WILLOW CREEK TRIB 16 6.1
END DESCRIPTION:
XS GIS Cut Line= 3
      3513954.67     10443574.22      3514819.26     10443624.56
      3515241.11     10443530.82
#Sta/Elev= 30
  4441.7  413.82  4499.2  411.71  4579.4  407.27  4629.5  403.67  4655.0  400.75
  4660.0  400.88  4689.6  398.87  4699.6  397.68  4739.6  390.98  4749.7  389.78
  4756.7  389.61  4759.4  389.11  4762.7  389.61  5040.2  390.95  5070.2  392.65
  5096.6  393.49  5130.3  393.89  5168.4  395.89  5250.5  398.33  5280.6  399.76
  5306.7  401.65  5331.2  402.38  5340.3  403.24  5345.4  402.95  5351.6  403.66
  5402.9  406.36  5524.7  409.57  5529.8  410.33  5616.9  414.33  5739.9  418.12
#Mann=4,-1,0
  4441.7    0.05       0  4756.7    0.03       0  4762.7    0.05       0
  5096.6    0.16       0
Bank Sta=4756.7,4762.7
Exp/Cntr=0.3,0.1

Type RM Length L Ch R = 1,3046,443,443,443
BEGIN DESCRIPTION:
WILLOW CREEK TRIB 16 6.0
END DESCRIPTION:
XS GIS Cut Line= 3
      3514036.25     10443708.12      3514492.11     10443841.64
      3514792.14     10444041.67
#Sta/Elev= 30
  4549.0  410.21  4613.6  406.77  4638.5  402.66  4647.1  398.74  4652.3  399.48
  4659.3  396.82  4685.7  395.57  4690.9  397.19  4701.0  398.16  4719.1  397.20
  4724.3  398.10  4752.5  394.02  4757.7  395.87  4784.3  391.45  4791.2  389.05
  4796.4  391.27  4805.2  388.77  4829.0  388.30  4878.1  389.78  4909.4  387.57
  4950.2  386.81  4970.9  385.19  4973.6  384.69  4976.9  385.19  5008.7  387.00
  5060.1  387.23  5129.8  390.07  5268.9  395.39  5320.0  398.87  5384.6  401.68
#Mann=7,-1,0
  4549.0    0.05       0  4829.0    0.16       0  4950.2    0.05       0
  4970.9    0.03       0  4976.9    0.05       0  5008.7    0.16       0
  5129.8    0.05       0
Bank Sta=4970.9,4976.9
Exp/Cntr=0.3,0.1

Type RM Length L Ch R = 1,2603,73,73,73
BEGIN DESCRIPTION:
Mapping XS 49c290c5
END DESCRIPTION:
XS GIS Cut Line= 3
      3514057.98     10444190.03      3514361.82     10444242.12
      3514726.39     10444621.88
#Sta/Elev= 30
  4701.2  398.73  4723.9  398.15  4867.7  388.24  4941.0  385.09  4956.0  384.69
  4958.8  384.19  4962.0  384.69  5030.6  384.86  5051.7  385.45  5058.9  386.96
  5065.8  386.70  5073.0  388.02  5080.0  387.79  5087.2  388.61  5129.6  389.11
  5136.6  388.63  5143.8  389.22  5164.9  388.61  5192.5  389.62  5257.0  390.30
  5292.2  392.76  5334.8  394.19  5398.2  397.49  5405.4  397.12  5412.4  397.96
  5419.6  397.84  5426.5  399.02  5440.7  400.06  5490.3  401.96  5535.9  404.69
#Mann=7,-1,0
  4701.2     0.1       0  4723.9    0.05       0  4941.0    0.16       0
  4956.0    0.07       0  4962.0    0.16       0  5192.5    0.05       0
  5334.8     0.1       0
Bank Sta=4956,4962
Exp/Cntr=0.3,0.1

Type RM Length L Ch R = 1,2530,233,233,233
BEGIN DESCRIPTION:
Mapping XS 04e4af75
END DESCRIPTION:
XS GIS Cut Line= 3
      3514031.99     10444266.00      3514361.82     10444313.74
      3514637.29     10444643.44
#Sta/Elev= 30
  4680.7  399.53  4731.3  397.43  4781.9  393.19  4918.0  385.88  4950.6  384.29
  4953.4  383.79  4956.6  384.29  5034.3  385.45  5062.3  386.63  5147.5  388.17
  5176.1  387.80  5197.0  389.24  5204.8  388.96  5211.3  390.24  5219.1  389.68
  5225.6  391.39  5239.9  390.33  5246.4  392.03  5256.3  391.94  5260.7  393.02
  5268.5  392.68  5275.1  393.83  5290.5  394.62  5381.8  399.52  5410.4  402.39
  5416.9  401.74  5424.7  403.18  5431.2  402.17  5439.0  403.75  5443.6  402.75
#Mann=7,-1,0
  4680.7    0.05       0  4918.0    0.16       0  4950.6    0.07       0
  4956.6    0.16       0  5062.3    0.05       0  5256.3     0.1       0
  5290.5    0.05       0
Bank Sta=4950.6,4956.6
Exp/Cntr=0.3,0.1

Type RM Length L Ch R = 1,2297,810,810,810
BEGIN DESCRIPTION:
WILLOW CREEK TRIB 16 4.0
END DESCRIPTION:
XS GIS Cut Line= 2
      3513971.14     10444391.72      3514708.03     10444705.98
#Sta/Elev= 30
  4750.1  397.91  4871.2  392.37  4877.4  391.99  4888.6  390.75  4941.2  387.89
  4998.2  382.84  5000.9  382.34  5004.2  382.84  5017.5  383.43  5033.8  382.99
  5070.2  383.84  5099.3  383.54  5207.7  384.57  5222.8  385.27  5246.4  387.89
  5305.6  391.03  5322.7  392.75  5375.4  395.69  5436.0  400.69  5446.2  402.90
  5451.6  402.21  5457.8  405.15  5480.7  407.97  5490.4  407.99  5498.9  406.57
  5504.3  408.28  5512.1  407.18  5522.5  407.50  5527.9  408.50  5551.2  409.96
#Mann=6,-1,0
  4750.1    0.05       0  4871.2     0.1       0  4877.4    0.05       0
  4998.2    0.03       0  5004.2    0.05       0  5451.6     0.1       0
Bank Sta=4998.2,5004.2
Exp/Cntr=0.3,0.1

Type RM Length L Ch R = 1,1487,946,946,946
BEGIN DESCRIPTION:
WILLOW CREEK TRIB 16 3.0
END DESCRIPTION:
XS GIS Cut Line= 3
      3513742.11     10444841.64      3514042.11     10445041.64
      3514342.14     10445191.66
#Sta/Elev= 30
  4632.4  390.10  4682.0  386.90  4691.0  386.75  4712.0  385.02  4779.2  381.97
  4783.7  381.79  4835.2  379.73  4898.3  379.31  4928.4  380.05  4943.4  379.60
  4964.4  379.88  5009.8  379.32  5034.7  379.10  5037.4  378.60  5040.7  379.10
  5060.0  379.68  5113.1  383.40  5118.7  383.16  5127.1  383.60  5135.5  384.69
  5180.2  387.26  5185.8  387.22  5202.6  388.73  5208.2  388.50  5224.9  390.10
  5230.5  390.02  5247.3  391.90  5261.3  391.80  5281.1  393.56  5328.4  397.94
#Mann=7,-1,0
  4632.4    0.05       0  4779.2     0.1       0  4783.7    0.05       0
  5009.8     0.1       0  5034.7    0.03       0  5040.7     0.1       0
  5281.1    0.16       0
Bank Sta=5034.7,5040.7
Exp/Cntr=0.3,0.1

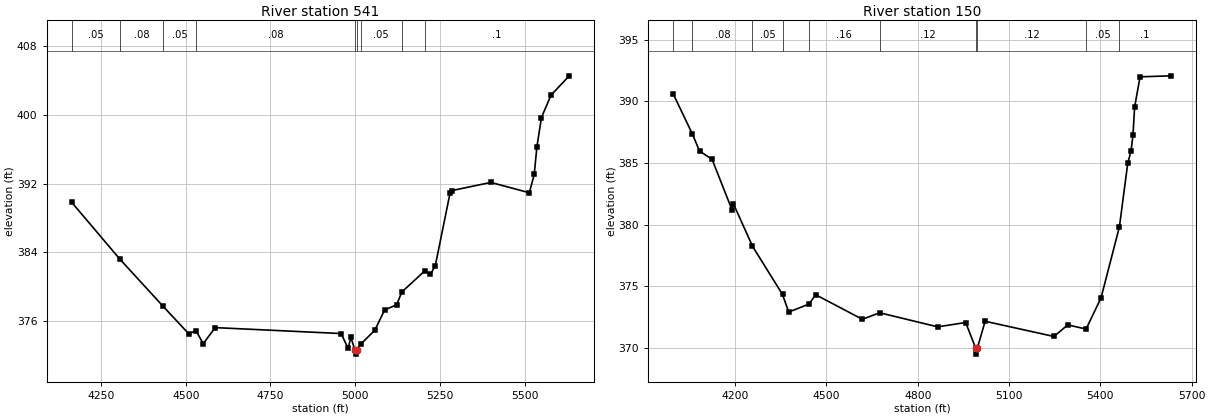
Type RM Length L Ch R = 1,541,391,391,391
BEGIN DESCRIPTION:
WILLOW CREEK TRIB 16 1.1
END DESCRIPTION:
XS GIS Cut Line= 4
      3513591.32     10445042.79      3513515.38     10445357.41
      3514242.38     10445921.65      3514383.42     10445748.05
#Sta/Elev= 30
  4163.4  389.84  4306.5  383.19  4432.8  377.77  4508.3  374.58  4530.5  374.89
  4551.8  373.41  4587.1  375.27  4958.2  374.58  4979.0  372.86  4987.2  374.15
  4998.7  372.69  5001.4  372.19  5004.7  372.69  5016.0  373.34  5057.8  374.97
  5086.7  377.33  5122.0  377.91  5137.4  379.41  5204.6  381.84  5221.6  381.44
  5236.1  382.47  5279.5  390.88  5285.9  391.19  5399.9  392.13  5513.4  390.93
  5527.8  393.07  5535.7  396.26  5549.1  399.67  5577.3  402.26  5631.0  404.51
#Mann=9,-1,0
  4163.4    0.05       0  4306.5    0.08       0  4432.8    0.05       0
  4530.5    0.08       0  4998.7    0.07       0  5004.7    0.08       0
  5016.0    0.05       0  5137.4    0.16       0  5204.6     0.1       0
Bank Sta=4998.7,5004.7
Exp/Cntr=0.3,0.1

Type RM Length L Ch R = 1,150,0,0,0
BEGIN DESCRIPTION:
WILLOW CREEK TRIB 16 1.0
END DESCRIPTION:
XS GIS Cut Line= 4
      3513544.90     10445046.01      3513457.22     10445648.90
      3513930.31     10446098.12      3514271.60     10445946.43
#Sta/Elev= 30
  3996.5  390.60  4059.8  387.34  4083.0  385.97  4124.3  385.30  4189.4  381.23
  4194.4  381.70  4257.1  378.26  4355.7  374.35  4376.1  372.93  4442.4  373.57
  4464.8  374.33  4618.2  372.34  4674.7  372.87  4865.7  371.73  4957.6  372.08
  4990.1  370.02  4992.9  369.52  4996.1  370.02  5021.4  372.18  5247.6  370.95
  5292.9  371.89  5353.1  371.55  5402.3  374.08  5462.7  379.84  5489.9  384.96
  5500.8  385.99  5507.1  387.23  5512.6  389.53  5530.4  391.98  5631.6  392.06
#Mann=10,-1,0
  3996.5    0.05       0  4059.8    0.08       0  4257.1    0.05       0
  4355.7    0.12       0  4442.4    0.16       0  4674.7    0.12       0
  4990.1    0.07       0  4996.1    0.12       0  5353.1    0.05       0
  5462.7     0.1       0
Bank Sta=4990.1,4996.1
Exp/Cntr=0.3,0.1

Chan Stop Cuts=-1