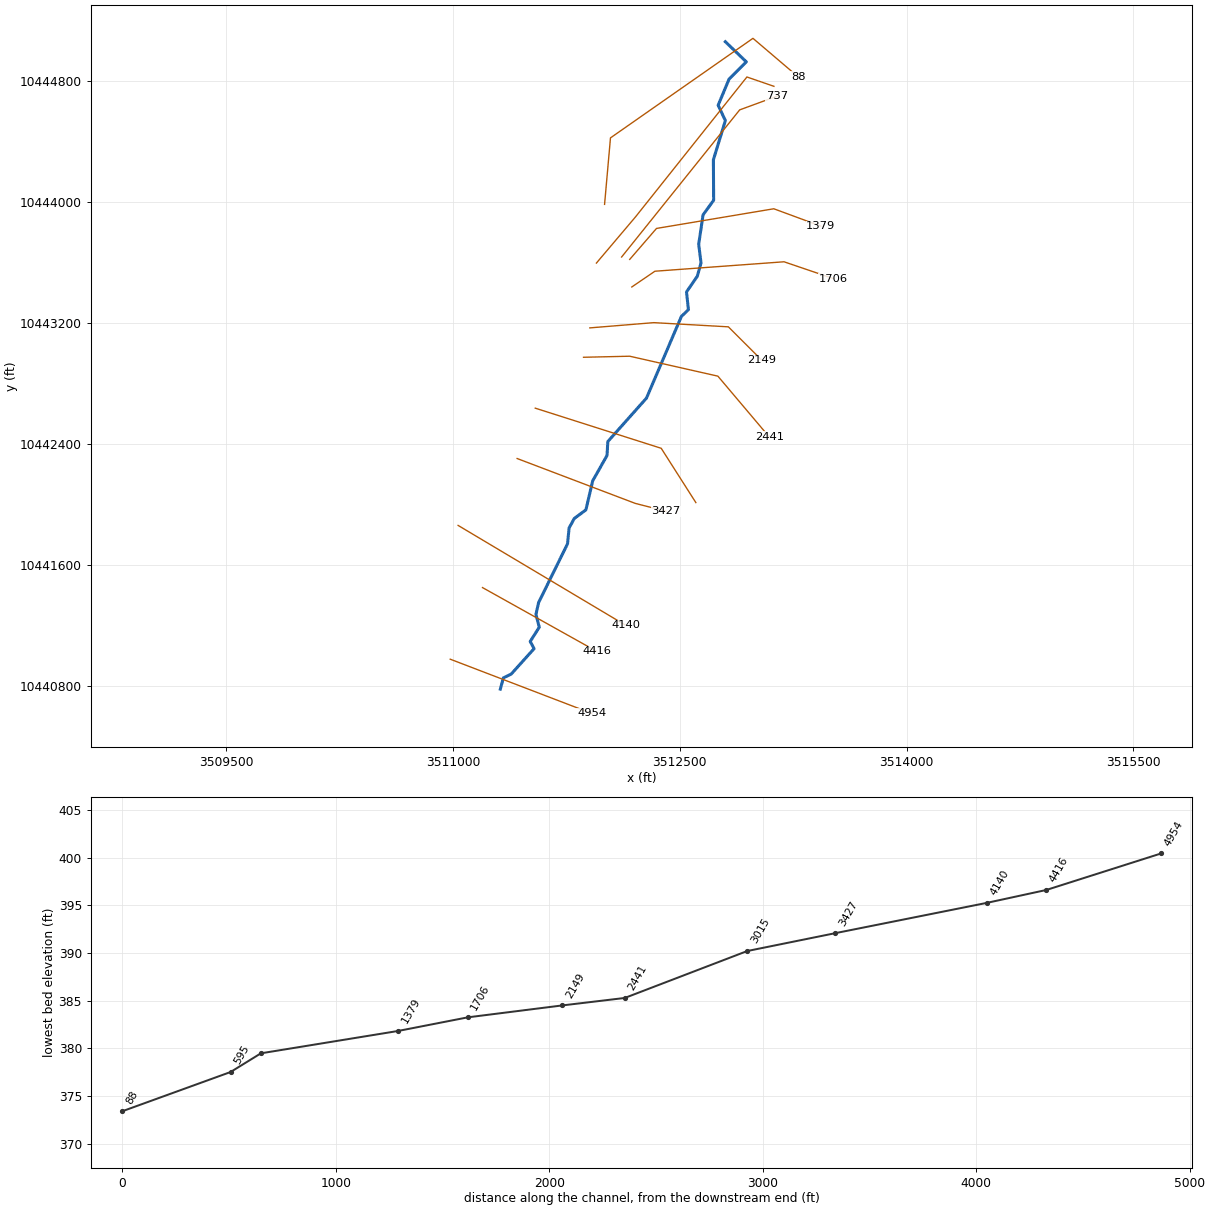
--- WILLOW CREEK TRIB 17.prj (project) ---

Proj Title=WILLOW CREEK TRIB 17 Base Level Engineering
Current Plan=p01
Default Exp/Contr=0.3,0.1
English Units
Geom File=g01
Flow File=f01
Plan File=p01
Y Axis Title=Elevation
X Axis Title(PF)=Main Channel Distance
X Axis Title(XS)=Station
BEGIN DESCRIPTION:
WILLOW CREEK TRIB 17
END DESCRIPTION:
DSS Export Rating Curves= 0
DSS Export Rating Curve Sorted= 0
DSS Export Volume Flow Curves= 0
DXF OffsetX= 0
DXF OffsetY= 0
DXF ScaleX= 1
DXF ScaleY= 10

--- WILLOW CREEK TRIB 17.p01 (plan) ---

Plan Title=Multiple Run
Short Identifier=Multiple
Geom File=g01
Flow File=f01
Subcritical Flow
K Sum by GR= 0
Std Step Tol= 0.01
Critical Tol= 0.01
Num of Std Step Trials= 20
Max Error Tol= 0.3
Flow Tol Ratio= 0.001
Split Flow NTrial= 30
Split Flow Tol= 0.02
Split Flow Ratio= 0.02
Log Output Level= 0
Friction Slope Method= 1
Unsteady Friction Slope Method= 2
Unsteady Bridges Friction Slope Method= 1
Parabolic Critical Depth
Global Vel Dist=  1 , 1 , 1
Global Log Level= 0
CheckData=True
Encroach Param= -1, 0, 0, 0
BEGIN DESCRIPTION:
Multiple Run
END DESCRIPTION:

--- WILLOW CREEK TRIB 17.f01 (steady flow) ---

Flow Title=Multiple
Number of Profiles=7
Profile Names=10-year,25-year,50-year,1pct_min,100-year,1pct_plu,500-year
River Rch & RM= WILLOW CREEK TRI,Reach-1,4954
     773    1052    1280    1138    1539    2081    2217
River Rch & RM= WILLOW CREEK TRI,Reach-1,88
    2600    3752    4744    4361    5898    7977    9106
Boundary for River Rch & Prof#=WILLOW CREEK TRI,Reach-1,1
Up Type=0
Dn Type=3
Dn Slope=0.005
Boundary for River Rch & Prof#=WILLOW CREEK TRI,Reach-1,2
Up Type=0
Dn Type=3
Dn Slope=0.005
Boundary for River Rch & Prof#=WILLOW CREEK TRI,Reach-1,3
Up Type=0
Dn Type=3
Dn Slope=0.005
Boundary for River Rch & Prof#=WILLOW CREEK TRI,Reach-1,4
Up Type=0
Dn Type=3
Dn Slope=0.005
Boundary for River Rch & Prof#=WILLOW CREEK TRI,Reach-1,5
Up Type=0
Dn Type=3
Dn Slope=0.005
Boundary for River Rch & Prof#=WILLOW CREEK TRI,Reach-1,6
Up Type=0
Dn Type=3
Dn Slope=0.005
Boundary for River Rch & Prof#=WILLOW CREEK TRI,Reach-1,7
Up Type=0
Dn Type=3
Dn Slope=0.005

--- WILLOW CREEK TRIB 17.g01 (geometry) ---

Geom Title=Existing Conditions
Program Version=4.10

River Reach=WILLOW CREEK TRI,Reach-1
Reach XY= 30
      3511312.59     10440776.77      3511332.67     10440851.46
       3511384.3     10440876.16      3511535.98     10441044.95
      3511510.27     10441092.38      3511570.17     10441186.71
      3511548.26     10441271.72      3511565.87     10441350.01
      3511757.17     10441738.78      3511767.63     10441844.15
       3511802.1     10441906.65       3511878.6     10441963.16
      3511923.84     10442155.91      3512018.53     10442323.41
      3512023.72     10442415.41      3512279.39     10442702.84
      3512510.56     10443243.62      3512557.01     10443288.34
      3512544.28     10443405.63      3512615.66     10443509.56
      3512640.41     10443597.36      3512624.94     10443721.33
      3512653.88      10443915.9      3512723.93     10444012.35
      3512722.09     10444280.18      3512801.46     10444539.73
      3512753.71      10444641.3      3512825.76     10444814.04
      3512940.06     10444928.52      3512801.31     10445061.52

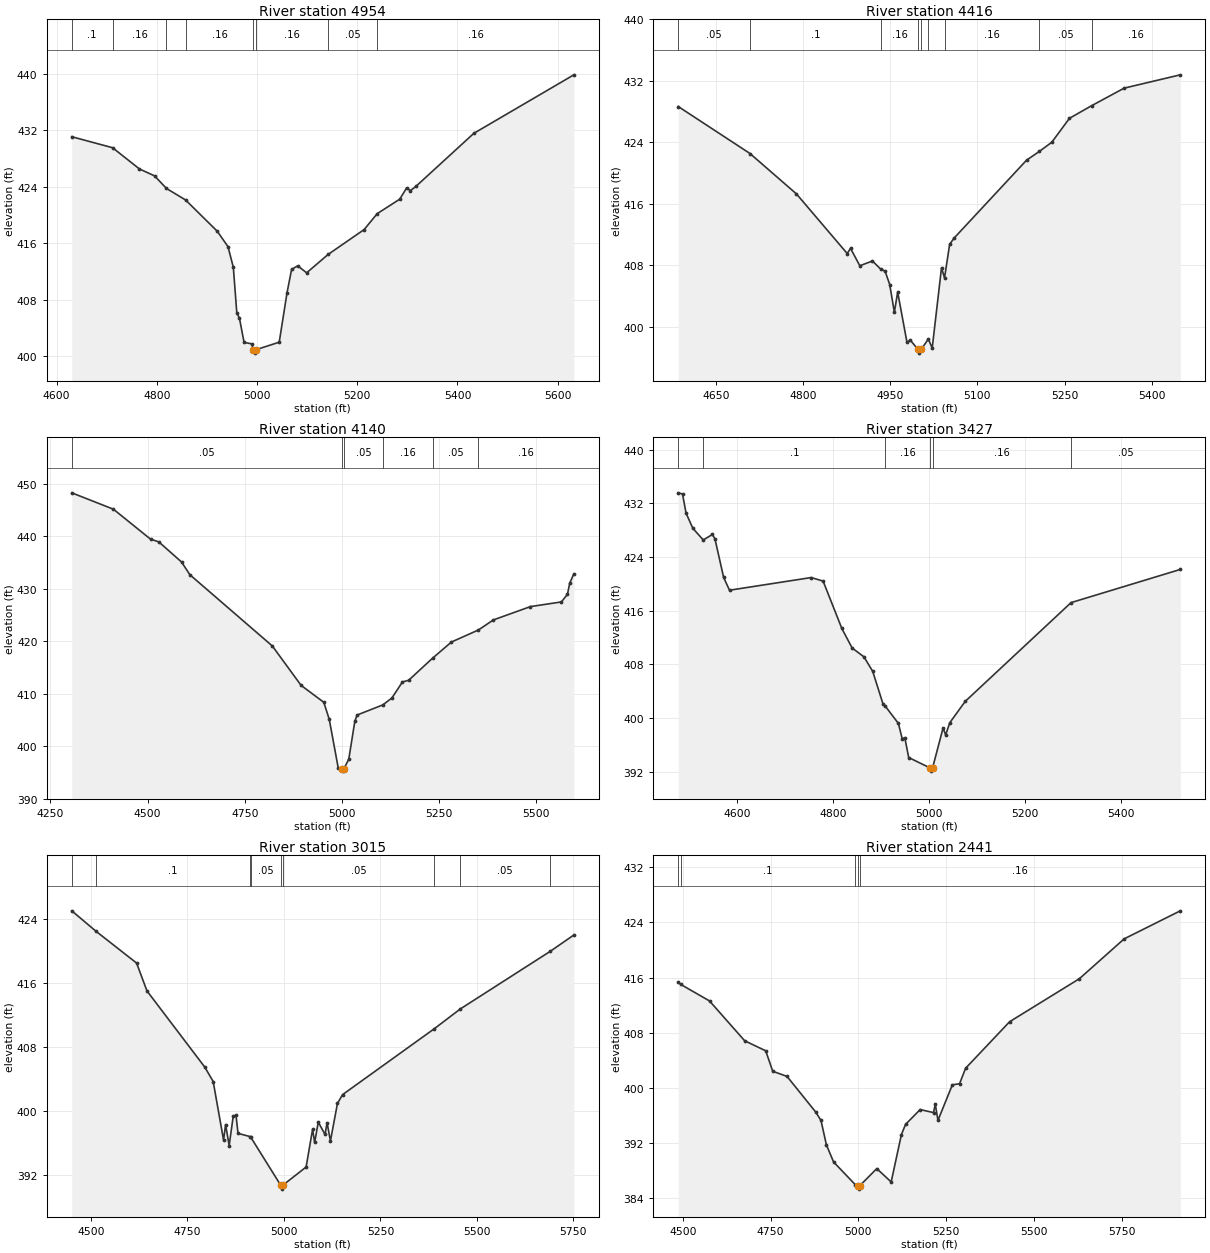
Type RM Length L Ch R = 1 ,4954    ,538,538,538
BEGIN DESCRIPTION:
WILLOW CREEK TRIB 17 11.0
END DESCRIPTION:
XS GIS Cut Line= 2
      3510981.07     10440975.04       3511916.6     10440616.43
#Sta/Elev= 30
  4630.3  431.09  4711.8  429.53  4765.4  426.52  4795.4  425.55  4819.3  423.76
  4857.4  422.13  4920.6   417.7    4942  415.52  4952.7  412.59  4959.6  406.16
  4964.9  405.38  4974.1  401.96  4989.6  401.74  4992.5  400.93  4995.3  400.43
  4998.5  400.93  5044.3  401.98  5059.8  408.96    5069   412.3  5081.2   412.8
    5099  411.81  5141.8  414.41  5213.8  417.94  5239.8  420.19  5284.7  422.24
  5298.5  423.83  5306.1  423.45  5316.8  424.04  5432.6  431.57  5632.2  439.86
#Mann= 8 ,-1 , 0
  4630.3      .1       0  4711.8     .16       0  4819.3     .05       0
  4857.4     .16       0  4992.5     .07       0  4998.5     .16       0
  5141.8     .05       0  5239.8     .16       0
Bank Sta=4992.5,4998.5
XS Rating Curve= 0 ,0
Exp/Cntr=0.3,0.1

Type RM Length L Ch R = 1 ,4416    ,276,276,276
BEGIN DESCRIPTION:
WILLOW CREEK TRIB 17 10.0
END DESCRIPTION:
XS GIS Cut Line= 2
      3511194.62       10441449.      3511948.47     10441027.88
#Sta/Elev= 30
  4585.5  428.66  4708.9  422.55  4788.8   417.3  4876.1  409.55  4881.8  410.22
  4897.8  407.96  4919.5  408.58  4934.1  407.49  4941.2  407.27  4949.2  405.52
  4957.2  401.91  4962.9  404.54  4978.9     398  4984.6  398.29  4997.6   397.1
  5000.3   396.6  5003.6   397.1  5015.6  398.43  5022.3  397.26  5038.3   407.7
  5043.5  406.38  5052.3  410.75    5060  411.56  5184.5  421.68  5206.5  422.82
  5227.9  424.01  5258.4  427.13  5296.3  428.76  5352.4  431.05    5449  432.78
#Mann= 9 ,-1 , 0
  4585.5     .05       0  4708.9      .1       0  4934.1     .16       0
  4997.6     .07       0  5003.6     .16       0  5015.6     .05       0
  5043.5     .16       0  5206.5     .05       0  5296.3     .16       0
Bank Sta=4997.6,5003.6
XS Rating Curve= 0 ,0
Exp/Cntr=0.3,0.1

Type RM Length L Ch R = 1 ,4140    ,713,713,713
BEGIN DESCRIPTION:
WILLOW CREEK TRIB 17 9.0
END DESCRIPTION:
XS GIS Cut Line= 2
      3511033.16     10441860.46      3512142.53       10441199.
#Sta/Elev= 30
    4305  448.24  4412.2  445.12  4507.6  439.42    4529   438.9  4587.4  435.07
  4608.8  432.65    4821  419.08    4895  411.58  4953.4  408.36  4967.4  405.11
  4990.4   395.9  4999.3  395.76  5002.1  395.26  5005.3  395.76  5017.6  397.53
  5033.2  404.76    5039  405.94  5105.3  407.87  5128.6  409.19  5155.8  412.25
  5171.4  412.54  5233.3  416.77  5281.8  419.84  5351.1  422.13  5389.4  424.04
  5484.8  426.58  5564.6  427.47  5580.2  428.93    5586  431.04  5596.6  432.81
#Mann= 6 ,-1 , 0
    4305     .05       0  4999.3     .03       0  5005.3     .05       0
  5105.3     .16       0  5233.3     .05       0  5351.1     .16       0
Bank Sta=4999.3,5005.3
XS Rating Curve= 0 ,0
Exp/Cntr=0.3,0.1

Type RM Length L Ch R = 1 ,3427    ,412,412,412
BEGIN DESCRIPTION:
WILLOW CREEK TRIB 17 8.0
END DESCRIPTION:
XS GIS Cut Line= 3
      3511423.79     10442303.16      3512205.05     10442006.29
      3512407.63     10441954.34
#Sta/Elev= 30
  4477.7  433.59  4486.6  433.41    4494  430.56    4508  428.31  4529.7  426.56
  4548.9  427.38  4554.2   426.7  4572.2  420.96  4584.4  419.06  4754.4  420.95
  4779.2  420.42  4818.2  413.35  4839.6  410.44  4864.2  409.12  4882.4  406.96
  4903.8  402.11    4909  401.72  4935.9  399.19  4943.9  396.87  4949.2  397.07
  4957.3   394.1  5001.1  392.57  5003.9  392.07  5007.1  392.57  5028.9  398.52
  5034.2  397.46  5042.9   399.3    5075  402.48  5295.2  417.21  5522.6  422.16
#Mann= 6 ,-1 , 0
  4477.7     .05       0  4529.7      .1       0    4909     .16       0
  5001.1     .07       0  5007.1     .16       0  5295.2     .05       0
Bank Sta=5001.1,5007.1
XS Rating Curve= 0 ,0
Exp/Cntr=0.3,0.1

Type RM Length L Ch R = 1 ,3015    ,574,574,574
BEGIN DESCRIPTION:
WILLOW CREEK TRIB 17 7.0
END DESCRIPTION:
XS GIS Cut Line= 3
       3511543.6     10442636.49      3512376.92     10442370.87
      3512606.12     10442011.46
#Sta/Elev= 30
  4450.2  424.96  4513.7  422.38  4618.1  418.44    4645  414.96    4795  405.43
  4816.6  403.64  4843.5  396.33  4848.8  398.27    4858  395.63  4868.5   399.3
  4875.7  399.43    4881  397.16  4912.5  396.76  4914.4  396.65  4991.4   390.7
  4994.2   390.2  4997.4   390.7  5057.4  392.96  5074.2  397.68  5079.5  396.03
  5088.9  398.57  5106.4  397.03  5111.7  398.49  5120.4  396.22  5138.6   400.9
  5151.8     402    5390  410.25  5456.8   412.7  5689.6  419.89  5751.1  421.94
#Mann= 9 ,-1 , 0
  4450.2     .05       0  4513.7      .1       0  4912.5     .16       0
  4914.4     .05       0  4991.4     .03       0  4997.4     .05       0
    5390     .16       0  5456.8     .05       0  5689.6     .16       0
Bank Sta=4991.4,4997.4
XS Rating Curve= 0 ,0
Exp/Cntr=0.3,0.1

Type RM Length L Ch R = 1 ,2441    ,292,292,292
BEGIN DESCRIPTION:
WILLOW CREEK TRIB 17 5.0
END DESCRIPTION:
XS GIS Cut Line= 4
        3511863.      10442973.3      3512168.59     10442980.24
      3512751.92      10442848.3      3513091.74     10442446.07
#Sta/Elev= 30
    4487   415.3  4494.4  414.99  4576.1   412.6  4676.2  406.82  4736.2  405.36
  4756.2  402.39    4797  401.64  4878.3  396.49  4893.7  395.25  4909.1   391.7
  4929.6  389.22  4990.9  385.95  4998.3  385.78  5001.1  385.28  5004.3  385.78
  5052.6  388.26  5093.6  386.32  5122.8   393.2  5134.6  394.68  5176.2  396.83
  5214.2  396.39  5219.3  397.61  5226.9  395.26  5267.9  400.42  5288.4  400.58
  5305.7  402.83    5431  409.58  5629.9  415.83  5757.3  421.61  5917.3  425.68
#Mann= 5 ,-1 , 0
    4487     .16       0  4494.4      .1       0  4990.9     .16       0
  4998.3     .07       0  5004.3     .16       0
Bank Sta=4998.3,5004.3
XS Rating Curve= 0 ,0
Exp/Cntr=0.3,0.1

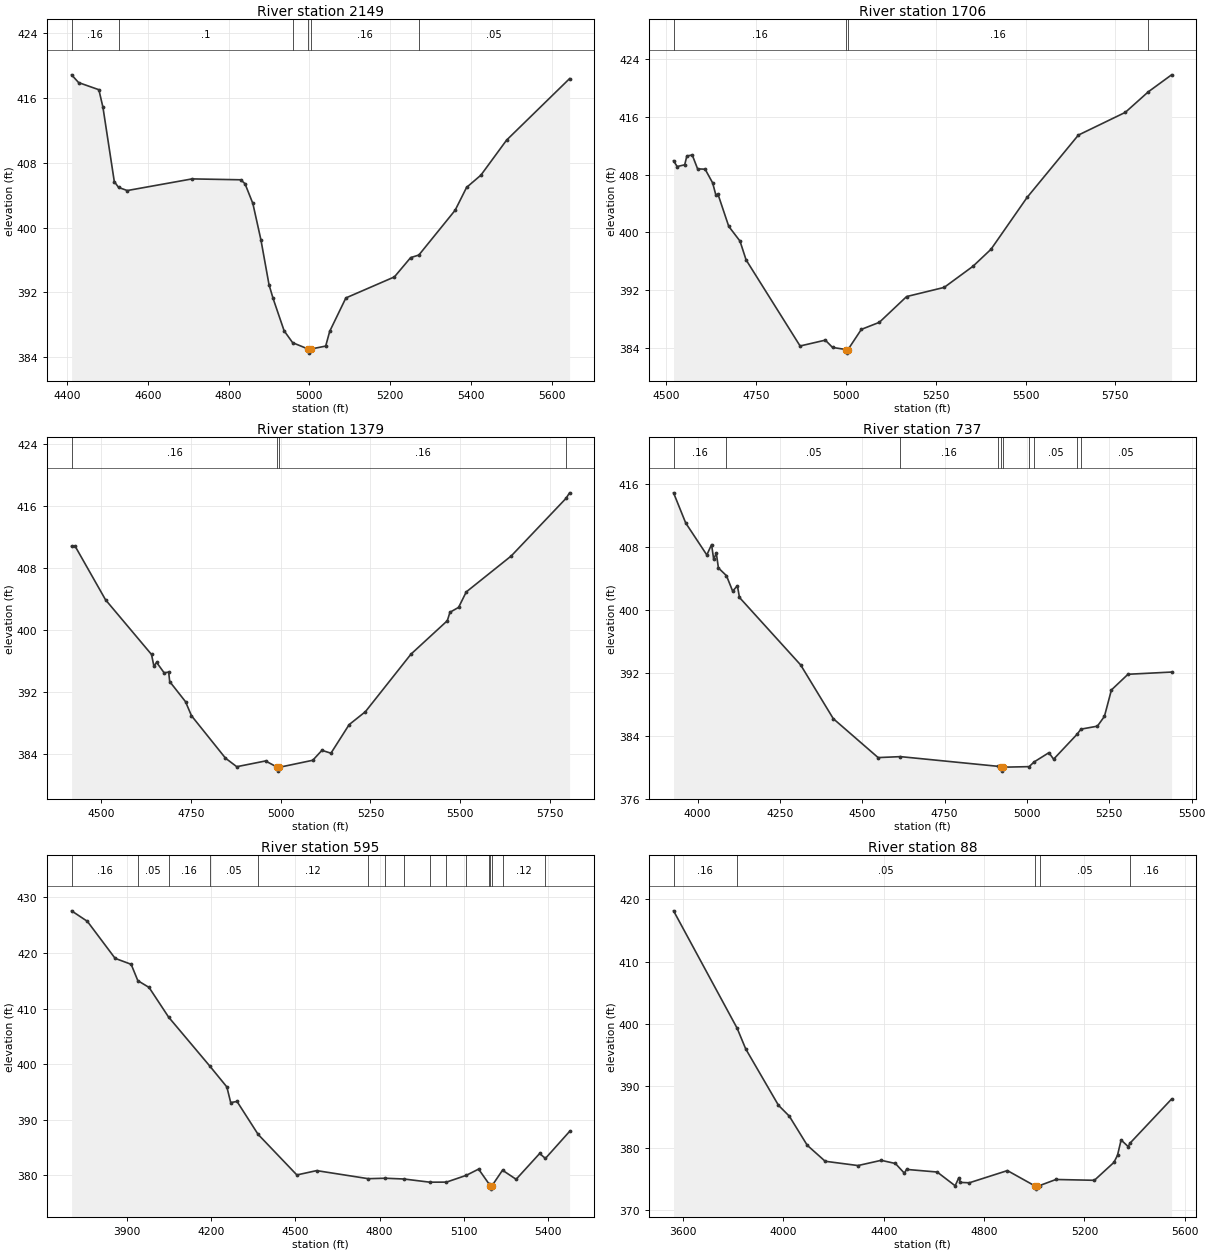
Type RM Length L Ch R = 1 ,2149    ,443,443,443
BEGIN DESCRIPTION:
WILLOW CREEK TRIB 17 4.0
END DESCRIPTION:
XS GIS Cut Line= 4
      3511904.69     10443167.74      3512328.31     10443202.47
      3512821.37     10443174.69      3513043.56      10442952.5
#Sta/Elev= 30
  4411.4  418.89  4428.9  417.93    4479  417.05  4489.1  414.88  4517.2   405.7
  4527.7  404.98  4549.3  404.59  4709.8  406.03  4830.2  405.92  4840.8  405.44
  4860.3  402.99  4880.3  398.49  4900.3  392.96  4910.3  391.27  4937.7  387.26
  4958.8  385.79  4997.5     385  5000.2   384.5  5003.5     385  5040.6  385.37
  5050.6   387.2  5090.6  391.32  5210.8  393.92  5250.9   396.3  5271.3  396.62
  5361.2  402.16  5389.5  404.98  5424.9  406.49  5488.5  410.82  5644.5  418.42
#Mann= 6 ,-1 , 0
  4411.4     .16       0  4527.7      .1       0  4958.8     .16       0
  4997.5     .07       0  5003.5     .16       0  5271.3     .05       0
Bank Sta=4997.5,5003.5
XS Rating Curve= 0 ,0
Exp/Cntr=0.3,0.1

Type RM Length L Ch R = 1 ,1706    ,327,327,327
BEGIN DESCRIPTION:
WILLOW CREEK TRIB 17 3.0
END DESCRIPTION:
XS GIS Cut Line= 4
      3512182.45     10443438.56      3512335.26     10443542.74
      3513189.42     10443605.24      3513515.83     10443494.13
#Sta/Elev= 30
  4520.1  409.91  4530.1  409.11  4551.1  409.35  4557.1  410.57  4572.1  410.71
    4587  408.79    4608  408.74  4628.9  406.84  4637.8  405.17  4643.9  405.25
  4673.7  400.82    4705  398.78  4721.9  396.18  4872.3  384.24  4942.5  385.05
  4962.6  384.04  4999.7  383.75  5002.4  383.25  5005.7  383.75  5042.8  386.54
  5092.9  387.52  5168.8  391.09  5273.4  392.36  5353.6  395.29  5403.8  397.65
    5504  404.82  5646.9  413.47  5777.6  416.62  5841.4  419.46  5906.3  421.82
#Mann= 4 ,-1 , 0
  4520.1     .16       0  4999.7     .07       0  5005.7     .16       0
  5841.4     .05       0
Bank Sta=4999.7,5005.7
XS Rating Curve= 0 ,0
Exp/Cntr=0.3,0.1

Type RM Length L Ch R = 1 ,1379    ,642,642,642
BEGIN DESCRIPTION:
WILLOW CREEK TRIB 17 2.0
END DESCRIPTION:
XS GIS Cut Line= 4
      3512168.66     10443621.01      3512345.76      10443825.9
       3513121.8     10443956.11      3513432.48     10443841.36
#Sta/Elev= 30
  4416.6  410.79  4426.8  410.78  4511.3   403.9  4639.6  396.85  4646.2  395.35
  4653.8  395.83  4674.7  394.49  4687.4  394.58  4690.3  393.36  4734.4  390.77
    4751  388.96  4845.9  383.49  4877.3  382.39  4957.5  383.13  4990.5  382.32
  4993.3  381.82  4996.5  382.32  5089.3  383.22  5114.8   384.5    5140  384.13
  5190.7  387.81  5236.1  389.48  5363.1  396.89  5464.5   401.2  5471.9  402.29
    5496  402.92  5517.3  404.91  5642.9  409.55  5795.4  416.96  5805.5  417.68
#Mann= 4 ,-1 , 0
  4416.6     .16       0  4990.5     .07       0  4996.5     .16       0
  5795.4     .05       0
Bank Sta=4990.5,4996.5
XS Rating Curve= 0 ,0
Exp/Cntr=0.3,0.1

Type RM Length L Ch R = 1 ,737     ,142,142,142
BEGIN DESCRIPTION:
Mapping XS db009ecf
END DESCRIPTION:
XS GIS Cut Line= 3
      3512114.89      10443636.7      3512896.11     10444610.62
      3513143.56     10444701.38
#Sta/Elev= 30
  3926.9  414.82  3963.8  410.99  4027.9  406.93  4042.3  408.25  4048.7  406.39
  4056.7  407.16  4063.1  405.28  4087.5   404.3  4106.3  402.34  4120.7  403.02
  4127.1  401.53  4312.7  392.97  4411.9  386.14    4548   381.2  4615.9  381.32
  4912.3  380.09    4921  379.98  4923.8  379.48    4927  379.98  5006.5  380.05
  5021.7  380.65  5066.5  381.82  5080.9     381  5151.6  384.14  5163.9  384.81
  5213.8  385.19  5235.1  386.43  5256.4  389.79  5306.7  391.78    5439  392.06
#Mann= 10 ,-1 , 0
  3926.9     .16       0  4087.5     .05       0  4615.9     .16       0
  4912.3     .05       0    4921     .03       0    4927     .05       0
  5006.5     .16       0  5021.7     .05       0  5151.6     .16       0
  5163.9     .05       0
Bank Sta=4921,4927
XS Rating Curve= 0 ,0
Exp/Cntr=0.3,0.1

Type RM Length L Ch R = 1 ,595     ,507,507,507
BEGIN DESCRIPTION:
WILLOW CREEK TRIB 17 1.2
END DESCRIPTION:
XS GIS Cut Line= 4
      3511948.22     10443596.76      3512206.87     10443902.29
      3512943.94     10444828.35      3513122.78     10444766.57
#Sta/Elev= 30
  3703.1  427.58  3759.3  425.69  3858.2  419.03  3915.3  417.96    3939  415.02
    3979   413.8  4048.8  408.45  4195.2  399.66    4256   395.9  4269.7  393.09
  4292.2  393.29  4367.4  387.36  4505.2  380.07  4575.7  380.85  4759.3   379.4
    4820  379.48  4886.7  379.34  4978.4  378.77  5037.8  378.78  5107.9  379.99
  5152.3  381.12    5189  378.48  5192.5  378.02  5195.3  377.52  5198.5  378.02
  5237.4  380.92  5285.9  379.29  5369.7  383.93  5390.1  383.04  5476.2   387.9
#Mann= 16 ,-1 , 0
  3703.1     .16       0    3939     .05       0  4048.8     .16       0
  4195.2     .05       0  4367.4     .12       0  4759.3     .16       0
    4820     .12       0  4886.7     .16       0  4978.4     .12       0
  5037.8     .16       0  5107.9     .12       0    5189     .16       0
  5192.5     .07       0  5198.5     .16       0  5237.4     .12       0
  5390.1     .05       0
Bank Sta=5192.5,5198.5
XS Rating Curve= 0 ,0
Exp/Cntr=0.3,0.1

Type RM Length L Ch R = 1 ,88      ,0,0,0
BEGIN DESCRIPTION:
WILLOW CREEK TRIB 17 1.0
END DESCRIPTION:
XS GIS Cut Line= 4
      3512002.21      10443985.1      3512041.28     10444425.25
      3512983.98      10445084.1      3513283.49     10444828.87
#Sta/Elev= 30
  3562.1  418.15  3815.5  399.28  3849.8  395.95  3980.3  386.89  4023.6  385.14
  4095.1  380.46  4166.6  377.89  4297.4   377.2  4389.9  378.04  4446.6  377.53
  4482.3  375.97    4491  376.58  4613.1  376.16  4684.7  373.95  4699.5  375.24
  4705.6  374.49  4741.3  374.43  4893.1  376.39  5003.5  373.91  5006.2  373.41
  5009.5  373.91  5021.3  373.98  5086.7  374.96  5239.9  374.83  5317.8  377.71
  5332.1  378.86  5346.4  381.31  5374.9  380.24  5381.5  380.78  5547.6  387.89
#Mann= 5 ,-1 , 0
  3562.1     .16       0  3815.5     .05       0  5003.5     .03       0
  5021.3     .05       0  5381.5     .16       0
Bank Sta=5003.5,5009.5
XS Rating Curve= 0 ,0
Exp/Cntr=0.3,0.1

Chan Stop Cuts=-1
Use User Specified Reach Order=0
Composite Channel Slope=5