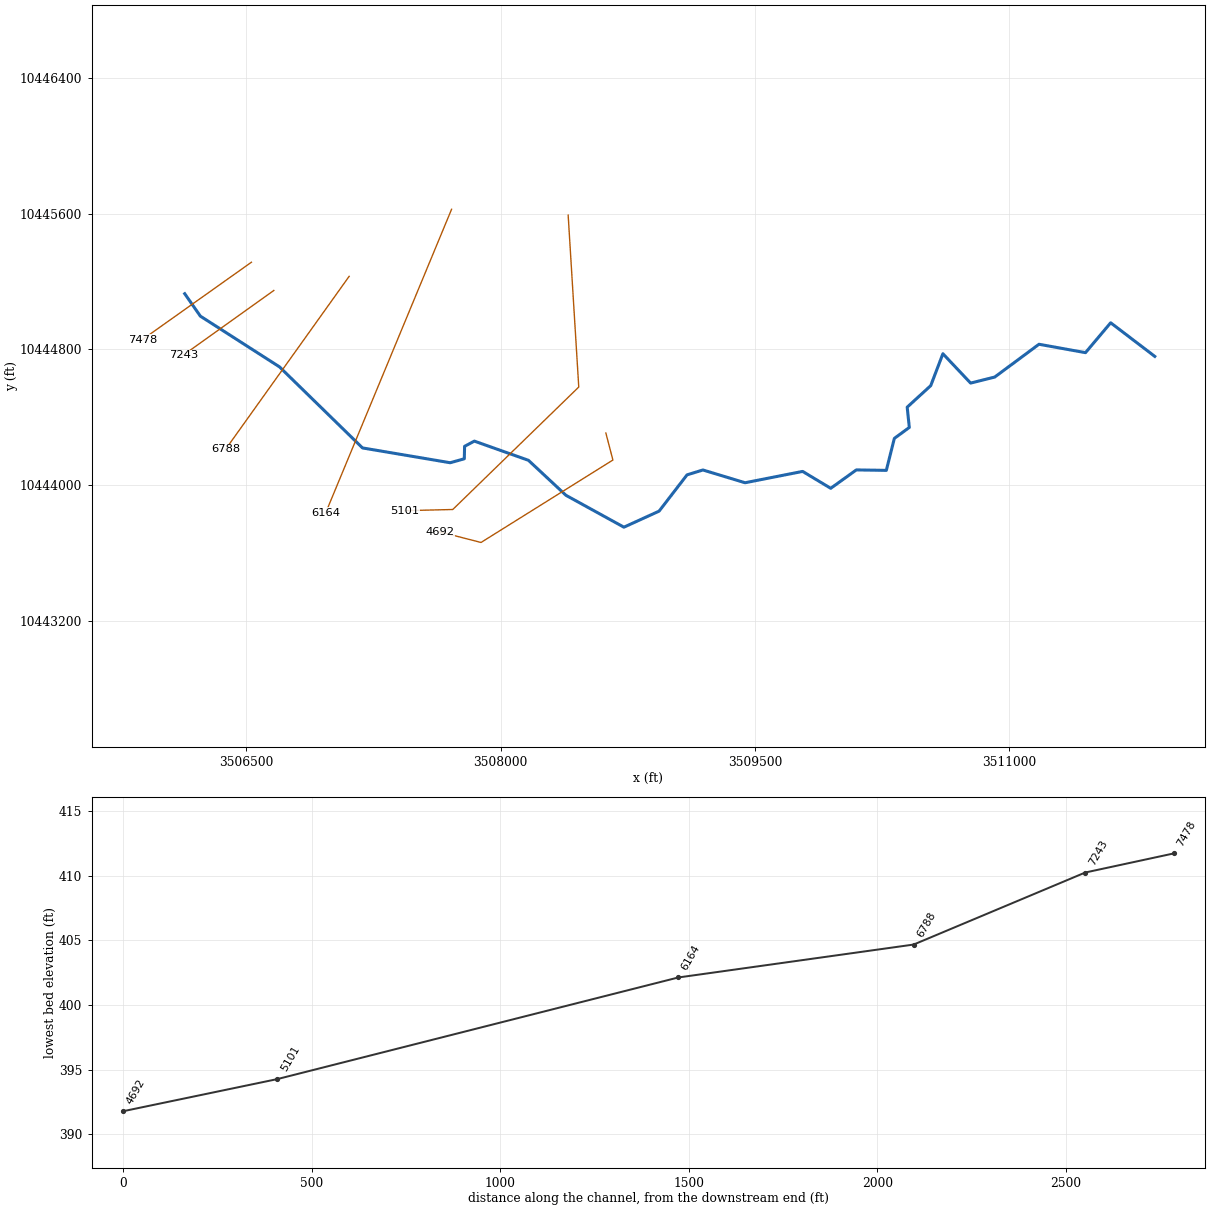
--- WILLOW CREEK TRIB 19.prj (project) ---

Proj Title=WILLOW CREEK TRIB 19 Base Level Engineering
Current Plan=p01
Default Exp/Contr=0.3,0.1
English Units
Geom File=g01
Flow File=f01
Plan File=p01
Y Axis Title=Elevation
X Axis Title(PF)=Main Channel Distance
X Axis Title(XS)=Station
BEGIN DESCRIPTION:
WILLOW CREEK TRIB 19
END DESCRIPTION:
DSS Export Rating Curves= 0
DSS Export Rating Curve Sorted= 0
DSS Export Volume Flow Curves= 0
DXF OffsetX= 0
DXF OffsetY= 0
DXF ScaleX= 1
DXF ScaleY= 10

--- WILLOW CREEK TRIB 19.p01 (plan) ---

Plan Title=Multiple Run
Short Identifier=Multiple
Geom File=g01
Flow File=f01
Subcritical Flow
K Sum by GR= 0
Std Step Tol= 0.01
Critical Tol= 0.01
Num of Std Step Trials= 20
Max Error Tol= 0.3
Flow Tol Ratio= 0.001
Split Flow NTrial= 30
Split Flow Tol= 0.02
Split Flow Ratio= 0.02
Log Output Level= 0
Friction Slope Method= 1
Unsteady Friction Slope Method= 2
Unsteady Bridges Friction Slope Method= 1
Parabolic Critical Depth
Global Vel Dist=  1 , 1 , 1
Global Log Level= 0
CheckData=True
Encroach Param= -1, 0, 0, 0
BEGIN DESCRIPTION:
Multiple Run
END DESCRIPTION:

--- WILLOW CREEK TRIB 19.f01 (steady flow) ---

Flow Title=Multiple
Program Version=4.10
Number of Profiles= 7
Profile Names=10-year,25-year,50-year,1pct_min,100-year,1pct_plu,500-year
River Rch & RM=WILLOW CREEK TRI,Reach-1         ,7478
     730     994    1210    1077    1456    1969    2100
Boundary for River Rch & Prof#=WILLOW CREEK TRI,Reach-1         , 1
Up Type= 0
Dn Type= 3
Dn Slope=0.01
Boundary for River Rch & Prof#=WILLOW CREEK TRI,Reach-1         , 2
Up Type= 0
Dn Type= 3
Dn Slope=0.01
Boundary for River Rch & Prof#=WILLOW CREEK TRI,Reach-1         , 3
Up Type= 0
Dn Type= 3
Dn Slope=0.01
Boundary for River Rch & Prof#=WILLOW CREEK TRI,Reach-1         , 4
Up Type= 0
Dn Type= 3
Dn Slope=0.01
Boundary for River Rch & Prof#=WILLOW CREEK TRI,Reach-1         , 5
Up Type= 0
Dn Type= 3
Dn Slope=0.01
Boundary for River Rch & Prof#=WILLOW CREEK TRI,Reach-1         , 6
Up Type= 0
Dn Type= 3
Dn Slope=0.01
Boundary for River Rch & Prof#=WILLOW CREEK TRI,Reach-1         , 7
Up Type= 0
Dn Type= 3
Dn Slope=0.01
DSS Import GetInterval= 0
DSS Import GetPeak= 0
DSS Import FillOption= 0

--- WILLOW CREEK TRIB 19.g01 (geometry) ---

Geom Title=Existing Conditions
Program Version=4.10

River Reach=WILLOW CREEK TRI,Reach-1
Reach XY= 30
      3506137.18     10445128.76      3506229.44     10444996.49
      3506696.02     10444697.34      3507185.75      10444219.2
       3507702.8     10444131.89      3507786.14      10444155.2
      3507787.78      10444228.5      3507845.32     10444259.38
      3508164.46     10444146.18      3508385.56      10443939.9
      3508727.38     10443751.81        3508935.     10443846.44
      3509099.74      10444060.4      3509193.39     10444089.16
        3509442.     10444013.89      3509781.49     10444080.74
      3509947.18     10443981.11      3510098.06     10444089.51
      3510274.96     10444086.88       3510322.4     10444275.51
       3510410.6     10444340.09       3510398.1     10444459.53
      3510536.99     10444586.62      3510608.74     10444774.84
      3510772.11     10444601.64      3510914.57     10444637.35
      3511175.44     10444830.62      3511449.75     10444781.14
      3511598.19     10444957.35      3511858.34     10444759.15

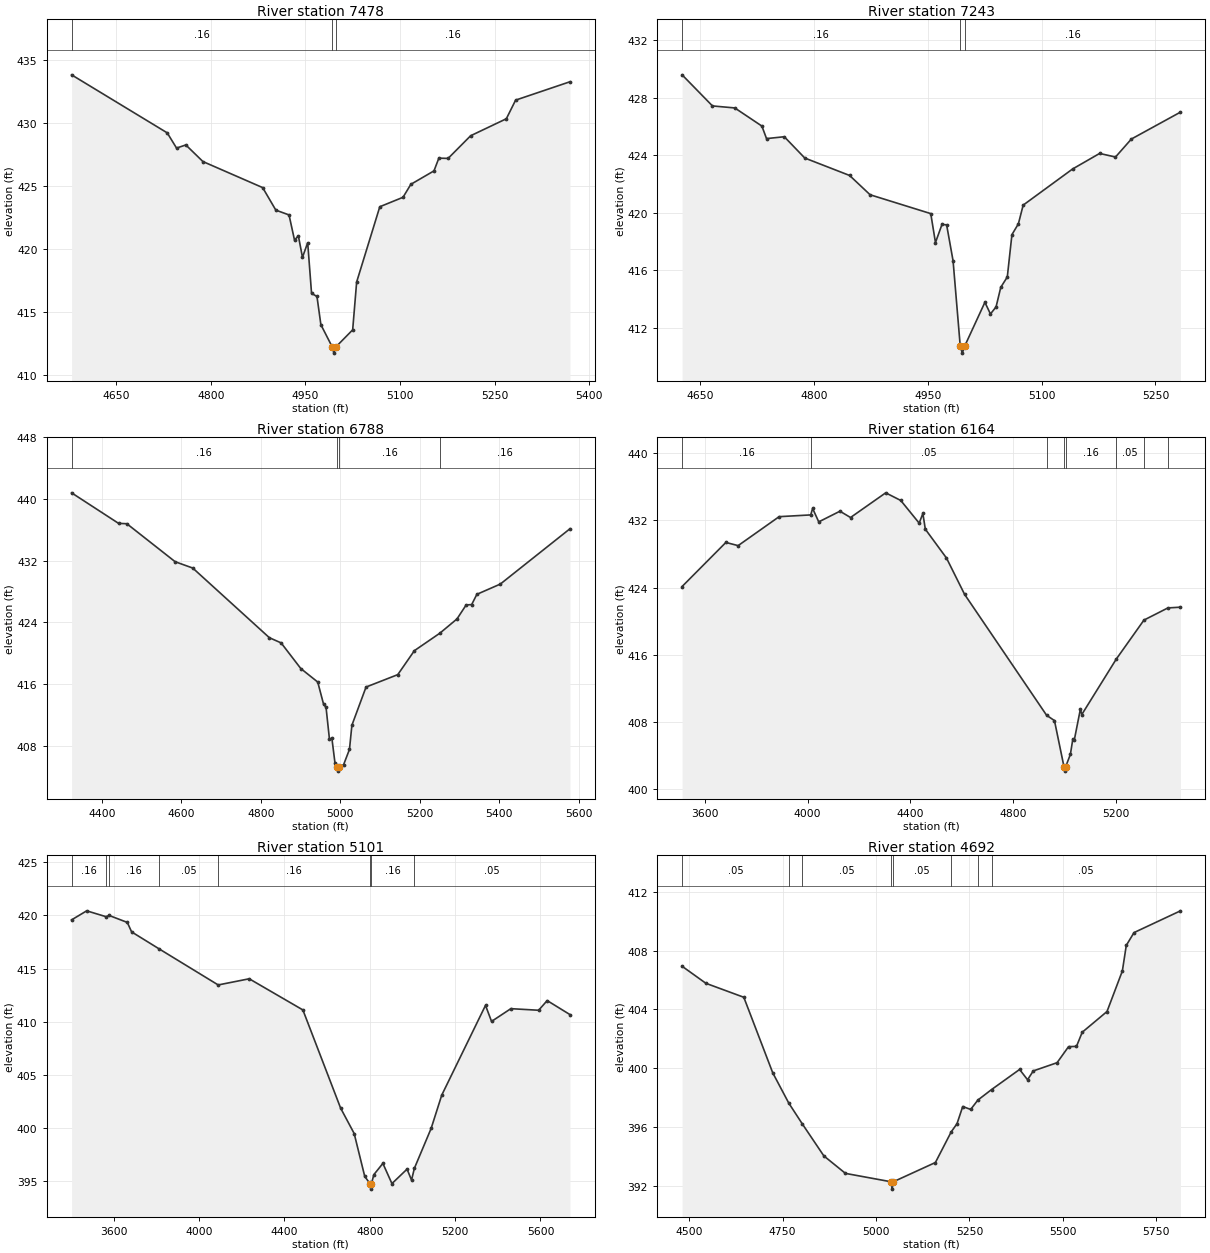
Type RM Length L Ch R = 1 ,7478    ,235,235,235
BEGIN DESCRIPTION:
WILLOW CREEK TRIB 19 8.0
END DESCRIPTION:
XS GIS Cut Line= 2
       3506530.6     10445314.46      3505886.26      10444857.2
#Sta/Elev= 30
  4579.4  433.85    4731  429.24  4745.8  428.03  4760.5  428.28  4787.6  426.96
  4882.3  424.89  4903.2   423.1  4924.1  422.72  4932.8  420.72  4938.9  421.06
  4945.4  419.35  4953.7  420.51  4959.8  416.49  4968.4  416.24  4974.6     414
  4992.5  412.24  4995.2  411.74  4998.5  412.24    5025  413.59  5031.3  417.39
    5068  423.37  5104.8  424.12  5117.2  425.15  5153.9  426.22  5161.6  427.23
  5176.3  427.21    5212  429.01  5268.6  430.36  5283.3  431.84  5369.5   433.3
#Mann= 3 ,-1 , 0
  4579.4     .16       0  4992.5     .07       0  4998.5     .16       0
Bank Sta=4992.5,4998.5
XS Rating Curve= 0 ,0
Exp/Cntr=0.3,0.1

Type RM Length L Ch R = 1 ,7243    ,455,455,455
BEGIN DESCRIPTION:
WILLOW CREEK TRIB 19 7.0
END DESCRIPTION:
XS GIS Cut Line= 2
      3506662.52     10445147.79      3506128.39     10444766.26
#Sta/Elev= 30
  4626.6  429.59  4666.6  427.43    4696  427.29  4731.7  426.03  4737.8  425.16
  4761.2  425.29  4788.2  423.81  4847.2   422.6  4874.2  421.26  4954.1  419.95
  4960.3  417.94  4968.9   419.2    4975  419.17  4983.5  416.67  4992.9  410.76
  4995.6  410.26  4998.9  410.76  5025.4  413.79  5032.7  412.98  5040.1  413.47
  5046.3  414.83  5054.9  415.55    5061  418.49  5069.5  419.24  5075.8  420.54
  5140.9  423.05  5176.5  424.13  5197.4  423.88  5218.3  425.13    5283     427
#Mann= 3 ,-1 , 0
  4626.6     .16       0  4992.9     .07       0  4998.9     .16       0
Bank Sta=4992.9,4998.9
XS Rating Curve= 0 ,0
Exp/Cntr=0.3,0.1

Type RM Length L Ch R = 1 ,6788    ,624,624,624
BEGIN DESCRIPTION:
WILLOW CREEK TRIB 19 6.0
END DESCRIPTION:
XS GIS Cut Line= 2
      3507106.99     10445231.15      3506377.76     10444210.24
#Sta/Elev= 30
  4323.4  440.79  4441.6  436.83  4462.5  436.78  4584.1  431.85  4628.4  431.03
  4821.3  421.99  4850.8  421.32  4900.4  417.99    4943  416.24  4957.7  413.36
  4963.9  412.97  4972.5  408.83  4978.6  408.96  4986.4  405.75  4990.4  405.18
  4993.1  404.68  4996.4  405.18  5008.1  405.51  5022.9   407.5    5029  410.63
  5064.6  415.59  5144.5   417.2  5186.3  420.31  5250.5  422.58  5293.6  424.43
  5316.6  426.24  5330.5  426.29  5343.6  427.62  5402.6  428.95    5578  436.13
#Mann= 4 ,-1 , 0
  4323.4     .16       0  4990.4     .03       0  4996.4     .16       0
  5250.5     .16       0
Bank Sta=4990.4,4996.4
XS Rating Curve= 0 ,0
Exp/Cntr=0.3,0.1

Type RM Length L Ch R = 1 ,6164    ,1063,1063,1063
BEGIN DESCRIPTION:
WILLOW CREEK TRIB 19 4.0
END DESCRIPTION:
XS GIS Cut Line= 2
      3507711.11     10445626.91      3506968.34     10443835.92
#Sta/Elev= 30
    3512  424.12  3682.3  429.37    3730  428.99  3889.5  432.44  4012.4  432.65
  4019.8  433.42  4043.6  431.82  4126.1  433.09  4167.3  432.34  4304.1  435.28
  4362.7  434.37  4434.3  431.67  4448.7  432.82  4458.2  430.95  4540.6  427.51
  4611.1  423.18  4930.1  408.78  4960.6  408.15  4997.8  402.63  5000.6  402.13
  5003.8  402.63  5022.5  404.12  5032.2  405.98  5037.6  405.81  5061.5  409.52
  5066.9  408.87  5200.7  415.46  5308.7  420.12  5401.9  421.57  5450.9  421.66
#Mann= 8 ,-1 , 0
    3512     .16       0  4012.4     .05       0  4930.1     .16       0
  4997.8     .07       0  5003.8     .16       0  5200.7     .05       0
  5308.7     .16       0  5401.9     .05       0
Bank Sta=4997.8,5003.8
XS Rating Curve= 0 ,0
Exp/Cntr=0.3,0.1

Type RM Length L Ch R = 1 ,5101    ,409,409,409
BEGIN DESCRIPTION:
WILLOW CREEK TRIB 19 2.0
END DESCRIPTION:
XS GIS Cut Line= 4
      3508398.62     10445592.26      3508461.13     10444578.33
      3507718.07     10443856.11      3507435.22     10443849.21
#Sta/Elev= 30
  3403.2  419.58    3474  420.43    3566  419.87  3578.3     420  3664.3  419.34
  3684.4  418.45  3814.3  416.84    4090  413.46  4235.4  414.04  4486.8  411.11
  4663.6  401.88  4727.1  399.49  4776.7  395.45    4802  394.76  4804.8  394.26
    4808  394.76  4819.2  395.62  4861.6  396.68    4904  394.78  4974.8  396.14
  4995.9  395.11    5009  396.21  5087.7  399.97  5137.4   403.1  5342.4  411.54
  5370.7  410.03  5461.2  411.23  5591.3  411.08  5631.3  411.99  5738.2  410.67
#Mann= 8 ,-1 , 0
  3403.2     .16       0    3566     .05       0  3578.3     .16       0
  3814.3     .05       0    4090     .16       0    4802     .07       0
    4808     .16       0    5009     .05       0
Bank Sta=4802,4808
XS Rating Curve= 0 ,0
Exp/Cntr=0.3,0.1

Type RM Length L Ch R = 1 ,4692    ,0,0,0
BEGIN DESCRIPTION:
WILLOW CREEK TRIB 19 1.0
END DESCRIPTION:
XS GIS Cut Line= 4
      3508620.84     10444307.51      3508662.51     10444147.78
      3507884.74     10443661.67      3507641.71     10443724.16
#Sta/Elev= 30
  4481.4  406.93  4545.1  405.77  4646.5  404.82  4723.9  399.68  4766.8  397.62
  4802.9  396.21  4860.6  394.03  4918.4  392.84  5040.4  392.27  5043.2  391.77
  5046.4  392.27    5159  393.58  5201.4  395.67  5216.8  396.22  5232.1  397.39
  5253.3  397.19  5272.7  397.83  5309.1  398.54  5384.2  399.91  5405.5  399.21
  5420.8  399.81  5484.5  400.37  5515.1  401.46  5536.4  401.48  5551.7  402.44
    5618  403.85  5659.1  406.61  5669.6  408.35  5690.3  409.22  5814.6   410.7
#Mann= 8 ,-1 , 0
  4481.4     .05       0  4766.8     .16       0  4802.9     .05       0
  5040.4     .03       0  5046.4     .05       0  5201.4     .05       0
  5272.7     .16       0  5309.1     .05       0
Bank Sta=5040.4,5046.4
XS Rating Curve= 0 ,0
Exp/Cntr=0.3,0.1

Chan Stop Cuts=-1
Use User Specified Reach Order=0
Composite Channel Slope=5