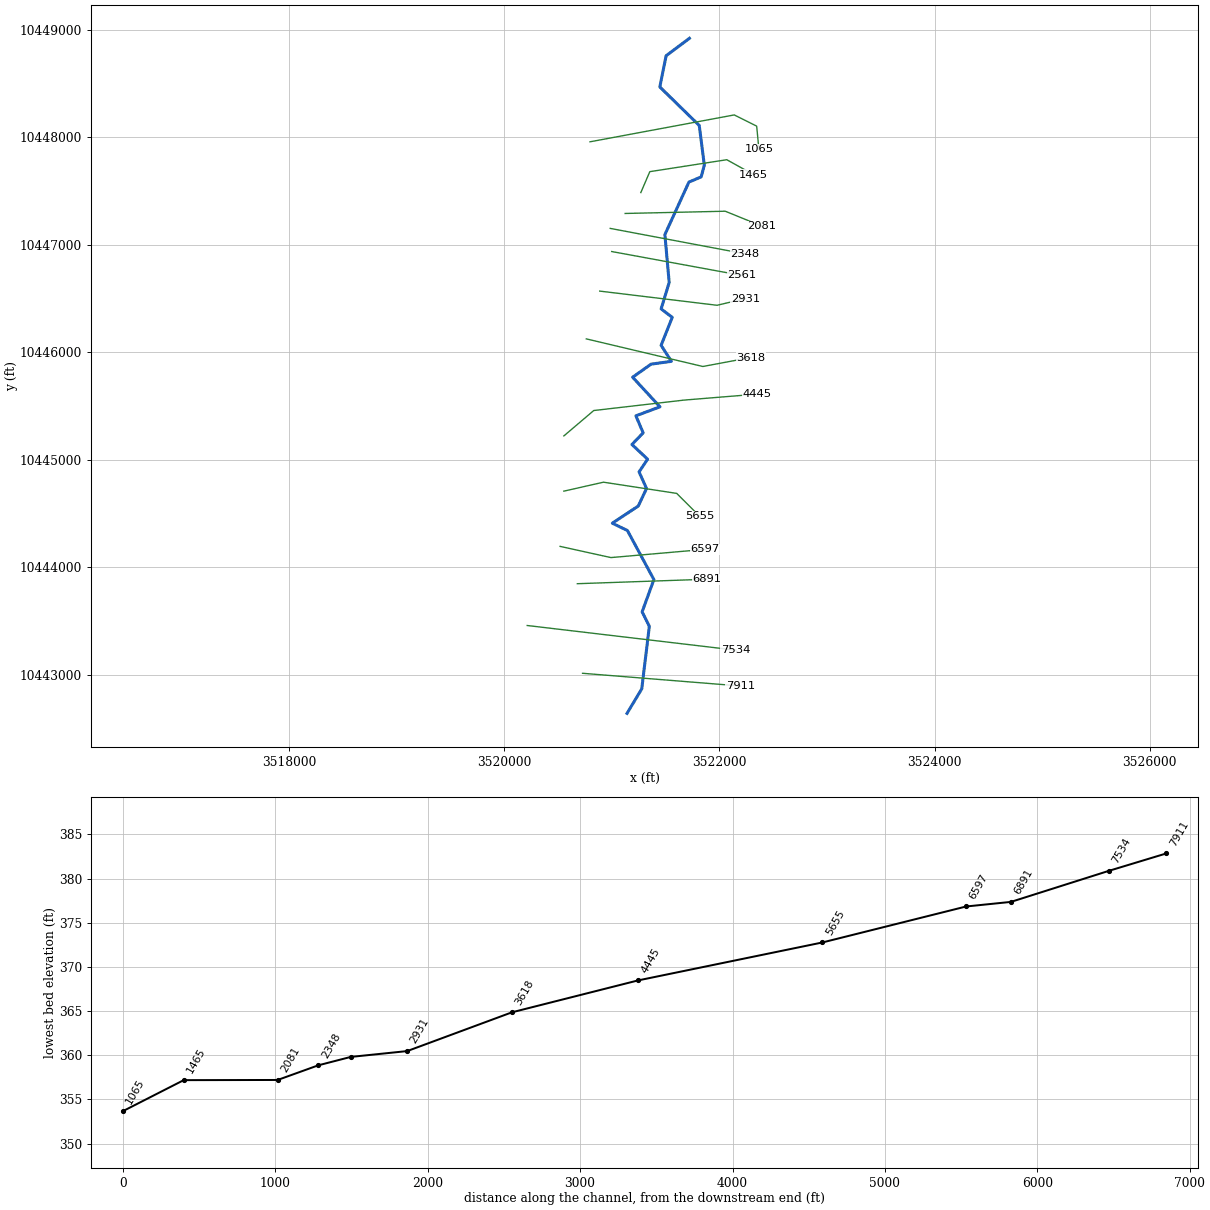
--- WILLOW CREEK TRIB 4 3.prj (project) ---

Proj Title=WILLOW CREEK TRIB 4 3 Base Level Engineering
Current Plan=p01
Default Exp/Contr=0.3,0.1
English Units
Geom File=g01
Flow File=f01
Plan File=p01
BEGIN DESCRIPTION:
WILLOW CREEK TRIB 4 3
END DESCRIPTION:

--- WILLOW CREEK TRIB 4 3.p01 (plan) ---

Plan Title=Multiple Run
Short Identifier=Multiple
Geom File=g01
Flow File=f01
Subcritical Flow
K Sum by GR= 0
Std Step Tol= 0.01
Critical Tol= 0.01
Num of Std Step Trials= 20
Max Error Tol= 0.3
Flow Tol Ratio= 0.001
Split Flow NTrial= 30
Split Flow Tol= 0.02
Split Flow Ratio= 0.02
Log Output Level= 0
Friction Slope Method= 1
Unsteady Friction Slope Method= 2
Unsteady Bridges Friction Slope Method= 1
Parabolic Critical Depth
Global Vel Dist=  1 , 1 , 1
Global Log Level= 0
CheckData=True
Encroach Param= -1, 0, 0, 0
BEGIN DESCRIPTION:
Multiple Run
END DESCRIPTION:

--- WILLOW CREEK TRIB 4 3.f01 (steady flow) ---

Flow Title=Multiple
Number of Profiles=7
Profile Names=10-year,25-year,50-year,1pct_min,100-year,1pct_plu,500-year
River Rch & RM= WILLOW CREEK TRI,Reach-1,7911
     761    1033    1254    1112    1504    2034    2158
Boundary for River Rch & Prof#=WILLOW CREEK TRI,Reach-1,1
Up Type=0
Dn Type=3
Dn Slope=0.005
Boundary for River Rch & Prof#=WILLOW CREEK TRI,Reach-1,2
Up Type=0
Dn Type=3
Dn Slope=0.005
Boundary for River Rch & Prof#=WILLOW CREEK TRI,Reach-1,3
Up Type=0
Dn Type=3
Dn Slope=0.005
Boundary for River Rch & Prof#=WILLOW CREEK TRI,Reach-1,4
Up Type=0
Dn Type=3
Dn Slope=0.005
Boundary for River Rch & Prof#=WILLOW CREEK TRI,Reach-1,5
Up Type=0
Dn Type=3
Dn Slope=0.005
Boundary for River Rch & Prof#=WILLOW CREEK TRI,Reach-1,6
Up Type=0
Dn Type=3
Dn Slope=0.005
Boundary for River Rch & Prof#=WILLOW CREEK TRI,Reach-1,7
Up Type=0
Dn Type=3
Dn Slope=0.005

--- WILLOW CREEK TRIB 4 3.g01 (geometry) ---

Geom Title=Existing Conditions

River Reach=WILLOW CREEK TRI,Reach-1
Reach XY= 30
      3521142.11     10442641.64      3521279.05     10442869.70
      3521349.65     10443451.35      3521282.64     10443586.18
      3521391.85     10443886.50      3521146.01     10444342.69
      3521005.60     10444410.83      3521246.81     10444570.76
      3521323.58     10444733.94      3521254.13     10444888.02
      3521333.34     10445006.29      3521187.94     10445143.01
      3521292.11     10445251.52      3521224.84     10445409.94
      3521448.36     10445493.49      3521194.45     10445769.10
      3521365.89     10445890.62      3521554.70     10445916.67
      3521459.21     10446065.32      3521562.29     10446325.74
      3521459.21     10446404.95      3521534.08     10446650.17
      3521494.02     10447095.83      3521717.45     10447584.30
      3521831.24     10447632.56      3521860.71     10447741.64
      3521813.39     10448111.04      3521447.12     10448469.15
      3521505.71     10448759.95      3521722.11     10448921.64

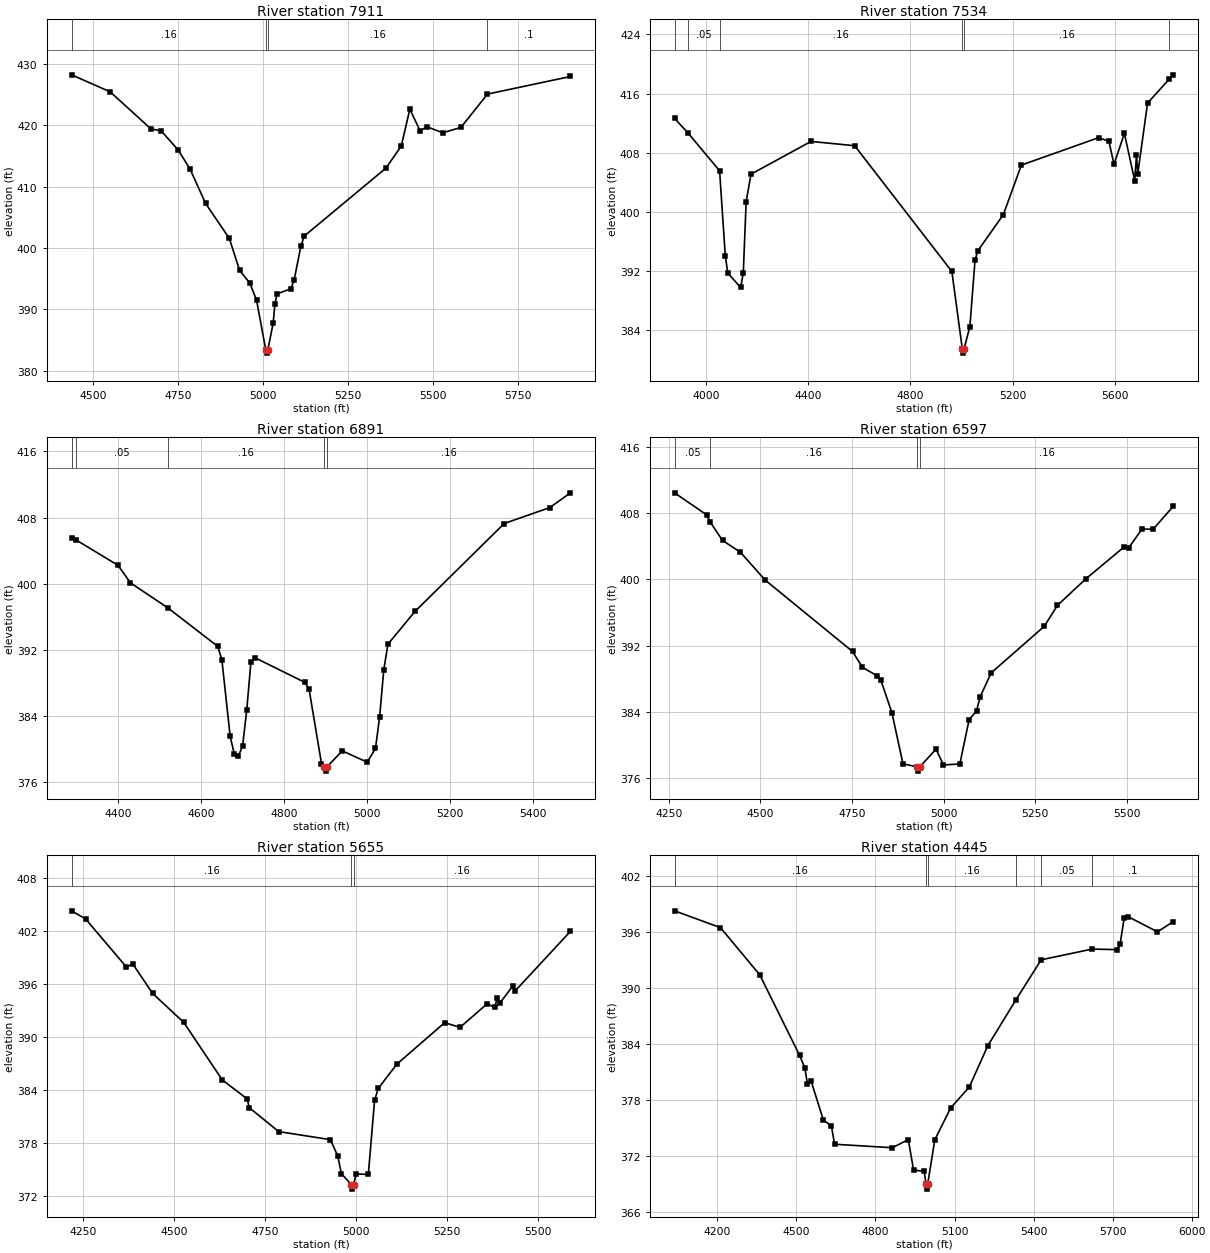
Type RM Length L Ch R = 1,7911,377,377,377
BEGIN DESCRIPTION:
WILLOW CREEK TRIB 4.3 15.0
END DESCRIPTION:
XS GIS Cut Line= 2
      3520728.92     10443014.62      3522193.77     10442896.60
#Sta/Elev= 30
  4435.6  428.20  4549.2  425.43  4669.5  419.38  4699.6  419.07  4749.8  415.92
  4784.5  412.85  4830.1  407.26  4900.3  401.53  4930.4  396.34  4960.5  394.27
  4980.5  391.48  5007.6  383.35  5010.4  382.85  5013.6  383.35  5029.4  387.76
  5034.4  390.79  5040.7  392.51  5080.9  393.32  5090.9  394.70  5111.0  400.27
  5121.0  401.93  5361.8  413.01  5406.8  416.61  5432.0  422.61  5462.1  419.08
  5482.2  419.73  5529.2  418.76  5582.5  419.63  5660.7  425.06  5905.2  427.93
#Mann=4,-1,0
  4435.6    0.16       0  5007.6    0.07       0  5013.6    0.16       0
  5660.7     0.1       0
Bank Sta=5007.6,5013.6
Exp/Cntr=0.3,0.1

Type RM Length L Ch R = 1,7534,643,643,643
BEGIN DESCRIPTION:
WILLOW CREEK TRIB 4.3 14.0
END DESCRIPTION:
XS GIS Cut Line= 2
      3520215.10     10443459.06      3522152.59     10443229.89
#Sta/Elev= 30
  3877.6  412.64  3929.3  410.70  4053.8  405.55  4076.0  394.04  4086.0  391.69
  4136.4  389.76  4146.5  391.78  4157.6  401.38  4176.7  405.09  4411.2  409.52
  4581.9  408.94  4962.1  391.93  5003.2  381.38  5005.9  380.88  5009.2  381.38
  5032.6  384.48  5052.7  393.44  5062.8  394.68  5163.5  399.62  5234.0  406.32
  5536.1  410.03  5576.4  409.54  5596.2  406.41  5636.8  410.61  5677.1  404.23
  5684.1  407.66  5689.1  405.14  5727.4  414.70  5811.1  417.91  5828.6  418.53
#Mann=6,-1,0
  3877.6     0.1       0  3929.3    0.05       0  4053.8    0.16       0
  5003.2    0.07       0  5009.2    0.16       0  5811.1     0.1       0
Bank Sta=5003.2,5009.2
Exp/Cntr=0.3,0.1

Type RM Length L Ch R = 1,6891,294,294,294
BEGIN DESCRIPTION:
WILLOW CREEK TRIB 4.3 13.0
END DESCRIPTION:
XS GIS Cut Line= 2
      3520680.36     10443847.95      3521881.74     10443889.62
#Sta/Elev= 30
  4288.4  405.52  4298.4  405.32  4400.2  402.23  4430.2  400.11  4520.5  397.08
  4640.4  392.44  4650.4  390.84  4670.4  381.58  4680.4  379.42  4690.4  379.21
  4700.4  380.39  4710.4  384.74  4720.4  390.49  4730.4  391.06  4850.5  388.08
  4860.5  387.28  4890.5  378.28  4897.5  377.86  4900.3  377.36  4903.5  377.86
  4940.5  379.81  5000.6  378.44  5020.6  380.10  5030.6  383.90  5040.6  389.61
  5050.6  392.70  5115.9  396.66  5330.8  407.28  5440.8  409.21  5490.5  410.99
#Mann=5,-1,0
  4288.4     0.1       0  4298.4    0.05       0  4520.5    0.16       0
  4897.5    0.07       0  4903.5    0.16       0
Bank Sta=4897.5,4903.5
Exp/Cntr=0.3,0.1

Type RM Length L Ch R = 1,6597,942,942,942
BEGIN DESCRIPTION:
WILLOW CREEK TRIB 4.3 12.0
END DESCRIPTION:
XS GIS Cut Line= 3
      3520520.62     10444195.18      3520992.85     10444091.01
      3521867.45     10444167.36
#Sta/Elev= 30
  4265.7  410.43  4353.0  407.78  4362.7  406.92  4396.7  404.68  4445.5  403.26
  4513.0  399.90  4751.4  391.28  4778.6  389.36  4818.9  388.34  4828.8  387.81
  4858.9  383.88  4889.1  377.73  4928.6  377.34  4931.4  376.84  4934.6  377.34
  4979.4  379.49  4999.5  377.59  5044.3  377.70  5069.7  383.07  5089.8  384.09
  5099.9  385.83  5130.0  388.71  5274.8  394.32  5310.7  396.85  5387.5  400.02
  5491.3  403.85  5505.2  403.79  5541.5  406.07  5571.6  406.02  5627.2  408.83
#Mann=4,-1,0
  4265.7    0.05       0  4362.7    0.16       0  4928.6    0.07       0
  4934.6    0.16       0
Bank Sta=4928.6,4934.6
Exp/Cntr=0.3,0.1

Type RM Length L Ch R = 1,5655,1210,1210,1210
BEGIN DESCRIPTION:
WILLOW CREEK TRIB 4.3 10.0
END DESCRIPTION:
XS GIS Cut Line= 4
      3520555.34     10444709.06      3520923.41     10444792.40
      3521603.96     10444688.23      3521818.17     10444474.02
#Sta/Elev= 30
  4219.4  404.32  4258.0  403.39  4369.9  397.94  4387.4  398.29  4441.6  394.96
  4527.1  391.67  4632.8  385.15  4701.3  382.99  4706.7  382.01  4787.7  379.29
  4929.3  378.38  4949.5  376.54  4959.7  374.52  4987.0  373.27  4989.8  372.77
  4993.0  373.27  5000.1  374.50  5033.5  374.43  5050.7  382.84  5060.8  384.19
  5111.4  386.92  5242.9  391.64  5285.3  391.11  5359.3  393.77  5380.5  393.39
  5387.6  394.47  5394.7  393.87  5430.0  395.81  5437.1  395.27  5588.2  402.00
#Mann=3,-1,0
  4219.4    0.16       0  4987.0    0.07       0  4993.0    0.16       0
Bank Sta=4987,4993
Exp/Cntr=0.3,0.1

Type RM Length L Ch R = 1,4445,827,827,827
BEGIN DESCRIPTION:
WILLOW CREEK TRIB 4.3 8.0
END DESCRIPTION:
XS GIS Cut Line= 4
      3520555.36     10445222.96      3520833.13     10445459.06
      3521673.41     10445556.29      3522354.01     10445611.84
#Sta/Elev= 30
  4037.5  398.30  4211.7  396.50  4361.1  391.43  4511.8  382.82  4531.9  381.47
  4542.0  379.73  4556.0  380.04  4602.4  375.86  4632.6  375.27  4644.8  373.28
  4864.1  372.91  4924.5  373.78  4944.6  370.52  4984.9  370.37  4992.0  368.97
  4994.8  368.47  4998.0  368.97  5025.2  373.76  5085.6  377.18  5156.0  379.41
  5226.5  383.85  5331.8  388.70  5428.9  393.05  5622.2  394.20  5718.2  394.14
  5728.2  394.70  5743.6  397.48  5758.3  397.68  5870.3  396.05  5930.8  397.15
#Mann=6,-1,0
  4037.5    0.16       0  4992.0    0.07       0  4998.0    0.16       0
  5331.8     0.1       0  5428.9    0.05       0  5622.2     0.1       0
Bank Sta=4992,4998
Exp/Cntr=0.3,0.1

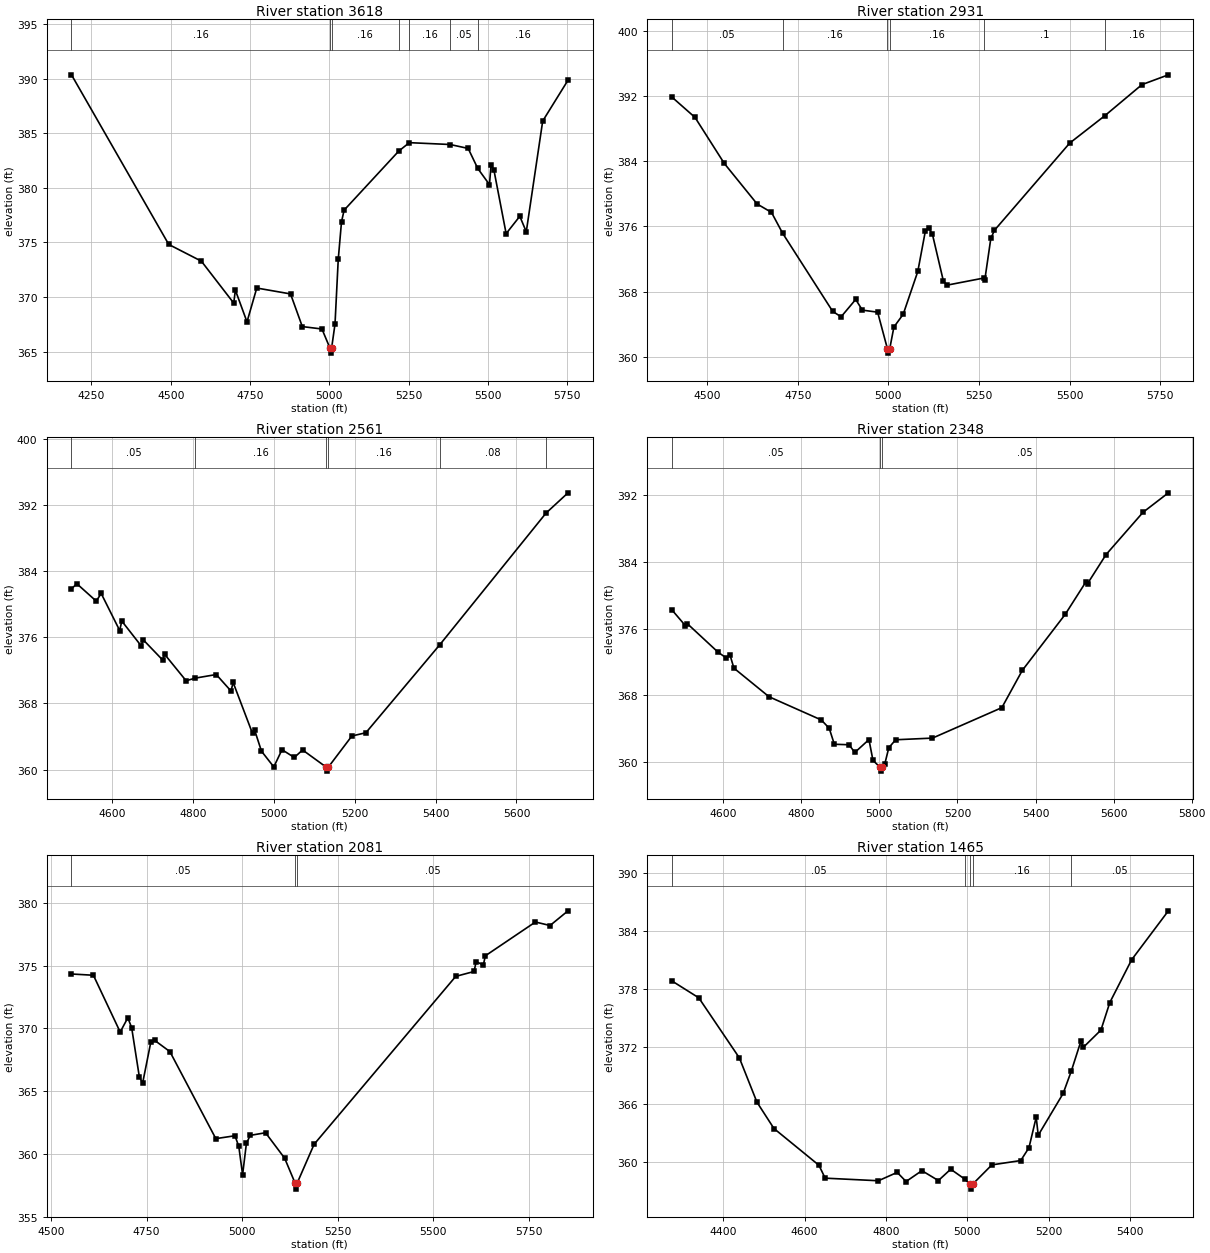
Type RM Length L Ch R = 1,3618,687,687,687
BEGIN DESCRIPTION:
WILLOW CREEK TRIB 4.3 7.0
END DESCRIPTION:
XS GIS Cut Line= 3
      3520763.68     10446125.73      3521847.02     10445868.79
      3522291.48     10445952.12
#Sta/Elev= 30
  4187.1  390.34  4493.8  374.81  4596.6  373.28  4698.7  369.44  4703.8  370.63
  4740.5  367.72  4771.3  370.82  4877.8  370.28  4914.9  367.29  4976.8  367.07
  5001.5  365.36  5004.2  364.86  5007.5  365.36  5018.0  367.52  5028.2  373.44
  5038.5  376.88  5046.7  377.95  5219.1  383.36  5252.4  384.13  5381.2  383.96
  5437.9  383.60  5468.1  381.77  5505.0  380.29  5510.1  382.10  5519.3  381.59
  5557.6  375.80  5600.7  377.39  5621.1  375.97  5672.9  386.11  5752.7  389.85
#Mann=7,-1,0
  4187.1    0.16       0  5001.5    0.07       0  5007.5    0.16       0
  5219.1     0.1       0  5252.4    0.16       0  5381.2    0.05       0
  5468.1    0.16       0
Bank Sta=5001.5,5007.5
Exp/Cntr=0.3,0.1

Type RM Length L Ch R = 1,2931,370,370,370
BEGIN DESCRIPTION:
WILLOW CREEK TRIB 4.3 6.0
END DESCRIPTION:
XS GIS Cut Line= 3
      3520888.66     10446570.18      3521978.96     10446438.23
      3522242.90     10446500.74
#Sta/Elev= 30
  4402.6  391.86  4466.5  389.36  4547.1  383.73  4637.8  378.75  4677.4  377.72
  4708.1  375.17  4846.2  365.59  4869.4  364.92  4909.7  367.05  4928.1  365.74
  4970.2  365.49  4997.4  360.97  5000.1  360.47  5003.4  360.97  5015.1  363.67
  5040.7  365.23  5081.0  370.48  5102.0  375.47  5111.2  375.79  5121.3  375.04
  5151.5  369.32  5161.5  368.80  5262.7  369.67  5265.8  369.45  5282.4  374.53
  5292.5  375.53  5499.9  386.21  5597.2  389.58  5699.3  393.38  5772.1  394.58
#Mann=6,-1,0
  4402.6    0.05       0  4708.1    0.16       0  4997.4    0.07       0
  5003.4    0.16       0  5262.7     0.1       0  5597.2    0.16       0
Bank Sta=4997.4,5003.4
Exp/Cntr=0.3,0.1

Type RM Length L Ch R = 1,2561,213,213,213
BEGIN DESCRIPTION:
WILLOW CREEK TRIB 4.3 5.0
END DESCRIPTION:
XS GIS Cut Line= 2
      3520999.79     10446938.23      3522208.12     10446716.01
#Sta/Elev= 30
  4498.9  381.85  4512.1  382.47  4560.1  380.37  4572.4  381.29  4618.2  376.81
  4623.3  377.96  4671.3  374.96  4676.4  375.69  4724.4  373.25  4729.4  373.93
  4782.5  370.74  4805.6  371.06  4857.1  371.49  4893.7  369.49  4898.8  370.54
  4946.8  364.37  4951.9  364.79  4969.0  362.22  4999.5  360.32  5019.8  362.40
  5050.3  361.46  5070.7  362.37  5128.7  360.31  5131.4  359.81  5134.7  360.31
  5192.7  364.06  5227.3  364.45  5410.2  375.09  5673.3  391.02  5727.5  393.46
#Mann=6,-1,0
  4498.9    0.05       0  4805.6    0.16       0  5128.7    0.07       0
  5134.7    0.16       0  5410.2    0.08       0  5673.3    0.16       0
Bank Sta=5128.7,5134.7
Exp/Cntr=0.3,0.1

Type RM Length L Ch R = 1,2348,267,267,267
BEGIN DESCRIPTION:
WILLOW CREEK TRIB 4.3 4.0
END DESCRIPTION:
XS GIS Cut Line= 2
      3520985.90     10447153.51      3522235.90     10446917.40
#Sta/Elev= 30
  4468.2  378.25  4502.6  376.36  4507.7  376.59  4586.5  373.16  4606.8  372.49
  4617.5  372.77  4627.2  371.24  4717.2  367.80  4851.1  365.01  4871.4  364.01
  4884.5  362.09  4922.3  362.03  4936.9  361.10  4973.2  362.65  4983.4  360.17
  5000.7  359.36  5003.5  358.86  5006.7  359.36  5013.9  359.75  5024.1  361.68
  5041.7  362.63  5136.0  362.83  5313.7  366.49  5366.1  370.97  5476.0  377.70
  5528.3  381.55  5533.4  381.41  5580.7  384.89  5675.4  389.97  5740.3  392.31
#Mann=3,-1,0
  4468.2    0.05       0  5000.7    0.04       0  5006.7    0.05       0
Bank Sta=5000.7,5006.7
Exp/Cntr=0.3,0.1

Type RM Length L Ch R = 1,2081,616,616,616
BEGIN DESCRIPTION:
WILLOW CREEK TRIB 4.3 3.0
END DESCRIPTION:
XS GIS Cut Line= 3
      3521124.84     10447292.40      3522055.35     10447313.23
      3522395.65     10447174.33
#Sta/Elev= 30
  4553.6  374.33  4610.9  374.23  4680.9  369.71  4700.9  370.84  4710.9  370.06
  4730.9  366.16  4739.6  365.64  4760.9  368.89  4770.9  369.05  4810.9  368.15
  4931.0  361.22  4981.0  361.45  4991.0  360.61  5001.0  358.35  5011.0  360.85
  5021.0  361.48  5061.0  361.69  5111.0  359.66  5138.0  357.70  5140.8  357.20
  5144.0  357.70  5188.0  360.77  5558.3  374.14  5606.3  374.53  5611.7  375.32
  5630.4  375.04  5635.8  375.78  5766.7  378.47  5804.9  378.19  5851.9  379.36
#Mann=3,-1,0
  4553.6    0.05       0  5138.0   0.035       0  5144.0    0.05       0
Bank Sta=5138,5144
Exp/Cntr=0.3,0.1

Type RM Length L Ch R = 1,1465,400,400,400
BEGIN DESCRIPTION:
WILLOW CREEK TRIB 4.3 2.0
END DESCRIPTION:
XS GIS Cut Line= 4
      3521270.62     10447486.82      3521353.96     10447681.29
      3522069.24     10447792.40      3522318.17     10447654.10
#Sta/Elev= 30
  4274.0  378.82  4340.2  377.06  4439.9  370.82  4483.1  366.22  4524.9  363.48
  4635.5  359.66  4650.7  358.32  4781.6  358.05  4827.8  358.92  4849.6  357.97
  4888.5  359.10  4929.0  358.07  4959.3  359.25  4993.9  358.22  5006.9  357.68
  5009.7  357.18  5012.9  357.68  5060.5  359.70  5131.4  360.15  5151.6  361.48
  5169.4  364.65  5174.4  362.78  5235.6  367.12  5255.7  369.45  5279.3  372.56
  5285.1  371.91  5328.5  373.71  5350.3  376.57  5404.0  381.02  5494.2  386.10
#Mann=5,-1,0
  4274.0    0.05       0  4993.9    0.16       0  5006.9    0.07       0
  5012.9    0.16       0  5255.7    0.05       0
Bank Sta=5006.9,5012.9
Exp/Cntr=0.3,0.1

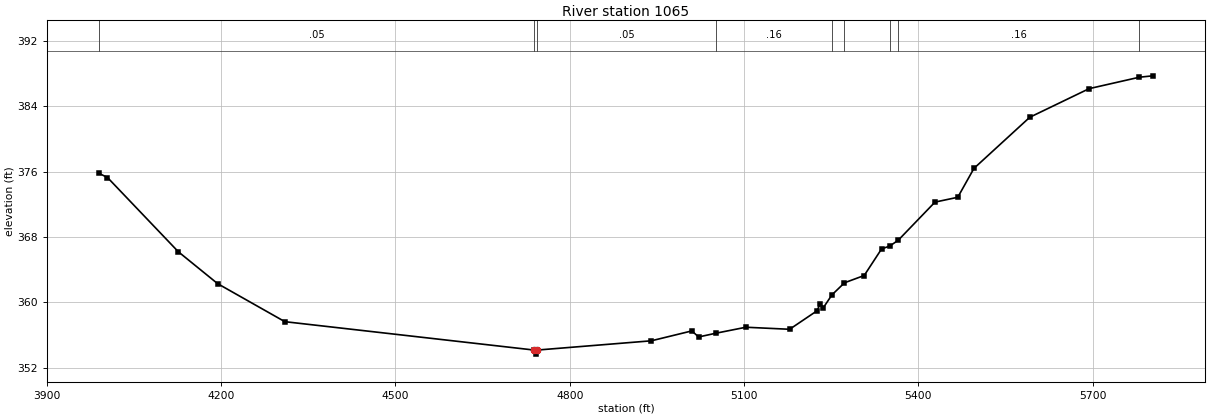
Type RM Length L Ch R = 1,1065,0,0,0
BEGIN DESCRIPTION:
WILLOW CREEK TRIB 4.3 1.0
END DESCRIPTION:
XS GIS Cut Line= 4
      3520798.37     10447959.06      3522138.69     10448209.06
      3522347.02     10448104.90      3522367.85     10447889.66
#Sta/Elev= 30
  3990.6  375.76  4004.6  375.27  4126.6  366.18  4194.2  362.28  4309.8  357.63
  4738.5  354.16  4741.3  353.66  4744.5  354.16  4940.4  355.29  5010.1  356.50
  5021.8  355.76  5051.6  356.22  5103.2  356.95  5178.4  356.70  5225.3  358.95
  5231.1  359.82  5236.1  359.31  5251.2  360.91  5272.8  362.39  5306.7  363.28
  5336.5  366.52  5351.0  366.90  5365.2  367.59  5428.5  372.26  5467.7  372.85
  5495.6  376.39  5591.6  382.64  5693.7  386.14  5780.2  387.54  5803.2  387.71
#Mann=9,-1,0
  3990.6    0.05       0  4738.5    0.03       0  4744.5    0.05       0
  5051.6    0.16       0  5251.2    0.05       0  5272.8    0.16       0
  5351.0    0.05       0  5365.2    0.16       0  5780.2    0.05       0
Bank Sta=4738.5,4744.5
Exp/Cntr=0.3,0.1

Chan Stop Cuts=-1