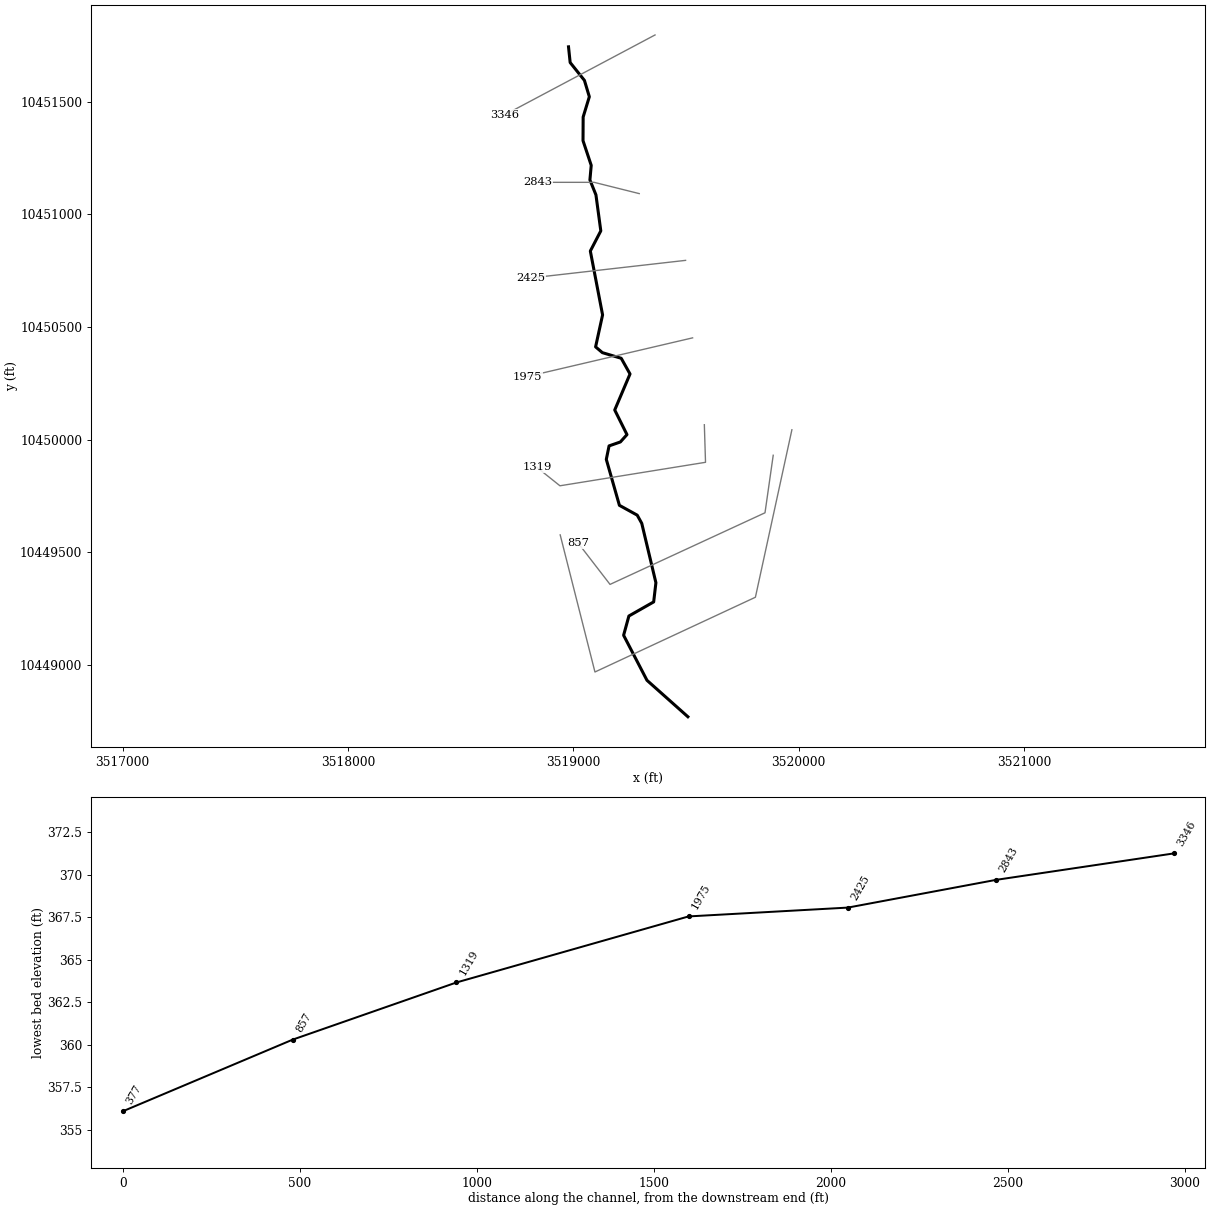
--- WILLOW CREEK TRIB 7.prj (project) ---

Proj Title=WILLOW CREEK TRIB 7 Base Level Engineering
Current Plan=p01
Default Exp/Contr=0.3,0.1
English Units
Geom File=g01
Flow File=f01
Plan File=p01
BEGIN DESCRIPTION:
WILLOW CREEK TRIB 7
END DESCRIPTION:

--- WILLOW CREEK TRIB 7.p01 (plan) ---

Plan Title=Multiple Run
Short Identifier=Multiple
Geom File=g01
Flow File=f01
Subcritical Flow
K Sum by GR= 0
Std Step Tol= 0.01
Critical Tol= 0.01
Num of Std Step Trials= 20
Max Error Tol= 0.3
Flow Tol Ratio= 0.001
Split Flow NTrial= 30
Split Flow Tol= 0.02
Split Flow Ratio= 0.02
Log Output Level= 0
Friction Slope Method= 1
Unsteady Friction Slope Method= 2
Unsteady Bridges Friction Slope Method= 1
Parabolic Critical Depth
Global Vel Dist=  1 , 1 , 1
Global Log Level= 0
CheckData=True
Encroach Param= -1, 0, 0, 0
BEGIN DESCRIPTION:
Multiple Run
END DESCRIPTION:

--- WILLOW CREEK TRIB 7.f01 (steady flow) ---

Flow Title=Multiple
Number of Profiles=7
Profile Names=10-year,25-year,50-year,1pct_min,100-year,1pct_plu,500-year
River Rch & RM= WILLOW CREEK TRI,Reach-1,3346
     444     584     694     604     817    1105    1127
Boundary for River Rch & Prof#=WILLOW CREEK TRI,Reach-1,1
Up Type=0
Dn Type=3
Dn Slope=0.005
Boundary for River Rch & Prof#=WILLOW CREEK TRI,Reach-1,2
Up Type=0
Dn Type=3
Dn Slope=0.005
Boundary for River Rch & Prof#=WILLOW CREEK TRI,Reach-1,3
Up Type=0
Dn Type=3
Dn Slope=0.005
Boundary for River Rch & Prof#=WILLOW CREEK TRI,Reach-1,4
Up Type=0
Dn Type=3
Dn Slope=0.005
Boundary for River Rch & Prof#=WILLOW CREEK TRI,Reach-1,5
Up Type=0
Dn Type=3
Dn Slope=0.005
Boundary for River Rch & Prof#=WILLOW CREEK TRI,Reach-1,6
Up Type=0
Dn Type=3
Dn Slope=0.005
Boundary for River Rch & Prof#=WILLOW CREEK TRI,Reach-1,7
Up Type=0
Dn Type=3
Dn Slope=0.005

--- WILLOW CREEK TRIB 7.g01 (geometry) ---

Geom Title=Existing Conditions

River Reach=WILLOW CREEK TRI,Reach-1
Reach XY= 30
      3518978.39     10451742.74      3518985.70     10451673.13
      3519048.99     10451593.86      3519070.74     10451521.32
      3519043.34     10451431.51      3519042.73     10451326.36
      3519079.11     10451216.99      3519073.31     10451152.22
      3519100.04     10451086.02      3519121.61     10450926.28
      3519075.17     10450836.86      3519129.52     10450553.49
      3519098.52     10450411.66      3519128.68     10450386.05
      3519212.21     10450361.08      3519251.23     10450291.40
      3519183.42     10450131.66      3519237.72     10450022.47
      3519208.52     10449989.91      3519158.30     10449972.38
      3519146.02     10449912.60      3519204.17     10449708.72
      3519283.19     10449665.15      3519303.31     10449628.83
      3519366.06     10449365.47      3519356.19     10449280.28
      3519246.25     10449217.75      3519222.79     10449132.25
      3519326.44     10448932.46      3519507.96     10448770.80

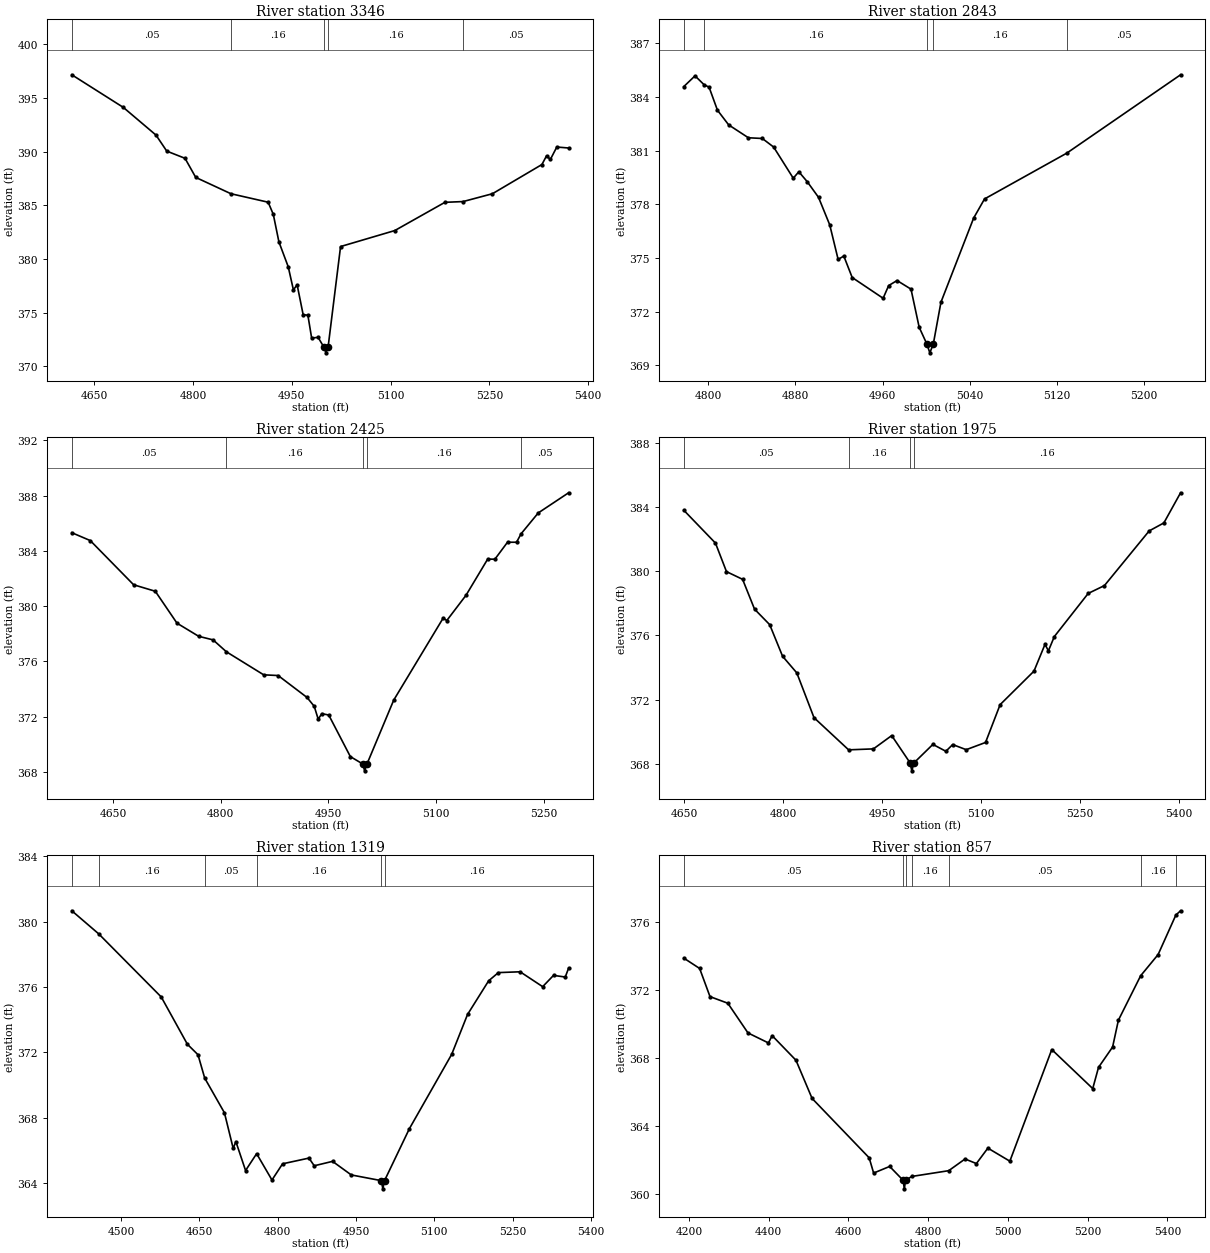
Type RM Length L Ch R = 1,3346,503,503,503
BEGIN DESCRIPTION:
WILLOW CREEK TRIB 7 7.0
END DESCRIPTION:
XS GIS Cut Line= 2
      3519362.21     10451795.43      3518696.34     10451441.69
#Sta/Elev= 30
  4616.2  397.16  4694.4  394.12  4744.0  391.54  4760.3  390.05  4788.0  389.38
  4804.3  387.60  4857.7  386.08  4914.2  385.29  4922.0  384.16  4930.5  381.60
  4944.7  379.27  4952.5  377.13  4958.2  377.59  4967.3  374.82  4974.5  374.76
  4980.2  372.64  4990.0  372.70  4999.1  371.76  5001.9  371.26  5005.1  371.76
  5024.1  381.16  5106.4  382.65  5182.5  385.28  5210.0  385.35  5254.6  386.08
  5329.7  388.80  5336.8  389.62  5342.5  389.27  5352.3  390.43  5370.2  390.34
#Mann=5,-1,0
  4616.2    0.05       0  4857.7    0.16       0  4999.1    0.07       0
  5005.1    0.16       0  5210.0    0.05       0
Bank Sta=4999.1,5005.1
Exp/Cntr=0.3,0.1

Type RM Length L Ch R = 1,2843,418,418,418
BEGIN DESCRIPTION:
WILLOW CREEK TRIB 7 6.0
END DESCRIPTION:
XS GIS Cut Line= 3
      3519292.10     10451091.64      3519092.11     10451141.64
      3518842.15     10451141.64
#Sta/Elev= 30
  4777.5  384.58  4787.8  385.18  4796.2  384.68  4800.7  384.55  4808.4  383.26
  4818.7  382.44  4836.8  381.72  4849.6  381.68  4860.0  381.20  4878.0  379.46
  4883.1  379.82  4890.9  379.26  4901.2  378.39  4911.5  376.85  4919.2  374.92
  4924.4  375.11  4932.1  373.91  4960.5  372.75  4965.6  373.46  4973.3  373.74
  4986.1  373.26  4993.6  371.13  5000.6  370.20  5003.4  369.70  5006.6  370.20
  5013.6  372.53  5043.6  377.23  5053.6  378.30  5129.1  380.86  5233.6  385.24
#Mann=5,-1,0
  4777.5    0.05       0  4796.2    0.16       0  5000.6    0.07       0
  5006.6    0.16       0  5129.1    0.05       0
Bank Sta=5000.6,5006.6
Exp/Cntr=0.3,0.1

Type RM Length L Ch R = 1,2425,450,450,450
BEGIN DESCRIPTION:
WILLOW CREEK TRIB 7 5.0
END DESCRIPTION:
XS GIS Cut Line= 2
      3519497.67     10450795.44      3518810.10     10450717.31
#Sta/Elev= 30
  4592.5  385.31  4618.2  384.74  4678.6  381.54  4708.8  381.07  4739.0  378.76
  4769.2  377.81  4789.3  377.55  4807.8  376.69  4859.8  375.02  4879.9  374.97
  4920.2  373.38  4930.2  372.74  4935.7  371.81  4940.7  372.21  4950.4  372.11
  4980.5  369.10  4997.7  368.57  5000.4  368.07  5003.7  368.57  5040.9  373.19
  5109.8  379.13  5114.8  378.95  5141.6  380.78  5171.8  383.40  5181.8  383.39
  5199.4  384.62  5212.0  384.62  5218.3  385.23  5242.2  386.74  5284.5  388.20
#Mann=5,-1,0
  4592.5    0.05       0  4807.8    0.16       0  4997.7    0.07       0
  5003.7    0.16       0  5218.3    0.05       0
Bank Sta=4997.7,5003.7
Exp/Cntr=0.3,0.1

Type RM Length L Ch R = 1,1975,656,656,656
BEGIN DESCRIPTION:
WILLOW CREEK TRIB 7 4.0
END DESCRIPTION:
XS GIS Cut Line= 2
      3519528.89     10450451.69      3518795.80     10450280.11
#Sta/Elev= 30
  4649.4  383.81  4697.4  381.76  4714.1  379.98  4738.5  379.50  4756.6  377.64
  4779.6  376.67  4799.1  374.70  4820.7  373.66  4846.7  370.87  4899.2  368.86
  4936.8  368.92  4964.5  369.75  4992.3  368.05  4995.0  367.55  4998.3  368.05
  5026.9  369.20  5046.6  368.77  5056.9  369.19  5077.4  368.87  5106.7  369.32
  5128.8  371.68  5180.1  373.77  5196.8  375.44  5202.0  375.04  5211.0  375.93
  5262.3  378.62  5286.9  379.11  5354.7  382.52  5377.0  383.02  5402.3  384.90
#Mann=4,-1,0
  4649.4    0.05       0  4899.2    0.16       0  4992.3    0.07       0
  4998.3    0.16       0
Bank Sta=4992.3,4998.3
Exp/Cntr=0.3,0.1

Type RM Length L Ch R = 1,1319,462,462,462
BEGIN DESCRIPTION:
WILLOW CREEK TRIB 7 2.0
END DESCRIPTION:
XS GIS Cut Line= 4
      3519580.96     10450066.31      3519586.17     10449899.60
      3518940.34     10449795.43      3518837.94     10449877.35
#Sta/Elev= 30
  4405.4  380.66  4456.9  379.25  4576.8  375.39  4626.9  372.50  4647.2  371.86
  4660.1  370.43  4697.9  368.31  4714.7  366.13  4719.8  366.55  4738.4  364.78
  4759.6  365.81  4789.0  364.20  4809.3  365.19  4859.9  365.54  4870.0  365.07
  4905.1  365.34  4941.0  364.51  4998.7  364.16  5001.5  363.66  5004.7  364.16
  5052.4  367.34  5133.4  371.88  5163.8  374.32  5204.3  376.38  5222.9  376.88
  5264.6  376.93  5307.8  376.02  5328.6  376.71  5351.1  376.61  5357.5  377.15
#Mann=6,-1,0
  4405.4    0.05       0  4456.9    0.16       0  4660.1    0.05       0
  4759.6    0.16       0  4998.7    0.07       0  5004.7    0.16       0
Bank Sta=4998.7,5004.7
Exp/Cntr=0.3,0.1

Type RM Length L Ch R = 1,857,480,480,480
BEGIN DESCRIPTION:
WILLOW CREEK TRIB 7 1.1
END DESCRIPTION:
XS GIS Cut Line= 4
      3519886.52     10449930.90      3519850.06     10449675.64
      3519162.56     10449357.93      3519021.96     10449540.20
#Sta/Elev= 30
  4187.4  373.90  4227.1  373.29  4253.1  371.63  4297.8  371.24  4348.3  369.49
  4399.6  368.90  4408.9  369.33  4468.6  367.88  4509.0  365.63  4652.1  362.13
  4663.3  361.23  4703.5  361.62  4737.4  360.80  4740.2  360.30  4743.4  360.80
  4758.8  361.03  4851.5  361.37  4892.5  362.06  4920.9  361.79  4949.7  362.70
  5004.8  361.93  5109.9  368.51  5212.6  366.21  5227.1  367.46  5262.4  368.66
  5276.9  370.24  5332.7  372.86  5376.5  374.11  5421.0  376.44  5432.8  376.69
#Mann=7,-1,0
  4187.4    0.05       0  4737.4    0.03       0  4743.4    0.05       0
  4758.8    0.16       0  4851.5    0.05       0  5332.7    0.16       0
  5421.0    0.05       0
Bank Sta=4737.4,4743.4
Exp/Cntr=0.3,0.1

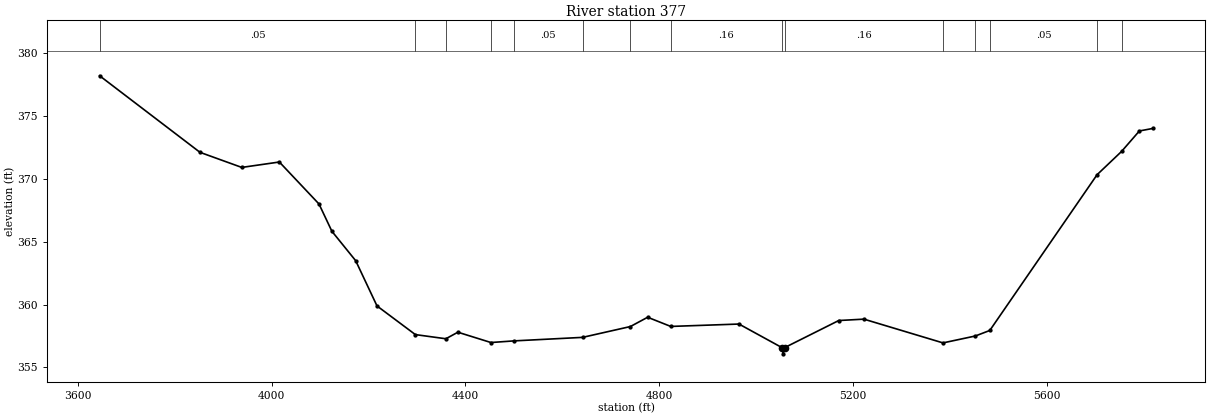
Type RM Length L Ch R = 1,377,0,0,0
BEGIN DESCRIPTION:
WILLOW CREEK TRIB 7 1.0
END DESCRIPTION:
XS GIS Cut Line= 4
      3519969.36     10450043.99      3519807.48     10449300.98
      3519095.67     10448969.38      3518941.42     10449577.74
#Sta/Elev= 30
  3645.0  378.20  3852.1  372.11  3938.3  370.91  4015.9  371.34  4097.7  368.00
  4124.3  365.83  4173.4  363.49  4217.4  359.89  4296.6  357.61  4359.5  357.28
  4384.3  357.80  4452.5  356.98  4500.0  357.11  4641.6  357.39  4740.2  358.25
  4775.9  358.99  4823.6  358.26  4964.4  358.45  5052.9  356.58  5055.7  356.08
  5058.9  356.58  5170.3  358.73  5222.2  358.84  5385.4  356.95  5452.2  357.50
  5482.0  357.94  5703.4  370.33  5753.9  372.18  5790.7  373.81  5818.3  374.01
#Mann=15,-1,0
  3645.0    0.05       0  4296.6     0.1       0  4359.5    0.16       0
  4452.5     0.1       0  4500.0    0.05       0  4641.6    0.16       0
  4740.2    0.05       0  4823.6    0.16       0  5052.9    0.07       0
  5058.9    0.16       0  5385.4    0.05       0  5452.2    0.16       0
  5482.0    0.05       0  5703.4    0.16       0  5753.9    0.05       0
Bank Sta=5052.9,5058.9
Exp/Cntr=0.3,0.1

Chan Stop Cuts=-1