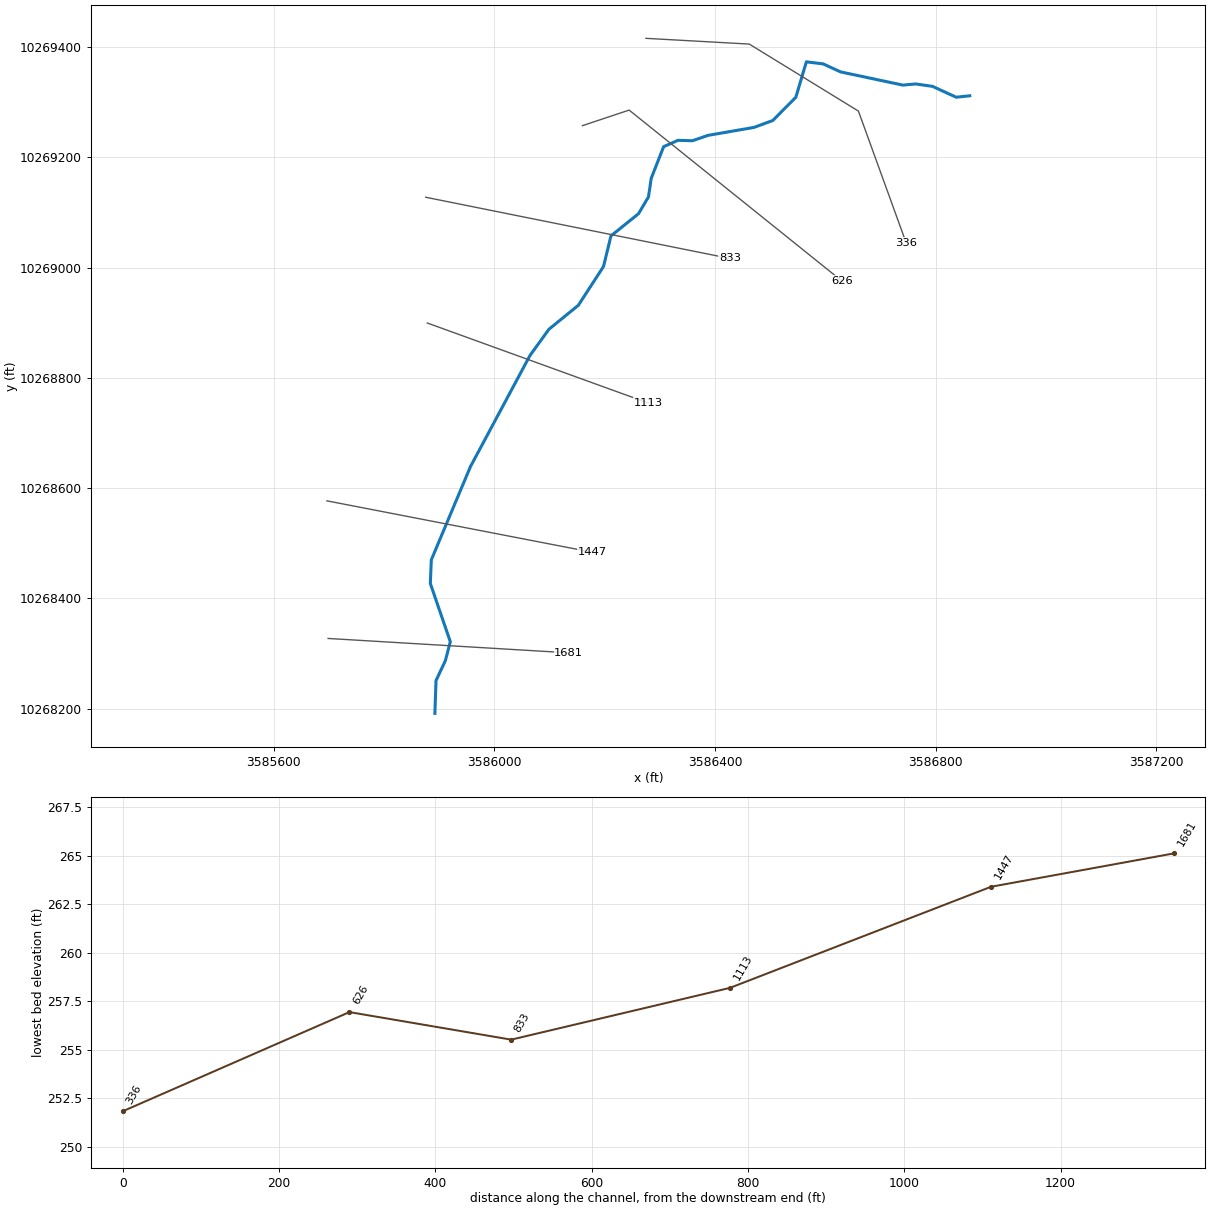
--- ALLCORNCRTRIB11.prj (project) ---

Proj Title=ALLCORN CREEK TRIB 11
Current Plan=p01
Default Exp/Contr=0.3,0.1
English Units
Geom File=g01
Flow File=f01
Plan File=p01
Y Axis Title=Elevation
X Axis Title(PF)=Main Channel Distance
X Axis Title(XS)=Station
BEGIN DESCRIPTION:
UNT04909 IN WICK
END DESCRIPTION:
DSS Export Rating Curves= 0
DSS Export Rating Curve Sorted= 0
DSS Export Volume Flow Curves= 0
DXF OffsetX= 0
DXF OffsetY= 0
DXF ScaleX= 1
DXF ScaleY= 10

--- ALLCORNCRTRIB11.p01 (plan) ---

Plan Title=Multiple Run
Short Identifier=Multiple
Geom File=g01
Flow File=f01
Subcritical Flow
K Sum by GR= 0
Std Step Tol= 0.01
Critical Tol= 0.01
Num of Std Step Trials= 20
Max Error Tol= 0.3
Flow Tol Ratio= 0.001
Split Flow NTrial= 30
Split Flow Tol= 0.02
Split Flow Ratio= 0.02
Log Output Level= 0
Friction Slope Method= 1
Unsteady Friction Slope Method= 2
Unsteady Bridges Friction Slope Method= 1
Parabolic Critical Depth
Global Vel Dist=  1 , 1 , 1
Global Log Level= 0
CheckData=True
Encroach Param= -1, 0, 0, 0
BEGIN DESCRIPTION:
Multiple Run
END DESCRIPTION:

--- ALLCORNCRTRIB11.f01 (steady flow) ---

Flow Title=Multiple
Program Version=4.10
Number of Profiles= 7
Profile Names=10-year,25-year,50-year,1pct_min,100-year,1pct_plu,500-year
River Rch & RM=UNT04909 IN WICK,Reach-1         ,1681
     156     193     220     186     252     340     327
River Rch & RM=ALLCORNCRTRIB11,Reach-1         ,1681
     156     193     220     186     252     340     327
Boundary for River Rch & Prof#=ALLCORNCRTRIB11,Reach-1         , 1
Up Type= 0
Dn Type= 3
Dn Slope=0.005
Boundary for River Rch & Prof#=ALLCORNCRTRIB11,Reach-1         , 2
Up Type= 0
Dn Type= 3
Dn Slope=0.005
Boundary for River Rch & Prof#=ALLCORNCRTRIB11,Reach-1         , 3
Up Type= 0
Dn Type= 3
Dn Slope=0.005
Boundary for River Rch & Prof#=ALLCORNCRTRIB11,Reach-1         , 4
Up Type= 0
Dn Type= 3
Dn Slope=0.005
Boundary for River Rch & Prof#=ALLCORNCRTRIB11,Reach-1         , 5
Up Type= 0
Dn Type= 3
Dn Slope=0.005
Boundary for River Rch & Prof#=ALLCORNCRTRIB11,Reach-1         , 6
Up Type= 0
Dn Type= 3
Dn Slope=0.005
Boundary for River Rch & Prof#=ALLCORNCRTRIB11,Reach-1         , 7
Up Type= 0
Dn Type= 3
Dn Slope=0.005
DSS Import GetInterval= 0
DSS Import GetPeak= 0
DSS Import FillOption= 0

--- ALLCORNCRTRIB11.g01 (geometry) ---

Geom Title=Existing Conditions
Program Version=4.10

River Reach=ALLCORNCRTRIB11 ,Reach-1
Reach XY= 30
      3585892.11     10268191.64      3585894.13     10268251.09
      3585911.16     10268287.34      3585920.06     10268321.58
      3585883.85     10268427.18      3585885.58       10268470.
      3585956.62     10268639.21      3586064.52     10268840.67
      3586098.91     10268888.24      3586152.22     10268931.68
      3586197.89     10269002.05      3586211.43      10269057.6
      3586261.43     10269097.88      3586279.49     10269128.44
      3586284.35     10269161.77      3586306.92     10269219.41
      3586332.96     10269230.87      3586359.18     10269230.15
      3586387.49     10269239.88      3586471.02     10269254.36
      3586504.89     10269266.86      3586546.69       10269309.
      3586565.77     10269373.23      3586596.39     10269369.46
      3586627.75       10269355.      3586740.77     10269331.04
      3586764.21     10269333.13      3586794.52     10269328.78
      3586837.46     10269309.09      3586862.11     10269311.64

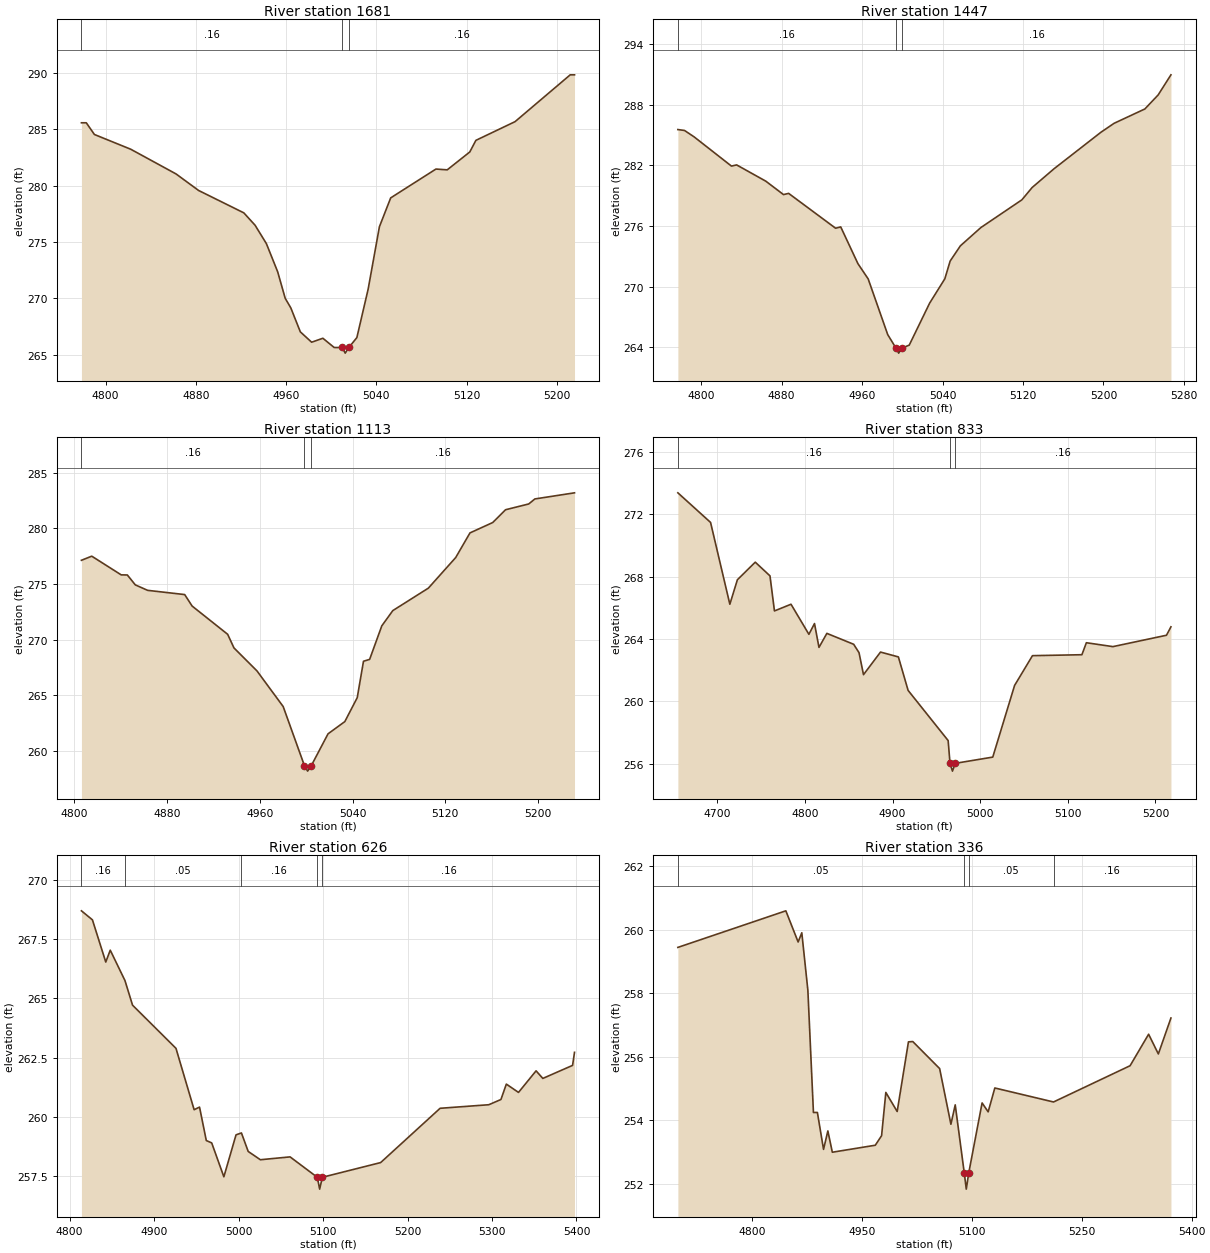
Type RM Length L Ch R = 1 ,1681    ,234,234,234
BEGIN DESCRIPTION:
UNT04909 IN WICK 3.0
END DESCRIPTION:
XS GIS Cut Line= 2
      3585698.48      10268327.5       3586134.7     10268301.46
#Sta/Elev= 30
  4778.6  285.59  4782.9  285.59  4790.1  284.55  4822.3  283.24  4862.4  281.05
  4882.4  279.58  4922.5  277.59  4932.5  276.49  4942.5  274.86  4952.5  272.36
  4959.2     270  4964.2  269.14  4972.6  267.02  4982.6   266.1  4992.6  266.45
  5002.6  265.63  5009.6  265.63  5012.4  265.13  5015.6  265.63  5022.7  266.51
  5032.7  270.81  5042.7  276.36  5052.7  278.92  5092.8  281.48  5102.8  281.41
  5122.8     283  5128.2  284.03  5162.9  285.69  5211.8  289.85  5215.6  289.85
#Mann= 3 ,-1 , 0
  4778.6     .16       0  5009.6     .07       0  5015.6     .16       0
Bank Sta=5009.6,5015.6
XS Rating Curve= 0 ,0
Exp/Cntr=0.3,0.1

Type RM Length L Ch R = 1 ,1447    ,334,334,334
BEGIN DESCRIPTION:
Mapping XS 856fd25e
END DESCRIPTION:
XS GIS Cut Line= 2
      3585696.32     10268577.07      3586177.58     10268483.86
#Sta/Elev= 30
  4776.9  285.55  4783.5  285.46    4793  284.83  4830.2  281.93  4835.3  282.05
  4864.3  280.44  4881.9  279.11    4887  279.23  4933.7  275.78  4938.8  275.91
  4955.9  272.27  4966.1  270.76  4985.5  265.25  4993.7  263.91  4996.4  263.41
  4999.7  263.91  5006.9   264.2  5027.2  268.36  5042.3  270.77  5047.6  272.53
  5057.8  274.04  5078.2  275.85  5118.9  278.59  5129.1  279.81  5150.9  281.67
  5197.6  285.29  5210.6  286.17  5241.2  287.59  5254.4  288.98  5267.1  290.97
#Mann= 3 ,-1 , 0
  4776.9     .16       0  4993.7     .07       0  4999.7     .16       0
Bank Sta=4993.7,4999.7
XS Rating Curve= 0 ,0
Exp/Cntr=0.3,0.1

Type RM Length L Ch R = 1 ,1113    ,280,280,280
BEGIN DESCRIPTION:
UNT04909 IN WICK 2.0
END DESCRIPTION:
XS GIS Cut Line= 2
      3585878.37     10268899.57      3586278.44     10268754.68
#Sta/Elev= 30
    4806  277.14  4814.9  277.51  4840.3  275.83  4845.6  275.82  4852.5  274.93
  4863.1  274.44  4895.1  274.06  4901.5  273.03  4932.2  270.49  4937.6  269.27
  4957.5   267.2  4980.1     264  4998.4   258.7  5001.2   258.2  5004.4   258.7
  5018.8  261.55  5033.3  262.65    5044   264.8  5049.4  268.07  5054.7  268.24
  5065.2  271.25  5074.7  272.62  5105.4  274.64    5129  277.39  5141.3   279.6
  5160.9  280.53    5172  281.68    5192   282.2  5197.3  282.65  5231.5   283.2
#Mann= 3 ,-1 , 0
    4806     .16       0  4998.4     .07       0  5004.4     .16       0
Bank Sta=4998.4,5004.4
XS Rating Curve= 0 ,0
Exp/Cntr=0.3,0.1

Type RM Length L Ch R = 1 ,833     ,207,207,207
BEGIN DESCRIPTION:
Mapping XS 1ffe607b
END DESCRIPTION:
XS GIS Cut Line= 2
       3585875.5     10269127.65      3586427.04     10269016.65
#Sta/Elev= 30
  4655.1  273.39  4692.4  271.49  4714.4  266.24    4723  267.81  4743.4  268.94
  4760.2  268.06  4765.3  265.81  4784.2  266.24  4804.6  264.31    4811     265
  4816.1  263.47  4825.1  264.37  4855.7  263.67  4861.8  263.13  4866.9  261.72
  4886.3  263.17  4906.7  262.86  4917.8  260.71  4963.5  257.49  4965.6  256.03
  4968.4  255.53  4971.6  256.03  5014.4  256.43  5039.3  261.03  5059.7  262.94
  5116.1     263  5121.2  263.77  5151.5  263.52  5212.6  264.25  5217.7  264.79
#Mann= 3 ,-1 , 0
  4655.1     .16       0  4965.6     .07       0  4971.6     .16       0
Bank Sta=4965.6,4971.6
XS Rating Curve= 0 ,0
Exp/Cntr=0.3,0.1

Type RM Length L Ch R = 1 ,626     ,290,290,290
BEGIN DESCRIPTION:
Mapping XS 7de1b43d
END DESCRIPTION:
XS GIS Cut Line= 3
      3586159.76     10269257.52      3586244.38     10269285.73
      3586629.88     10268976.02
#Sta/Elev= 30
    4814  268.69    4827  268.31  4842.8  266.53  4848.1  267.03  4865.5  265.75
  4874.5  264.71  4925.9  262.89  4947.4   260.3  4953.8  260.41  4961.8     259
  4968.2   258.9  4982.6  257.47    4997  259.24  5003.4  259.32  5011.4  258.54
  5025.8  258.19    5061  258.31  5093.2  257.45    5096  256.95  5099.2  257.45
  5168.2  258.07  5238.6  260.36  5296.2  260.51  5310.6  260.73    5317  261.38
  5331.4  261.03  5352.2  261.94  5360.2  261.62  5395.4  262.17  5397.7  262.72
#Mann= 5 ,-1 , 0
    4814     .16       0  4865.5     .05       0  5003.4     .16       0
  5093.2     .03       0  5099.2     .16       0
Bank Sta=5093.2,5099.2
XS Rating Curve= 0 ,0
Exp/Cntr=0.3,0.1

Type RM Length L Ch R = 1 ,336     ,0,0,0
BEGIN DESCRIPTION:
UNT04909 IN WICK 1.0
END DESCRIPTION:
XS GIS Cut Line= 4
      3586274.81     10269415.85      3586462.26     10269405.43
      3586660.18     10269283.91      3586746.57     10269045.47
#Sta/Elev= 30
  4698.1  259.44  4845.6  260.59  4862.4  259.61  4867.4   259.9  4875.7  258.09
  4883.3  254.25  4888.7  254.25  4897.1  253.09    4903  253.67  4909.1     253
  4967.8  253.22  4976.4  253.52  4982.2  254.88  4997.7  254.28  5013.1  256.47
    5019  256.48  5055.7  255.63  5071.1  253.88    5077  254.49  5089.4  252.34
  5092.1  251.84  5095.4  252.34  5113.7  254.55    5122  254.27  5131.1  255.02
  5211.3  254.58  5315.9  255.72  5341.2  256.71  5354.5  256.09  5371.7  257.22
#Mann= 4 ,-1 , 0
  4698.1     .05       0  5089.4     .03       0  5095.4     .05       0
  5211.3     .16       0
Bank Sta=5089.4,5095.4
XS Rating Curve= 0 ,0
Exp/Cntr=0.3,0.1

Chan Stop Cuts=-1
Use User Specified Reach Order=0
Composite Channel Slope=5