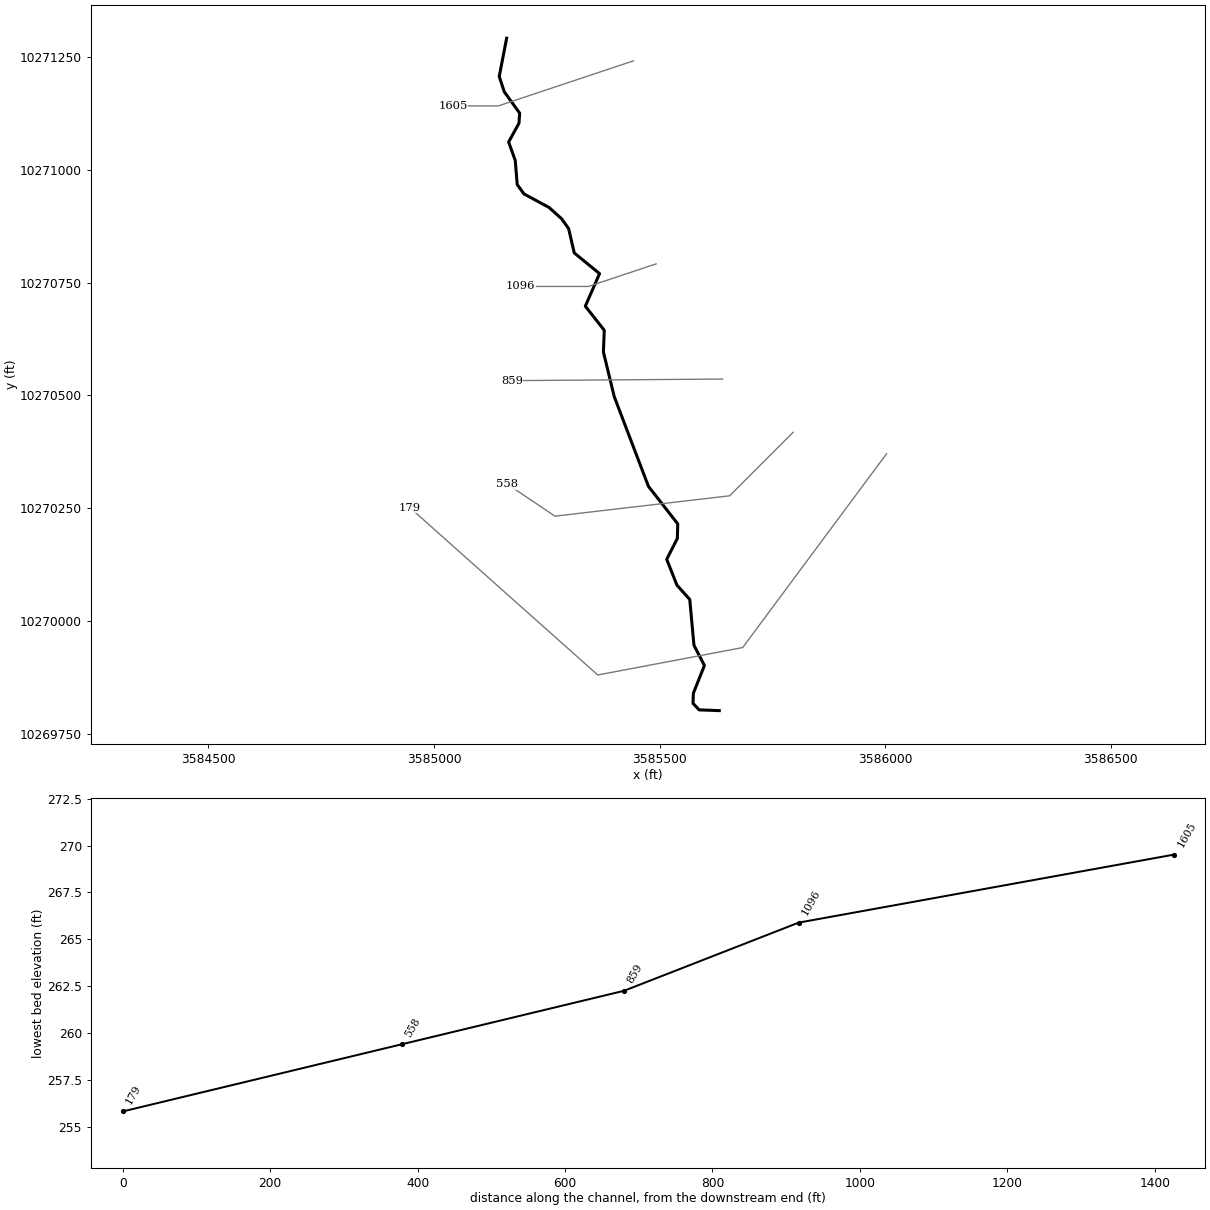
--- ALLCORNCRTRIB12.prj (project) ---

Proj Title=ALLCORN CREEK TRIB 12
Current Plan=p01
Default Exp/Contr=0.3,0.1
English Units
Geom File=g01
Flow File=f01
Plan File=p01
Y Axis Title=Elevation
X Axis Title(PF)=Main Channel Distance
X Axis Title(XS)=Station
BEGIN DESCRIPTION:
UNT04908 IN WICK
END DESCRIPTION:
DSS Export Rating Curves= 0
DSS Export Rating Curve Sorted= 0
DSS Export Volume Flow Curves= 0
DXF OffsetX= 0
DXF OffsetY= 0
DXF ScaleX= 1
DXF ScaleY= 10

--- ALLCORNCRTRIB12.p01 (plan) ---

Plan Title=Multiple Run
Short Identifier=Multiple
Geom File=g01
Flow File=f01
Subcritical Flow
K Sum by GR= 0
Std Step Tol= 0.01
Critical Tol= 0.01
Num of Std Step Trials= 20
Max Error Tol= 0.3
Flow Tol Ratio= 0.001
Split Flow NTrial= 30
Split Flow Tol= 0.02
Split Flow Ratio= 0.02
Log Output Level= 0
Friction Slope Method= 1
Unsteady Friction Slope Method= 2
Unsteady Bridges Friction Slope Method= 1
Parabolic Critical Depth
Global Vel Dist=  1 , 1 , 1
Global Log Level= 0
CheckData=True
Encroach Param= -1, 0, 0, 0
BEGIN DESCRIPTION:
Multiple Run
END DESCRIPTION:

--- ALLCORNCRTRIB12.f01 (steady flow) ---

Flow Title=Multiple
Program Version=4.10
Number of Profiles= 7
Profile Names=10-year,25-year,50-year,1pct_min,100-year,1pct_plu,500-year
River Rch & RM=UNT04908 IN WICK,Reach-1         ,1605
     177     222     255     217     293     397     386
River Rch & RM=ALLCORNCRTRIB12,Reach-1         ,1605
     177     222     255     217     293     397     386
Boundary for River Rch & Prof#=ALLCORNCRTRIB12,Reach-1         , 1
Up Type= 0
Dn Type= 3
Dn Slope=0.005
Boundary for River Rch & Prof#=ALLCORNCRTRIB12,Reach-1         , 2
Up Type= 0
Dn Type= 3
Dn Slope=0.005
Boundary for River Rch & Prof#=ALLCORNCRTRIB12,Reach-1         , 3
Up Type= 0
Dn Type= 3
Dn Slope=0.005
Boundary for River Rch & Prof#=ALLCORNCRTRIB12,Reach-1         , 4
Up Type= 0
Dn Type= 3
Dn Slope=0.005
Boundary for River Rch & Prof#=ALLCORNCRTRIB12,Reach-1         , 5
Up Type= 0
Dn Type= 3
Dn Slope=0.005
Boundary for River Rch & Prof#=ALLCORNCRTRIB12,Reach-1         , 6
Up Type= 0
Dn Type= 3
Dn Slope=0.005
Boundary for River Rch & Prof#=ALLCORNCRTRIB12,Reach-1         , 7
Up Type= 0
Dn Type= 3
Dn Slope=0.005
DSS Import GetInterval= 0
DSS Import GetPeak= 0
DSS Import FillOption= 0

--- ALLCORNCRTRIB12.g01 (geometry) ---

Geom Title=Existing Conditions
Program Version=4.10

River Reach=ALLCORNCRTRIB12 ,Reach-1
Reach XY= 30
      3585160.82     10271291.76      3585144.42     10271207.06
      3585155.51     10271173.11       3585189.7     10271125.64
      3585188.18     10271103.36      3585165.21     10271061.71
      3585179.92     10271020.92      3585184.26     10270967.45
      3585199.32     10270946.63      3585254.87     10270916.65
      3585282.37     10270891.89      3585298.16     10270870.04
      3585310.68     10270815.98      3585366.76       10270770.
      3585335.21      10270697.9      3585377.15     10270644.62
      3585375.31     10270596.34      3585399.33     10270497.44
      3585475.13     10270298.56      3585540.09     10270215.54
      3585539.12     10270183.07      3585515.62     10270137.01
      3585538.25      10270079.7      3585566.65     10270048.08
        3585576.     10269946.54      3585599.15     10269901.64
      3585574.64     10269840.08      3585573.92     10269817.66
      3585587.43     10269803.31      3585632.11     10269801.64

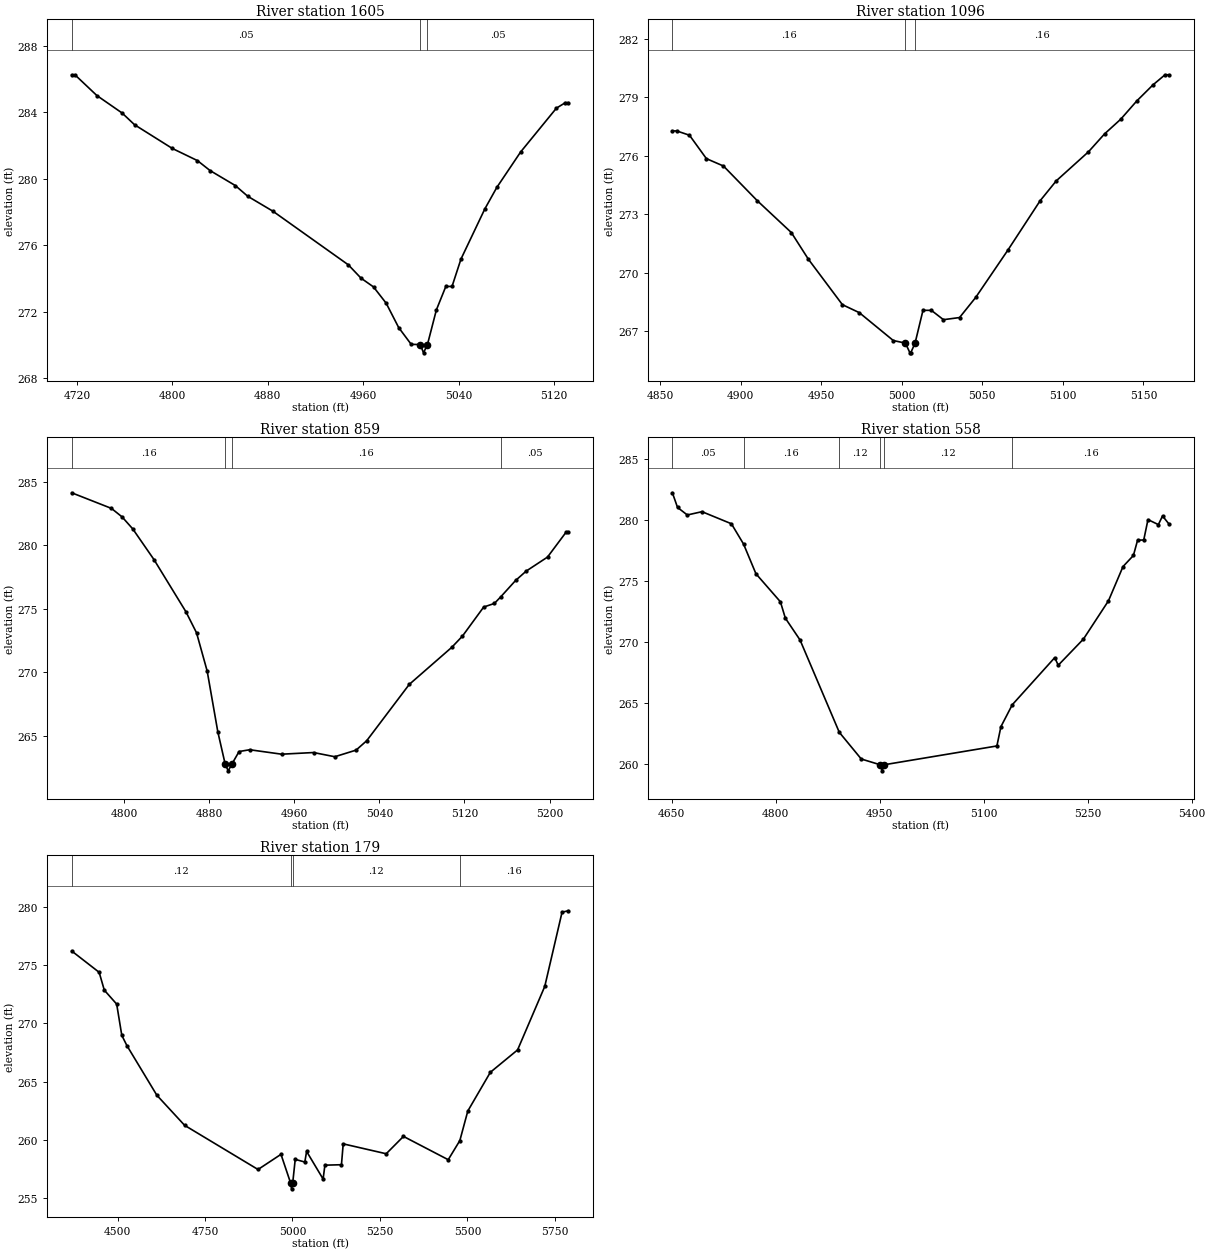
Type RM Length L Ch R = 1 ,1605    ,509,509,509
BEGIN DESCRIPTION:
UNT04908 IN WICK 3.0
END DESCRIPTION:
XS GIS Cut Line= 3
      3585442.13     10271241.65      3585142.11     10271141.64
      3585042.06     10271141.64
#Sta/Elev= 30
  4715.6  286.27  4718.3  286.27  4736.7  285.02  4757.8  283.97  4768.3  283.26
    4800  281.83    4821   281.1  4831.6   280.5  4852.7   279.6  4863.2  278.95
  4884.3  278.05  4947.5  274.82  4958.1  274.02  4968.6  273.49  4979.2  272.51
  4989.7  271.04  5000.2  270.03  5007.8  270.02  5010.5  269.52  5013.8  270.02
  5021.3  272.11  5029.2  273.52  5034.4  273.52  5041.9  275.17  5061.9  278.19
  5071.9  279.48  5091.9  281.62  5121.9  284.26  5129.4  284.59  5131.9  284.59
#Mann= 3 ,-1 , 0
  4715.6     .05       0  5007.8    .035       0  5013.8     .05       0
Bank Sta=5007.8,5013.8
XS Rating Curve= 0 ,0
Exp/Cntr=0.3,0.1

Type RM Length L Ch R = 1 ,1096    ,237,237,237
BEGIN DESCRIPTION:
UNT04908 IN WICK 2.0
END DESCRIPTION:
XS GIS Cut Line= 3
      3585492.15     10270791.66      3585342.11     10270741.64
      3585192.06     10270741.64
#Sta/Elev= 30
  4857.7  277.27  4860.4  277.27  4868.3  277.05  4878.8  275.85  4889.4  275.47
  4910.4  273.69  4931.5  272.06  4942.1  270.69  4963.2  268.36  4973.7  267.95
  4994.8  266.52  5002.3  266.39  5005.1  265.89  5005.6  265.89  5008.3  266.39
  5013.2  268.07  5018.4  268.07  5025.9  267.59  5035.9   267.7  5045.9  268.73
  5065.9  271.16  5085.9  273.69  5095.9  274.71  5115.9   276.2  5125.9  277.12
  5135.9  277.87  5145.9  278.81  5155.9  279.63  5163.4  280.15  5165.9  280.15
#Mann= 3 ,-1 , 0
  4857.7     .16       0  5002.3     .07       0  5008.3     .16       0
Bank Sta=5002.3,5008.3
XS Rating Curve= 0 ,0
Exp/Cntr=0.3,0.1

Type RM Length L Ch R = 1 ,859     ,301,301,301
BEGIN DESCRIPTION:
Mapping XS 408f9122
END DESCRIPTION:
XS GIS Cut Line= 2
      3585639.51      10270536.4      3585172.52     10270532.93
#Sta/Elev= 30
  4750.7  284.13  4788.1   282.9  4798.1  282.23  4808.1  281.29  4828.1  278.87
  4858.1  274.77  4868.1  273.11  4878.1   270.1  4888.1  265.32  4895.1  262.75
  4897.9  262.25  4901.1  262.75  4908.1  263.77  4918.1  263.91  4948.1  263.56
  4978.1  263.69  4998.1  263.36  5018.1  263.88  5028.1  264.62  5068.1  269.05
  5108.1  271.97  5118.1  272.85  5138.1  275.14  5148.1  275.42    5154  275.93
  5168.1  277.23  5178.1  277.97  5198.1  279.07  5215.4  281.01  5217.7  281.01
#Mann= 4 ,-1 , 0
  4750.7     .16       0  4895.1     .07       0  4901.1     .16       0
    5154     .05       0
Bank Sta=4895.1,4901.1
XS Rating Curve= 0 ,0
Exp/Cntr=0.3,0.1

Type RM Length L Ch R = 1 ,558     ,379,379,379
BEGIN DESCRIPTION:
Mapping XS 59632906
END DESCRIPTION:
XS GIS Cut Line= 4
      3585795.78     10270418.37      3585655.12     10270277.72
      3585267.97     10270232.58      3585162.06     10270303.76
#Sta/Elev= 30
    4651   282.2  4658.4     281  4672.5  280.38  4693.7  280.65  4736.1  279.66
  4753.6     278  4771.5  275.56  4806.8  273.26  4813.9  271.92  4835.1  270.13
  4891.7  262.56  4923.4  260.37  4950.6   259.9  4953.4   259.4  4956.6   259.9
    5119  261.44  5124.8  263.02  5141.2  264.82  5202.4  268.68  5207.5  268.06
  5243.9  270.21  5279.9  273.34  5300.9  276.15  5315.9  277.06  5321.9  278.31
  5330.8  278.33  5336.9     280  5351.9  279.59  5357.9   280.3  5367.3  279.63
#Mann= 6 ,-1 , 0
    4651     .05       0  4753.6     .16       0  4891.7     .12       0
  4950.6     .07       0  4956.6     .12       0  5141.2     .16       0
Bank Sta=4950.6,4956.6
XS Rating Curve= 0 ,0
Exp/Cntr=0.3,0.1

Type RM Length L Ch R = 1 ,179     ,0,0,0
BEGIN DESCRIPTION:
UNT04908 IN WICK 1.0
END DESCRIPTION:
XS GIS Cut Line= 4
      3586002.95     10270371.02      3585683.96     10269941.37
      3585362.78     10269880.61      3584946.61     10270251.26
#Sta/Elev= 30
    4369  276.22  4447.5  274.39  4462.2  272.86  4497.6  271.66  4512.2  268.98
  4526.8   268.1  4612.4  263.84  4691.7  261.26  4901.5  257.47  4967.1  258.77
  4994.6  256.31  4997.4  255.81  5000.6  256.31  5007.8  258.34  5035.2  258.11
  5040.3  259.02  5087.5  256.65  5092.6  257.84  5139.9  257.88  5144.9  259.67
  5267.8  258.82  5317.1  260.31    5445  258.31  5478.2  259.95    5501  262.49
  5565.4  265.81  5643.2  267.73  5720.9  273.18  5770.3  279.55  5788.3  279.67
#Mann= 4 ,-1 , 0
    4369     .12       0  4994.6     .07       0  5000.6     .12       0
  5478.2     .16       0
Bank Sta=4994.6,5000.6
XS Rating Curve= 0 ,0
Exp/Cntr=0.3,0.1

Chan Stop Cuts=-1
Use User Specified Reach Order=0
Composite Channel Slope=5