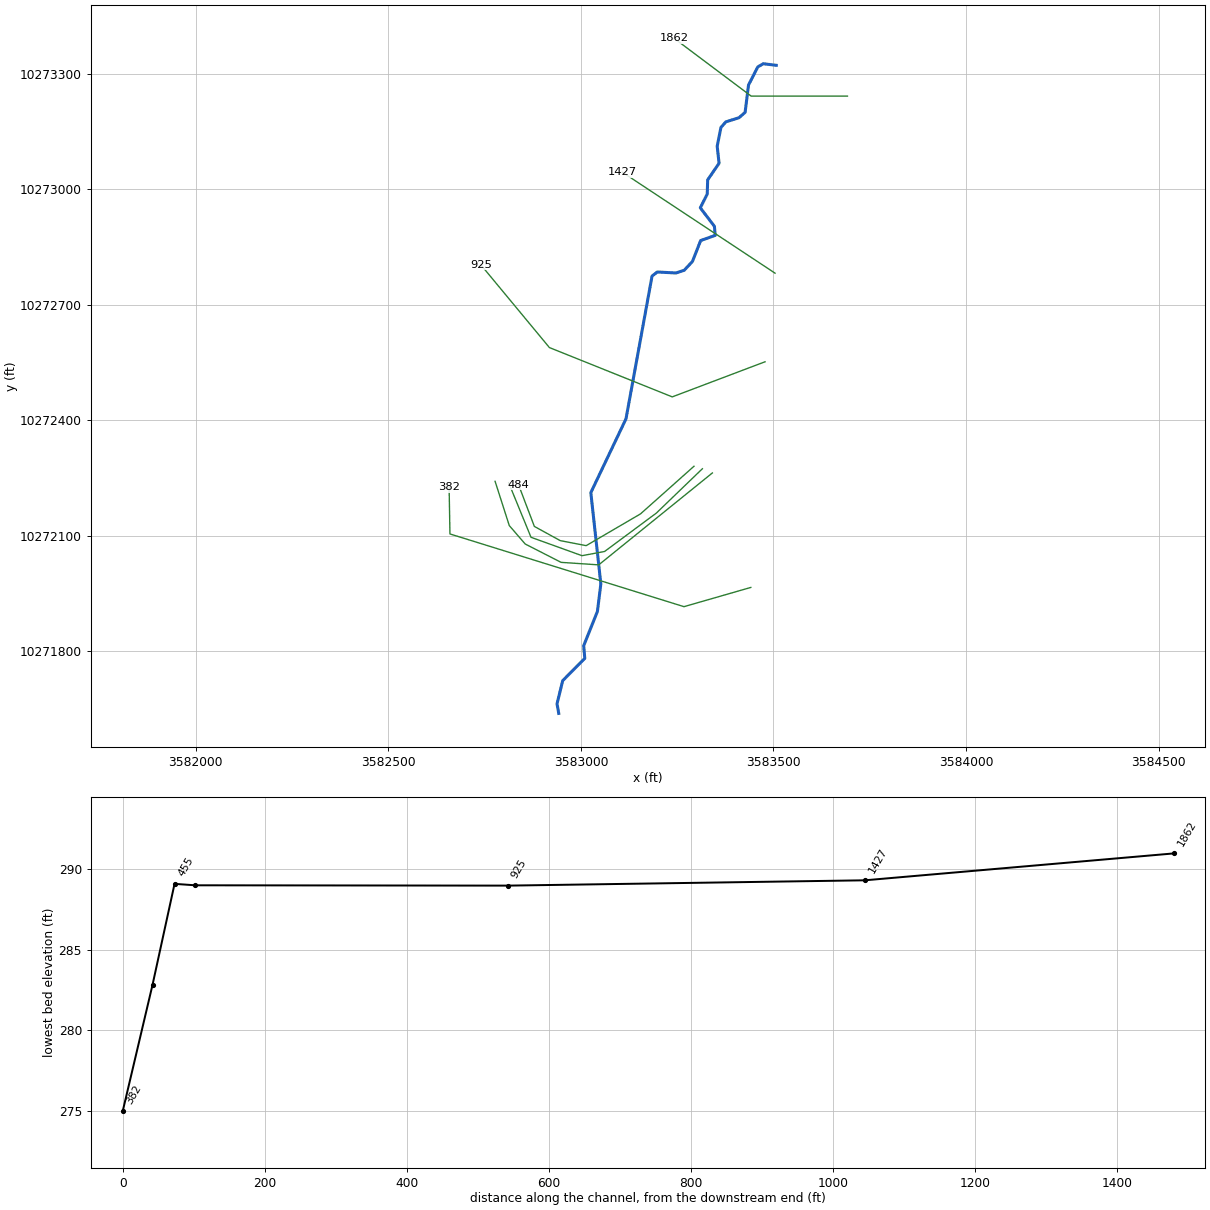
--- ALLCORNCRTRIB14.prj (project) ---

Proj Title=ALLCORN CREEK TRIB 14
Current Plan=p01
Default Exp/Contr=0.3,0.1
English Units
Geom File=g01
Flow File=f01
Plan File=p01
Y Axis Title=Elevation
X Axis Title(PF)=Main Channel Distance
X Axis Title(XS)=Station
BEGIN DESCRIPTION:
UNT04904 IN WICK
END DESCRIPTION:
DSS Export Rating Curves= 0
DSS Export Rating Curve Sorted= 0
DSS Export Volume Flow Curves= 0
DXF OffsetX= 0
DXF OffsetY= 0
DXF ScaleX= 1
DXF ScaleY= 10

--- ALLCORNCRTRIB14.p01 (plan) ---

Plan Title=Multiple Run
Short Identifier=Multiple
Geom File=g01
Flow File=f01
Subcritical Flow
K Sum by GR= 0
Std Step Tol= 0.01
Critical Tol= 0.01
Num of Std Step Trials= 20
Max Error Tol= 0.3
Flow Tol Ratio= 0.001
Split Flow NTrial= 30
Split Flow Tol= 0.02
Split Flow Ratio= 0.02
Log Output Level= 0
Friction Slope Method= 1
Unsteady Friction Slope Method= 2
Unsteady Bridges Friction Slope Method= 1
Parabolic Critical Depth
Global Vel Dist=  1 , 1 , 1
Global Log Level= 0
CheckData=True
Encroach Param= -1, 0, 0, 0
BEGIN DESCRIPTION:
Multiple Run
END DESCRIPTION:

--- ALLCORNCRTRIB14.f01 (steady flow) ---

Flow Title=Multiple
Program Version=4.10
Number of Profiles= 7
Profile Names=10-year,25-year,50-year,1pct_min,100-year,1pct_plu,500-year
River Rch & RM=UNT04904 IN WICK,Reach-1         ,1862
     185     232     268     229     309     418     409
River Rch & RM=ALLCORNCRTRIB14,Reach-1         ,1862
     185     232     268     229     309     418     409
Boundary for River Rch & Prof#=ALLCORNCRTRIB14,Reach-1         , 1
Up Type= 0
Dn Type= 3
Dn Slope=0.005
Boundary for River Rch & Prof#=ALLCORNCRTRIB14,Reach-1         , 2
Up Type= 0
Dn Type= 3
Dn Slope=0.005
Boundary for River Rch & Prof#=ALLCORNCRTRIB14,Reach-1         , 3
Up Type= 0
Dn Type= 3
Dn Slope=0.005
Boundary for River Rch & Prof#=ALLCORNCRTRIB14,Reach-1         , 4
Up Type= 0
Dn Type= 3
Dn Slope=0.005
Boundary for River Rch & Prof#=ALLCORNCRTRIB14,Reach-1         , 5
Up Type= 0
Dn Type= 3
Dn Slope=0.005
Boundary for River Rch & Prof#=ALLCORNCRTRIB14,Reach-1         , 6
Up Type= 0
Dn Type= 3
Dn Slope=0.005
Boundary for River Rch & Prof#=ALLCORNCRTRIB14,Reach-1         , 7
Up Type= 0
Dn Type= 3
Dn Slope=0.005
DSS Import GetInterval= 0
DSS Import GetPeak= 0
DSS Import FillOption= 0

--- ALLCORNCRTRIB14.g01 (geometry) ---

Geom Title=Existing Conditions
Program Version=4.10

River Reach=ALLCORNCRTRIB14 ,Reach-1
Reach XY= 30
      3583507.11     10273321.64      3583473.59     10273325.69
      3583459.33     10273317.54       3583435.2     10273270.47
      3583426.29     10273199.41      3583410.47     10273185.53
      3583376.19     10273174.69      3583363.54     10273160.22
      3583353.83     10273111.43      3583358.69     10273067.33
      3583329.11     10273024.12      3583327.99     10272987.34
        3583310.     10272951.54      3583346.59     10272903.54
      3583348.78     10272880.03      3583310.87     10272866.54
      3583289.65     10272812.42      3583268.31      10272789.5
      3583246.77     10272782.36      3583198.45     10272784.97
      3583184.71     10272774.35      3583117.05     10272403.68
      3583025.73     10272212.01      3583051.72     10271974.88
      3583042.83     10271903.59      3583007.15     10271814.53
      3583010.02     10271781.72      3582952.73     10271723.91
      3582937.97     10271663.58      3582942.41      10271638.9

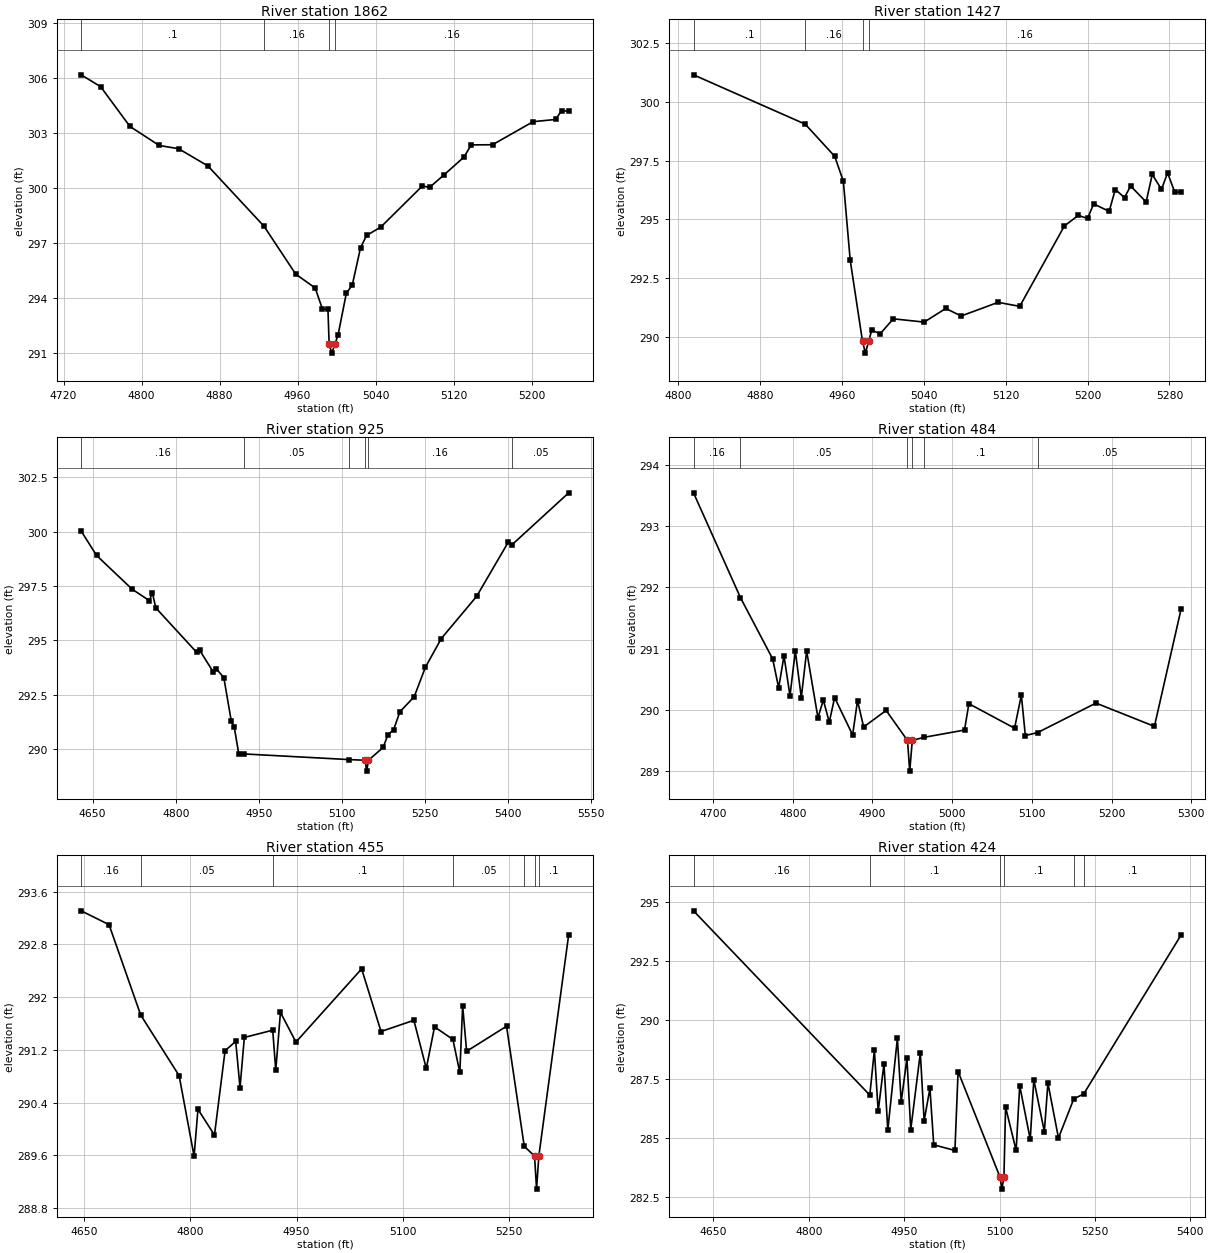
Type RM Length L Ch R = 1 ,1862    ,435,435,435
BEGIN DESCRIPTION:
UNT04904 IN WICK 4.0
END DESCRIPTION:
XS GIS Cut Line= 3
       3583692.1     10273241.64      3583442.11     10273241.64
       3583242.1     10273391.64
#Sta/Elev= 30
  4738.1  306.19  4758.1  305.54  4788.1  303.37  4818.1  302.33  4838.1  302.15
  4868.1  301.21  4925.7  297.91  4958.1   295.3  4978.1  294.54  4985.6  293.38
  4991.2  293.38  4992.4  291.48  4995.1  290.98  4998.4  291.48  5001.6  291.98
    5010  294.24  5016.2  294.71  5024.6  296.74  5030.8  297.41  5045.4  297.87
  5088.1  300.12  5095.4  300.04    5110  300.71  5130.8   301.7  5138.1  302.36
    5160  302.37  5201.6  303.63  5224.6  303.75  5230.8  304.23  5238.1   304.2
#Mann= 4 ,-1 , 0
  4738.1      .1       0  4925.7     .16       0  4992.4     .07       0
  4998.4     .16       0
Bank Sta=4992.4,4998.4
XS Rating Curve= 0 ,0
Exp/Cntr=0.3,0.1

Type RM Length L Ch R = 1 ,1427    ,502,502,502
BEGIN DESCRIPTION:
UNT04904 IN WICK 3.0
END DESCRIPTION:
XS GIS Cut Line= 2
      3583504.11     10272781.87      3583107.06      10273044.4
#Sta/Elev= 30
  4815.3  301.15  4924.4  299.05  4953.2  297.68  4961.6  296.62  4968.3  293.26
  4980.3  289.81  4983.1  289.31  4986.3  289.81  4989.3  290.29  4997.5  290.13
  5010.4  290.77  5040.5  290.63  5061.6  291.21  5076.6  290.89  5112.7  291.47
  5133.8   291.3  5177.4  294.72    5191  295.17    5200  295.04    5206  295.66
  5221.1  295.34  5227.1  296.27  5236.1  295.93  5242.1  296.42  5257.2  295.74
  5263.2  296.91  5272.2  296.28  5278.2  296.98  5285.2  296.15  5291.3  296.17
#Mann= 4 ,-1 , 0
  4815.3      .1       0  4924.4     .16       0  4980.3     .07       0
  4986.3     .16       0
Bank Sta=4980.3,4986.3
XS Rating Curve= 0 ,0
Exp/Cntr=0.3,0.1

Type RM Length L Ch R = 1 ,925     ,441,441,441
BEGIN DESCRIPTION:
UNT04904 IN WICK 2.0
END DESCRIPTION:
XS GIS Cut Line= 4
       3583478.1     10272551.84      3583237.19     10272460.68
      3582918.18     10272588.72      3582740.23     10272803.57
#Sta/Elev= 30
  4629.3  300.02  4657.1   298.9  4721.2  297.35  4752.5  296.82  4757.8  297.19
    4764  296.49  4837.6  294.45    4843  294.55  4867.8  293.54  4873.2  293.69
  4886.9  293.28  4900.3  291.29  4905.7  291.01  4913.9  289.77  4923.9  289.77
  5113.6  289.51    5142  289.48  5144.8  288.98    5148  289.48  5174.6  290.07
  5183.3  290.66  5193.4  290.88  5204.8  291.71  5230.6   292.4  5250.9  293.76
  5279.6  295.08  5343.4  297.02  5400.7  299.52  5407.6   299.4  5509.6  301.78
#Mann= 6 ,-1 , 0
  4629.3     .16       0  4923.9     .05       0  5113.6     .16       0
    5142    .033       0    5148     .16       0  5407.6     .05       0
Bank Sta=5142,5148
XS Rating Curve= 0 ,0
Exp/Cntr=0.3,0.1

Type RM Length L Ch R = 1 ,484     ,29,29,29
BEGIN DESCRIPTION:
Mapping XS c233c194
END DESCRIPTION:
XS GIS Cut Line= 6
       3583293.6     10272280.55      3583154.73     10272156.86
      3583013.67      10272074.4       3582946.4     10272087.42
      3582879.12     10272124.31      3582837.87     10272232.86
#Sta/Elev= 30
  4675.5  293.54  4734.4  291.83  4774.8  290.83  4782.3  290.36    4789  290.88
  4796.5  290.23  4803.2  290.96  4810.7   290.2  4817.4  290.96  4831.6  289.87
  4838.3  290.16  4845.8   289.8  4852.5   290.2  4875.1  289.59  4881.2  290.15
  4888.9  289.72  4917.1  289.99  4943.9   289.5  4946.7     289  4949.9   289.5
    4964  289.55  5015.4  289.67  5020.9   290.1  5078.2   289.7  5086.7  290.24
  5091.7  289.58  5107.3  289.63  5180.3  290.11  5253.6  289.73    5287  291.64
#Mann= 6 ,-1 , 0
  4675.5     .16       0  4734.4     .05       0  4943.9     .07       0
  4949.9     .05       0    4964      .1       0  5107.3     .05       0
Bank Sta=4943.9,4949.9
XS Rating Curve= 0 ,0
Exp/Cntr=0.3,0.1

Type RM Length L Ch R = 1 ,455     ,31,31,31
BEGIN DESCRIPTION:
Mapping XS 54a43e73
END DESCRIPTION:
XS GIS Cut Line= 6
      3583315.35     10272274.08      3583195.96     10272159.03
      3583061.41     10272059.21      3583002.82     10272048.36
      3582870.44      10272096.1       3582812.3     10272237.95
#Sta/Elev= 30
  4645.7  293.31  4685.1   293.1  4729.8  291.73  4784.1  290.81  4805.2  289.59
  4810.7   290.3    4834  289.91    4849  291.19    4864  291.33  4870.1  290.63
  4876.2  291.39  4916.3   291.5  4920.6  290.89  4927.2  291.77  4949.1  291.32
  5041.9  292.43  5069.3  291.48  5115.7  291.65  5133.2  290.92  5144.9  291.55
  5170.8  291.36  5180.6  290.86  5184.6  291.87  5190.2  291.18  5246.6  291.56
  5271.6  289.74  5286.2  289.59    5289  289.09  5292.2  289.59  5334.4  292.95
#Mann= 7 ,-1 , 0
  4645.7     .16       0  4729.8     .05       0  4916.3      .1       0
  5170.8     .05       0  5271.6      .1       0  5286.2     .07       0
  5292.2      .1       0
Bank Sta=5286.2,5292.2
XS Rating Curve= 0 ,0
Exp/Cntr=0.3,0.1

Type RM Length L Ch R = 1 ,424     ,42,42,42
BEGIN DESCRIPTION:
Mapping XS fe1c9a36
END DESCRIPTION:
XS GIS Cut Line= 6
      3583341.36      10272263.2      3583046.22     10272024.48
      3582948.57       10272031.      3582855.25     10272078.74
      3582814.02     10272126.48      3582777.13     10272241.47
#Sta/Elev= 30
  4618.6  294.63  4895.9  286.81  4903.1  288.71  4909.1  286.12  4918.2  288.14
  4924.2  285.32  4939.3  289.22  4945.3  286.52  4954.3  288.37  4960.3  285.34
  4975.4   288.6  4981.4  285.72  4990.5   287.1  4996.5   284.7  5029.8  284.46
  5034.8  287.81  5100.9  283.32  5103.6  282.82  5106.9  283.32  5109.5   286.3
  5126.1  284.46  5131.7  287.21  5148.3  284.93  5153.9  287.46  5170.5  285.26
  5176.1  287.32  5192.7  284.99  5216.8  286.65  5232.4  286.86  5385.5   293.6
#Mann= 6 ,-1 , 0
  4618.6     .16       0  4895.9      .1       0  5100.9     .07       0
  5106.9      .1       0  5216.8     .05       0  5232.4      .1       0
Bank Sta=5100.9,5106.9
XS Rating Curve= 0 ,0
Exp/Cntr=0.3,0.1

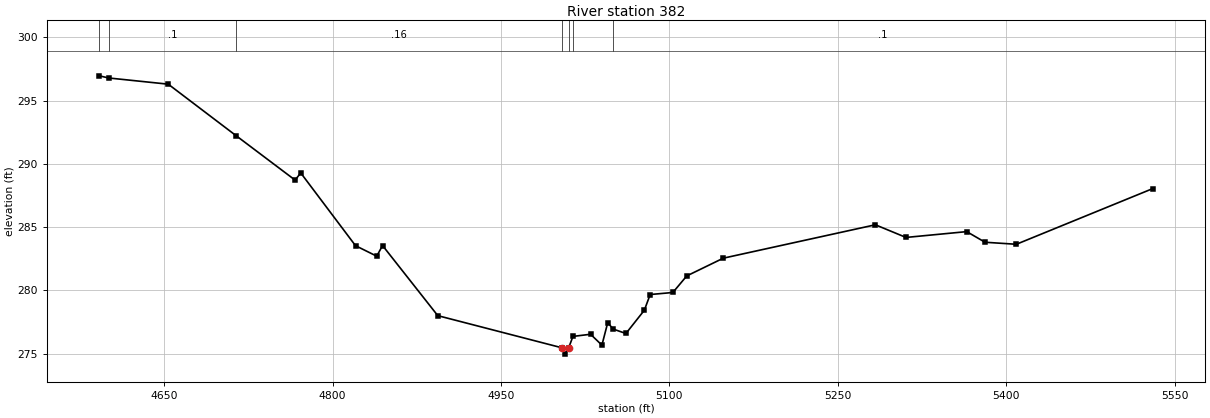
Type RM Length L Ch R = 1 ,382     ,0,0,0
BEGIN DESCRIPTION:
UNT04904 IN WICK 1.0
END DESCRIPTION:
XS GIS Cut Line= 4
      3583441.14     10271965.88      3583267.58     10271915.98
      3582659.94     10272104.78      3582657.77     10272226.27
#Sta/Elev= 30
  4592.2  296.96  4600.5  296.79  4653.6   296.3  4713.9  292.24  4766.6  288.72
  4771.6  289.29  4820.4  283.54  4839.3  282.71  4844.5  283.55  4893.7  278.01
  5004.3  275.47  5007.1  274.97  5010.3  275.47  5014.1  276.37  5029.8  276.54
  5039.9  275.68  5045.1  277.46  5049.9  276.95  5061.3   276.6  5077.7  278.44
  5082.9  279.68  5103.1  279.84  5115.5  281.15    5148  282.55  5283.5  285.19
  5310.8  284.19  5364.9  284.65  5381.2  283.81  5409.1  283.65  5530.6  288.05
#Mann= 7 ,-1 , 0
  4592.2     .05       0  4600.5      .1       0  4713.9     .16       0
  5004.3     .07       0  5010.3     .16       0  5014.1     .12       0
  5049.9      .1       0
Bank Sta=5004.3,5010.3
XS Rating Curve= 0 ,0
Exp/Cntr=0.3,0.1

Chan Stop Cuts=-1
Use User Specified Reach Order=0
Composite Channel Slope=5