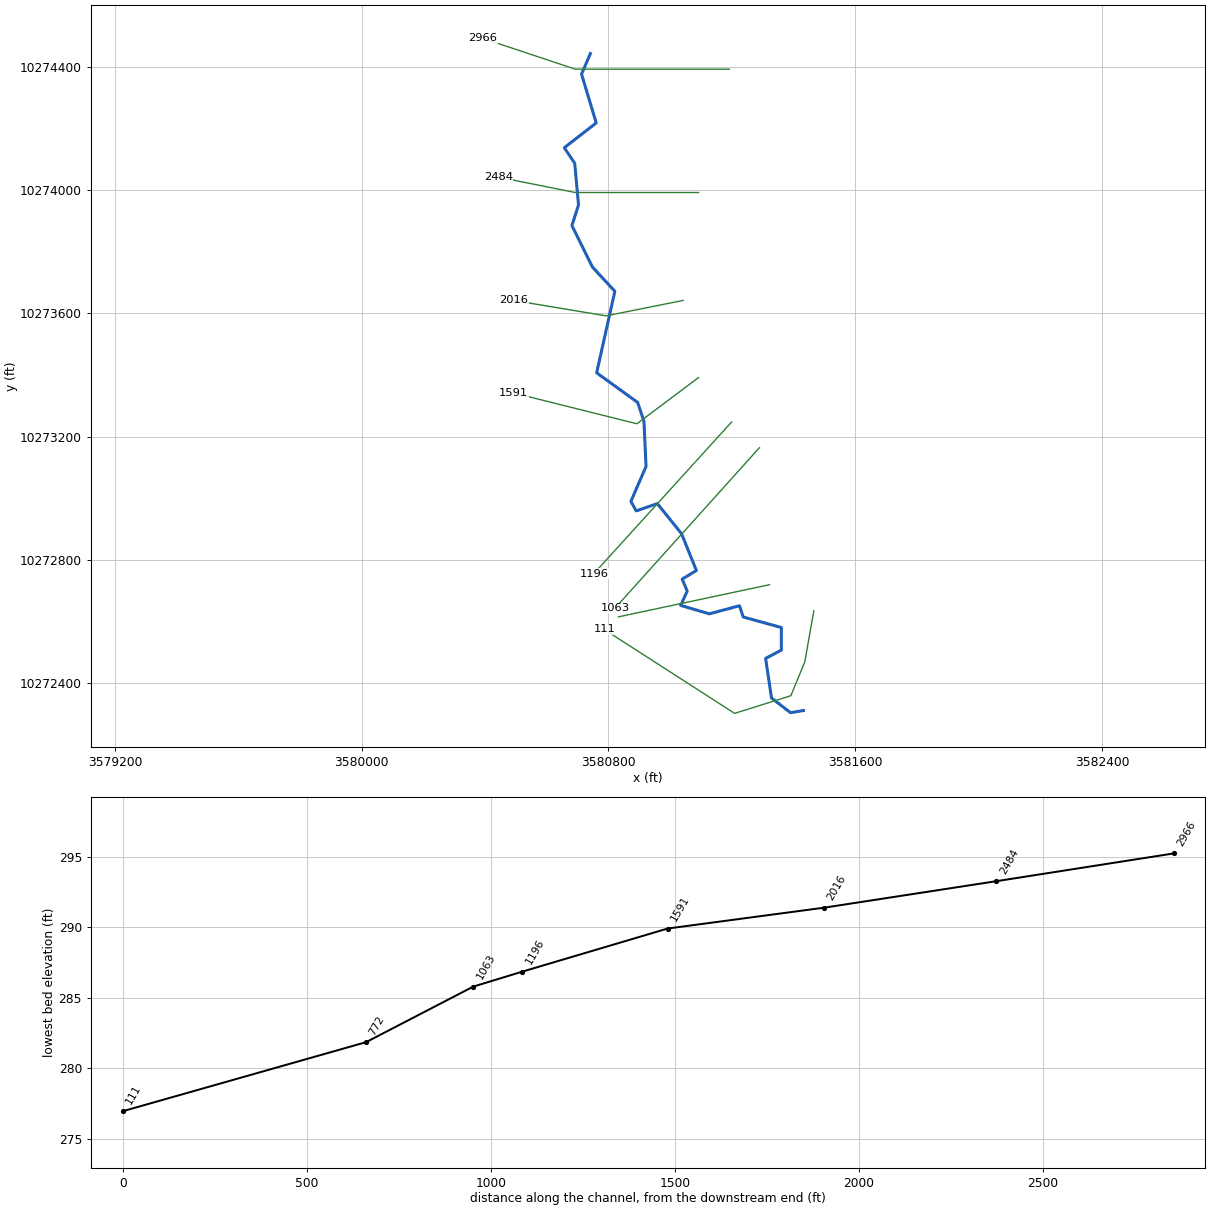
--- ALLCORNCRTRIB15.prj (project) ---

Proj Title=ALLCORN CREEK TRIB 15
Current Plan=p01
Default Exp/Contr=0.3,0.1
English Units
Geom File=g01
Flow File=f01
Plan File=p01
Y Axis Title=Elevation
X Axis Title(PF)=Main Channel Distance
X Axis Title(XS)=Station
BEGIN DESCRIPTION:
UNT04902 IN WICK
END DESCRIPTION:
DSS Export Rating Curves= 0
DSS Export Rating Curve Sorted= 0
DSS Export Volume Flow Curves= 0
DXF OffsetX= 0
DXF OffsetY= 0
DXF ScaleX= 1
DXF ScaleY= 10

--- ALLCORNCRTRIB15.p01 (plan) ---

Plan Title=Multiple Run
Short Identifier=Multiple
Geom File=g01
Flow File=f01
Subcritical Flow
K Sum by GR= 0
Std Step Tol= 0.01
Critical Tol= 0.01
Num of Std Step Trials= 20
Max Error Tol= 0.3
Flow Tol Ratio= 0.001
Split Flow NTrial= 30
Split Flow Tol= 0.02
Split Flow Ratio= 0.02
Log Output Level= 0
Friction Slope Method= 1
Unsteady Friction Slope Method= 2
Unsteady Bridges Friction Slope Method= 1
Parabolic Critical Depth
Global Vel Dist=  1 , 1 , 1
Global Log Level= 0
CheckData=True
Encroach Param= -1, 0, 0, 0
BEGIN DESCRIPTION:
Multiple Run
END DESCRIPTION:

--- ALLCORNCRTRIB15.f01 (steady flow) ---

Flow Title=Multiple
Program Version=4.10
Number of Profiles= 7
Profile Names=10-year,25-year,50-year,1pct_min,100-year,1pct_plu,500-year
River Rch & RM=UNT04902 IN WICK,Reach-1         ,2966
     218     275     319     272     369     498     490
River Rch & RM=ALLCORNCRTRIB15,Reach-1         ,2966
     218     275     319     272     369     498     490
Boundary for River Rch & Prof#=ALLCORNCRTRIB15,Reach-1         , 1
Up Type= 0
Dn Type= 3
Dn Slope=0.005
Boundary for River Rch & Prof#=ALLCORNCRTRIB15,Reach-1         , 2
Up Type= 0
Dn Type= 3
Dn Slope=0.005
Boundary for River Rch & Prof#=ALLCORNCRTRIB15,Reach-1         , 3
Up Type= 0
Dn Type= 3
Dn Slope=0.005
Boundary for River Rch & Prof#=ALLCORNCRTRIB15,Reach-1         , 4
Up Type= 0
Dn Type= 3
Dn Slope=0.005
Boundary for River Rch & Prof#=ALLCORNCRTRIB15,Reach-1         , 5
Up Type= 0
Dn Type= 3
Dn Slope=0.005
Boundary for River Rch & Prof#=ALLCORNCRTRIB15,Reach-1         , 6
Up Type= 0
Dn Type= 3
Dn Slope=0.005
Boundary for River Rch & Prof#=ALLCORNCRTRIB15,Reach-1         , 7
Up Type= 0
Dn Type= 3
Dn Slope=0.005
DSS Import GetInterval= 0
DSS Import GetPeak= 0
DSS Import FillOption= 0

--- ALLCORNCRTRIB15.g01 (geometry) ---

Geom Title=Existing Conditions
Program Version=4.10

River Reach=ALLCORNCRTRIB15 ,Reach-1
Reach XY= 30
      3580741.33     10274442.28      3580712.55     10274375.81
      3580760.18      10274217.3      3580656.63      10274136.9
      3580690.39     10274086.68      3580702.74     10273951.03
      3580681.39     10273884.36       3580748.1     10273749.61
       3580820.6     10273671.44       3580761.6     10273407.02
      3580894.41     10273310.92      3580914.97     10273249.89
      3580921.75     10273103.37      3580872.62     10272989.81
      3580889.98      10272959.1      3580958.35     10272982.75
      3581036.86     10272885.14      3581085.04     10272765.84
      3581038.95     10272737.83      3581055.28     10272699.06
      3581034.25     10272652.59      3581127.03     10272625.29
      3581224.88     10272651.55      3581236.86     10272615.09
      3581360.59     10272580.91      3581360.52     10272507.78
       3581309.5     10272480.48      3581328.74     10272352.33
      3581390.26     10272304.72      3581432.11     10272311.64

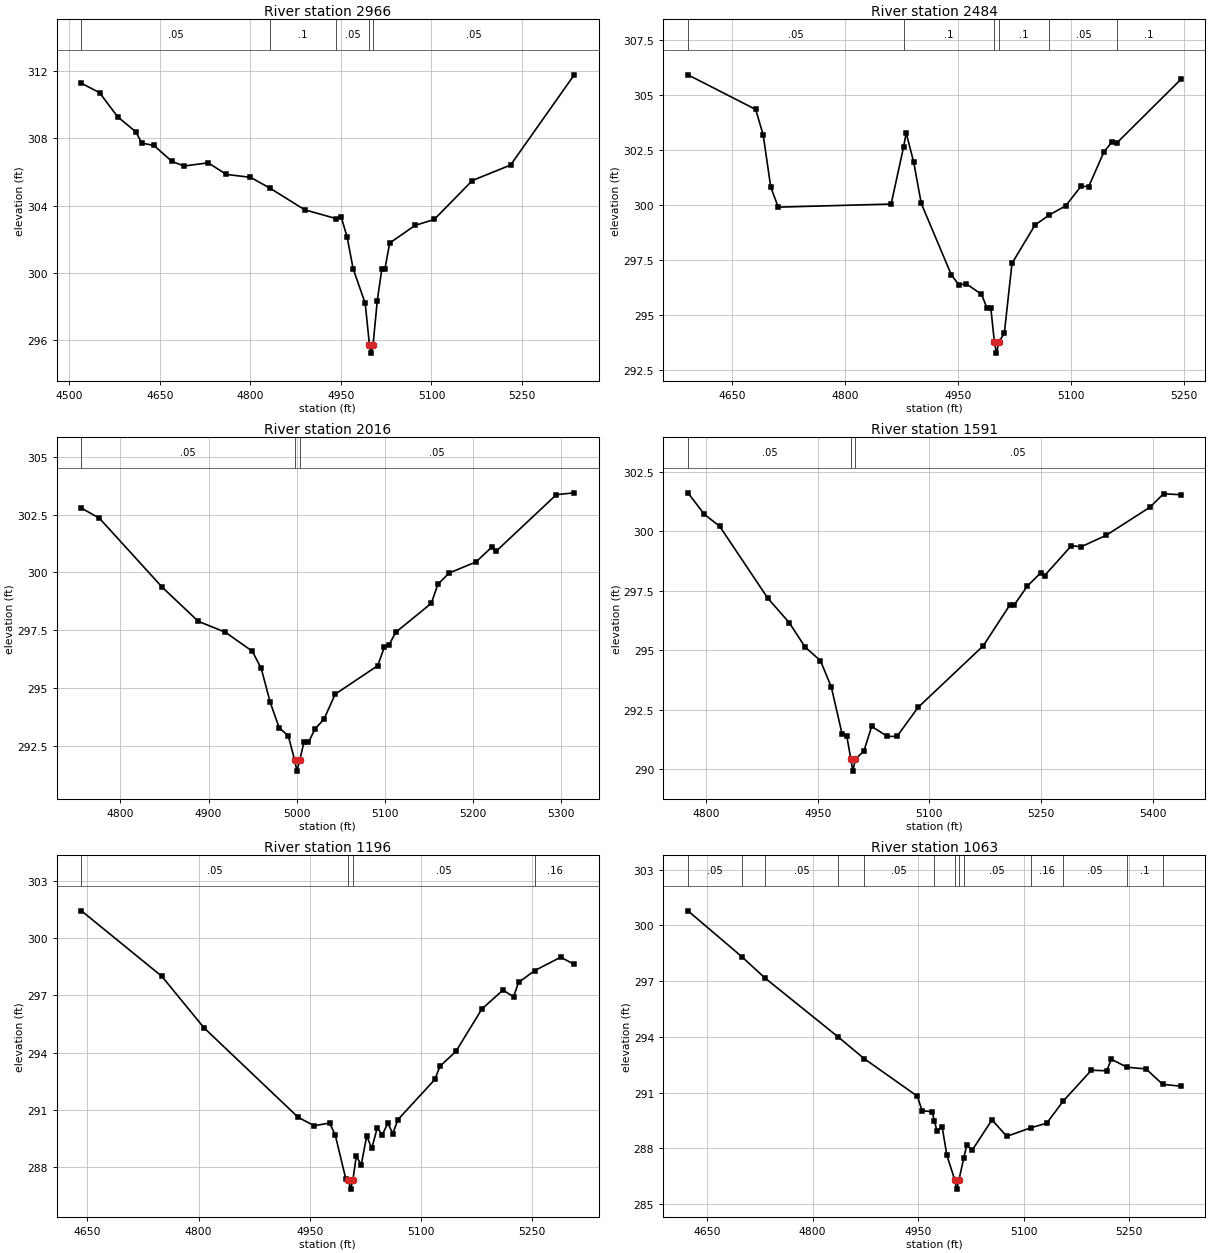
Type RM Length L Ch R = 1 ,2966    ,482,482,482
BEGIN DESCRIPTION:
UNT04902 IN WICK 5.0
END DESCRIPTION:
XS GIS Cut Line= 3
      3581192.07     10274391.64      3580692.11     10274391.64
       3580392.1     10274491.64
#Sta/Elev= 30
  4520.3  311.26  4550.3   310.7  4580.3  309.27  4610.3  308.38  4620.3  307.71
  4640.3  307.57  4670.3  306.62  4690.3  306.35  4730.3  306.54  4760.3  305.85
  4800.3  305.68  4832.4  305.04  4890.3  303.75  4942.3  303.23  4950.3  303.35
  4960.3  302.14  4970.3  300.26  4990.3   298.2  4997.3  295.75    5000  295.25
  5003.3  295.75  5010.3  298.37  5017.8  300.23  5022.9  300.23  5030.8  301.78
    5073  302.83  5104.6  303.18  5167.8  305.49  5231.1  306.41  5336.5  311.76
#Mann= 5 ,-1 , 0
  4520.3     .05       0  4832.4      .1       0  4942.3     .05       0
  4997.3    .035       0  5003.3     .05       0
Bank Sta=4997.3,5003.3
XS Rating Curve= 0 ,0
Exp/Cntr=0.3,0.1

Type RM Length L Ch R = 1 ,2484    ,468,468,468
BEGIN DESCRIPTION:
UNT04902 IN WICK 4.0
END DESCRIPTION:
XS GIS Cut Line= 3
      3581092.08     10273991.64      3580692.11     10273991.64
      3580442.13     10274041.64
#Sta/Elev= 30
    4591   305.9    4681  304.33    4691  303.17    4701  300.81    4711   299.9
    4861  300.04  4877.5  302.62    4881  303.26    4891  301.94    4901  300.07
    4941  296.83    4951  296.38    4961  296.42    4981  295.95  4988.5  295.32
  4993.5  295.32  4998.2  293.78  5000.9  293.28  5004.2  293.78  5011.4  294.18
  5021.6  297.35  5052.2  299.09  5071.4  299.55    5093  299.96  5113.4  300.85
  5123.5  300.83  5143.9  302.41  5154.1  302.84  5161.5  302.83  5245.9  305.69
#Mann= 6 ,-1 , 0
    4591     .05       0  4877.5      .1       0  4998.2     .07       0
  5004.2      .1       0  5071.4     .05       0  5161.5      .1       0
Bank Sta=4998.2,5004.2
XS Rating Curve= 0 ,0
Exp/Cntr=0.3,0.1

Type RM Length L Ch R = 1 ,2016    ,425,425,425
BEGIN DESCRIPTION:
UNT04902 IN WICK 3.0
END DESCRIPTION:
XS GIS Cut Line= 3
      3581042.13     10273641.65      3580792.11     10273591.64
      3580492.12     10273641.64
#Sta/Elev= 30
  4755.7  302.78  4776.1  302.34  4847.5  299.35  4888.3  297.88  4918.9  297.41
  4949.5  296.59  4959.7  295.84  4969.9  294.37  4980.1  293.27  4990.3  292.93
  4997.5   291.9  5000.2   291.4  5003.5   291.9  5008.1  292.64  5013.2  292.64
  5020.8  293.23  5030.9  293.65  5043.6  294.73  5091.8  295.96  5099.4  296.77
  5104.5  296.84  5112.1   297.4  5152.6  298.66  5160.2  299.49  5172.9  299.97
  5203.3  300.45    5221  301.08  5226.1  300.91  5294.5  303.36  5314.8  303.44
#Mann= 3 ,-1 , 0
  4755.7     .05       0  4997.5     .03       0  5003.5     .05       0
Bank Sta=4997.5,5003.5
XS Rating Curve= 0 ,0
Exp/Cntr=0.3,0.1

Type RM Length L Ch R = 1 ,1591    ,395,395,395
BEGIN DESCRIPTION:
UNT04902 IN WICK 2.0
END DESCRIPTION:
XS GIS Cut Line= 3
      3581092.09     10273391.63      3580892.11     10273241.64
       3580492.1     10273341.64
#Sta/Elev= 30
  4775.6  301.62  4797.5  300.72  4818.3  300.21  4882.9  297.19    4912  296.15
  4932.9  295.14  4953.7  294.56  4968.3  293.45  4982.9  291.46  4989.1  291.39
  4994.5  290.42  4997.2  289.92  5000.5  290.42    5012  290.76  5022.5   291.8
  5043.6  291.38  5056.5  291.38  5084.9   292.6  5172.5  295.19  5208.5  296.92
  5213.7  296.89  5231.7   297.7  5249.8  298.26  5254.9  298.14    5291   299.4
  5303.9  299.35  5337.4  299.83  5396.7  301.02  5414.7  301.58  5437.9  301.54
#Mann= 3 ,-1 , 0
  4775.6     .05       0  4994.5     .03       0  5000.5     .05       0
Bank Sta=4994.5,5000.5
XS Rating Curve= 0 ,0
Exp/Cntr=0.3,0.1

Type RM Length L Ch R = 1 ,1196    ,133,133,133
BEGIN DESCRIPTION:
Mapping XS cd3a97d5
END DESCRIPTION:
XS GIS Cut Line= 2
      3581199.41     10273247.61      3580752.46     10272755.61
#Sta/Elev= 30
  4641.9  301.43  4750.4     298  4807.1  295.31  4934.2  290.62  4955.8  290.18
  4976.7  290.32  4984.2   289.7  4998.4  287.41  5002.1  287.36  5004.9  286.86
  5008.1  287.36  5012.6  288.58  5019.3  288.14  5026.7  289.64  5033.5  288.99
  5040.9  290.07  5047.7   289.7  5055.1  290.31  5061.9  289.77  5068.8   290.5
  5118.6   292.6  5125.4  293.29    5147  294.07  5182.2   296.3  5210.5  297.28
  5224.7  296.93  5231.5  297.68  5253.2   298.3  5288.3     299  5306.6  298.63
#Mann= 4 ,-1 , 0
  4641.9     .05       0  5002.1     .03       0  5008.1     .05       0
  5253.2     .16       0
Bank Sta=5002.1,5008.1
XS Rating Curve= 0 ,0
Exp/Cntr=0.3,0.1

Type RM Length L Ch R = 1 ,1063    ,291,291,291
BEGIN DESCRIPTION:
Mapping XS ef234b9d
END DESCRIPTION:
XS GIS Cut Line= 2
      3581289.68     10273164.26      3580820.93     10272643.44
#Sta/Elev= 30
  4622.8  300.78  4699.1  298.32  4732.1  297.17  4836.1     294  4873.5  292.82
    4949   290.8  4955.7  290.02  4969.9  289.97  4973.1  289.49  4976.7  288.95
  4984.1  289.17  4990.9  287.63  5002.1   286.3  5004.8   285.8  5008.1   286.3
    5015  287.48  5019.3  288.19  5026.7  287.88  5055.1  289.53  5076.1  288.64
  5110.1   289.1  5132.9  289.35  5156.4  290.54  5196.4   292.2  5218.1  292.17
  5224.8  292.79  5247.1  292.36  5274.1  292.27  5297.8  291.44  5323.5  291.34
#Mann= 13 ,-1 , 0
  4622.8     .05       0  4699.1      .1       0  4732.1     .05       0
  4836.1      .1       0  4873.5     .05       0  4973.1     .16       0
  5002.1     .07       0  5008.1     .16       0    5015     .05       0
  5110.1     .16       0  5156.4     .05       0  5247.1      .1       0
  5297.8     .05       0
Bank Sta=5002.1,5008.1
XS Rating Curve= 0 ,0
Exp/Cntr=0.3,0.1

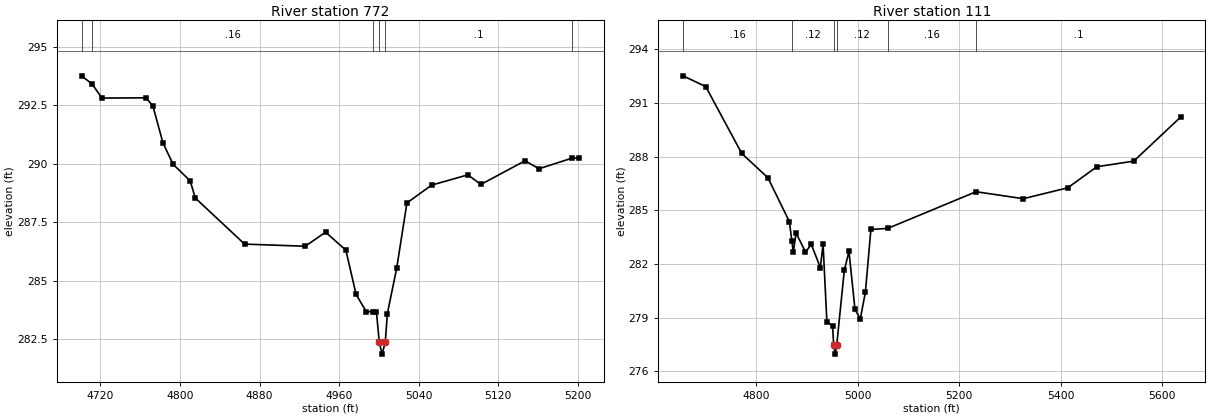
Type RM Length L Ch R = 1 ,772     ,661,661,661
BEGIN DESCRIPTION:
Mapping XS d0b67720
END DESCRIPTION:
XS GIS Cut Line= 2
       3581322.1     10272719.74      3580832.56     10272615.58
#Sta/Elev= 30
  4701.1  293.75  4711.8  293.39  4721.5   292.8  4765.8  292.81  4772.7  292.47
  4782.9  290.88  4793.1  289.97  4810.3  289.26  4815.4  288.53    4865  286.56
    4926  286.47  4946.5  287.07  4966.9   286.3  4977.1  284.42  4987.4  283.67
  4993.9  283.68  4997.6  283.68  5000.5  282.36  5003.3  281.86  5006.5  282.36
  5008.6  283.59    5018  285.53  5028.3  288.32  5053.1  289.08  5089.6  289.52
  5102.7  289.11  5147.1  290.12  5161.2  289.78  5194.1  290.23  5201.6  290.24
#Mann= 6 ,-1 , 0
  4701.1      .1       0  4711.8     .16       0  4993.9      .1       0
  5000.5     .07       0  5006.5      .1       0  5194.1     .05       0
Bank Sta=5000.5,5006.5
XS Rating Curve= 0 ,0
Exp/Cntr=0.3,0.1

Type RM Length L Ch R = 1 ,111     ,0,0,0
BEGIN DESCRIPTION:
UNT04902 IN WICK 1.0
END DESCRIPTION:
XS GIS Cut Line= 5
        3581466.     10272635.78       3581436.5     10272469.14
      3581391.36     10272359.76      3581209.07     10272302.47
      3580786.26     10272574.52
#Sta/Elev= 30
  4655.3  292.52  4700.1  291.92  4771.2  288.18  4822.8  286.82  4865.1  284.37
  4870.1  283.27  4872.9  282.65  4878.3  283.73  4896.9  282.67  4908.4  283.09
  4926.2   281.8  4931.6   283.1  4939.1  278.76  4950.3  278.55  4952.5  277.46
  4955.3  276.96  4958.5  277.46  4973.5  281.65  4982.7   282.7  4994.5  279.46
    5005  278.93  5015.1  280.43  5025.9  283.93  5059.2  283.99  5233.4  286.04
  5326.5  285.65  5414.3  286.26  5471.8  287.44  5544.4  287.75  5636.7  290.21
#Mann= 6 ,-1 , 0
  4655.3     .16       0  4870.1     .12       0  4952.5     .07       0
  4958.5     .12       0  5059.2     .16       0  5233.4      .1       0
Bank Sta=4952.5,4958.5
XS Rating Curve= 0 ,0
Exp/Cntr=0.3,0.1

Chan Stop Cuts=-1
Use User Specified Reach Order=0
Composite Channel Slope=5