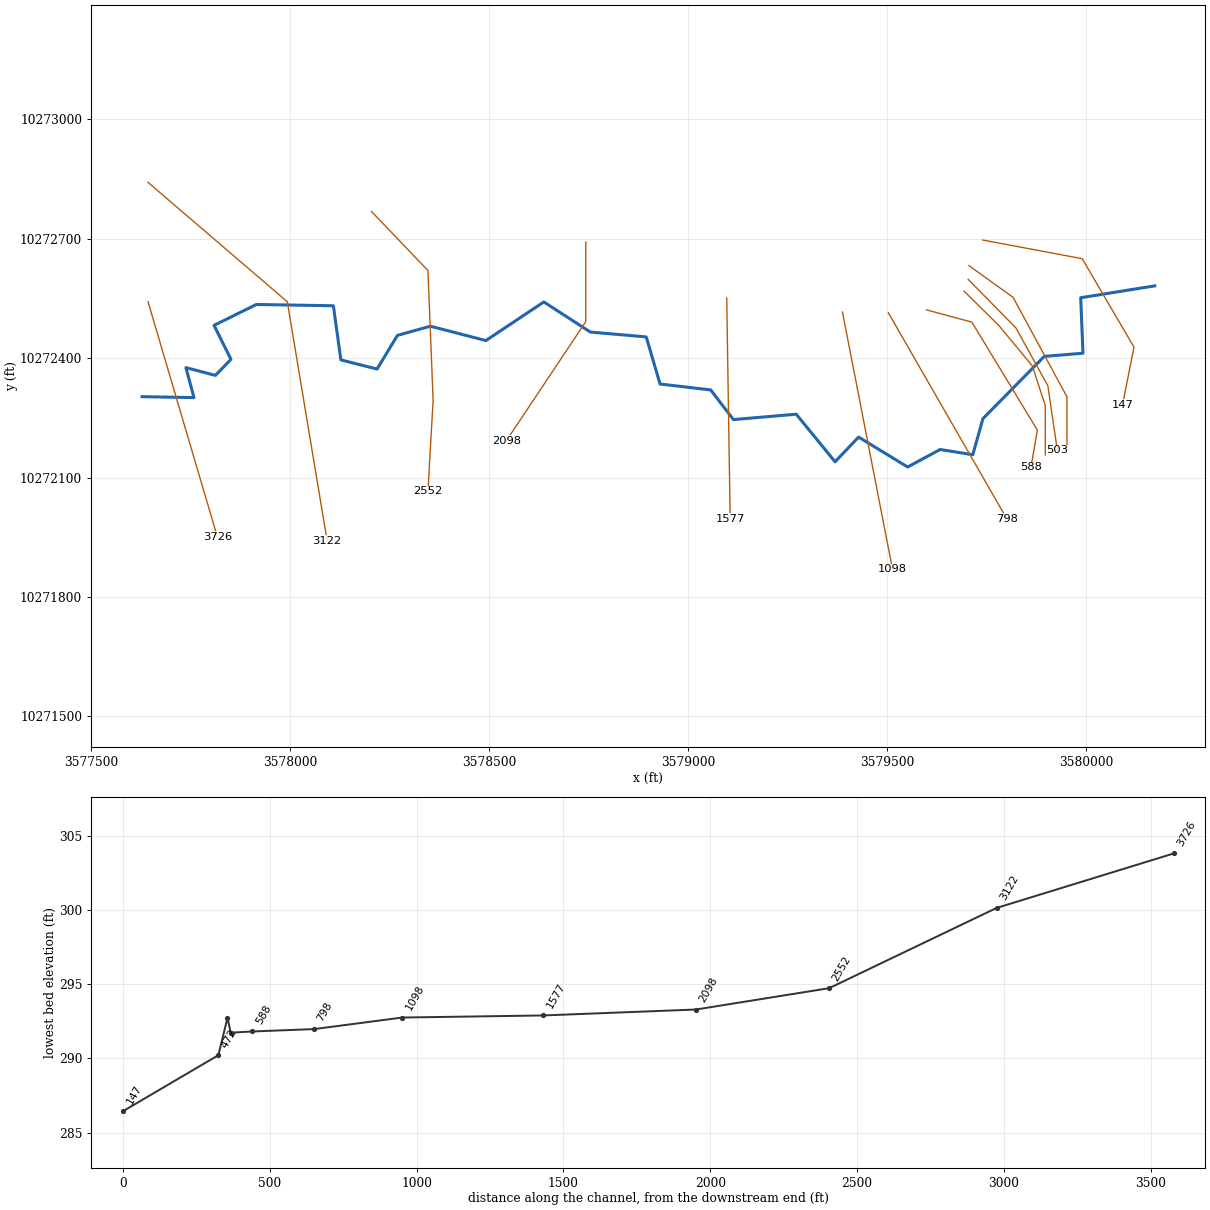
--- ALLCORNCRTRIB16.prj (project) ---

Proj Title=ALLCORN CREEK TRIB 16
Current Plan=p01
Default Exp/Contr=0.3,0.1
English Units
Geom File=g01
Flow File=f01
Plan File=p01
Y Axis Title=Elevation
X Axis Title(PF)=Main Channel Distance
X Axis Title(XS)=Station
BEGIN DESCRIPTION:
UNT04900 IN WICK
END DESCRIPTION:
DSS Export Rating Curves= 0
DSS Export Rating Curve Sorted= 0
DSS Export Volume Flow Curves= 0
DXF OffsetX= 0
DXF OffsetY= 0
DXF ScaleX= 1
DXF ScaleY= 10

--- ALLCORNCRTRIB16.p01 (plan) ---

Plan Title=Multiple Run
Short Identifier=Multiple
Geom File=g01
Flow File=f01
Subcritical Flow
K Sum by GR= 0
Std Step Tol= 0.01
Critical Tol= 0.01
Num of Std Step Trials= 20
Max Error Tol= 0.3
Flow Tol Ratio= 0.001
Split Flow NTrial= 30
Split Flow Tol= 0.02
Split Flow Ratio= 0.02
Log Output Level= 0
Friction Slope Method= 1
Unsteady Friction Slope Method= 2
Unsteady Bridges Friction Slope Method= 1
Parabolic Critical Depth
Global Vel Dist=  1 , 1 , 1
Global Log Level= 0
CheckData=True
Encroach Param= -1, 0, 0, 0
BEGIN DESCRIPTION:
Multiple Run
END DESCRIPTION:

--- ALLCORNCRTRIB16.f01 (steady flow) ---

Flow Title=Multiple
Program Version=4.10
Number of Profiles= 7
Profile Names=10-year,25-year,50-year,1pct_min,100-year,1pct_plu,500-year
River Rch & RM=UNT04900 IN WICK,Reach-1         ,3726
     341     444     526     457     618     835     854
River Rch & RM=ALLCORNCRTRIB16,Reach-1         ,3726
     341     444     526     457     618     835     854
Boundary for River Rch & Prof#=ALLCORNCRTRIB16,Reach-1         , 1
Up Type= 0
Dn Type= 3
Dn Slope=0.005
Boundary for River Rch & Prof#=ALLCORNCRTRIB16,Reach-1         , 2
Up Type= 0
Dn Type= 3
Dn Slope=0.005
Boundary for River Rch & Prof#=ALLCORNCRTRIB16,Reach-1         , 3
Up Type= 0
Dn Type= 3
Dn Slope=0.005
Boundary for River Rch & Prof#=ALLCORNCRTRIB16,Reach-1         , 4
Up Type= 0
Dn Type= 3
Dn Slope=0.005
Boundary for River Rch & Prof#=ALLCORNCRTRIB16,Reach-1         , 5
Up Type= 0
Dn Type= 3
Dn Slope=0.005
Boundary for River Rch & Prof#=ALLCORNCRTRIB16,Reach-1         , 6
Up Type= 0
Dn Type= 3
Dn Slope=0.005
Boundary for River Rch & Prof#=ALLCORNCRTRIB16,Reach-1         , 7
Up Type= 0
Dn Type= 3
Dn Slope=0.005
DSS Import GetInterval= 0
DSS Import GetPeak= 0
DSS Import FillOption= 0

--- ALLCORNCRTRIB16.g01 (geometry) ---

Geom Title=Existing Conditions
Program Version=4.10

River Reach=ALLCORNCRTRIB16 ,Reach-1
Reach XY= 30
      3577627.08     10272303.13      3577757.56     10272300.86
      3577737.33     10272376.16      3577811.47     10272356.62
      3577850.46       10272397.      3577808.01     10272482.39
      3577914.36     10272534.86      3578107.83     10272531.61
      3578126.77     10272395.56      3578217.66     10272372.56
      3578268.83     10272457.16      3578351.75     10272480.23
      3578491.08     10272444.13      3578636.73     10272541.17
      3578753.72     10272465.51      3578894.08     10272453.34
      3578928.85     10272334.95      3579056.14     10272320.04
      3579113.19     10272245.55      3579271.12     10272259.08
      3579368.74     10272139.45      3579427.79     10272201.63
      3579551.01     10272126.39      3579632.79     10272170.42
      3579714.72     10272157.23      3579740.41     10272248.12
      3579894.46     10272404.39      3579991.68     10272412.36
      3579985.94     10272551.77      3580172.11     10272581.64

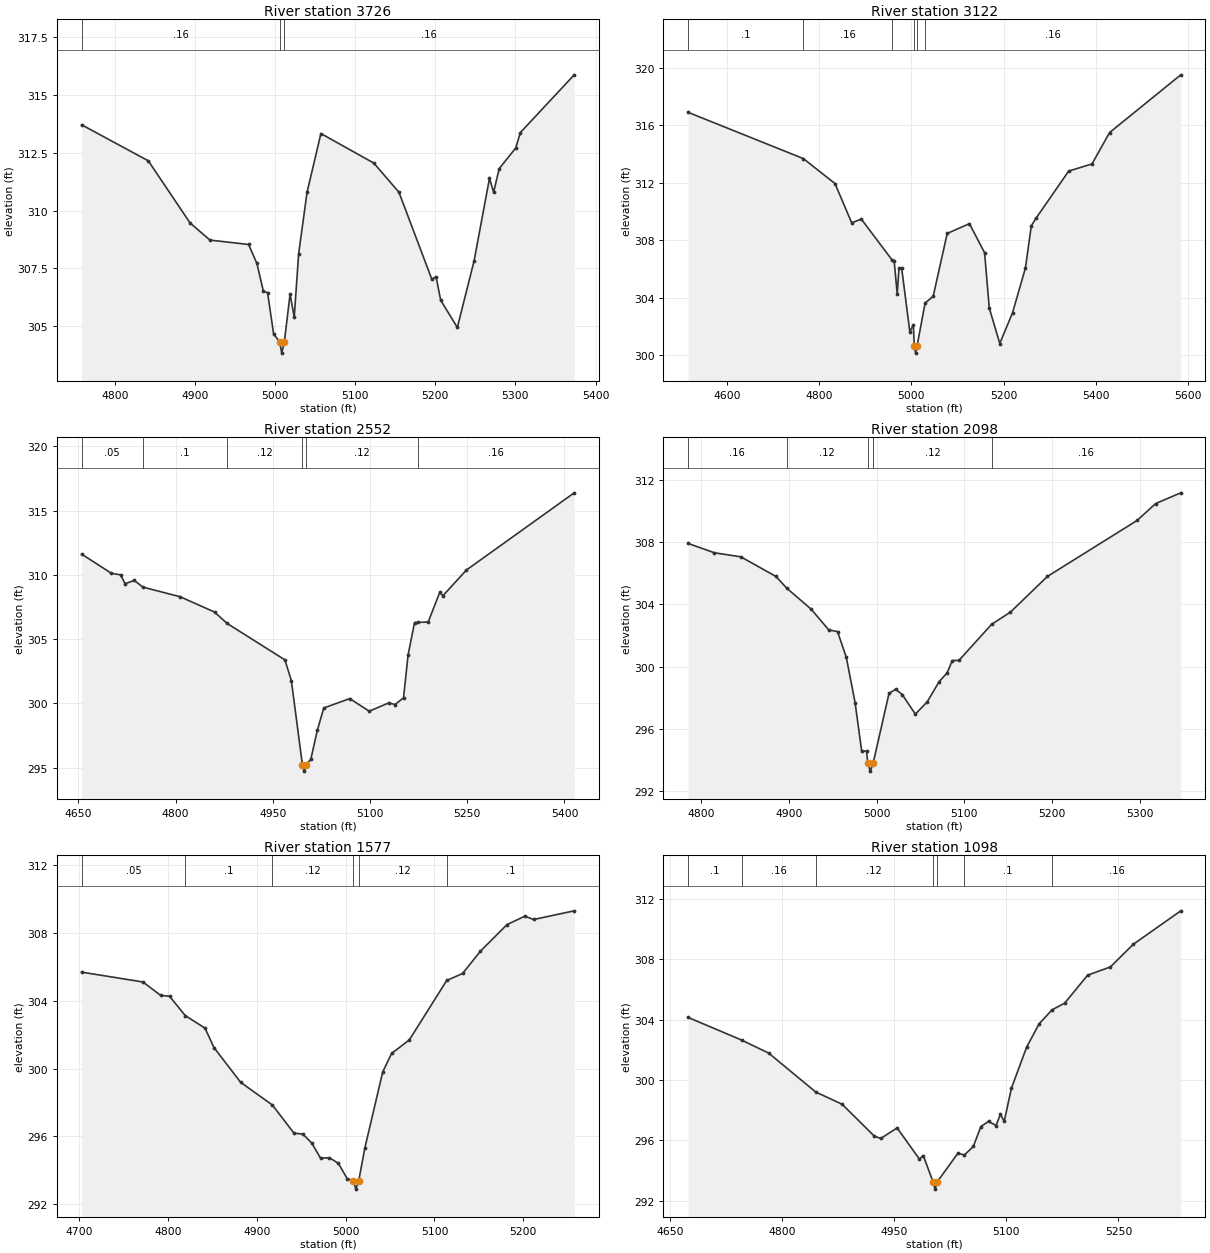
Type RM Length L Ch R = 1 ,3726    ,604,604,604
BEGIN DESCRIPTION:
UNT04900 IN WICK 7.0
END DESCRIPTION:
XS GIS Cut Line= 2
      3577642.11     10272541.63      3577816.03     10271951.73
#Sta/Elev= 30
  4758.4  313.71  4841.7  312.15  4893.9  309.46  4918.7  308.72  4966.9  308.53
  4977.3  307.71  4985.4   306.5  4990.6  306.45  4998.2  304.65  5005.6  304.33
  5008.3  303.83  5011.6  304.33  5018.7  306.38  5023.9  305.39  5029.4  308.13
  5039.9  310.79  5057.2  313.33  5123.3  312.05  5154.6  310.79  5195.7  307.02
  5200.9  307.14  5206.7  306.12  5227.5  304.94  5248.4  307.82  5267.6  311.39
  5272.8  310.79  5279.7  311.81  5300.5  312.71  5306.1  313.37  5373.4  315.87
#Mann= 3 ,-1 , 0
  4758.4     .16       0  5005.6     .07       0  5011.6     .16       0
Bank Sta=5005.6,5011.6
XS Rating Curve= 0 ,0
Exp/Cntr=0.3,0.1

Type RM Length L Ch R = 1 ,3122    ,570,570,570
BEGIN DESCRIPTION:
UNT04900 IN WICK 6.0
END DESCRIPTION:
XS GIS Cut Line= 3
      3577642.14     10272841.61      3577992.11     10272541.64
       3578092.1     10271941.65
#Sta/Elev= 30
  4515.4  316.91  4765.5  313.69  4834.2  311.95  4870.4  309.22  4891.3  309.48
  4958.6  306.61  4962.6  306.55  4969.2  304.28    4973  306.06  4978.9  306.06
  4996.6  301.64  5004.2  302.11  5006.3  300.65    5009  300.15  5012.3  300.65
  5029.7  303.63  5047.3  304.11  5077.7  308.48  5125.9  309.16  5158.8  307.14
    5169  303.29  5191.8  300.82  5219.6  302.97  5247.5  306.08  5260.2  309.01
  5270.3  309.53  5341.3  312.82    5392  313.32    5430   315.5  5584.6  319.52
#Mann= 6 ,-1 , 0
  4515.4      .1       0  4765.5     .16       0  4958.6     .12       0
  5006.3     .07       0  5012.3     .12       0  5029.7     .16       0
Bank Sta=5006.3,5012.3
XS Rating Curve= 0 ,0
Exp/Cntr=0.3,0.1

Type RM Length L Ch R = 1 ,2552    ,454,454,454
BEGIN DESCRIPTION:
UNT04900 IN WICK 5.0
END DESCRIPTION:
XS GIS Cut Line= 4
      3578203.72     10272768.43      3578345.53     10272620.17
      3578358.55     10272294.65      3578345.59     10272065.65
#Sta/Elev= 30
  4654.8  311.62  4700.9  310.12  4715.1     310    4722  309.31  4736.2  309.57
  4749.4  309.05  4806.9   308.3    4860  307.11  4879.3  306.23  4968.6  303.39
  4978.6  301.77  4995.6  295.24  4998.3  294.74  5001.6  295.24  5008.6  295.66
  5018.6   297.9  5028.6  299.65  5068.7  300.38  5098.7   299.4  5128.7  300.04
  5138.7  299.92  5151.7  300.44  5158.7  303.77  5168.7  306.29  5173.7  306.31
  5189.7  306.33  5207.5  308.63  5212.5  308.38  5248.8  310.38  5415.1  316.38
#Mann= 6 ,-1 , 0
  4654.8     .05       0  4749.4      .1       0  4879.3     .12       0
  4995.6     .07       0  5001.6     .12       0  5173.7     .16       0
Bank Sta=4995.6,5001.6
XS Rating Curve= 0 ,0
Exp/Cntr=0.3,0.1

Type RM Length L Ch R = 1 ,2098    ,521,521,521
BEGIN DESCRIPTION:
UNT04900 IN WICK 4.0
END DESCRIPTION:
XS GIS Cut Line= 3
      3578742.11     10272691.65      3578742.11     10272491.64
      3578542.08     10272191.61
#Sta/Elev= 30
  4785.6  307.92  4815.6  307.32  4845.6  307.06  4885.6   305.8  4897.6  305.06
  4925.6   303.7  4945.6  302.37  4955.6  302.26  4965.6  300.61  4975.6   297.7
  4983.1  294.59  4988.6  294.59  4990.1   293.8  4992.9   293.3  4996.1   293.8
  5014.2  298.29  5021.7  298.56  5029.2  298.22  5044.2  296.96  5057.7  297.75
  5071.2  299.04  5080.3  299.61  5086.3   300.4  5093.8  300.41    5131  302.73
  5152.4  303.51  5194.4   305.8  5296.6   309.4  5317.6  310.48  5346.2  311.17
#Mann= 5 ,-1 , 0
  4785.6     .16       0  4897.6     .12       0  4990.1     .07       0
  4996.1     .12       0    5131     .16       0
Bank Sta=4990.1,4996.1
XS Rating Curve= 0 ,0
Exp/Cntr=0.3,0.1

Type RM Length L Ch R = 1 ,1577    ,479,479,479
BEGIN DESCRIPTION:
UNT04900 IN WICK 3.0
END DESCRIPTION:
XS GIS Cut Line= 2
      3579096.39     10272550.77      3579105.06     10271995.94
#Sta/Elev= 30
  4702.5  305.68  4771.6   305.1  4791.6  304.31  4801.6  304.26  4819.3  303.12
  4841.6  302.38  4851.6  301.24  4881.7  299.19  4917.5  297.85  4941.7   296.2
  4951.7  296.14  4961.7  295.62  4971.7  294.72  4981.7  294.75  4991.7  294.42
  5001.7  293.52  5008.7   293.4  5011.4   292.9  5014.7   293.4  5021.7  295.35
  5041.7   299.8  5051.7  300.89  5071.7  301.69  5113.8  305.19  5131.7   305.6
  5151.7  306.91  5181.7  308.48  5201.7  308.97  5211.7  308.78  5257.4  309.29
#Mann= 6 ,-1 , 0
  4702.5     .05       0  4819.3      .1       0  4917.5     .12       0
  5008.7     .07       0  5014.7     .12       0  5113.8      .1       0
Bank Sta=5008.7,5014.7
XS Rating Curve= 0 ,0
Exp/Cntr=0.3,0.1

Type RM Length L Ch R = 1 ,1098    ,300,300,300
BEGIN DESCRIPTION:
UNT04900 IN WICK 2.0
END DESCRIPTION:
XS GIS Cut Line= 2
       3579387.2     10272515.97      3579513.06     10271869.31
#Sta/Elev= 30
  4674.5  304.15  4745.9  302.65  4782.3  301.78  4845.2   299.2  4880.5  298.39
  4923.4  296.28  4932.1  296.12    4954  296.82  4983.8  294.75  4988.9  294.99
  5001.9  293.26  5004.7  292.76  5007.9  293.26  5035.4  295.15  5043.8  295.02
  5055.9  295.59    5066  296.91  5076.2  297.25  5086.4  296.98  5092.1  297.73
  5097.2  297.25  5106.8  299.45  5127.2  302.18  5143.8  303.72  5161.1  304.65
  5178.1   305.1  5208.7  306.95  5239.2   307.5  5269.8     309  5333.3  311.22
#Mann= 7 ,-1 , 0
  4674.5      .1       0  4745.9     .16       0  4845.2     .12       0
  5001.9     .07       0  5007.9     .12       0  5043.8      .1       0
  5161.1     .16       0
Bank Sta=5001.9,5007.9
XS Rating Curve= 0 ,0
Exp/Cntr=0.3,0.1

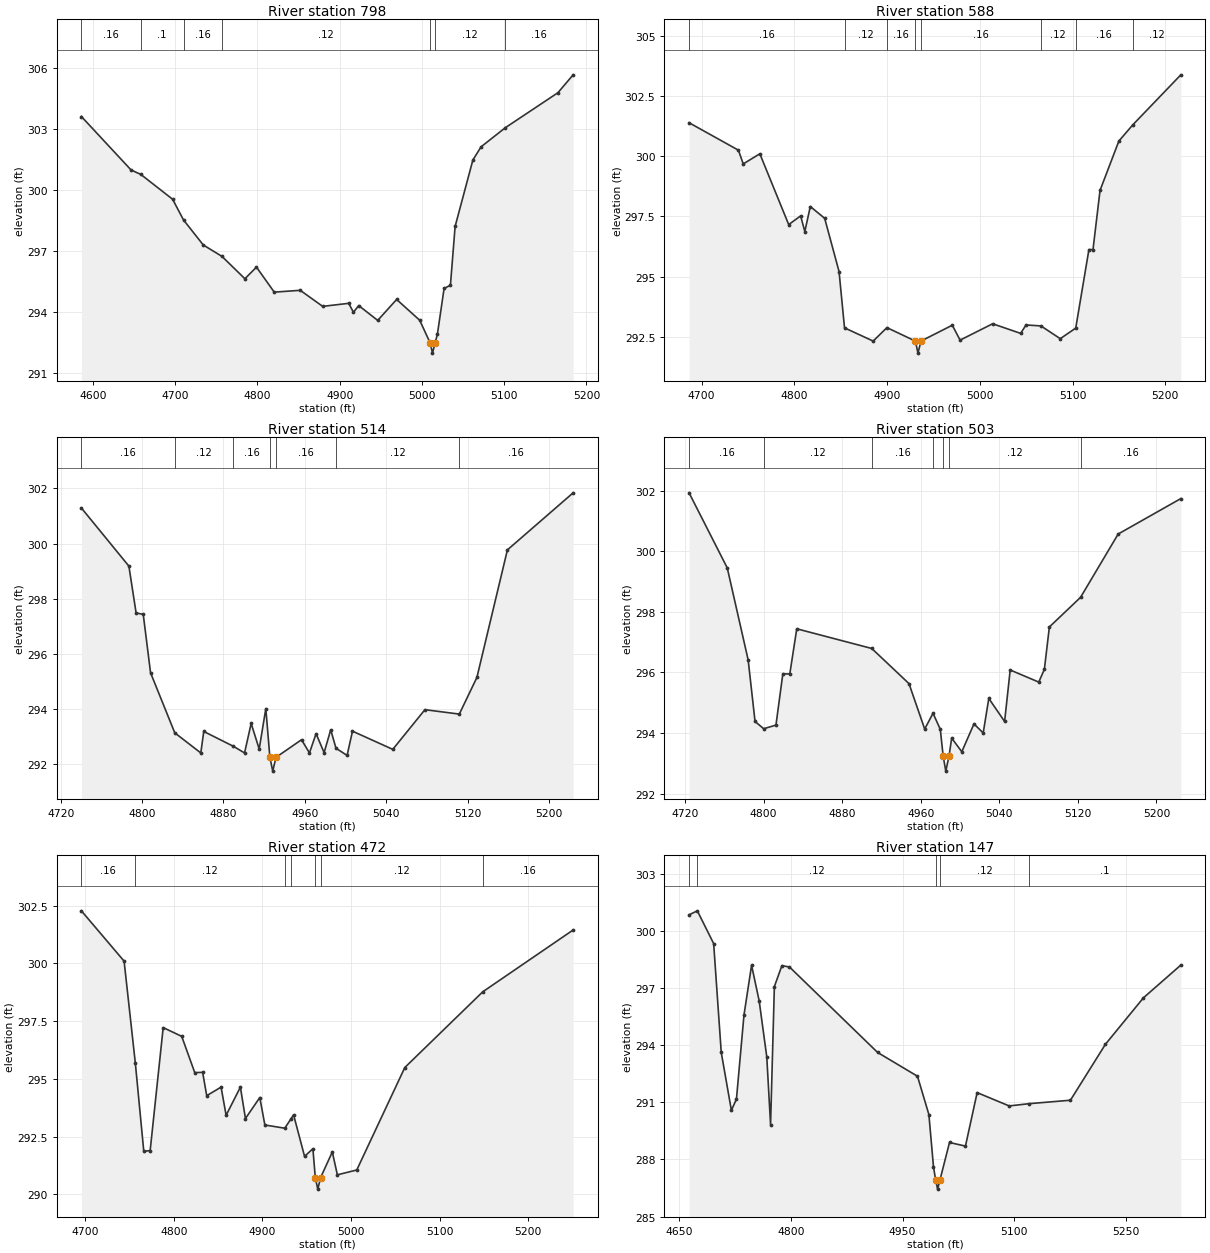
Type RM Length L Ch R = 1 ,798     ,210,210,210
BEGIN DESCRIPTION:
Mapping XS 39951f6e
END DESCRIPTION:
XS GIS Cut Line= 2
      3579502.55     10272513.98      3579800.55     10271995.64
#Sta/Elev= 30
  4585.9  303.62  4646.3  300.99  4658.2  300.77  4696.8  299.55  4710.1  298.53
  4734.1   297.3  4756.8  296.74  4784.7  295.64  4798.8  296.21  4820.4  294.98
    4852  295.07  4879.3  294.28  4910.9  294.43  4916.7  293.99  4923.1  294.32
  4946.2  293.59  4969.2  294.62  4997.2   293.6    5010  292.48  5012.8  291.98
    5016  292.48  5018.8  292.92  5026.9  295.16  5034.6  295.32  5040.3  298.21
  5061.9  301.48  5071.9  302.13  5101.4  303.07  5165.3  304.79  5183.8  305.67
#Mann= 7 ,-1 , 0
  4585.9     .16       0  4658.2      .1       0  4710.1     .16       0
  4756.8     .12       0    5010     .07       0    5016     .12       0
  5101.4     .16       0
Bank Sta=5010,5016
XS Rating Curve= 0 ,0
Exp/Cntr=0.3,0.1

Type RM Length L Ch R = 1 ,588     ,74,74,74
BEGIN DESCRIPTION:
Mapping XS f8c098df
END DESCRIPTION:
XS GIS Cut Line= 4
      3579598.41     10272521.24      3579712.42     10272490.47
      3579877.07     10272219.07      3579860.93     10272125.79
#Sta/Elev= 30
  4686.5  301.39  4739.7  300.25  4744.9  299.68  4762.8   300.1  4793.9  297.16
  4806.8  297.52  4811.3  296.87  4817.2  297.91  4832.7  297.42  4848.2  295.21
  4854.1  292.87    4885  292.32  4899.8  292.88  4930.5  292.32  4933.3  291.82
  4936.5  292.32  4970.3  292.98  4978.7  292.36  5013.8  293.04    5044  292.64
  5049.8  292.99  5065.9  292.95  5086.7  292.42  5103.4  292.86  5117.6  296.12
    5122  296.12  5129.6  298.58  5149.9  300.63  5165.1  301.31  5216.7  303.38
#Mann= 8 ,-1 , 0
  4686.5     .16       0  4854.1     .12       0  4899.8     .16       0
  4930.5     .07       0  4936.5     .16       0  5065.9     .12       0
  5103.4     .16       0  5165.1     .12       0
Bank Sta=4930.5,4936.5
XS Rating Curve= 0 ,0
Exp/Cntr=0.3,0.1

Type RM Length L Ch R = 1 ,514     ,11,11,11
BEGIN DESCRIPTION:
Mapping XS 10118a3a
END DESCRIPTION:
XS GIS Cut Line= 5
      3579692.76     10272568.35      3579779.71     10272482.55
      3579864.34     10272380.55       3579896.9     10272280.72
       3579896.9     10272157.02
#Sta/Elev= 30
  4740.4  301.29  4787.1  299.18  4794.2  297.48  4801.2  297.43  4808.4  295.31
  4832.2  293.13  4857.8   292.4  4860.7  293.18  4889.9  292.64  4900.8   292.4
  4907.3  293.47  4915.2  292.54  4921.7  294.01  4925.7  292.24  4928.5  291.74
  4931.7  292.24  4956.8  292.88  4964.6   292.4  4971.1   293.1    4979  292.41
  4985.5  293.24  4990.7  292.57  5001.6  292.31  5006.9  293.19  5046.5  292.53
  5078.1  293.97  5111.9  293.81  5129.2  295.14  5159.2  299.77  5223.8  301.84
#Mann= 7 ,-1 , 0
  4740.4     .16       0  4832.2     .12       0  4889.9     .16       0
  4925.7     .07       0  4931.7     .16       0  4990.7     .12       0
  5111.9     .16       0
Bank Sta=4925.7,4931.7
XS Rating Curve= 0 ,0
Exp/Cntr=0.3,0.1

Type RM Length L Ch R = 1 ,503     ,31,31,31
BEGIN DESCRIPTION:
Mapping XS 3d8a4cdb
END DESCRIPTION:
XS GIS Cut Line= 4
      3579703.19     10272597.85      3579823.11     10272476.04
      3579903.41     10272330.64      3579927.19      10272168.5
#Sta/Elev= 30
    4724  301.93  4762.9  299.45  4784.2  296.41  4791.2  294.38    4800  294.14
  4812.5  294.26  4819.5  295.95  4826.6  295.95  4833.7  297.44  4910.1  296.79
    4948  295.63    4964  294.13  4972.5  294.65  4979.9  294.12  4982.8  293.24
  4985.5  292.74  4988.8  293.24  4991.5  293.83  5001.8  293.38  5014.2   294.3
  5023.6     294  5029.3  295.14  5045.4  294.38  5051.1  296.08  5080.2  295.68
  5085.9   296.1    5091   297.5  5122.8  298.48  5161.1  300.57  5224.9  301.74
#Mann= 7 ,-1 , 0
    4724     .16       0    4800     .12       0  4910.1     .16       0
  4972.5     .12       0  4982.8     .07       0  4988.8     .12       0
  5122.8     .16       0
Bank Sta=4982.8,4988.8
XS Rating Curve= 0 ,0
Exp/Cntr=0.3,0.1

Type RM Length L Ch R = 1 ,472     ,325,325,325
BEGIN DESCRIPTION:
Mapping XS 1890f742
END DESCRIPTION:
XS GIS Cut Line= 4
      3579704.94     10272632.56      3579816.05      10272552.7
      3579951.47      10272302.7      3579951.47     10272169.05
#Sta/Elev= 30
  4695.8  302.28    4744   300.1  4756.7  295.67  4766.2  291.86  4773.4  291.89
  4788.1  297.22    4809  296.84  4823.7  295.27  4832.6  295.28  4837.2  294.27
  4853.4  294.64  4859.1  293.42  4875.2  294.64  4880.9  293.28  4897.1  294.19
  4902.8     293  4925.3  292.86  4931.8  293.24  4935.2  293.44  4947.6  291.64
    4957  291.97  4959.7  290.72  4962.5  290.22  4965.7  290.72  4978.9  291.83
  4984.6  290.84  5006.5  291.05  5060.7  295.49  5148.6  298.77  5250.6  301.45
#Mann= 7 ,-1 , 0
  4695.8     .16       0  4756.7     .12       0  4925.3     .16       0
  4931.8     .12       0  4959.7     .07       0  4965.7     .12       0
  5148.6     .16       0
Bank Sta=4959.7,4965.7
XS Rating Curve= 0 ,0
Exp/Cntr=0.3,0.1

Type RM Length L Ch R = 1 ,147     ,0,0,0
BEGIN DESCRIPTION:
UNT04900 IN WICK 1.0
END DESCRIPTION:
XS GIS Cut Line= 4
      3579739.64      10272696.8      3579989.67     10272649.92
      3580119.87      10272427.7      3580091.02     10272282.38
#Sta/Elev= 30
  4663.5  300.85  4674.6  301.06  4696.5  299.34  4706.7  293.62  4720.3  290.58
  4727.1  291.17  4737.2  295.58  4747.4   298.2  4757.6  296.33  4767.8  293.39
  4772.9  289.83    4778  297.08  4788.1  298.18  4798.3  298.11  4916.6  293.62
  4970.1  292.37  4985.4  290.36  4991.6  287.61  4994.4  286.94  4997.1  286.44
  5000.4  286.94  5013.1  288.89  5034.5   288.7  5050.2  291.51  5093.2  290.81
  5120.2  290.93  5175.4  291.11  5222.4  294.05  5273.4  296.49  5323.6  298.21
#Mann= 5 ,-1 , 0
  4663.5     .16       0  4674.6     .12       0  4994.4     .07       0
  5000.4     .12       0  5120.2      .1       0
Bank Sta=4994.4,5000.4
XS Rating Curve= 0 ,0
Exp/Cntr=0.3,0.1

Chan Stop Cuts=-1
Use User Specified Reach Order=0
Composite Channel Slope=5