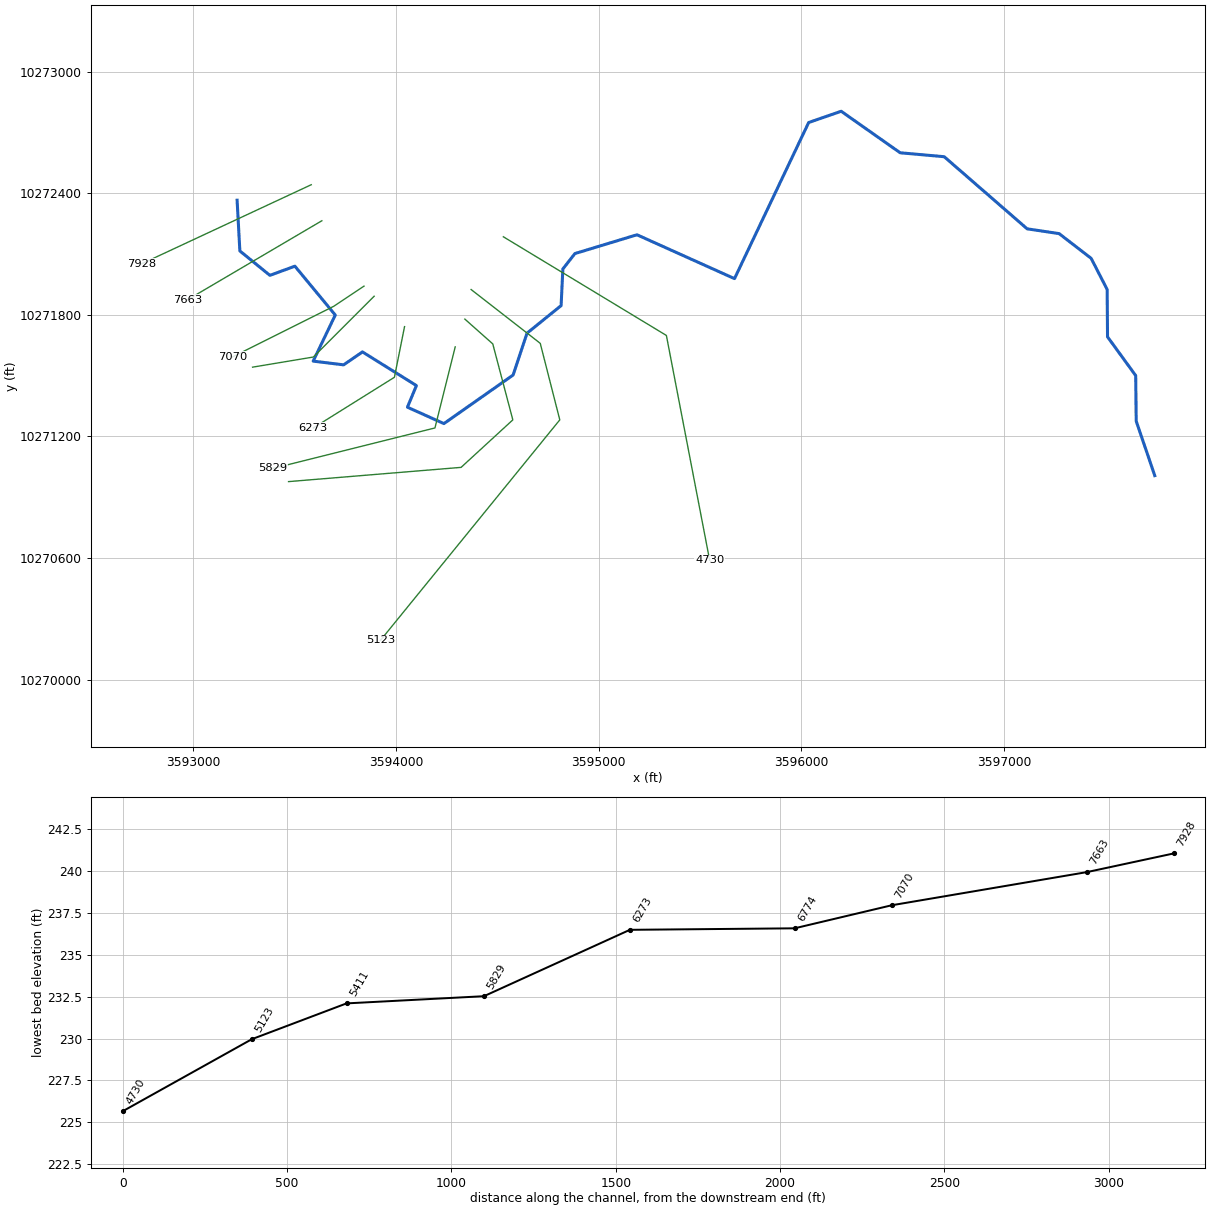
--- ALLCORNCRTRIB6.prj (project) ---

Proj Title=ALLCORN CREEK TRIB 6
Current Plan=p01
Default Exp/Contr=0.3,0.1
English Units
Geom File=g01
Flow File=f01
Plan File=p01
Y Axis Title=Elevation
X Axis Title(PF)=Main Channel Distance
X Axis Title(XS)=Station
BEGIN DESCRIPTION:
UNT0473 IN WICK
END DESCRIPTION:
DSS Export Rating Curves= 0
DSS Export Rating Curve Sorted= 0
DSS Export Volume Flow Curves= 0
DXF Filename=UNT0473 IN WICK.
DXF OffsetX= 0
DXF OffsetY= 0
DXF ScaleX= 1
DXF ScaleY= 10

--- ALLCORNCRTRIB6.p01 (plan) ---

Plan Title=Multiple Run
Short Identifier=Multiple
Geom File=g01
Flow File=f01
Subcritical Flow
K Sum by GR= 0
Std Step Tol= 0.01
Critical Tol= 0.01
Num of Std Step Trials= 20
Max Error Tol= 0.3
Flow Tol Ratio= 0.001
Split Flow NTrial= 30
Split Flow Tol= 0.02
Split Flow Ratio= 0.02
Log Output Level= 0
Friction Slope Method= 1
Unsteady Friction Slope Method= 2
Unsteady Bridges Friction Slope Method= 1
Parabolic Critical Depth
Global Vel Dist=  1 , 1 , 1
Global Log Level= 0
CheckData=True
Encroach Param= -1, 0, 0, 0
BEGIN DESCRIPTION:
Multiple Run
END DESCRIPTION:

--- ALLCORNCRTRIB6.f01 (steady flow) ---

Flow Title=Multiple
Program Version=4.10
Number of Profiles= 7
Profile Names=10-year,25-year,50-year,1pct_min,100-year,1pct_plu,500-year
River Rch & RM=UNT0473 IN WICK,Reach-1         ,7928
     556     746     899     795    1076    1455    1541
River Rch & RM=UNT0473 IN WICK,Reach-1         ,6774
     743    1008    1224    1088    1471    1990    2132
River Rch & RM=ALLCORNCRTRIB6,Reach-1         ,7928
     556     746     899     795    1076    1455    1541
River Rch & RM=ALLCORNCRTRIB6,Reach-1         ,6774
     743    1008    1224    1088    1471    1990    2132
Boundary for River Rch & Prof#=ALLCORNCRTRIB6,Reach-1         , 1
Up Type= 0
Dn Type= 3
Dn Slope=0.005
Boundary for River Rch & Prof#=ALLCORNCRTRIB6,Reach-1         , 2
Up Type= 0
Dn Type= 3
Dn Slope=0.005
Boundary for River Rch & Prof#=ALLCORNCRTRIB6,Reach-1         , 3
Up Type= 0
Dn Type= 3
Dn Slope=0.005
Boundary for River Rch & Prof#=ALLCORNCRTRIB6,Reach-1         , 4
Up Type= 0
Dn Type= 3
Dn Slope=0.005
Boundary for River Rch & Prof#=ALLCORNCRTRIB6,Reach-1         , 5
Up Type= 0
Dn Type= 3
Dn Slope=0.005
Boundary for River Rch & Prof#=ALLCORNCRTRIB6,Reach-1         , 6
Up Type= 0
Dn Type= 3
Dn Slope=0.005
Boundary for River Rch & Prof#=ALLCORNCRTRIB6,Reach-1         , 7
Up Type= 0
Dn Type= 3
Dn Slope=0.005
DSS Import GetInterval= 0
DSS Import GetPeak= 0
DSS Import FillOption= 0

--- ALLCORNCRTRIB6.g01 (geometry) ---

Geom Title=Existing Conditions
Program Version=4.10

River Reach=ALLCORNCRTRIB6  ,Reach-1
Reach XY= 30
      3593215.79     10272365.52      3593229.38     10272115.11
      3593377.74     10271994.62      3593500.95     10272039.94
      3593700.26     10271798.81      3593591.23     10271571.38
      3593741.39     10271552.99      3593834.46     10271616.85
      3594100.68     10271450.67      3594056.34     10271343.97
      3594236.36     10271263.07      3594577.69     10271502.63
      3594646.44     10271709.23      3594814.75     10271845.43
      3594823.33      10272026.1      3594882.92     10272102.22
      3595189.17     10272194.93      3595670.45     10271978.47
      3596036.43     10272748.89      3596196.85     10272804.45
      3596487.97     10272599.59      3596705.33     10272580.14
       3597114.7     10272224.24      3597272.34     10272200.63
      3597430.33     10272078.75      3597509.49     10271924.93
       3597511.3     10271691.25      3597650.31     10271500.03
      3597652.79     10271275.45      3597744.42     10271006.16

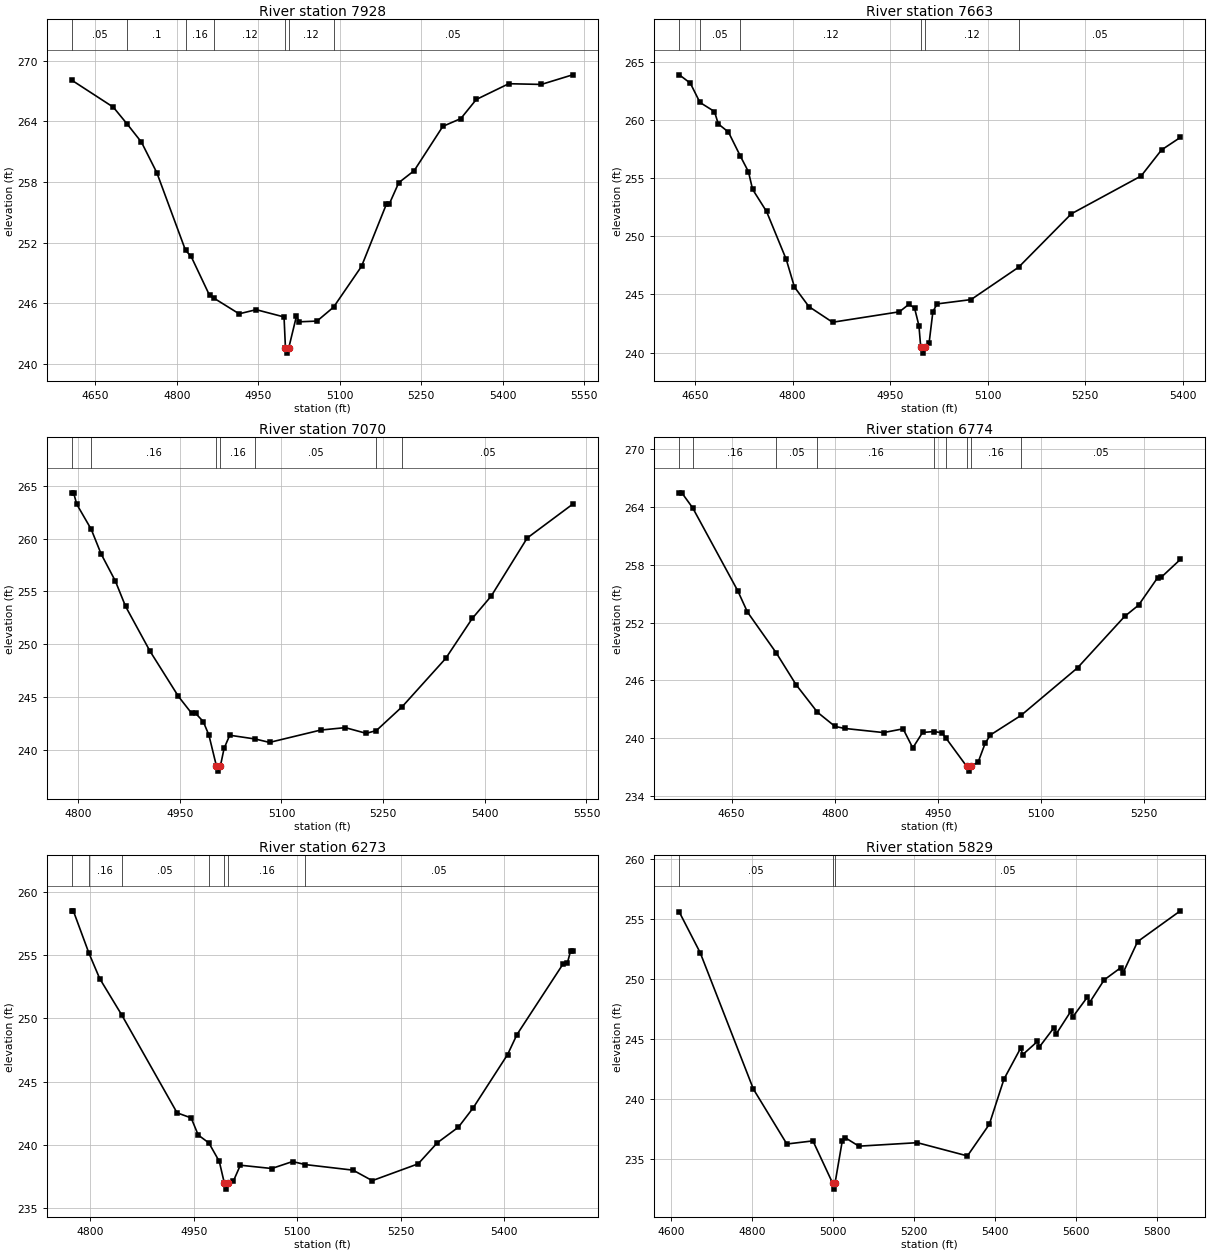
Type RM Length L Ch R = 1 ,7928    ,265,265,265
BEGIN DESCRIPTION:
UNT0473 IN WICK 8.0
END DESCRIPTION:
XS GIS Cut Line= 2
      3593581.69     10272441.94      3592745.54     10272052.02
#Sta/Elev= 30
  4606.1  268.09  4682.9  265.41  4708.9  263.71  4734.7  261.95  4763.1  258.92
  4815.9  251.24  4826.2  250.64  4860.1  246.79  4868.8  246.49  4914.6  244.96
    4946  245.37  4997.3  244.65  4999.9  241.57  5002.6  241.07  5005.9  241.57
  5020.1  244.72  5025.7  244.17    5058  244.24  5088.5  245.62    5140  249.66
  5185.7   255.8  5191.2  255.84  5208.6  257.94    5237  259.13  5289.7  263.51
  5322.8  264.28  5351.3  266.17  5411.1  267.73  5471.1  267.66  5528.7  268.61
#Mann= 7 ,-1 , 0
  4606.1     .05       0  4708.9      .1       0  4815.9     .16       0
  4868.8     .12       0  4999.9     .07       0  5005.9     .12       0
  5088.5     .05       0
Bank Sta=4999.9,5005.9
XS Rating Curve= 0 ,0
Exp/Cntr=0.3,0.1

Type RM Length L Ch R = 1 ,7663    ,593,593,593
BEGIN DESCRIPTION:
Mapping XS eabec873
END DESCRIPTION:
XS GIS Cut Line= 2
      3593633.77     10272263.98      3592969.73     10271873.37
#Sta/Elev= 30
  4625.8  263.92  4642.7   263.2  4657.5  261.54  4679.8  260.76  4685.7  259.69
  4701.3  258.99  4719.8   256.9  4732.1  255.57  4738.4  254.06  4759.9  252.15
  4790.2  248.02  4802.8  245.64    4825  243.96  4861.4  242.61  4964.2  243.51
  4978.6  244.15  4987.4  243.85  4994.2  242.32    4997  240.45  4999.8  239.95
    5003  240.45  5009.9  240.85  5015.7  243.53  5022.2  244.19  5074.3  244.56
  5147.5  247.35  5228.6  251.95  5335.9  255.21  5367.2  257.45  5396.2  258.53
#Mann= 6 ,-1 , 0
  4625.8     .16       0  4657.5     .05       0  4719.8     .12       0
    4997     .07       0    5003     .12       0  5147.5     .05       0
Bank Sta=4997,5003
XS Rating Curve= 0 ,0
Exp/Cntr=0.3,0.1

Type RM Length L Ch R = 1 ,7070    ,296,296,296
BEGIN DESCRIPTION:
UNT0473 IN WICK 7.0
END DESCRIPTION:
XS GIS Cut Line= 3
      3593842.07     10271941.62      3593692.11     10271841.64
      3593192.15     10271591.66
#Sta/Elev= 30
  4790.4  264.33  4793.4  264.33  4797.9  263.26  4819.4  260.87  4833.9  258.55
    4855  255.97    4870  253.58    4906  249.34  4948.1  245.04  4967.6  243.44
  4973.4  243.44  4984.6  242.67    4993  241.38    5004  238.47  5006.7  237.97
    5010  238.47  5015.4  240.13  5023.7  241.37  5061.6  241.01  5082.4  240.69
  5157.9  241.86  5194.2  242.09    5225  241.55    5240  241.81  5278.1  244.07
  5342.4  248.65  5381.5  252.43  5409.5  254.55  5462.6  260.05  5529.6  263.25
#Mann= 7 ,-1 , 0
  4790.4     .05       0  4819.4     .16       0    5004     .07       0
    5010     .16       0  5061.6     .05       0    5240     .16       0
  5278.1     .05       0
Bank Sta=5004,5010
XS Rating Curve= 0 ,0
Exp/Cntr=0.3,0.1

Type RM Length L Ch R = 1 ,6774    ,501,501,501
BEGIN DESCRIPTION:
UNT0473 IN WICK 6.0
END DESCRIPTION:
XS GIS Cut Line= 3
      3593892.12     10271891.66      3593592.11     10271591.64
      3593292.13     10271541.65
#Sta/Elev= 30
    4574  265.47  4577.6  265.47  4593.5   263.9  4658.9  255.31    4673   253.1
    4715  248.85  4743.7  245.56  4774.8   242.7  4800.3  241.23  4814.4  241.02
    4871  240.59  4899.3  240.98  4913.4     239  4927.6   240.6  4944.1   240.7
  4955.9  240.57  4961.7  240.01  4991.7  237.09  4994.5  236.59  4997.7  237.09
  5008.4  237.52  5018.6  239.48  5026.2  240.34  5070.7  242.37  5152.9  247.31
  5221.3  252.64  5241.6  253.81  5269.5  256.68  5274.5   256.7  5302.4  258.56
#Mann= 9 ,-1 , 0
    4574     .05       0  4593.5     .16       0    4715     .05       0
  4774.8     .16       0  4944.1     .05       0  4961.7     .16       0
  4991.7     .07       0  4997.7     .16       0  5070.7     .05       0
Bank Sta=4991.7,4997.7
XS Rating Curve= 0 ,0
Exp/Cntr=0.3,0.1

Type RM Length L Ch R = 1 ,6273    ,444,444,444
BEGIN DESCRIPTION:
UNT0473 IN WICK 5.0
END DESCRIPTION:
XS GIS Cut Line= 3
       3594042.1     10271741.64      3593992.11     10271491.64
      3593592.14     10271241.67
#Sta/Elev= 30
    4773   258.5  4775.5   258.5  4798.1  255.16  4813.8  253.14  4845.7  250.27
    4926  242.53  4946.4  242.13  4956.6  240.78  4972.1  240.15  4987.2  238.69
  4994.4     237  4997.1   236.5  5000.4     237  5007.6  237.13  5017.7  238.39
  5063.3  238.13  5093.4  238.68  5111.9  238.44  5181.2     238    5209  237.17
  5275.6   238.5  5303.3  240.16    5334   241.4  5355.2  242.91  5405.3  247.14
  5418.9  248.72  5486.1  254.33    5492  254.38  5496.7  255.34  5499.6  255.34
#Mann= 7 ,-1 , 0
    4773     .05       0  4798.1     .16       0  4845.7     .05       0
  4972.1     .16       0  4994.4     .07       0  5000.4     .16       0
  5111.9     .05       0
Bank Sta=4994.4,5000.4
XS Rating Curve= 0 ,0
Exp/Cntr=0.3,0.1

Type RM Length L Ch R = 1 ,5829    ,418,418,418
BEGIN DESCRIPTION:
UNT0473 IN WICK 4.0
END DESCRIPTION:
XS GIS Cut Line= 3
       3594292.1     10271641.62      3594192.11     10271241.64
      3593392.12     10271041.65
#Sta/Elev= 30
  4620.9  255.55  4672.4  252.18  4803.8  240.84  4886.3  236.28  4950.7  236.54
  4999.3  233.03    5002  232.53  5005.3  233.03  5022.9  236.49  5030.6   236.8
  5064.1   236.1  5208.4  236.39  5332.1  235.29  5386.2  237.92  5422.3  241.67
  5463.5  244.25  5468.7  243.71  5504.8   244.8  5509.9  244.35    5546  245.96
  5551.2  245.42  5587.2   247.3  5592.4  246.85  5628.5   248.5  5633.6  248.03
  5669.7  249.92  5710.9  250.94  5716.1  250.49  5752.2   253.1  5857.8  255.66
#Mann= 3 ,-1 , 0
  4620.9     .05       0  4999.3     .03       0  5005.3     .05       0
Bank Sta=4999.3,5005.3
XS Rating Curve= 0 ,0
Exp/Cntr=0.3,0.1

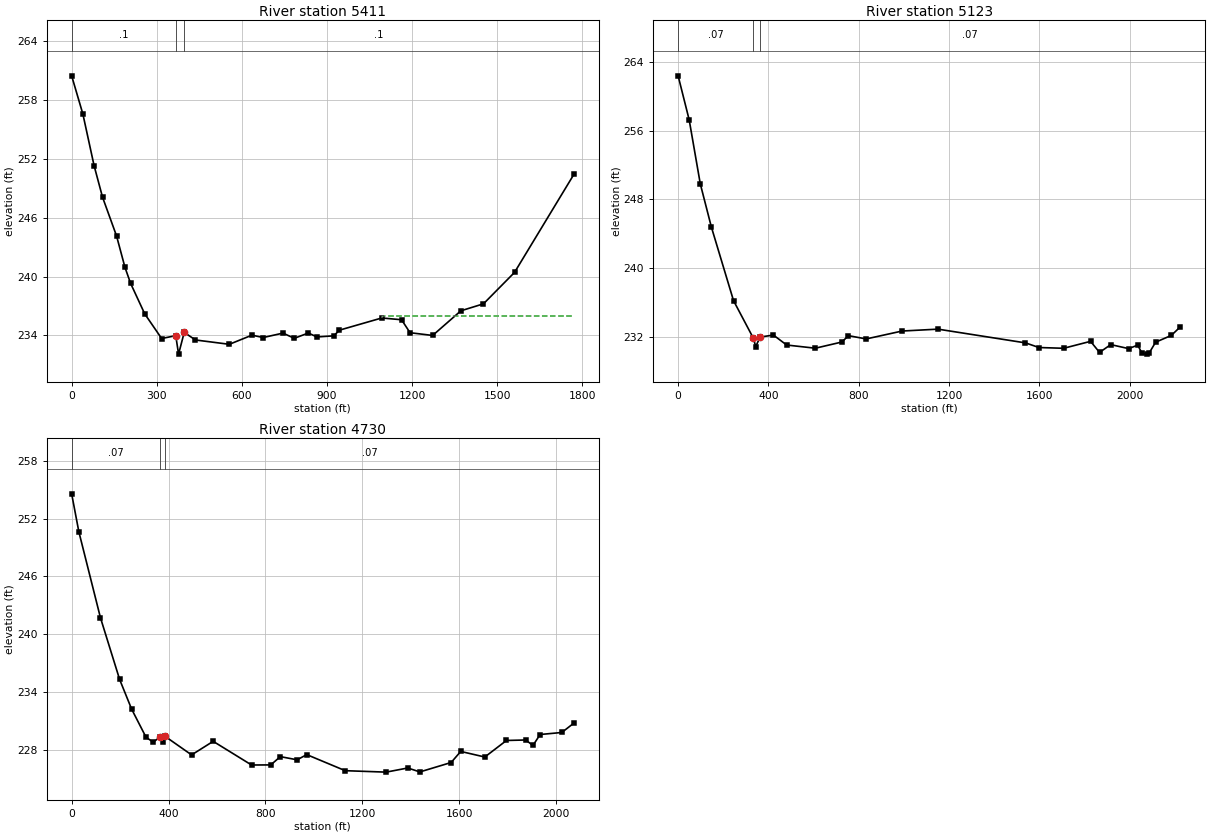
Type RM Length L Ch R = 1 ,5411    ,288,288,288
BEGIN DESCRIPTION:
UNT0473 IN WICK 1.0
END DESCRIPTION:
XS GIS Cut Line= 5
     3594339.479    10271778.853     3594477.499    10271656.457
     3594576.458    10271281.457     3594321.249    10271047.082
     3593469.687     10270976.77
#Sta/Elev= 30
       0  260.43   39.57  256.54   79.15  251.28  108.82  248.08  158.29  244.13
  187.97  240.93  207.86   239.3  257.58   236.2  317.25  233.69  366.97  233.98
  376.92   232.1  396.81  234.31  436.58  233.54  555.92   233.1  635.51  234.03
  675.31  233.79  744.97  234.24  784.77  233.71  834.52  234.25  864.37  233.85
  924.07  233.96  943.99  234.54 1093.33  235.78 1163.02   235.6 1192.89  234.28
 1272.53     234 1372.09  236.51 1451.74  237.22 1561.26  240.42 1770.33  250.39
#Mann= 3 , 0 , 0
       0      .1       0  366.97     .05       0  396.81      .1       0
#XS Ineff= 2 , 0
                         1092.59          235.95
Permanent Ineff=
       F       F
Bank Sta=366.97,396.81
XS Rating Curve= 0 ,0
Exp/Cntr=0.3,0.1

Type RM Length L Ch R = 1 ,5123    ,393,393,393
XS GIS Cut Line= 4
     3594370.729    10271924.686     3594711.874    10271659.061
     3594808.229    10271281.457     3593922.812    10270192.915
#Sta/Elev= 30
       0  262.38   49.09  257.24   98.18   249.8  147.27  244.77  245.44  236.19
   333.8  231.79  343.62  230.84  363.26  231.95  422.16  232.18  480.82  231.02
   607.9  230.65  725.21  231.37  754.53  232.11  833.07  231.73  992.08  232.65
  1151.1  232.87  1538.7  231.27 1598.33  230.73 1707.65  230.64 1826.91  231.45
 1866.67  230.16 1916.36  231.07 1995.87   230.6 2035.62  231.01  2055.5  230.04
 2075.38  229.96 2085.32  230.04 2115.13  231.35  2184.7  232.14 2224.45  233.14
#Mann= 3 , 0 , 0
       0     .07       0   333.8     .03       0  363.26     .07       0
Bank Sta=333.8,363.26
XS Rating Curve= 0 ,0
Exp/Cntr=0.3,0.1

Type RM Length L Ch R = 1 ,4730    ,0,0,0
XS GIS Cut Line= 3
     3594529.583    10272185.103      3595334.27    10271698.124
     3595547.812    10270588.749
#Sta/Elev= 30
       0  254.57   29.71  250.63  118.85   241.7  198.09  235.28  247.61   232.2
  307.04  229.28  336.75  228.76  366.47  229.33  376.37  228.82  386.28  229.36
  495.23  227.44  584.37  228.85  742.84  226.39  822.08   226.4  861.69  227.26
  931.03  226.93  970.71  227.47 1129.67   225.8 1298.57  225.65 1387.99  226.08
 1437.67  225.67 1566.83  226.65 1606.57   227.8 1705.92  227.22 1795.34  228.94
 1874.82  228.99 1904.63  228.42 1934.43  229.56 2023.85  229.77 2073.53  230.74
#Mann= 3 , 0 , 0
       0     .07       0  366.47     .03       0  386.28     .07       0
#XS Ineff= 2 , 0
       0                  390.33       0   228.8
Permanent Ineff=
       F       T
Bank Sta=366.47,386.28
XS Rating Curve= 0 ,0
Exp/Cntr=0.3,0.1

Chan Stop Cuts=-1
Use User Specified Reach Order=0
Composite Channel Slope=5