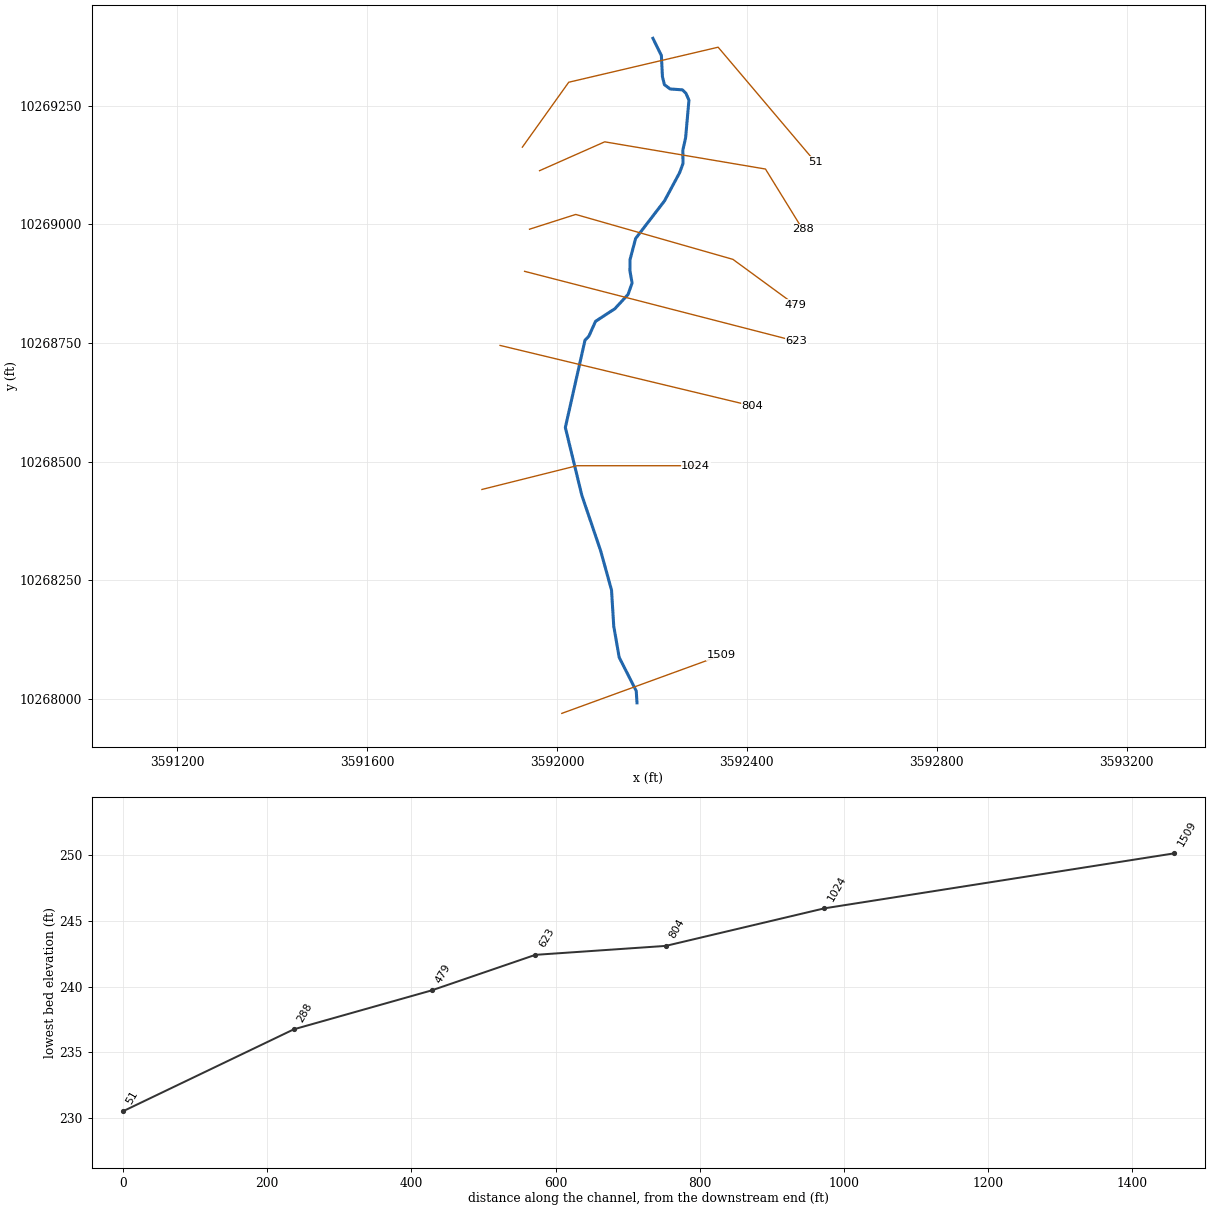
--- ALLCORNCRKTRIB7.prj (project) ---

Proj Title=ALLCORN CREEK TRIB 7
Current Plan=p01
Default Exp/Contr=0.3,0.1
English Units
Geom File=g01
Flow File=f01
Plan File=p01
Y Axis Title=Elevation
X Axis Title(PF)=Main Channel Distance
X Axis Title(XS)=Station
BEGIN DESCRIPTION:
UNT04919 IN WICK
END DESCRIPTION:
DSS Export Rating Curves= 0
DSS Export Rating Curve Sorted= 0
DSS Export Volume Flow Curves= 0
DXF Filename=UNT04919 IN WICK.
DXF OffsetX= 0
DXF OffsetY= 0
DXF ScaleX= 1
DXF ScaleY= 10

--- ALLCORNCRKTRIB7.p01 (plan) ---

Plan Title=Multiple Run
Short Identifier=Multiple
Geom File=g01
Flow File=f01
Subcritical Flow
K Sum by GR= 0
Std Step Tol= 0.01
Critical Tol= 0.01
Num of Std Step Trials= 20
Max Error Tol= 0.3
Flow Tol Ratio= 0.001
Split Flow NTrial= 30
Split Flow Tol= 0.02
Split Flow Ratio= 0.02
Log Output Level= 0
Friction Slope Method= 1
Unsteady Friction Slope Method= 2
Unsteady Bridges Friction Slope Method= 1
Parabolic Critical Depth
Global Vel Dist=  1 , 1 , 1
Global Log Level= 0
CheckData=True
Encroach Param= -1, 0, 0, 0
BEGIN DESCRIPTION:
Multiple Run
END DESCRIPTION:

--- ALLCORNCRKTRIB7.f01 (steady flow) ---

Flow Title=Multiple
Program Version=4.10
Number of Profiles= 7
Profile Names=10-year,25-year,50-year,1pct_min,100-year,1pct_plu,500-year
River Rch & RM=UNT04919 IN WICK,Reach-1         ,1509
     143     176     200     168     227     307     291
River Rch & RM=ALLCORNCRTRIB7,Reach-1         ,1509
     143     176     200     168     227     307     291
Boundary for River Rch & Prof#=ALLCORNCRTRIB7,Reach-1         , 1
Up Type= 0
Dn Type= 3
Dn Slope=0.015
Boundary for River Rch & Prof#=ALLCORNCRTRIB7,Reach-1         , 2
Up Type= 0
Dn Type= 3
Dn Slope=0.015
Boundary for River Rch & Prof#=ALLCORNCRTRIB7,Reach-1         , 3
Up Type= 0
Dn Type= 3
Dn Slope=0.015
Boundary for River Rch & Prof#=ALLCORNCRTRIB7,Reach-1         , 4
Up Type= 0
Dn Type= 3
Dn Slope=0.015
Boundary for River Rch & Prof#=ALLCORNCRTRIB7,Reach-1         , 5
Up Type= 0
Dn Type= 3
Dn Slope=0.015
Boundary for River Rch & Prof#=ALLCORNCRTRIB7,Reach-1         , 6
Up Type= 0
Dn Type= 3
Dn Slope=0.015
Boundary for River Rch & Prof#=ALLCORNCRTRIB7,Reach-1         , 7
Up Type= 0
Dn Type= 3
Dn Slope=0.015
DSS Import GetInterval= 0
DSS Import GetPeak= 0
DSS Import FillOption= 0

--- ALLCORNCRKTRIB7.g01 (geometry) ---

Geom Title=Existing Conditions
Program Version=4.10

River Reach=ALLCORNCRTRIB7  ,Reach-1
Reach XY= 30
      3592168.57      10267992.3      3592167.01      10268017.3
      3592131.07     10268088.13      3592119.62     10268153.76
      3592114.93      10268229.8      3592092.01     10268312.61
      3592052.43     10268429.28       3592017.7     10268572.17
      3592059.07     10268755.87      3592067.27     10268764.48
      3592081.22     10268795.63      3592122.04     10268822.28
      3592149.85     10268852.47      3592158.26     10268876.49
      3592153.66     10268902.07      3592153.98     10268925.82
      3592165.68     10268970.11      3592226.47     10269049.29
      3592258.21     10269108.48      3592265.49     10269127.95
      3592265.14     10269156.08      3592270.92     10269182.17
      3592277.99      10269261.3      3592271.82     10269275.65
      3592264.32     10269283.14      3592238.33     10269285.05
      3592226.33     10269294.01      3592222.14      10269311.2
      3592219.92     10269355.49      3592202.11     10269391.64

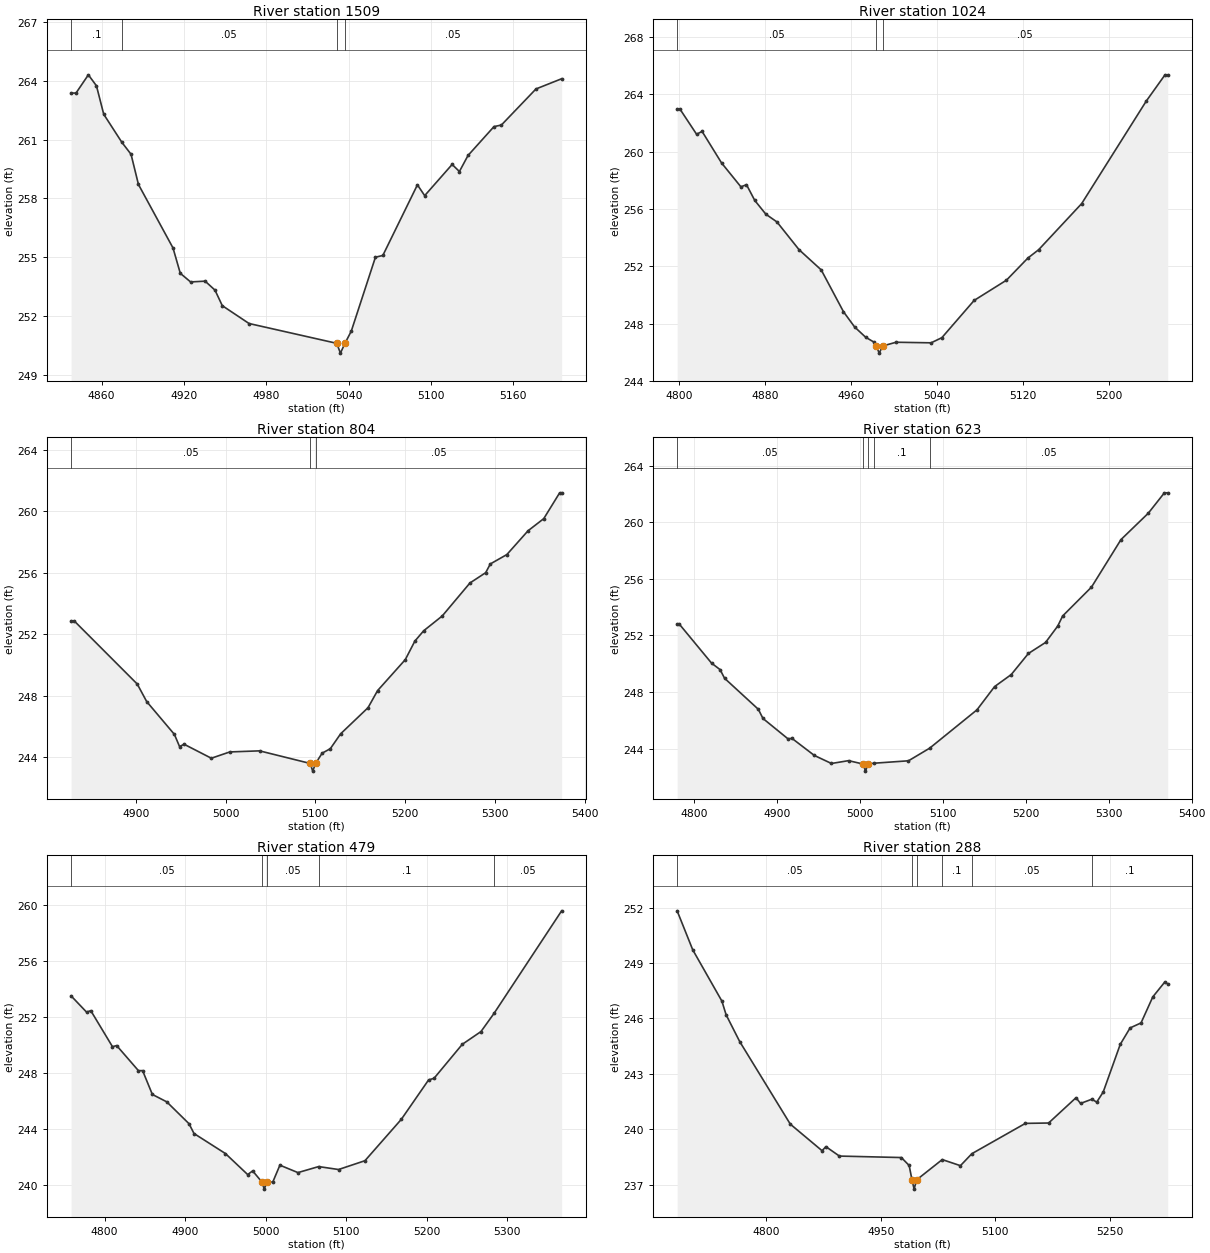
Type RM Length L Ch R = 1 ,1509    ,485,485,485
BEGIN DESCRIPTION:
UNT04919 IN WICK 3.0
END DESCRIPTION:
XS GIS Cut Line= 2
      3592010.27     10267970.12      3592346.17      10268092.5
#Sta/Elev= 30
  4837.7  263.37  4841.3  263.37  4850.3   264.3  4856.2  263.74  4861.5  262.29
  4874.7  260.86  4881.4  260.25  4886.8  258.71    4912  255.47  4917.3  254.18
  4924.8  253.74  4935.4  253.78  4942.6  253.32  4947.9  252.53  4967.4  251.62
  5031.3  250.61    5034  250.11  5037.3  250.61  5041.9  251.23  5059.5     255
  5064.9  255.09  5090.1  258.69  5095.4  258.14  5115.4  259.73  5120.7  259.37
    5127  260.19  5145.9  261.66  5151.3  261.74  5176.5  263.58  5195.2   264.1
#Mann= 4 ,-1 , 0
  4837.7      .1       0  4874.7     .05       0  5031.3     .03       0
  5037.3     .05       0
Bank Sta=5031.3,5037.3
XS Rating Curve= 0 ,0
Exp/Cntr=0.3,0.1

Type RM Length L Ch R = 1 ,1024    ,220,220,220
BEGIN DESCRIPTION:
UNT04919 IN WICK 2.0
END DESCRIPTION:
XS GIS Cut Line= 3
      3591842.06     10268441.63      3592042.11     10268491.64
      3592292.11     10268491.64
#Sta/Elev= 30
  4798.5  262.98  4801.1  262.98  4816.6  261.22  4821.7  261.42  4839.8  259.22
  4857.8  257.55    4863   257.7  4870.7   256.6    4881  255.64  4891.3   255.1
  4911.9  253.16  4932.5  251.75  4953.2  248.83  4963.5  247.77  4973.8  247.05
  4981.5  246.71  4983.7  246.44  4986.4  245.94  4989.7  246.44  5002.1   246.7
  5034.7  246.66  5044.7  247.02  5074.7  249.62  5104.7  251.03  5124.7  252.58
  5134.7  253.16  5174.7  256.38  5234.7  263.53  5252.2  265.37  5254.7  265.37
#Mann= 3 ,-1 , 0
  4798.5     .05       0  4983.7     .03       0  4989.7     .05       0
Bank Sta=4983.7,4989.7
XS Rating Curve= 0 ,0
Exp/Cntr=0.3,0.1

Type RM Length L Ch R = 1 ,804     ,181,181,181
BEGIN DESCRIPTION:
Mapping XS 8632e755
END DESCRIPTION:
XS GIS Cut Line= 2
      3591880.23     10268744.98      3592411.42     10268617.39
#Sta/Elev= 30
  4827.9  252.87  4831.4  252.87  4901.6  248.76  4912.1  247.62    4943  245.48
  4948.7  244.69  4953.8  244.84  4984.1  243.93  5004.7  244.34  5037.8  244.41
  5094.2  243.59    5097  243.09  5100.2  243.59  5107.5  244.26  5116.6  244.55
  5128.1  245.52  5158.6  247.22  5169.2  248.33  5200.1  250.35  5210.8  251.56
  5220.6  252.23  5241.2  253.19  5272.1  255.34  5289.6  256.01  5294.8  256.58
  5313.2  257.19  5336.8  258.74  5354.3  259.53    5372  261.21  5374.2  261.21
#Mann= 3 ,-1 , 0
  4827.9     .05       0  5094.2     .03       0  5100.2     .05       0
Bank Sta=5094.2,5100.2
XS Rating Curve= 0 ,0
Exp/Cntr=0.3,0.1

Type RM Length L Ch R = 1 ,623     ,144,144,144
BEGIN DESCRIPTION:
Mapping XS 2265d852
END DESCRIPTION:
XS GIS Cut Line= 2
       3591931.9     10268900.97       3592504.8      10268753.4
#Sta/Elev= 30
  4779.5  252.79  4782.2  252.79    4821  250.04  4831.3  249.58  4836.7  248.97
  4877.4  246.78    4883  246.13    4913   244.7  4918.1  244.72  4944.9  243.52
  4965.6  242.95  4986.2  243.15  5003.9  242.91  5006.6  242.41  5009.9  242.91
  5017.1  242.97  5058.5  243.14    5084  244.03  5141.1  246.74  5162.3  248.38
  5182.4  249.23  5203.1  250.72  5223.8   251.5  5238.5  252.66  5244.4  253.37
  5279.2  255.41  5314.8  258.77  5347.7  260.63  5367.1  262.07  5371.1  262.07
#Mann= 5 ,-1 , 0
  4779.5     .05       0  5003.9     .03       0  5009.9     .05       0
  5017.1      .1       0    5084     .05       0
Bank Sta=5003.9,5009.9
XS Rating Curve= 0 ,0
Exp/Cntr=0.3,0.1

Type RM Length L Ch R = 1 ,479     ,191,191,191
BEGIN DESCRIPTION:
Mapping XS 10440ba4
END DESCRIPTION:
XS GIS Cut Line= 4
      3591942.23      10268989.7      3592039.55     10269020.79
      3592370.61      10268926.2      3592501.68     10268830.26
#Sta/Elev= 30
  4758.5  253.51  4777.7  252.35    4783  252.45  4809.9  249.88  4815.1  249.96
  4842.1  248.17  4847.3  248.17  4859.4  246.47  4877.3  245.94  4904.9  244.38
  4911.1  243.68  4950.1  242.25  4977.7  240.75  4983.9  241.01  4995.5  240.21
  4998.3  239.71  5001.5  240.21  5008.9  240.22  5017.7  241.42  5040.1  240.89
  5065.8  241.32  5090.5  241.11  5123.3  241.74  5168.5   244.7  5202.3  247.51
    5209  247.62  5244.1  250.05  5267.3  250.96  5283.4  252.25  5367.4  259.58
#Mann= 5 ,-1 , 0
  4758.5     .05       0  4995.5     .03       0  5001.5     .05       0
  5065.8      .1       0  5283.4     .05       0
Bank Sta=4995.5,5001.5
XS Rating Curve= 0 ,0
Exp/Cntr=0.3,0.1

Type RM Length L Ch R = 1 ,288     ,237,237,237
BEGIN DESCRIPTION:
Mapping XS 9ceaad7d
END DESCRIPTION:
XS GIS Cut Line= 4
      3591963.45     10269112.94      3592100.59      10269173.7
      3592439.13     10269116.41      3592517.19     10268989.78
#Sta/Elev= 30
  4683.4  251.83  4703.8  249.72    4742  246.94  4747.5   246.2  4765.3  244.75
  4831.5  240.28  4873.1  238.84  4878.1  239.06  4895.8  238.55  4976.9  238.47
  4987.1  238.04  4990.8  237.26  4993.6  236.76  4996.8  237.26  5030.4  238.36
  5054.2  238.03  5069.2  238.68  5139.2  240.32  5169.6  240.34  5205.5  241.71
  5211.4   241.4  5226.3  241.63  5232.6  241.47  5241.1  242.02  5263.4   244.6
  5276.3  245.49  5290.6  245.76    5306  247.17  5321.4  247.96  5325.5  247.88
#Mann= 6 ,-1 , 0
  4683.4     .05       0  4990.8     .03       0  4996.8     .05       0
  5030.4      .1       0  5069.2     .05       0  5226.3      .1       0
Bank Sta=4990.8,4996.8
XS Rating Curve= 0 ,0
Exp/Cntr=0.3,0.1

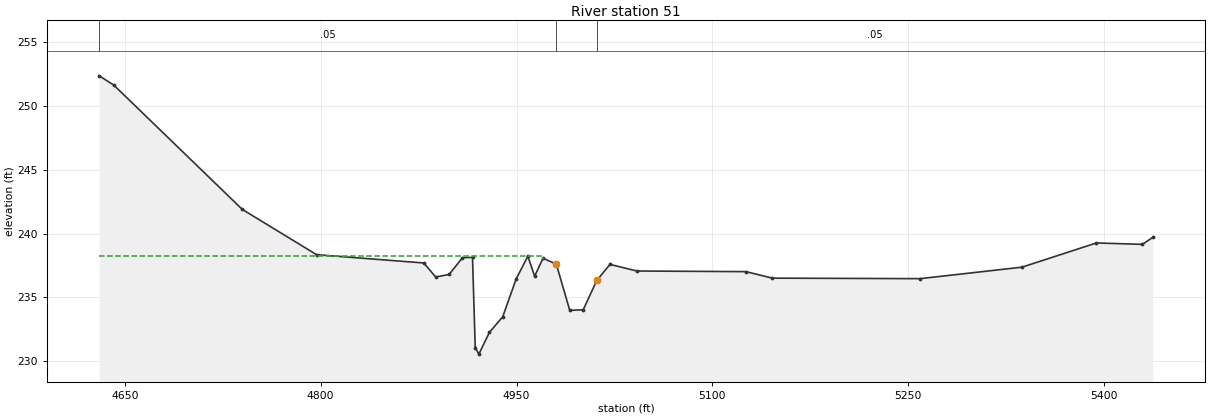
Type RM Length L Ch R = 1 ,51      ,0,0,0
BEGIN DESCRIPTION:
UNT04919 IN WICK 1.0
END DESCRIPTION:
XS GIS Cut Line= 4
      3591927.14     10269162.43      3592024.81     10269299.16
      3592339.48     10269372.95      3592543.47     10269132.06
#Sta/Elev= 30
  4630.4  252.37  4641.6  251.64    4740  241.89  4796.9  238.34    4879  237.69
  4888.1  236.59  4898.4  236.79  4908.6   238.1  4916.3  238.13  4918.4  231.04
  4921.2  230.54  4929.2  232.24  4939.5  233.48  4949.7  236.43  4958.7  238.22
  4963.9  236.65  4970.3  238.06  4980.5   237.6  4990.8  233.97  5001.1  234.02
  5011.5  236.32  5021.6  237.58  5042.2  237.06  5125.8  237.01    5146   236.5
  5259.1  236.46  5337.1  237.36  5394.2  239.26  5429.4  239.15  5437.3   239.7
#Mann= 3 , 0 , 0
  4630.4     .05       0  4980.5     .03       0  5011.5     .05       0
#XS Ineff= 2 , 0
          4970.1  238.22 5021.56          237.55
Permanent Ineff=
       F       F
Bank Sta=4980.5,5011.5
XS Rating Curve= 0 ,0
Exp/Cntr=0.3,0.1

Chan Stop Cuts=-1
Use User Specified Reach Order=0
Composite Channel Slope=5