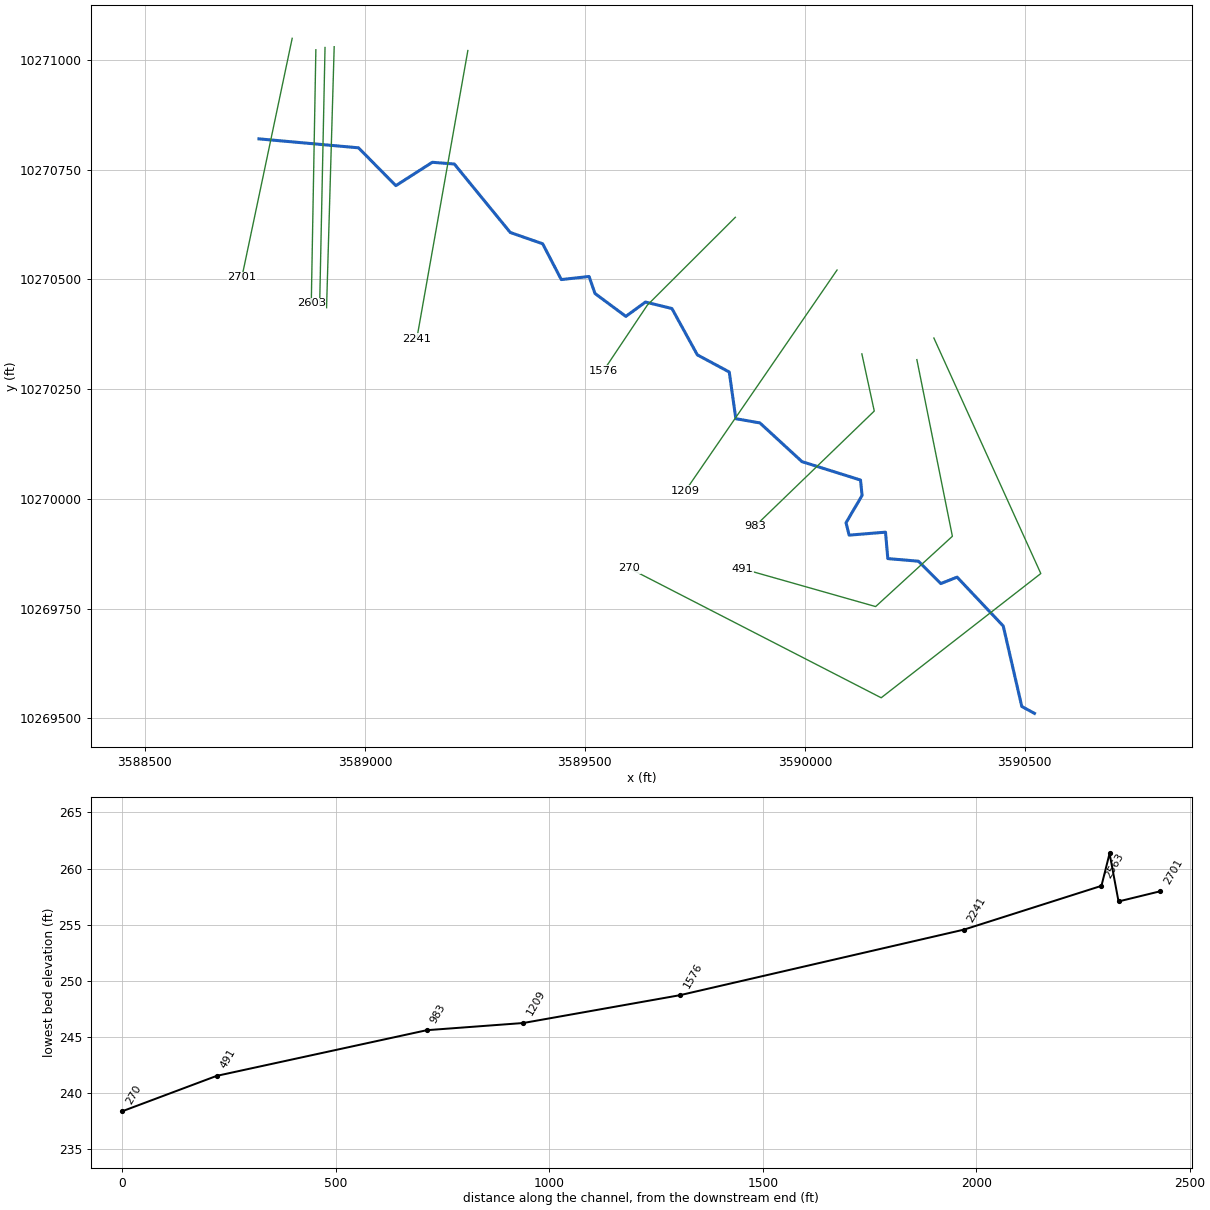
--- ALLCORNCREEKTRIB.prj (project) ---

Proj Title=ALLCORN CREEK TRIB 8
Current Plan=p01
Default Exp/Contr=0.3,0.1
English Units
Geom File=g01
Flow File=f01
Plan File=p01
Y Axis Title=Elevation
X Axis Title(PF)=Main Channel Distance
X Axis Title(XS)=Station
BEGIN DESCRIPTION:
UNT04911 IN WICK
END DESCRIPTION:
DSS Export Rating Curves= 0
DSS Export Rating Curve Sorted= 0
DSS Export Volume Flow Curves= 0
DXF Filename=UNT04911 IN WICK.
DXF OffsetX= 0
DXF OffsetY= 0
DXF ScaleX= 1
DXF ScaleY= 10

--- ALLCORNCREEKTRIB.p01 (plan) ---

Plan Title=Multiple Run
Short Identifier=Multiple
Geom File=g01
Flow File=f01
Subcritical Flow
K Sum by GR= 0
Std Step Tol= 0.01
Critical Tol= 0.01
Num of Std Step Trials= 20
Max Error Tol= 0.3
Flow Tol Ratio= 0.001
Split Flow NTrial= 30
Split Flow Tol= 0.02
Split Flow Ratio= 0.02
Log Output Level= 0
Friction Slope Method= 1
Unsteady Friction Slope Method= 2
Unsteady Bridges Friction Slope Method= 1
Parabolic Critical Depth
Global Vel Dist=  1 , 1 , 1
Global Log Level= 0
CheckData=True
Encroach Param= -1, 0, 0, 0
BEGIN DESCRIPTION:
Multiple Run
END DESCRIPTION:

--- ALLCORNCREEKTRIB.f01 (steady flow) ---

Flow Title=Multiple
Program Version=4.10
Number of Profiles= 7
Profile Names=10-year,25-year,50-year,1pct_min,100-year,1pct_plu,500-year
River Rch & RM=UNT04911 IN WICK,Reach-1         ,2701
     247     317     372     321     434     587     590
River Rch & RM=ALLCORNCRTRIB8,Reach-1         ,2701
     247     317     372     321     434     587     590
Boundary for River Rch & Prof#=ALLCORNCRTRIB8,Reach-1         , 1
Up Type= 0
Dn Type= 3
Dn Slope=0.005
Boundary for River Rch & Prof#=ALLCORNCRTRIB8,Reach-1         , 2
Up Type= 0
Dn Type= 3
Dn Slope=0.005
Boundary for River Rch & Prof#=ALLCORNCRTRIB8,Reach-1         , 3
Up Type= 0
Dn Type= 3
Dn Slope=0.005
Boundary for River Rch & Prof#=ALLCORNCRTRIB8,Reach-1         , 4
Up Type= 0
Dn Type= 3
Dn Slope=0.005
Boundary for River Rch & Prof#=ALLCORNCRTRIB8,Reach-1         , 5
Up Type= 0
Dn Type= 3
Dn Slope=0.005
Boundary for River Rch & Prof#=ALLCORNCRTRIB8,Reach-1         , 6
Up Type= 0
Dn Type= 3
Dn Slope=0.005
Boundary for River Rch & Prof#=ALLCORNCRTRIB8,Reach-1         , 7
Up Type= 0
Dn Type= 3
Dn Slope=0.005
DSS Import GetInterval= 0
DSS Import GetPeak= 0
DSS Import FillOption= 0

--- ALLCORNCREEKTRIB.g01 (geometry) ---

Geom Title=Existing Conditions
Program Version=4.10

River Reach=ALLCORNCRTRIB8  ,Reach-1
Reach XY= 30
      3588759.17     10270820.26      3588985.51     10270799.87
      3589070.39     10270713.71      3589153.26     10270766.92
      3589203.32       10270763.      3589330.52       10270607.
       3589404.1     10270581.32      3589446.46     10270499.79
      3589509.66     10270506.79      3589523.04     10270468.09
      3589593.18      10270415.9      3589637.83     10270448.56
      3589697.91     10270433.84      3589755.76      10270328.2
      3589828.23     10270289.24      3589843.18     10270182.87
      3589897.94     10270173.22      3589993.61       10270085.
      3590126.59     10270043.13       3590130.2     10270008.08
       3590093.7     10269945.87      3590100.68      10269917.6
      3590183.41     10269924.41      3590188.67     10269864.23
      3590258.28     10269858.22      3590309.08     10269807.28
      3590346.09     10269821.98      3590451.04     10269710.62
      3590493.22     10269527.28      3590522.11     10269511.64

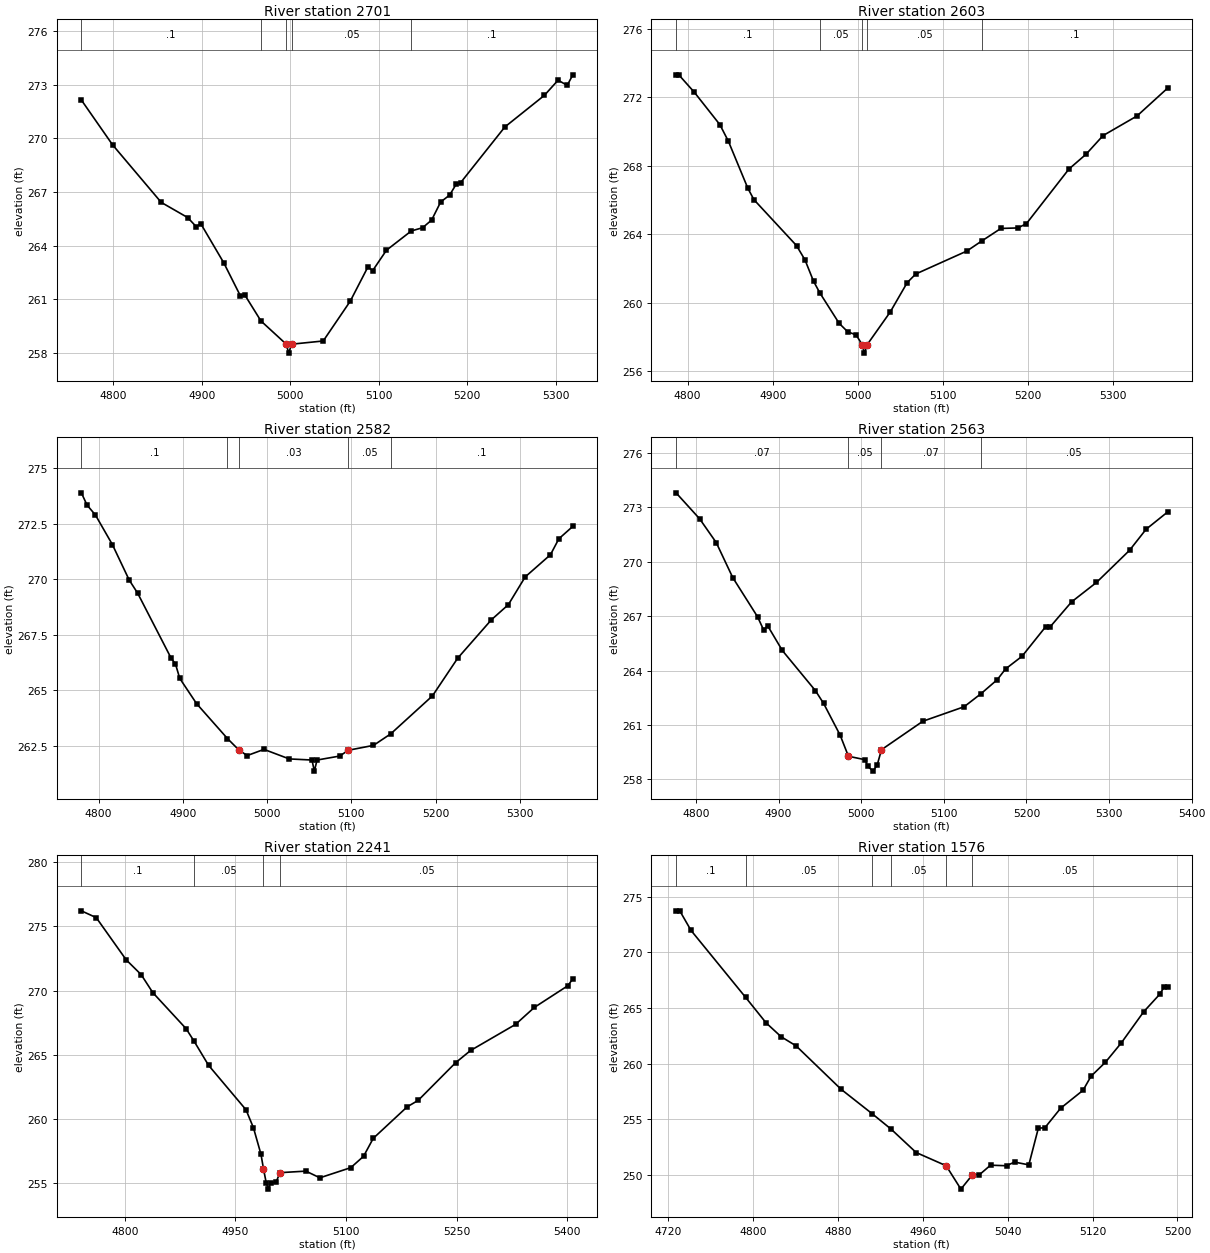
Type RM Length L Ch R = 1 ,2701    ,98,98,98
BEGIN DESCRIPTION:
UNT04911 IN WICK 3.0
END DESCRIPTION:
XS GIS Cut Line= 2
      3588834.77     10271049.26      3588720.45     10270505.35
#Sta/Elev= 30
  4763.7  272.15    4799  269.64    4854  266.42  4883.9  265.57  4893.6  265.06
  4898.7  265.23  4924.8  263.03  4943.5  261.19  4948.6  261.23  4966.8  259.78
  4995.4  258.48  4998.2  257.98  5001.4  258.48  5037.2  258.66  5067.8  260.89
  5087.9  262.82    5093  262.59  5108.7  263.74  5136.8  264.82  5149.6     265
  5159.8  265.43    5170  266.44  5180.2  266.83  5187.6  267.44  5192.7  267.53
  5242.6  270.64  5287.3  272.41  5302.8  273.26  5313.1  272.97  5319.5  273.56
#Mann= 5 ,-1 , 0
  4763.7      .1       0  4966.8     .05       0  4995.4     .03       0
  5001.4     .05       0  5136.8      .1       0
Bank Sta=4995.4,5001.4
XS Rating Curve= 0 ,0
Exp/Cntr=0.3,0.1

Type RM Length L Ch R = 1 ,2603    ,21,21,21
BEGIN DESCRIPTION:
Mapping XS a5bea26f
END DESCRIPTION:
XS GIS Cut Line= 2
      3588888.59     10271023.16      3588878.19     10270445.86
#Sta/Elev= 30
  4786.5  273.32  4789.7  273.32    4808   272.3    4838  270.41    4848  269.44
  4870.9  266.69    4878  266.03    4928  263.35    4938  262.51    4948  261.27
  4955.5  260.58  4978.1  258.81  4988.1  258.32  4998.1  258.13  5005.1  257.57
  5007.8  257.07  5011.1  257.57  5038.1  259.47  5058.1  261.19  5068.1  261.69
  5128.1  263.03  5145.4  263.61  5168.1  264.35  5188.1  264.38  5198.1  264.63
  5248.1  267.82  5268.1  268.68  5288.1  269.77  5328.1  270.92  5363.9  272.54
#Mann= 5 ,-1 , 0
  4786.5      .1       0  4955.5     .05       0  5005.1     .03       0
  5011.1     .05       0  5145.4      .1       0
Bank Sta=5005.1,5011.1
XS Rating Curve= 0 ,0
Exp/Cntr=0.3,0.1

Type RM Length L Ch R = 1 ,2582    ,19,19,19
BEGIN DESCRIPTION:
Mapping XS f755d127
END DESCRIPTION:
XS GIS Cut Line= 2
      3588909.42     10271028.39       3588897.3     10270445.01
#Sta/Elev= 30
  4779.5  273.89  4786.2  273.34  4796.2  272.89  4816.3  271.56  4836.3  269.96
  4846.3  269.37  4886.2  266.43  4891.2  266.18  4896.3  265.53  4916.3  264.39
  4952.9  262.82  4966.3  262.31  4976.3  262.05  4996.3  262.33  5026.3   261.9
  5053.3  261.85  5056.1  261.35  5059.3  261.85  5086.3  262.03  5096.3  262.29
  5126.3  262.51  5146.8  263.03  5196.3  264.74  5226.3  266.44  5266.3  268.17
  5286.4  268.85  5306.4   270.1  5336.4   271.1  5346.4  271.82    5363  272.38
#Mann= 5 ,-1 , 0
  4779.5      .1       0  4952.9     .05       0  4966.3     .03       0
  5096.3     .05       0  5146.8      .1       0
Bank Sta=4966.3,5096.3
XS Rating Curve= 0 ,0
Exp/Cntr=0.3,0.1

Type RM Length L Ch R = 1 ,2563    ,322,322,322
BEGIN DESCRIPTION:
Mapping XS 4b552b64
END DESCRIPTION:
XS GIS Cut Line= 2
      3588930.26     10271030.18      3588912.92     10270435.63
#Sta/Elev= 30
    4776   273.8  4804.5  272.37  4824.6  271.06  4844.6  269.13  4874.6  266.97
  4881.9  266.25  4886.9  266.47  4904.6  265.11  4944.6   262.9  4954.6  262.19
  4974.6  260.44  4984.6  259.28  5004.6  259.09 5008.13  258.72  5014.4  258.46
 5019.43   258.8  5024.6  259.64  5074.7  261.21  5124.7  262.01  5145.1  262.73
  5164.7   263.5  5174.7  264.09  5194.7  264.79  5223.5  266.43  5228.5   266.4
  5254.7  267.79  5284.8  268.86  5324.8  270.63  5344.8  271.79  5370.8  272.74
#Mann= 4 ,-1 , 0
    4776     .07       0  4984.6     .05       0  5024.6     .07       0
  5145.1     .05       0
Bank Sta=4984.6,5024.6
XS Rating Curve= 0 ,0
Exp/Cntr=0.3,0.1

Type RM Length L Ch R = 1 ,2241    ,665,665,665
BEGIN DESCRIPTION:
Mapping XS c3f4e375
END DESCRIPTION:
XS GIS Cut Line= 2
      3589234.08     10271021.51      3589118.04     10270365.09
#Sta/Elev= 30
  4741.1   276.2  4761.3  275.67  4801.9  272.39  4822.2  271.24    4838  269.84
  4883.1  267.04  4893.9  266.07  4913.6  264.19  4964.4  260.73  4974.5  259.33
  4984.7  257.27 4988.11  256.14  4991.8  255.06  4994.6  254.56  4997.8  255.06
    5005  255.08  5010.5  255.84  5045.6  255.96  5064.6  255.44  5106.5  256.23
  5123.8  257.11    5137  258.51    5183  260.96  5197.9  261.46  5248.7  264.39
    5269  265.34    5330  267.37  5355.5  268.69    5401  270.38  5407.7  270.92
#Mann= 4 ,-1 , 0
  4741.1      .1       0  4893.9     .05       0 4988.11     .03       0
  5010.5     .05       0
Bank Sta=4988.11,5010.5
XS Rating Curve= 0 ,0
Exp/Cntr=0.3,0.1

Type RM Length L Ch R = 1 ,1576    ,367,367,367
BEGIN DESCRIPTION:
UNT04911 IN WICK 2.0
END DESCRIPTION:
XS GIS Cut Line= 3
      3589842.09     10270641.62      3589642.11     10270441.64
       3589542.1     10270291.64
#Sta/Elev= 30
  4727.6  273.72  4731.1  273.72  4741.7  271.96  4793.2  265.94  4812.4  263.66
  4826.6  262.41  4840.7  261.59  4883.1  257.69  4912.3   255.5  4930.2  254.11
  4953.8  252.01  4982.1  250.82    4996  248.72  5006.9  250.01  5013.4  250.01
  5023.9  250.87    5039  250.82  5046.5  251.15    5060   250.9    5069  254.21
    5075  254.22    5090  255.99  5111.1   257.6  5118.6  258.86  5132.1  260.11
  5147.1  261.85  5168.2  264.65  5183.2  266.21  5187.7   266.9  5190.7   266.9
#Mann= 6 ,-1 , 0
  4727.6      .1       0  4793.2     .05       0  4912.3      .1       0
  4930.2     .05       0  4982.1     .03       0  5006.9     .05       0
Bank Sta=4982.1,5006.9
XS Rating Curve= 0 ,0
Exp/Cntr=0.3,0.1

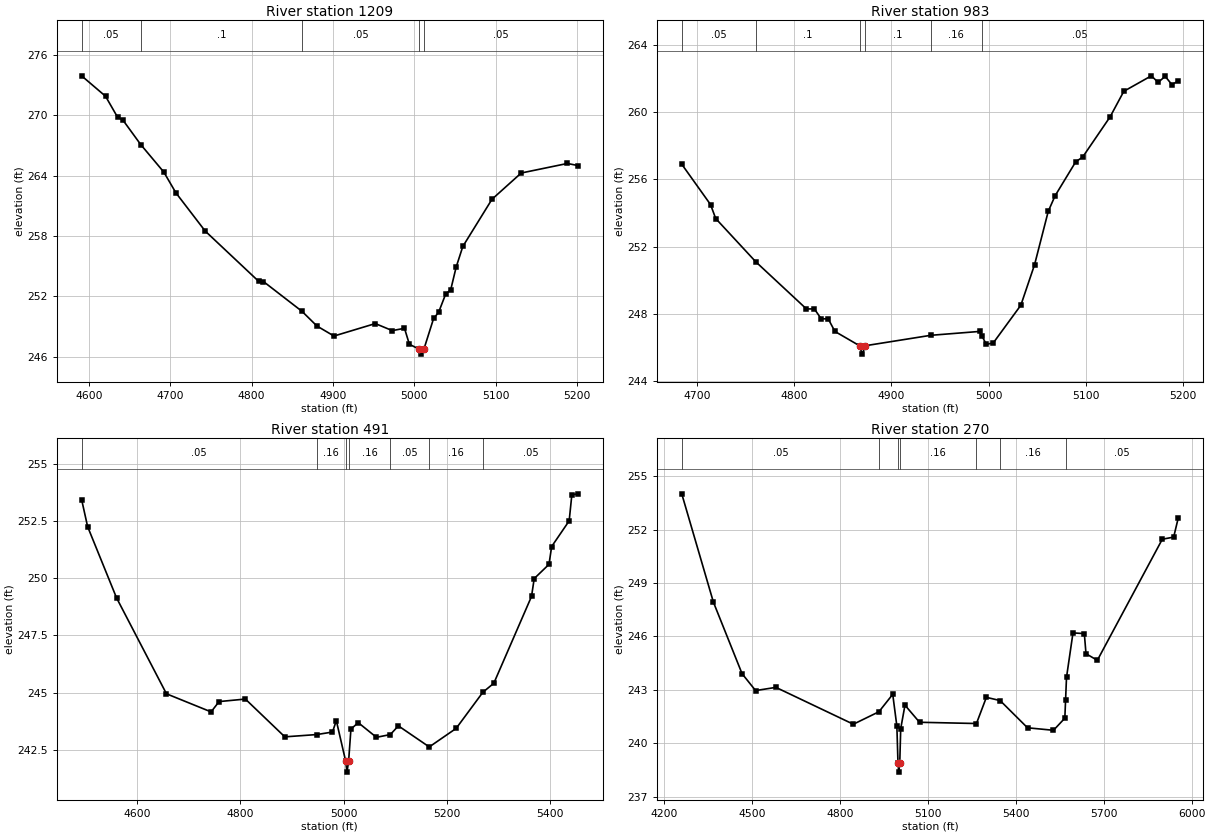
Type RM Length L Ch R = 1 ,1209    ,226,226,226
BEGIN DESCRIPTION:
Mapping XS 65a47f15
END DESCRIPTION:
XS GIS Cut Line= 2
      3590073.27     10270521.51       3589728.2     10270018.01
#Sta/Elev= 30
    4591  273.93  4620.4   271.9  4635.3   269.8  4641.3  269.58  4663.7  267.09
  4692.1  264.35    4707  262.28  4742.9  258.49  4808.6  253.49  4814.6  253.46
  4862.1  250.49  4880.3  249.04  4901.3  248.04  4952.1  249.28    4973  248.58
    4988  248.81    4994  247.22  5005.9  246.74  5008.7  246.24  5011.9  246.74
  5023.8  249.79  5029.9  250.39  5038.7  252.23  5044.8  252.63  5051.5  254.89
  5059.7  256.95  5095.6  261.65  5131.5  264.26  5188.3  265.21  5201.4     265
#Mann= 5 ,-1 , 0
    4591     .05       0  4663.7      .1       0  4862.1     .05       0
  5005.9     .03       0  5011.9     .05       0
Bank Sta=5005.9,5011.9
XS Rating Curve= 0 ,0
Exp/Cntr=0.3,0.1

Type RM Length L Ch R = 1 ,983     ,492,492,492
BEGIN DESCRIPTION:
Mapping XS cdfda287
END DESCRIPTION:
XS GIS Cut Line= 3
      3590129.66     10270330.54      3590157.88     10270200.29
      3589886.84     10269937.92
#Sta/Elev= 30
  4684.5   256.9  4714.1   254.5  4719.4  253.67  4760.7  251.09  4812.7  248.29
  4820.9  248.29  4827.9   247.7  4835.1   247.7    4842  246.95  4867.3   246.1
  4870.1   245.6  4873.3   246.1  4940.6  246.72  4990.7  246.95  4993.2  246.68
  4997.7  246.18  5004.9  246.27  5033.2  248.51  5047.3  250.92  5061.4   254.1
  5068.4  255.02  5089.7  257.05  5096.7  257.32    5125  259.72  5139.1  261.24
  5167.4  262.16  5174.4  261.77  5181.6  262.13  5188.5  261.64    5195  261.85
#Mann= 6 ,-1 , 0
  4684.5     .05       0  4760.7      .1       0  4867.3     .03       0
  4873.3      .1       0  4940.6     .16       0  4993.2     .05       0
Bank Sta=4867.3,4873.3
XS Rating Curve= 0 ,0
Exp/Cntr=0.3,0.1

Type RM Length L Ch R = 1 ,491     ,221,221,221
BEGIN DESCRIPTION:
Mapping XS c9748405
END DESCRIPTION:
XS GIS Cut Line= 4
      3590254.71     10270317.42      3590335.44     10269915.07
      3590160.96     10269754.92      3589858.85     10269840.86
#Sta/Elev= 30
  4492.7  253.43  4504.3  252.25  4560.3  249.14    4657  244.95  4743.4  244.16
  4758.9  244.61  4809.8  244.72  4886.2  243.07  4947.9  243.17  4978.5  243.28
  4985.9  243.78  5003.8  242.03  5006.6  241.53  5009.8  242.03  5014.2  243.41
  5028.4  243.69  5063.6  243.05  5090.5  243.17  5106.1  243.55  5165.9  242.63
    5218  243.44  5269.8  245.02  5290.9  245.41  5363.9   249.2  5369.1  249.98
  5397.7   250.6  5402.9  251.38  5436.8   252.5    5442  253.64    5454  253.68
#Mann= 7 ,-1 , 0
  4492.7     .05       0  4947.9     .16       0  5003.8     .07       0
  5009.8     .16       0  5090.5     .05       0  5165.9     .16       0
  5269.8     .05       0
Bank Sta=5003.8,5009.8
XS Rating Curve= 0 ,0
Exp/Cntr=0.3,0.1

Type RM Length L Ch R = 1 ,270     ,0,0,0
BEGIN DESCRIPTION:
UNT04911 IN WICK 1.0
END DESCRIPTION:
XS GIS Cut Line= 4
      3590293.36     10270366.63      3590536.42     10269830.16
      3590173.58     10269547.17      3589600.65     10269842.31
#Sta/Elev= 30
  4260.5  254.01  4368.4  247.93  4466.2  243.91  4512.4  242.96  4581.7  243.14
  4845.9  241.07  4933.1  241.77  4980.3  242.75  4994.4  240.96  4998.2  238.88
  5000.9  238.38  5004.2  238.88  5007.5  240.82    5022  242.14  5071.7  241.18
  5265.9  241.11  5299.7  242.58  5346.6   242.4  5440.1  240.87  5528.7  240.73
  5567.4  241.41  5569.9  242.41  5573.1   243.7  5595.2   246.2  5633.9  246.16
  5639.6  245.03  5678.3  244.66  5899.9  251.46  5938.7  251.58  5954.1  252.64
#Mann= 7 ,-1 , 0
  4260.5     .05       0  4933.1     .16       0  4998.2     .07       0
  5004.2     .16       0  5265.9     .05       0  5346.6     .16       0
  5569.9     .05       0
Bank Sta=4998.2,5004.2
XS Rating Curve= 0 ,0
Exp/Cntr=0.3,0.1

Chan Stop Cuts=-1
Use User Specified Reach Order=0
Composite Channel Slope=5