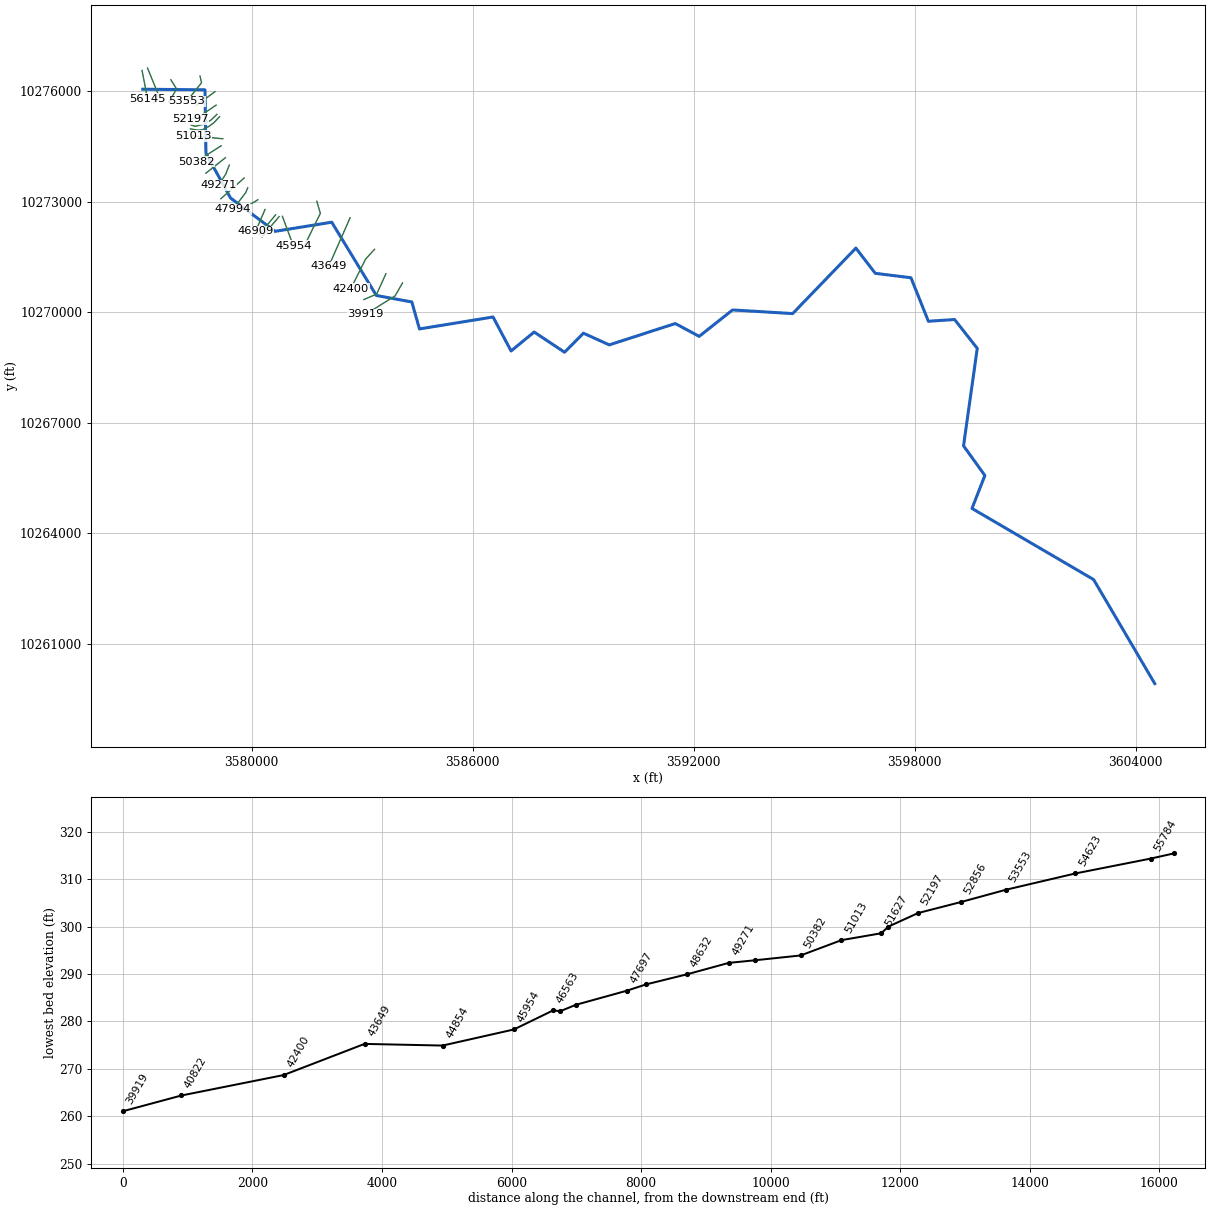
--- ALLCORN CREEK.prj (project) ---

Proj Title=ALLCORN CREEK Base Level Engineering
Current Plan=p01
Default Exp/Contr=0.3,0.1
English Units
Geom File=g01
Flow File=f01
Plan File=p01
Y Axis Title=Elevation
X Axis Title(PF)=Main Channel Distance
X Axis Title(XS)=Station
BEGIN DESCRIPTION:
ALLCORN CREEK
END DESCRIPTION:
DSS File=dss
DSS Export Rating Curves= 0
DSS Export Rating Curve Sorted= 0
DSS Export Volume Flow Curves= 0
DXF OffsetX= 0
DXF OffsetY= 0
DXF ScaleX= 1
DXF ScaleY= 10

--- ALLCORN CREEK.p01 (plan) ---

Plan Title=Multiple Run
Program Version=4.10
Short Identifier=Multiple Run
Geom File=g01
Flow File=f01
Subcritical Flow
K Sum by GR= 0
Std Step Tol= 0.01
Critical Tol= 0.01
Num of Std Step Trials= 20
Max Error Tol= 0.3
Flow Tol Ratio= 0.001
Split Flow NTrial= 30
Split Flow Tol= 0.02
Split Flow Ratio= 0.02
Log Output Level= 0
Friction Slope Method= 1
Unsteady Friction Slope Method= 2
Unsteady Bridges Friction Slope Method= 1
Parabolic Critical Depth
Global Vel Dist= 1 , 1 , 1
Global Log Level= 0
CheckData=True
Encroach Param=-1 ,0,0, 0
BEGIN DESCRIPTION:
Multiple Run
END DESCRIPTION:
Computation Interval=1HOUR
Output Interval=1HOUR
Run HTab= 0
Run UNet= 0
Run PostProcess= 0
Run WQNet= 0
UNET Theta= 1
UNET Theta Warmup= 1
UNET ZTol= 0.02
UNET ZSATol= 0.05
UNET MxIter= 20
UNET MaxInSteps= 0
UNET DtIC= 0
UNET DtMin= 0
UNET MaxCRTS= 20
UNET WFStab= 2
UNET SFStab= 1
UNET WFX= 1
UNET SFX= 1
UNET DSS MLevel= 4
UNET DZMax Abort= 100
UNET Convert EG Bridges= 0
UNET Use Existing IB Tables=-1
UNET Froude Reduction=False
UNET Froude Limit= 1
UNET Froude Power= 10
UNET Time Slicing=0,0, 5
UNET Junction Losses=0
Instantaneous Interval=1HOUR
DSS File=dss
Write IC File= 0
Write IC File at Sim End=0
Echo Input=False
Echo Parameters=False
Echo Output=False
Write Detailed= 0
WQ AD Non Conservative
WQ ULTIMATE=-1
WQ Max Comp Step=1HOUR
WQ Output Interval=15MIN
WQ Output Selected Increments= 0
WQ Output face flow=0
WQ Output face velocity=0
WQ Output face area=0
WQ Output face dispersion=0
WQ Output cell volume=0
WQ Output cell surface area=0
WQ Output cell continuity=0
WQ Output cumulative cell continuity=0
WQ Output face conc=0
WQ Output face dconc_dx=0
WQ Output face courant=0
WQ Output face peclet=0
WQ Output face adv mass=0
WQ Output face disp mass=0
WQ Output cell mass=0
WQ Output cell source sink temp=0
WQ Output cell source sink nsm=0
WQ Output MaxMinRange=-1
WQ Daily Max Min Mean=-1
WQ Daily Range=0
WQ Daily Time=0
WQ Create Restart=0
WQ Fixed Restart=0
WQ System Summary=0
WQ Use Fixed Temperature=0
Sorting and Armoring Iterations= 10
XS Update Threshold= 0.02
Hydraulics Update Threshold= 0.02
Energy Slope Method= 1
Volume Change Method= 0
XS Weighting Method= 0
Number of US Weighted Cross Sections= 1
Number of DS Weighted Cross Sections= 1
Upstream XS Weight=0.25
Main XS Weight=0.5
Downstream XS Weight=0.25
Number of DS XS's Weighted with US Boundary= 1
Upstream Boundary Weight= 1
Weight of XSs Associated with US Boundary= 0
Number of US XS's Weighted with DS Boundary= 1
Downstream Boundary Weight= 0.5
Weight of XSs Associated with DS Boundary= 0.5
Sediment Output Level= 4
Mass or Volume Output= 0
Output Increment Type= 1
Profile and TS Output Increment= 10
XS Output Flag= 0
XS Output Increment= 10
Disregard all LS=0
Disregard all Conn=0
Disregard all Breaches=0
Disregard all Pumps=0

--- ALLCORN CREEK.f01 (steady flow) ---

Flow Title=Multiple
Program Version=4.10
Number of Profiles= 7
Profile Names=10-year,25-year,50-year,1pct_min,100-year,1pct_plu,500-year
River Rch & RM=ALLCORN CREEK,Reach-1         ,56145
     448     593     709     622     841    1138    1185
River Rch & RM=ALLCORN CREEK,Reach-1         ,51738
     530     708     851     750    1015    1372    1444
River Rch & RM=ALLCORN CREEK,Reach-1         ,46909
     759    1035    1262    1127    1524    2060    2226
River Rch & RM=ALLCORN CREEK,Reach-1         ,44854
     921    1268    1556    1397    1889    2555    2793
River Rch & RM=ALLCORN CREEK,Reach-1         ,42400
    1216    1694    2095    1893    2561    3463    3836
River Rch & RM=ALLCORN CREEK,Reach-1         ,36566
    1244    1731    2139    1931    2612    3532    3906
River Rch & RM=ALLCORN CREEK,Reach-1         ,33804
    1332    1855    2293    2070    2799    3785    4185
River Rch & RM=ALLCORN CREEK,Reach-1         ,26532
    1538    2159    2684    2436    3294    4455    4978
River Rch & RM=ALLCORN CREEK,Reach-1         ,25613
    1990    2825    3537    3232    4371    5911    6694
River Rch & RM=ALLCORN CREEK,Reach-1         ,24074
    1942    2742    3420    3111    4208    5690    6390
Boundary for River Rch & Prof#=ALLCORN CREEK,Reach-1         , 1
Up Type= 0
Dn Type= 3
Dn Slope=0.001
Boundary for River Rch & Prof#=ALLCORN CREEK,Reach-1         , 2
Up Type= 0
Dn Type= 3
Dn Slope=0.001
Boundary for River Rch & Prof#=ALLCORN CREEK,Reach-1         , 3
Up Type= 0
Dn Type= 3
Dn Slope=0.001
Boundary for River Rch & Prof#=ALLCORN CREEK,Reach-1         , 4
Up Type= 0
Dn Type= 3
Dn Slope=0.001
Boundary for River Rch & Prof#=ALLCORN CREEK,Reach-1         , 5
Up Type= 0
Dn Type= 3
Dn Slope=0.001
Boundary for River Rch & Prof#=ALLCORN CREEK,Reach-1         , 6
Up Type= 0
Dn Type= 3
Dn Slope=0.001
Boundary for River Rch & Prof#=ALLCORN CREEK,Reach-1         , 7
Up Type= 0
Dn Type= 3
Dn Slope=0.001
DSS Import GetInterval= 0
DSS Import GetPeak= 0
DSS Import FillOption= 0

--- ALLCORN CREEK.g01 (geometry) ---

Geom Title=Existing Conditions
Program Version=4.10

River Reach=ALLCORN CREEK   ,Reach-1
Reach XY= 30
      3577042.14     10276051.52      3578731.28     10276035.32
      3578756.74      10274312.7      3579425.04     10273098.37
       3580633.6     10272193.99      3582172.11     10272441.64
       3583382.9     10270452.67      3584345.56     10270276.74
      3584553.22     10269544.75      3586551.16     10269868.96
      3587039.74     10268946.21      3587666.81     10269460.66
      3588492.13     10268912.39      3589003.89     10269428.98
      3589706.55     10269111.61      3591496.84     10269691.14
      3592146.14     10269343.09      3593052.65     10270060.39
      3594683.82     10269961.22      3596399.72     10271739.18
      3596925.71     10271054.06      3597894.92     10270933.71
      3598367.96     10269753.17      3599079.34     10269800.13
      3599694.45     10269016.59      3599322.02     10266371.65
        3599901.     10265566.71      3599552.11     10264671.64
      3602853.28     10262741.06      3604513.18     10259915.82

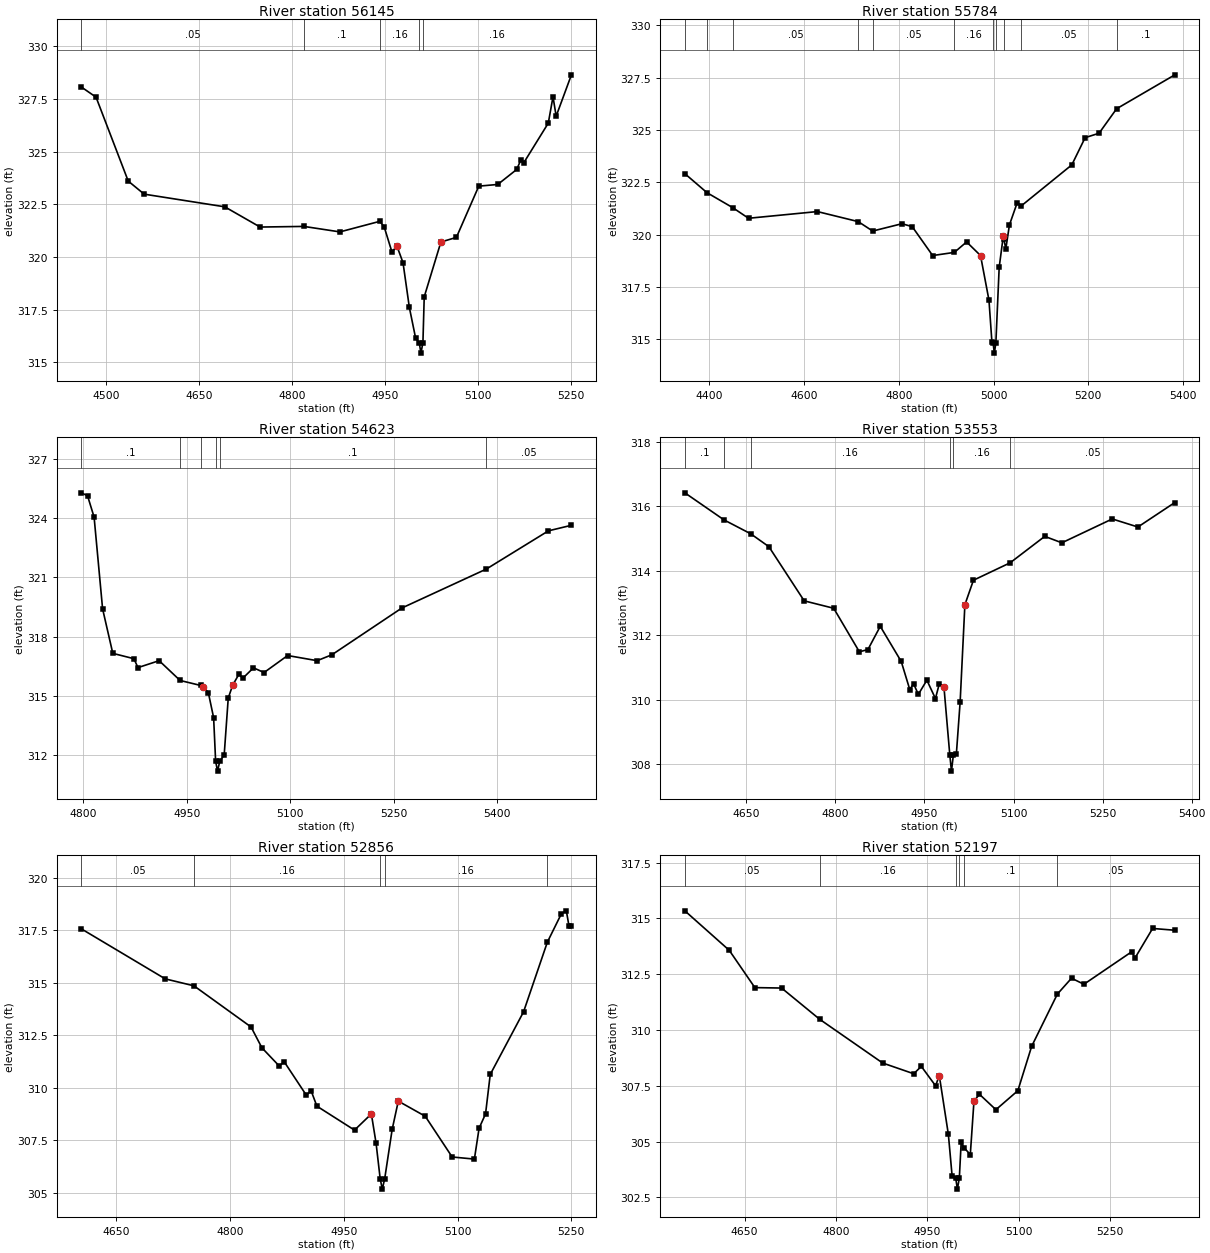
Type RM Length L Ch R = 1 ,56145   ,361,361,361
BEGIN DESCRIPTION:
ALLCORN CREEK 69.0
END DESCRIPTION:
XS GIS Cut Line= 2
      3577022.89     10276561.03      3577172.25     10275784.97
#Sta/Elev= 30
  4460.5  328.06  4484.1  327.58    4536   323.6  4561.7  322.98  4691.7  322.38
  4748.7  321.42  4819.3  321.45  4877.4  321.19  4941.6  321.69  4948.7  321.44
  4961.5  320.22  4969.1  320.54  4979.2  319.73  4989.4  317.61  4999.6  316.14
  5005.3  315.94  5008.1  315.44  5011.3  315.94  5013.4  318.11  5040.3  320.71
  5065.3  320.93  5101.4  323.36    5132  323.44  5162.5  324.15  5169.2   324.6
  5174.2  324.48  5213.5  326.35  5221.1   327.6  5226.2  326.68  5250.8  328.64
#Mann= 5 ,-1 , 0
  4460.5     .05       0  4819.3      .1       0  4941.6     .16       0
  5005.3     .07       0  5011.3     .16       0
Bank Sta=4969.1,5040.3
XS Rating Curve= 0 ,0
Exp/Cntr=0.3,0.1

Type RM Length L Ch R = 1 ,55784   ,1161,1161,1161
BEGIN DESCRIPTION:
ALLCORN CREEK 68.0
END DESCRIPTION:
XS GIS Cut Line= 3
      3577171.33     10276626.13       3577467.7     10275901.39
      3577342.73     10275682.68
#Sta/Elev= 30
    4348  322.91  4394.9     322  4448.9  321.29  4482.5  320.78  4627.9   321.1
  4714.2  320.62  4744.7  320.17  4806.6  320.52  4828.2  320.38  4871.4     319
  4917.1  319.15  4943.1  319.65  4972.5     319  4990.3  316.87  4996.5  314.88
  4998.9  314.84  5001.7  314.34  5004.9  314.84  5011.9  318.44  5020.5  319.92
  5021.5  319.81  5025.9  319.32  5033.5  320.46  5049.9  321.52    5059  321.38
  5165.3  323.33  5193.4  324.63  5222.8  324.84  5259.9  326.01  5382.9  327.63
#Mann= 11 ,-1 , 0
    4348     .05       0  4394.9     .16       0  4448.9     .05       0
  4714.2      .1       0  4744.7     .05       0  4917.1     .16       0
  4998.9     .07       0  5004.9     .16       0  5021.5      .1       0
    5059     .05       0  5259.9      .1       0
Bank Sta=4972.5,5020.5
XS Rating Curve= 0 ,0
Exp/Cntr=0.3,0.1

Type RM Length L Ch R = 1 ,54623   ,1070,1070,1070
BEGIN DESCRIPTION:
Mapping XS 376c8ead
END DESCRIPTION:
XS GIS Cut Line= 3
      3577804.51     10276307.64      3577960.76     10276057.64
      3577748.93     10275699.97
#Sta/Elev= 30
    4797  325.27  4805.9  325.12  4815.4  324.04  4827.7  319.41  4842.5  317.16
  4873.1  316.89    4879  316.44  4909.7  316.79  4940.1  315.79  4969.7  315.54
  4973.4  315.48    4981  315.18  4988.7  313.91  4991.6  311.71  4994.4  311.21
  4997.6  311.71    5004  312.02  5009.9   314.9  5016.3  315.55  5025.3   316.1
  5031.2  315.91  5046.5  316.43  5061.8  316.19    5096  317.05  5138.8  316.79
  5160.3  317.09  5261.6  319.45  5384.2  321.42  5474.2  323.35  5507.5  323.63
#Mann= 6 ,-1 , 0
    4797      .1       0  4940.1     .16       0  4969.7      .1       0
  4991.6     .07       0  4997.6      .1       0  5384.2     .05       0
Bank Sta=4973.4,5016.3
XS Rating Curve= 0 ,0
Exp/Cntr=0.3,0.1

Type RM Length L Ch R = 1 ,53553   ,697,697,697
BEGIN DESCRIPTION:
ALLCORN CREEK 67.0
END DESCRIPTION:
XS GIS Cut Line= 3
      3578596.17     10276408.35      3578637.84     10276227.78
      3578238.54     10275727.78
#Sta/Elev= 30
  4546.5  316.41  4612.5  315.57  4657.4  315.14    4688  314.74  4747.5  313.06
  4797.2  312.83  4840.4  311.48  4854.8  311.55  4875.6  312.27  4910.9  311.18
  4925.3  310.31  4931.7  310.49  4939.7  310.16  4954.1   310.6  4968.5  310.03
  4974.9  310.48  4982.8   310.4  4992.7  308.28  4995.5  307.78  4998.7  308.28
  5003.7   308.3  5010.1  309.92  5018.1  312.94  5032.5   313.7  5094.3  314.24
  5152.6  315.06  5181.4  314.86  5266.3   315.6  5309.5  315.35  5371.7  316.11
#Mann= 6 ,-1 , 0
  4546.5      .1       0  4612.5     .05       0  4657.4     .16       0
  4992.7     .07       0  4998.7     .16       0  5094.3     .05       0
Bank Sta=4982.8,5018.1
XS Rating Curve= 0 ,0
Exp/Cntr=0.3,0.1

Type RM Length L Ch R = 1 ,52856   ,659,659,659
BEGIN DESCRIPTION:
ALLCORN CREEK 66.0
END DESCRIPTION:
XS GIS Cut Line= 2
      3579002.43     10275984.72      3578481.57     10275602.76
#Sta/Elev= 30
  4604.2  317.57  4714.7  315.19  4752.5  314.86  4827.8   312.9  4842.1  311.91
    4865  311.04  4871.4  311.25  4900.7  309.65  4906.9  309.87  4914.6  309.13
  4964.2  307.99  4986.4  308.76  4992.6  307.37    4998  305.68  5000.8  305.18
    5004  305.68  5013.8  308.02  5021.9  309.37  5057.4  308.65  5092.9  306.71
  5122.2  306.61  5128.4  308.08  5136.9  308.76  5143.1  310.64    5187  313.62
  5218.4  316.94    5237   318.3  5243.4  318.43  5246.8  317.73  5250.1  317.73
#Mann= 5 ,-1 , 0
  4604.2     .05       0  4752.5     .16       0    4998     .07       0
    5004     .16       0  5218.4     .05       0
Bank Sta=4986.4,5021.9
XS Rating Curve= 0 ,0
Exp/Cntr=0.3,0.1

Type RM Length L Ch R = 1 ,52197   ,459,459,459
BEGIN DESCRIPTION:
ALLCORN CREEK 65.0
END DESCRIPTION:
XS GIS Cut Line= 3
      3579033.64     10275620.11      3578540.62     10275286.81
      3578336.43     10275241.82
#Sta/Elev= 30
  4551.9  315.34  4624.8  313.57  4666.8   311.9  4710.7  311.88  4773.2  310.48
  4876.6  308.52  4927.5  308.04    4940  308.37  4963.4   307.5  4969.5  307.96
  4984.4  305.32  4990.5  303.47  4996.4  303.37  4999.2  302.87  5002.4  303.37
  5005.4  304.96  5010.3  304.72  5020.4  304.42  5026.4  306.81  5035.4  307.12
  5062.4  306.43  5098.4  307.28  5121.1  309.27  5163.3  311.61  5186.5  312.32
  5206.9  312.05  5285.5  313.51  5290.6  313.22  5319.6  314.55  5356.1  314.47
#Mann= 6 ,-1 , 0
  4551.9     .05       0  4773.2     .16       0  4996.4     .07       0
  5002.4     .16       0  5010.3      .1       0  5163.3     .05       0
Bank Sta=4969.5,5026.4
XS Rating Curve= 0 ,0
Exp/Cntr=0.3,0.1

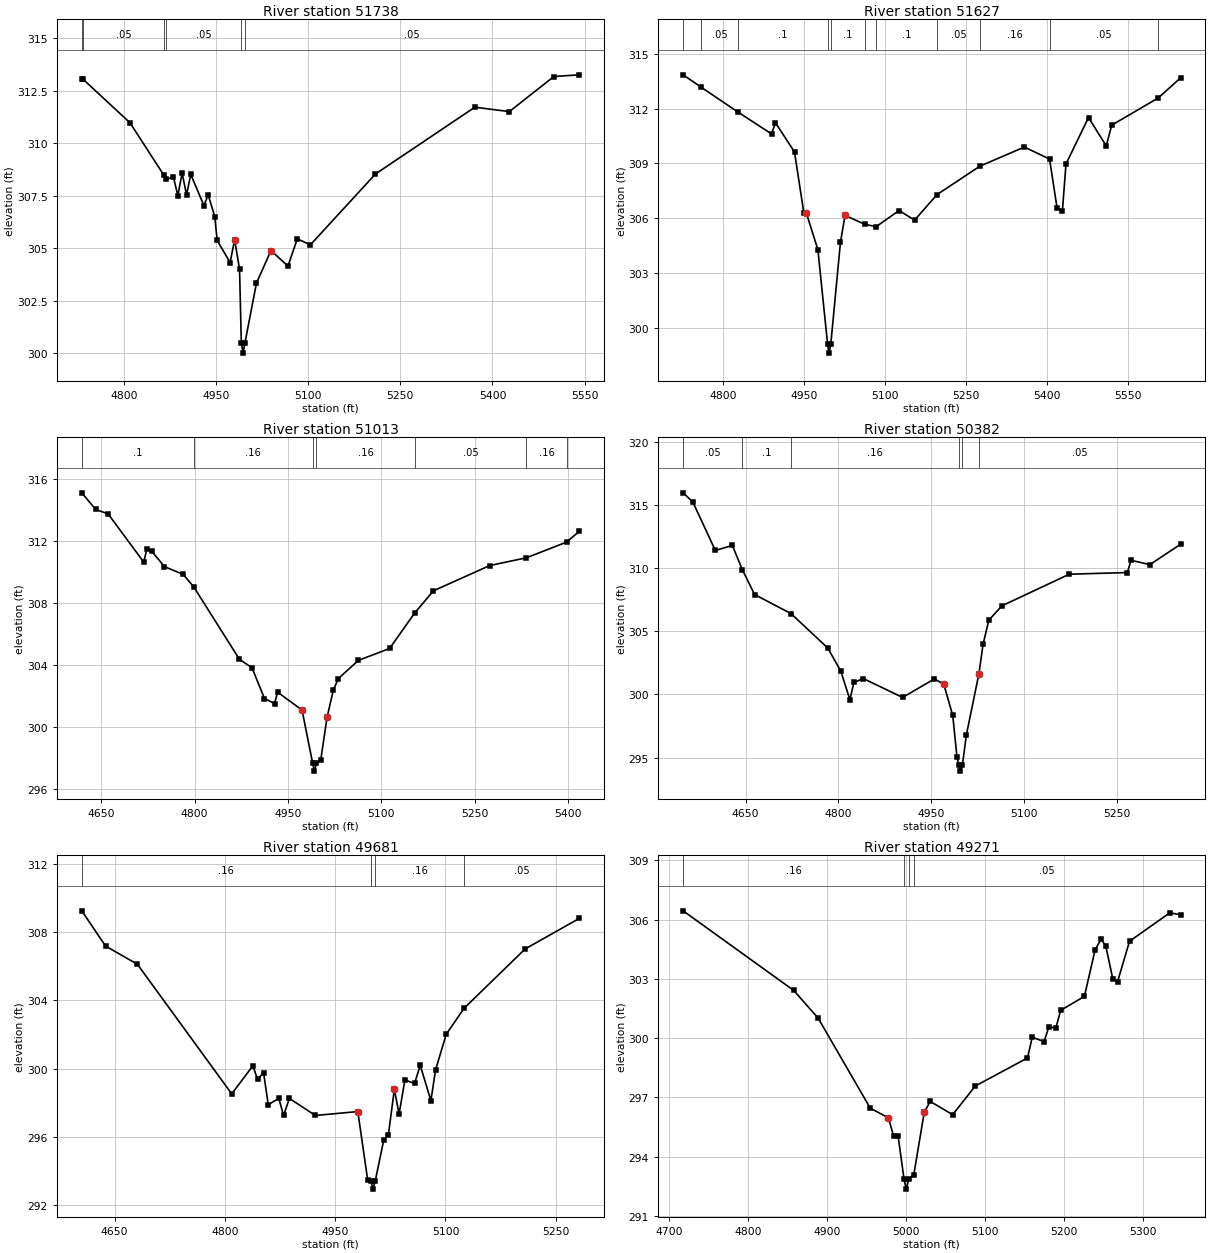
Type RM Length L Ch R = 1 ,51738   ,111,111,111
BEGIN DESCRIPTION:
ALLCORN CREEK 64.0
END DESCRIPTION:
XS GIS Cut Line= 6
      3579054.51     10275370.14      3578901.73     10275220.83
      3578721.18     10275106.25       3578568.4     10275071.53
      3578464.23     10275043.75      3578353.15     10275081.93
#Sta/Elev= 30
  4731.7  313.03  4734.1  313.03  4810.1  310.97  4864.7   308.5    4869  308.28
  4880.8  308.39    4888   307.5    4895  308.58  4902.1  307.54  4909.1  308.51
  4930.4  307.03  4937.4  307.54  4948.1   306.5    4952  305.37  4973.1  304.32
  4980.4  305.41  4988.4     304  4991.3  300.51  4994.1  300.01  4997.3  300.51
  5015.9  303.34  5039.6  304.89  5067.2  304.15  5082.4  305.45  5103.6  305.16
  5209.5  308.53  5371.3  311.71  5427.4   311.5  5499.9  313.17  5541.1  313.25
#Mann= 6 ,-1 , 0
  4731.7      .1       0  4734.1     .05       0  4864.7      .1       0
    4869     .05       0  4991.3     .04       0  4997.3     .05       0
Bank Sta=4980.4,5039.6
XS Rating Curve= 0 ,0
Exp/Cntr=0.3,0.1

Type RM Length L Ch R = 1 ,51627   ,614,614,614
BEGIN DESCRIPTION:
ALLCORN CREEK 63.0
END DESCRIPTION:
XS GIS Cut Line= 6
      3579127.43     10275307.64      3578974.65     10275144.44
      3578828.81     10275036.81      3578662.15     10274953.47
      3578544.09     10274939.58      3578336.47     10274974.19
#Sta/Elev= 30
  4726.3  313.86  4760.2  313.17  4827.7  311.82  4889.9  310.62  4897.2  311.23
  4932.4  309.63  4949.8  306.27  4954.5  306.27  4975.7  304.27  4993.6   299.1
  4996.3   298.6  4999.6   299.1  5017.4  304.67  5025.9  306.15  5062.1  305.67
  5083.3  305.53    5126  306.42  5154.6  305.89    5196  307.29  5275.4  308.85
  5357.8   309.9  5404.4  309.24  5418.2  306.58  5428.2  306.41  5434.8  308.97
  5476.5  311.52  5509.3  309.96  5519.4   311.1  5605.4  312.59  5646.8  313.69
#Mann= 11 ,-1 , 0
  4726.3      .1       0  4760.2     .05       0  4827.7      .1       0
  4993.6     .07       0  4999.6      .1       0  5062.1     .16       0
  5083.3      .1       0    5196     .05       0  5275.4     .16       0
  5404.4     .05       0  5605.4     .16       0
Bank Sta=4954.5,5025.9
XS Rating Curve= 0 ,0
Exp/Cntr=0.3,0.1

Type RM Length L Ch R = 1 ,51013   ,631,631,631
BEGIN DESCRIPTION:
ALLCORN CREEK 62.0
END DESCRIPTION:
XS GIS Cut Line= 2
      3579214.19     10274706.95      3578419.05     10274783.34
#Sta/Elev= 30
  4618.8   315.1    4641  314.03  4661.1  313.74  4718.3  310.63  4723.3  311.48
  4731.4  311.32  4751.5  310.34  4781.6  309.84  4798.8  309.02    4872  304.36
  4892.1  303.82  4912.2  301.83  4928.3  301.51  4933.3  302.24  4972.5  301.09
  4989.6  297.65  4992.3  297.15  4995.6  297.65  5002.6  297.89  5012.7  300.62
  5022.7  302.37  5030.8  303.12  5062.9  304.29  5113.1  305.06  5153.6  307.36
  5183.5  308.78  5273.9  310.41  5332.8  310.91  5397.2  311.92  5417.6  312.61
#Mann= 7 ,-1 , 0
  4618.8      .1       0  4798.8     .16       0  4989.6     .07       0
  4995.6     .16       0  5153.6     .05       0  5332.8     .16       0
  5397.2     .05       0
Bank Sta=4972.5,5012.7
XS Rating Curve= 0 ,0
Exp/Cntr=0.3,0.1

Type RM Length L Ch R = 1 ,50382   ,701,701,701
BEGIN DESCRIPTION:
ALLCORN CREEK 61.0
END DESCRIPTION:
XS GIS Cut Line= 2
      3579169.08     10274515.96      3578492.04     10274081.97
#Sta/Elev= 30
    4549  315.98  4564.7  315.25  4601.1  311.41  4628.6  311.81  4644.8  309.88
  4664.5  307.92  4723.3  306.41  4782.8  303.68    4804  301.84  4818.6  299.58
  4825.1  300.95  4840.3  301.26  4903.8  299.76  4955.3  301.23  4970.5   300.8
  4984.9  298.33  4991.7  295.07  4994.6  294.42  4997.3  293.92  5000.6  294.42
  5006.9  296.78  5027.2  301.63  5033.9  303.97  5043.2  305.88  5064.3  307.02
  5173.4  309.53  5267.2  309.66  5273.2  310.63  5303.6  310.29  5353.2   311.9
#Mann= 6 ,-1 , 0
    4549     .05       0  4644.8      .1       0  4723.3     .16       0
  4994.6     .07       0  5000.6     .16       0  5027.2     .05       0
Bank Sta=4970.5,5027.2
XS Rating Curve= 0 ,0
Exp/Cntr=0.3,0.1

Type RM Length L Ch R = 1 ,49681   ,410,410,410
BEGIN DESCRIPTION:
ALLCORN CREEK 60.0
END DESCRIPTION:
XS GIS Cut Line= 2
      3579287.11     10274193.03       3578756.5     10273773.39
#Sta/Elev= 30
  4605.4  309.27  4637.7   307.2    4681  306.13  4809.3  298.51  4838.1  300.16
  4844.5  299.36  4852.6  299.76    4859  297.87  4873.4  298.25  4879.8  297.24
  4887.8  298.24  4923.1  297.24  4980.8  297.47  4994.3  293.42  4998.6  293.41
  5001.4  292.91  5004.6  293.41  5016.1   295.8  5022.4  296.11  5030.5  298.78
  5036.9  297.32  5044.9  299.33    5058  299.12  5065.7  300.19  5080.2  298.11
  5086.5  299.91    5101  302.01  5125.3  303.54  5208.4  307.03  5281.9  308.82
#Mann= 4 ,-1 , 0
  4605.4     .16       0  4998.6     .07       0  5004.6     .16       0
  5125.3     .05       0
Bank Sta=4980.8,5030.5
XS Rating Curve= 0 ,0
Exp/Cntr=0.3,0.1

Type RM Length L Ch R = 1 ,49271   ,639,639,639
BEGIN DESCRIPTION:
ALLCORN CREEK 59.0
END DESCRIPTION:
XS GIS Cut Line= 3
      3579392.09      10273991.6      3579292.11     10273741.64
      3579092.09     10273441.62
#Sta/Elev= 30
  4717.6  306.44  4857.6  302.41  4888.5  301.01  4954.5  296.45  4977.4  295.96
  4984.1  295.04  4989.8  295.04  4997.3  292.85  5000.1  292.35  5003.3  292.85
  5009.7  293.09  5022.9  296.24  5030.4  296.79  5058.9  296.12  5087.5  297.57
  5153.6  298.99  5159.6  300.04  5174.6  299.82  5180.6  300.55  5189.6  300.52
  5195.6   301.4  5225.7  302.11  5239.2  304.46  5246.7  305.01  5252.7  304.66
  5261.7  302.98  5267.7  302.86  5282.8   304.9  5333.8  306.34  5347.4  306.24
#Mann= 4 ,-1 , 0
  4717.6     .16       0  4997.3     .07       0  5003.3     .16       0
  5009.7     .05       0
Bank Sta=4977.4,5022.9
XS Rating Curve= 0 ,0
Exp/Cntr=0.3,0.1

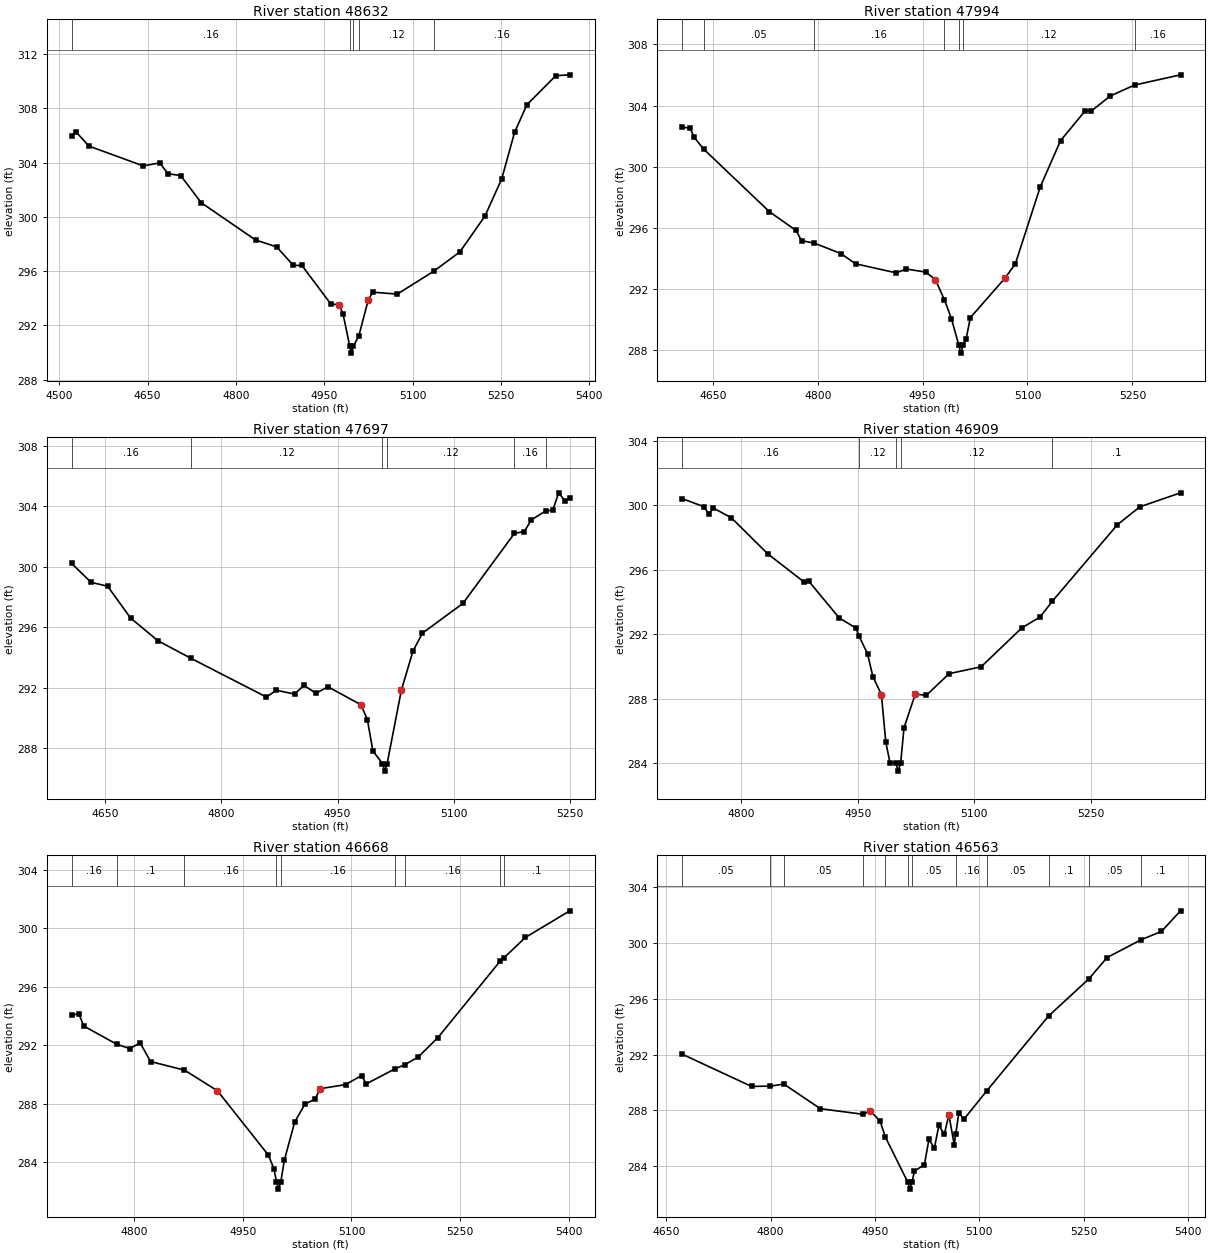
Type RM Length L Ch R = 1 ,48632   ,638,638,638
BEGIN DESCRIPTION:
ALLCORN CREEK 58.0
END DESCRIPTION:
XS GIS Cut Line= 2
      3579794.09     10273640.97      3579162.16     10273078.49
#Sta/Elev= 30
  4520.8  305.97  4528.7  306.25  4550.2  305.22  4642.4  303.76  4670.7  303.98
  4684.3  303.18    4706  303.05  4741.1  301.04  4833.1   298.3    4869  297.79
  4897.5  296.42  4911.7  296.43    4961  293.58  4975.2  293.53  4981.9  292.82
  4993.1  290.46  4995.9  289.96  4999.1  290.46  5008.4  291.21  5024.6  293.89
  5032.1  294.45  5073.9  294.31  5136.2  296.01  5180.1  297.42  5222.7  300.06
  5251.2  302.81  5272.9  306.22  5293.8  308.26  5343.1  310.41  5366.8  310.47
#Mann= 5 ,-1 , 0
  4520.8     .16       0  4993.1     .07       0  4999.1     .16       0
  5008.4     .12       0  5136.2     .16       0
Bank Sta=4975.2,5024.6
XS Rating Curve= 0 ,0
Exp/Cntr=0.3,0.1

Type RM Length L Ch R = 1 ,47994   ,297,297,297
BEGIN DESCRIPTION:
ALLCORN CREEK 57.0
END DESCRIPTION:
XS GIS Cut Line= 3
      3579891.32     10273377.11      3579839.23     10273248.61
      3579492.12     10272791.66
#Sta/Elev= 30
  4606.3  302.58  4617.6  302.53    4623  301.94  4636.8  301.16  4730.9  297.06
  4768.8  295.84    4777  295.16  4794.9  295.01  4833.2  294.32  4854.2  293.65
  4912.2  293.06  4926.8  293.31  4954.6  293.11  4968.4  292.61  4981.3  291.29
  4991.2  290.07  5001.9  288.31  5004.6  287.81  5007.9  288.31  5012.1  288.71
  5018.3  290.13  5068.3  292.74  5082.8  293.67  5118.2  298.68  5147.3  301.71
  5182.6  303.66  5190.9  303.63  5218.4  304.63  5253.1  305.34  5318.8  306.01
#Mann= 7 ,-1 , 0
  4606.3     .16       0  4636.8     .05       0  4794.9     .16       0
  4981.3     .12       0  5001.9     .07       0  5007.9     .12       0
  5253.1     .16       0
Bank Sta=4968.4,5068.3
XS Rating Curve= 0 ,0
Exp/Cntr=0.3,0.1

Type RM Length L Ch R = 1 ,47697   ,788,788,788
BEGIN DESCRIPTION:
Mapping XS 7497d855
END DESCRIPTION:
XS GIS Cut Line= 2
      3580166.78     10273050.98      3579619.88     10272714.16
#Sta/Elev= 30
  4607.2  300.22  4632.4  298.97  4653.7  298.71  4683.2  296.61  4718.4  295.11
  4760.8  293.95  4858.4  291.38  4871.1  291.83  4894.6  291.58  4906.8  292.15
  4922.2  291.63  4937.7  292.06  4980.2  290.87  4988.5  289.89  4995.6  287.82
    5008  286.98  5010.8  286.48    5014  286.98  5032.3  291.83  5047.2  294.41
  5059.5  295.61  5111.6  297.57  5178.1  302.21  5190.8  302.33  5199.9   303.1
  5218.3  303.69  5227.5  303.74  5235.1  304.89  5242.9  304.37  5249.5  304.53
#Mann= 6 ,-1 , 0
  4607.2     .16       0  4760.8     .12       0    5008     .07       0
    5014     .12       0  5178.1     .16       0  5218.3      .1       0
Bank Sta=4980.2,5032.3
XS Rating Curve= 0 ,0
Exp/Cntr=0.3,0.1

Type RM Length L Ch R = 1 ,46909   ,241,241,241
BEGIN DESCRIPTION:
Mapping XS c87e9e2d
END DESCRIPTION:
XS GIS Cut Line= 2
      3580361.19     10272787.06      3580106.53     10272198.05
#Sta/Elev= 30
    4724  300.42  4751.7  299.92  4758.3  299.47  4763.8  299.84  4787.3  299.23
  4834.2  296.99  4881.2  295.23  4886.7  295.31    4926  293.02  4947.8  292.38
  4951.4  291.91  4962.6  290.79  4969.6  289.36  4980.5  288.25  4986.1  285.32
  4991.5  284.03  4999.3     284    5002   283.5  5005.3     284  5009.6  286.19
  5024.1  288.28  5038.5  288.21  5067.6  289.55    5109  289.98  5161.5   292.4
  5184.9  293.07  5200.8  294.06  5284.4   298.8  5313.3  299.91  5365.7  300.78
#Mann= 5 ,-1 , 0
    4724     .16       0  4951.4     .12       0  4999.3     .07       0
  5005.3     .12       0  5200.8      .1       0
Bank Sta=4980.5,5024.1
XS Rating Curve= 0 ,0
Exp/Cntr=0.3,0.1

Type RM Length L Ch R = 1 ,46668   ,105,105,105
BEGIN DESCRIPTION:
ALLCORN CREEK 56.0
END DESCRIPTION:
XS GIS Cut Line= 2
      3580647.55     10272639.74        3580206.     10272111.61
#Sta/Elev= 30
  4713.3  294.06  4723.5  294.14    4730  293.31  4776.1  292.05  4793.7  291.77
  4808.1  292.15  4822.4  290.88  4869.3  290.29  4914.8  288.88    4985  284.49
  4992.8  283.56  4996.4  282.65  4999.1  282.15  5002.4  282.65  5007.2  284.12
  5021.5  286.73  5035.8  287.98  5049.7   288.3  5056.6  289.02  5091.8   289.3
  5113.9  289.92  5120.4  289.35  5160.6  290.39  5173.3  290.65  5191.9  291.18
  5219.3  292.51  5305.6  297.76  5310.4  297.96  5340.3  299.37  5401.7  301.19
#Mann= 9 ,-1 , 0
  4713.3     .16       0  4776.1      .1       0  4869.3     .16       0
  4996.4     .07       0  5002.4     .16       0  5160.6     .12       0
  5173.3     .16       0  5305.6     .05       0  5310.4      .1       0
Bank Sta=4914.8,5056.6
XS Rating Curve= 0 ,0
Exp/Cntr=0.3,0.1

Type RM Length L Ch R = 1 ,46563   ,609,609,609
BEGIN DESCRIPTION:
ALLCORN CREEK 55.0
END DESCRIPTION:
XS GIS Cut Line= 2
      3580742.07     10272591.98      3580279.29      10272045.9
#Sta/Elev= 30
  4673.2  292.03  4772.8  289.72  4799.7  289.74  4819.1  289.89  4871.7  288.12
  4932.9  287.72  4943.1  287.97  4957.4  287.24    4965  286.09  4997.2  282.85
    5000  282.35  5003.2  282.85  5006.8  283.64  5021.1  284.11  5027.6  285.92
  5035.4  285.29  5041.9  286.92  5049.7  286.27  5056.2  287.69  5063.9  285.55
  5066.2  286.33  5070.5   287.8  5078.2  287.39    5111  289.42  5199.4  294.77
    5257  297.42  5283.6  298.97  5332.6  300.25  5361.6  300.84    5389  302.32
#Mann= 12 ,-1 , 0
  4673.2     .05       0  4799.7      .1       0  4819.1     .05       0
  4932.9     .16       0    4965     .05       0  4997.2     .04       0
  5003.2     .05       0  5066.2     .16       0    5111     .05       0
  5199.4      .1       0    5257     .05       0  5332.6      .1       0
Bank Sta=4943.1,5056.2
XS Rating Curve= 0 ,0
Exp/Cntr=0.3,0.1

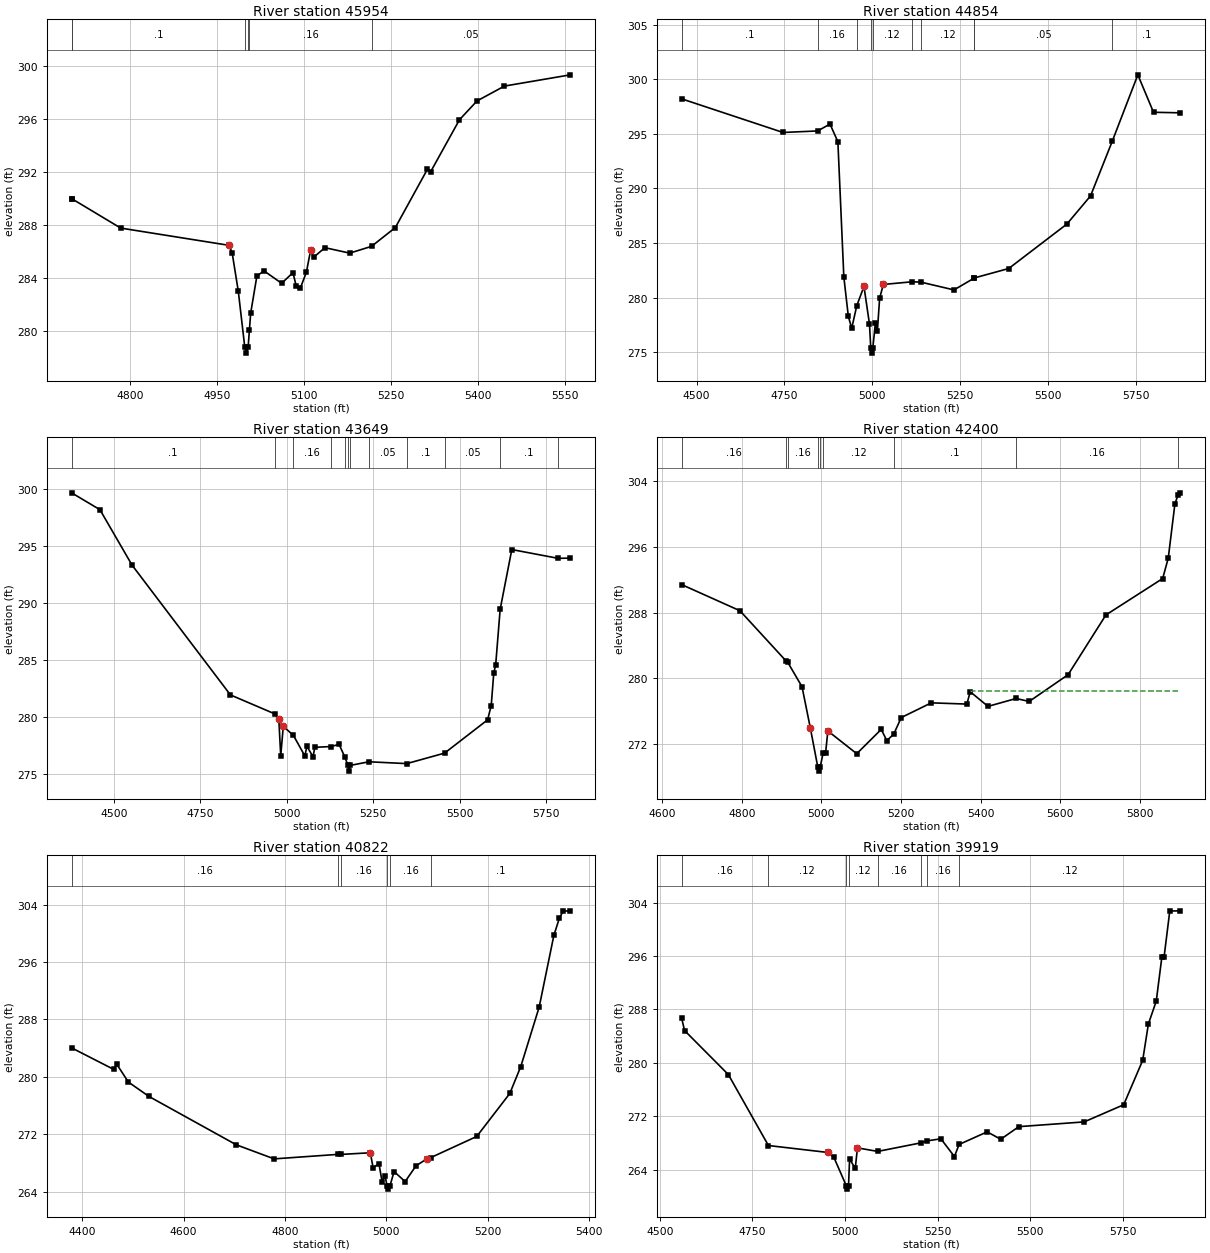
Type RM Length L Ch R = 1 ,45954   ,1100,1100,1100
BEGIN DESCRIPTION:
ALLCORN CREEK 54.0
END DESCRIPTION:
XS GIS Cut Line= 2
      3580832.39     10272600.96      3581133.07     10271795.02
#Sta/Elev= 30
  4699.6  289.96  4700.2  289.96  4784.3  287.75  4970.8  286.45  4976.4   285.9
  4987.1  282.97  4998.1  278.81  5000.9  278.31  5004.1  278.81  5006.3  280.09
  5008.4  281.32  5019.1  284.13  5031.4  284.52  5061.8  283.58  5081.4  284.39
  5086.7  283.41  5093.8  283.19  5104.5  284.42  5111.7  286.06    5117  285.55
  5136.5  286.27  5179.2  285.86  5216.8  286.37  5257.9  287.79  5313.2  292.19
  5318.6  291.99  5368.5  295.93  5398.8  297.35    5446  298.47  5559.8  299.32
#Mann= 6 ,-1 , 0
  4699.6     .05       0  4700.2      .1       0  4998.1     .07       0
  5004.1      .1       0  5006.3     .16       0  5216.8     .05       0
Bank Sta=4970.8,5111.7
XS Rating Curve= 0 ,0
Exp/Cntr=0.3,0.1

Type RM Length L Ch R = 1 ,44854   ,1205,1205,1205
BEGIN DESCRIPTION:
ALLCORN CREEK 53.0
END DESCRIPTION:
XS GIS Cut Line= 3
      3581767.37     10273008.64      3581862.84     10272683.16
      3581386.26     10271712.66
#Sta/Elev= 30
  4457.4  298.21  4746.1  295.13  4844.5  295.27  4879.8   295.9  4902.2  294.28
  4919.2  281.89    4932  278.28  4941.6   277.2  4956.1  279.27  4976.5  281.03
  4992.2  277.58  4995.8  275.42  4998.6  274.92  5001.8  275.42  5009.1  277.71
  5014.7  276.93  5021.1  279.94  5031.6  281.21  5112.4  281.45  5137.5  281.43
  5232.8  280.71  5290.9   281.8  5291.1  281.81  5388.7  282.67  5554.3  286.74
  5621.7  289.32  5684.2  294.38  5756.4  300.41    5801  296.98  5877.8  296.93
#Mann= 10 ,-1 , 0
  4457.4      .1       0  4844.5     .16       0  4956.1     .12       0
  4995.8     .07       0  5001.8     .12       0  5112.4     .16       0
  5137.5     .12       0  5290.9     .16       0  5291.1     .05       0
  5684.2      .1       0
Bank Sta=4976.5,5031.6
XS Rating Curve= 0 ,0
Exp/Cntr=0.3,0.1

Type RM Length L Ch R = 1 ,43649   ,1249,1249,1249
BEGIN DESCRIPTION:
ALLCORN CREEK 51.0
END DESCRIPTION:
XS GIS Cut Line= 2
      3582670.11     10272561.59      3582088.53     10271242.18
#Sta/Elev= 30
  4377.8   299.7  4459.7  298.22  4552.6  293.35  4836.9  281.96  4964.8   280.3
  4976.8  279.82  4982.3  276.62  4989.7   279.2  5018.9  278.41  5052.3  276.59
  5057.7  277.46  5075.6  276.54    5081  277.36  5128.2  277.43    5151  277.62
  5167.1  276.54  5176.8  275.77  5179.6  275.27  5182.8  275.77  5237.4  276.09
  5346.7  275.93  5455.9  276.85  5580.3  279.77  5590.8  281.03  5598.2   283.9
  5603.6  284.57  5616.6  289.47  5650.3  294.72  5784.2  293.95  5819.7  293.97
#Mann= 12 ,-1 , 0
  4377.8      .1       0  4964.8     .12       0  5018.9     .16       0
  5128.2     .12       0  5167.1      .1       0  5176.8     .07       0
  5182.8      .1       0  5237.4     .05       0  5346.7      .1       0
  5455.9     .05       0  5616.6      .1       0  5784.2     .05       0
Bank Sta=4976.8,4989.7
XS Rating Curve= 0 ,0
Exp/Cntr=0.3,0.1

Type RM Length L Ch R = 1 ,42400   ,1578,1578,1578
BEGIN DESCRIPTION:
ALLCORN CREEK 49.0
END DESCRIPTION:
XS GIS Cut Line= 3
      3583334.18     10271706.58      3583092.11     10271441.64
       3582692.1     10270641.64
#Sta/Elev= 30
    4649   291.4  4795.4  288.22  4911.1  282.12  4915.1  281.98  4951.4  278.97
  4972.4  273.92    4991   269.2  4993.8   268.7    4997   269.2  5004.6  270.94
  5010.7  270.94  5016.3  273.59  5088.9  270.82  5150.4  273.78  5164.4  272.42
  5181.6  273.18  5200.7  275.22  5276.2  277.01  5365.6  276.86    5374  278.36
  5418.7  276.58  5489.4  277.54  5522.2  277.18    5620  280.44    5715  287.71
  5857.6  292.14  5871.6  294.63  5888.3  301.22    5896  302.29  5902.3  302.57
#Mann= 9 ,-1 , 0
    4649     .16       0  4911.1     .12       0  4915.1     .16       0
    4991     .07       0    4997     .16       0  5004.6     .12       0
  5181.6      .1       0  5489.4     .16       0    5896     .05       0
#XS Ineff= 2 , 0
                         5375.21          278.47
Permanent Ineff=
       F       F
Bank Sta=4972.4,5016.3
XS Rating Curve= 0 ,0
Exp/Cntr=0.3,0.1

Type RM Length L Ch R = 1 ,40822   ,903,903,903
BEGIN DESCRIPTION:
ALLCORN CREEK 47.0
END DESCRIPTION:
XS GIS Cut Line= 3
      3583642.12     10271041.66      3583392.11     10270491.64
      3583042.07     10270341.63
#Sta/Elev= 30
  4378.7  284.05  4462.2  281.04  4467.7  281.79  4490.8  279.29  4531.4  277.29
  4703.9  270.56  4778.6   268.6  4905.5  269.23  4910.6  269.22  4968.6  269.45
  4974.1  267.35  4985.6  267.95  4991.9  265.39  4997.4  266.28  5001.6  264.89
  5004.4  264.39  5007.6  264.89  5015.5  266.84  5037.3  265.44    5059  267.65
  5080.8  268.62  5088.3  268.79  5178.7  271.72    5244   277.7  5265.7  281.45
    5302  289.72    5331  299.69  5341.9   302.1  5349.2  303.07  5363.7  303.12
#Mann= 6 ,-1 , 0
  4378.7     .16       0  4905.5     .12       0  4910.6     .16       0
  5001.6     .07       0  5007.6     .16       0  5088.3      .1       0
Bank Sta=4968.6,5080.8
XS Rating Curve= 0 ,0
Exp/Cntr=0.3,0.1

Type RM Length L Ch R = 1 ,39919   ,426,426,426
BEGIN DESCRIPTION:
ALLCORN CREEK 46.0
END DESCRIPTION:
XS GIS Cut Line= 3
      3584092.12     10270791.67      3583892.11     10270441.64
      3583092.14     10269941.66
#Sta/Elev= 30
  4559.1  286.65    4567  284.82  4685.1  278.23  4793.3   267.6  4954.3  266.56
  4969.9  265.84  5003.5  261.57  5006.2  261.07  5009.5  261.57  5012.4  265.58
  5027.7  264.17  5033.6  267.25  5088.3  266.72  5203.9  267.99  5221.9   268.3
  5258.8  268.61  5295.4  265.95  5307.9  267.76  5383.8  269.65  5420.4  268.54
  5469.3  270.43  5645.6  271.14  5752.3  273.71  5803.6  280.36    5819  285.82
  5840.2  289.23  5855.5   295.9  5861.4  295.87  5876.7  302.73  5905.6  302.76
#Mann= 8 ,-1 , 0
  4559.1     .16       0  4793.3     .12       0  5003.5     .07       0
  5009.5     .12       0  5088.3     .16       0  5203.9     .05       0
  5221.9     .16       0  5307.9     .12       0
Bank Sta=4954.3,5033.6
XS Rating Curve= 0 ,0
Exp/Cntr=0.3,0.1