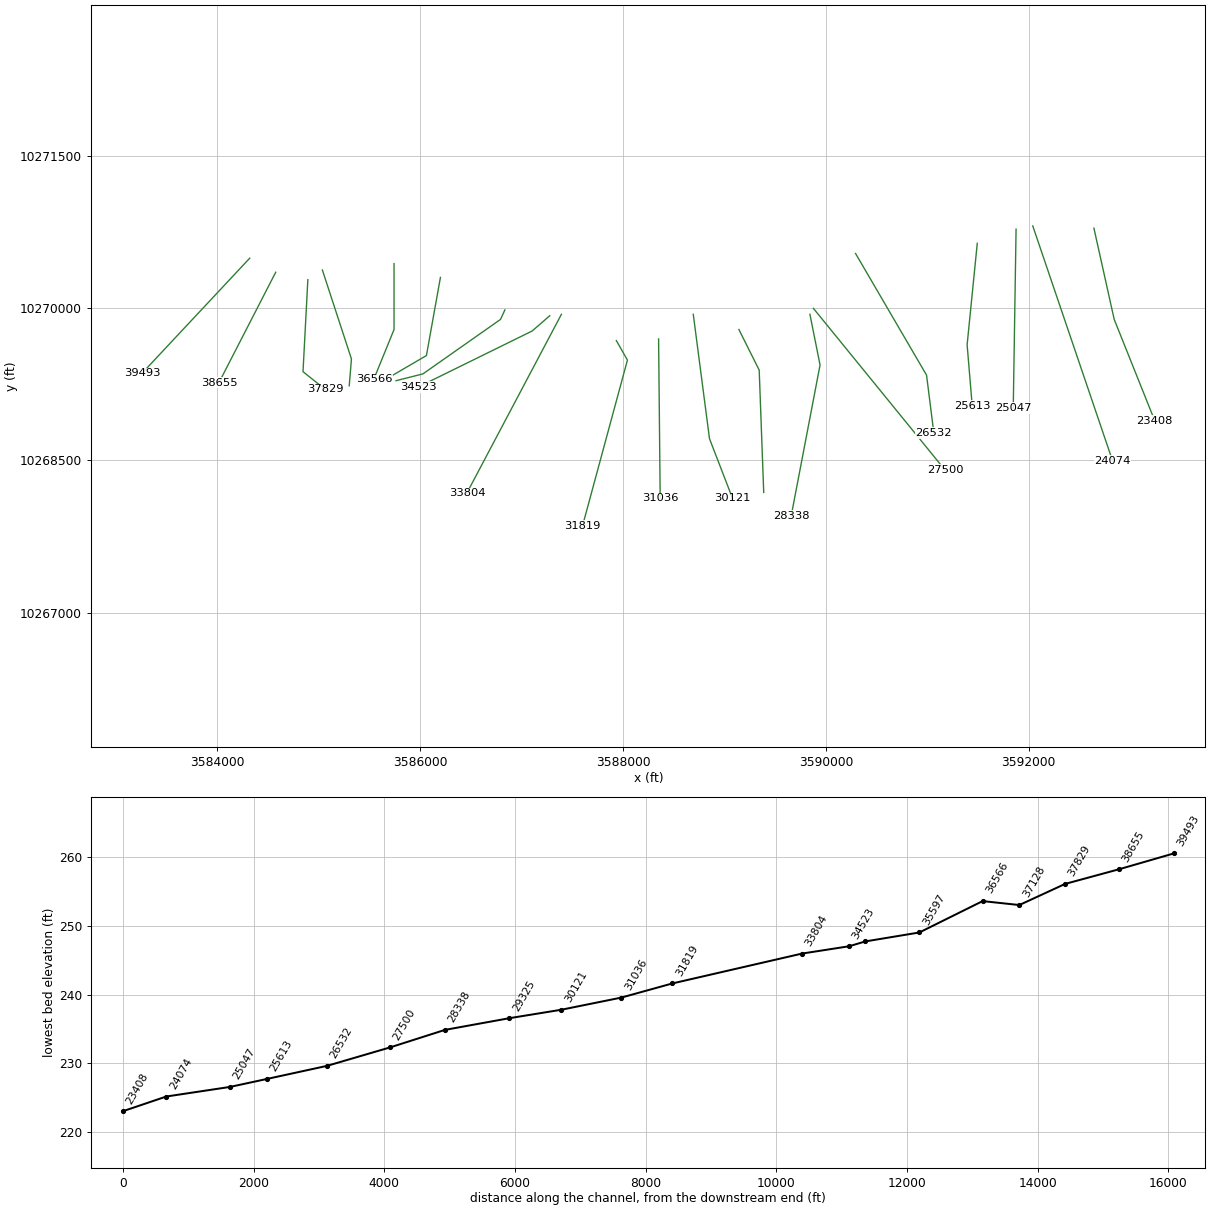
HEC-RAS study ALLCORN CREEK.prj: ALLCORN CREEK Base Level Engineering

--- ALLCORN CREEK.g01 (geometry) --- (continued)

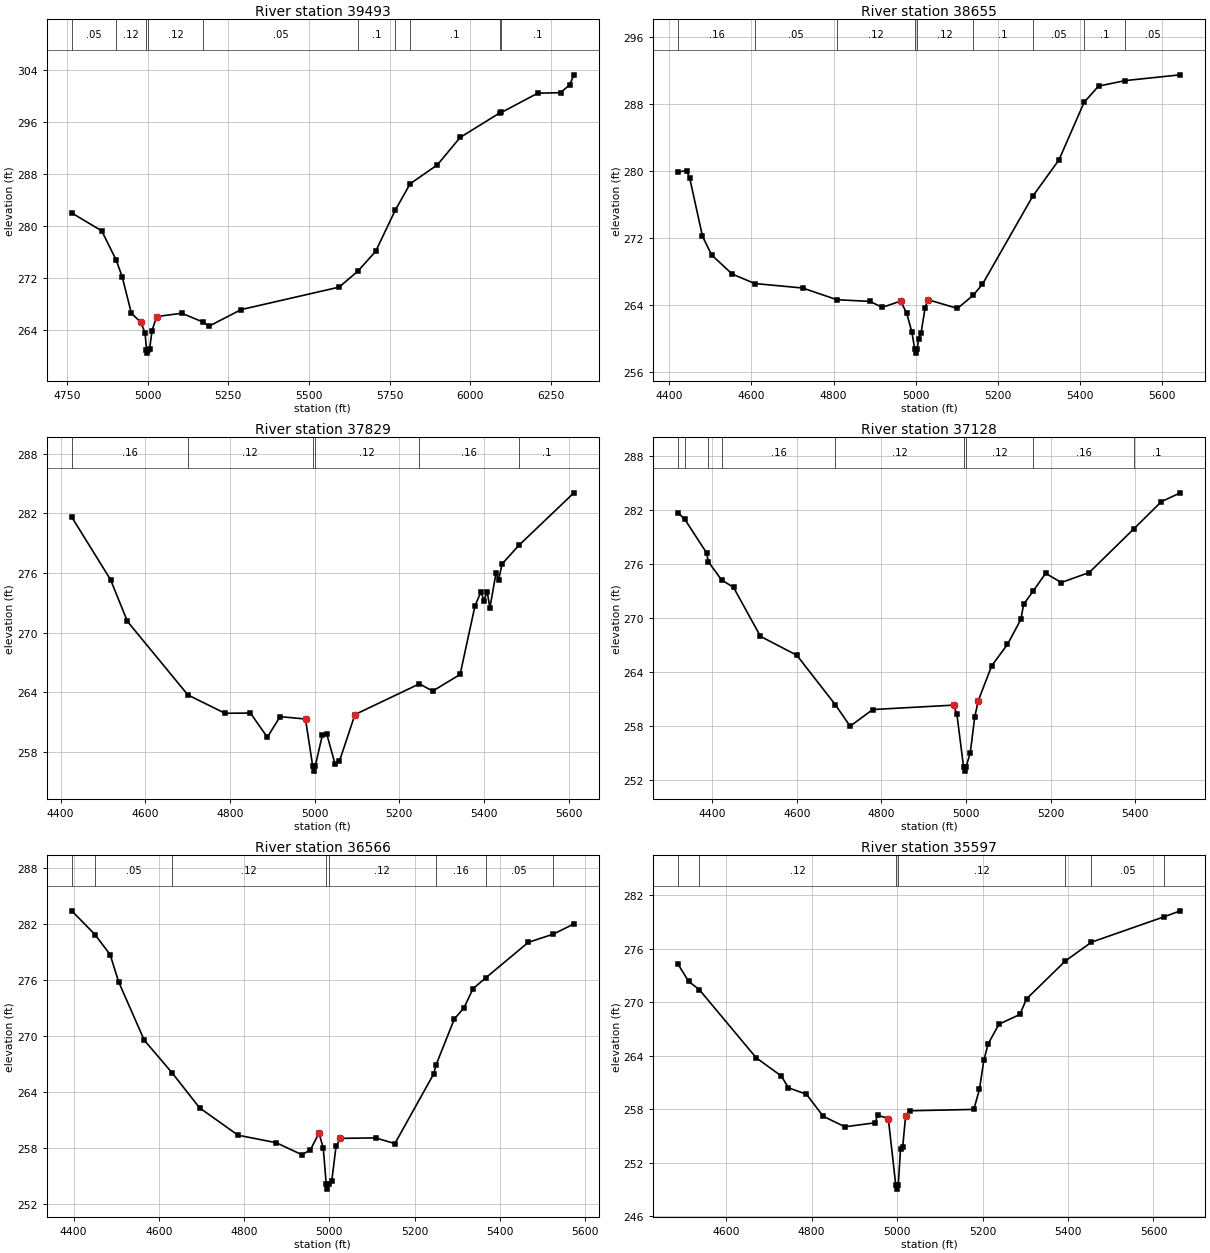
Type RM Length L Ch R = 1 ,39493   ,838,838,838
BEGIN DESCRIPTION:
ALLCORN CREEK 45.0
END DESCRIPTION:
XS GIS Cut Line= 2
      3584319.41     10270495.63      3583256.57     10269359.05
#Sta/Elev= 30
  4765.1  282.01  4857.9  279.27  4902.2  274.84  4921.4  272.22  4949.8  266.62
  4978.1  265.28  4992.3  263.63  4996.6     261  4999.3   260.5  5002.6     261
  5006.4  261.15  5013.8  263.93  5027.9  266.11  5105.6  266.62  5171.2  265.29
  5190.6  264.64  5289.8  267.18  5593.6  270.63  5651.7  273.08  5706.9  276.13
  5767.2   282.4  5813.4  286.48    5898   289.4  5968.8  293.61  6092.6  297.41
  6096.3  297.44  6209.1   300.4    6280  300.48  6308.3   301.7  6321.2  303.22
#Mann= 10 ,-1 , 0
  4765.1     .05       0  4902.2     .12       0  4996.6     .07       0
  5002.6     .12       0  5171.2     .05       0  5651.7      .1       0
  5767.2     .05       0  5813.4      .1       0  6092.6     .05       0
  6096.3      .1       0
Bank Sta=4978.1,5027.9
XS Rating Curve= 0 ,0
Exp/Cntr=0.3,0.1

Type RM Length L Ch R = 1 ,38655   ,826,826,826
BEGIN DESCRIPTION:
ALLCORN CREEK 44.0
END DESCRIPTION:
XS GIS Cut Line= 2
       3584575.5     10270356.75      3584016.37     10269268.82
#Sta/Elev= 30
  4421.5  279.87    4442  280.05  4449.7  279.12  4480.7  272.19  4502.9  269.95
  4552.9  267.67  4607.8  266.53  4724.7  265.99  4808.4  264.59  4888.2  264.39
  4918.7  263.68  4963.1  264.42  4978.2  262.99  4990.9  260.68  4997.7   258.7
  5000.4   258.2  5003.7   258.7  5007.5  259.95  5013.1   260.6  5023.1  263.64
  5029.7   264.6  5101.8  263.55  5139.9  265.11  5162.7  266.44    5285  276.96
  5349.2  281.33  5410.4  288.21  5445.5  290.15  5510.5  290.81  5644.7   291.5
#Mann= 9 ,-1 , 0
  4421.5     .16       0  4607.8     .05       0  4808.4     .12       0
  4997.7     .07       0  5003.7     .12       0  5139.9      .1       0
    5285     .05       0  5410.4      .1       0  5510.5     .05       0
Bank Sta=4963.1,5029.7
XS Rating Curve= 0 ,0
Exp/Cntr=0.3,0.1

Type RM Length L Ch R = 1 ,37829   ,701,701,701
BEGIN DESCRIPTION:
ALLCORN CREEK 42.0
END DESCRIPTION:
XS GIS Cut Line= 3
      3584892.36     10270283.03      3584844.61     10269375.87
       3585061.6     10269202.28
#Sta/Elev= 30
  4426.4  281.62  4517.9  275.33    4558  271.12  4700.8  263.73  4788.3  261.89
  4848.4  261.91  4888.4  259.48  4918.5  261.55  4978.6  261.31  4995.6  256.57
  4998.3  256.07  5001.6  256.57  5018.6  259.73  5028.6  259.83  5048.7  256.74
  5058.7  257.06  5095.4  261.76  5247.8  264.85    5279  264.12  5343.8  265.79
    5379  272.69  5393.4  274.12  5399.8  273.23  5407.8   274.1  5414.2   272.5
  5428.6  275.96    5435  275.34  5443.1  276.91  5483.2   278.8  5612.7  284.06
#Mann= 6 ,-1 , 0
  4426.4     .16       0  4700.8     .12       0  4995.6     .07       0
  5001.6     .12       0  5247.8     .16       0  5483.2      .1       0
Bank Sta=4978.6,5095.4
XS Rating Curve= 0 ,0
Exp/Cntr=0.3,0.1

Type RM Length L Ch R = 1 ,37128   ,562,562,562
BEGIN DESCRIPTION:
ALLCORN CREEK 41.0
END DESCRIPTION:
XS GIS Cut Line= 3
      3585035.59     10270378.45      3585322.04     10269501.74
      3585300.34     10269236.95
#Sta/Elev= 30
    4319  281.69  4334.3  280.99  4386.1  277.25  4390.2  276.27  4421.6  274.24
  4449.9  273.41  4513.7  267.97  4599.7  265.87  4691.1  260.36  4725.9  257.99
  4779.2  259.84  4970.5  260.33  4978.4  259.33  4994.1   253.5  4996.9     253
  5000.1   253.5    5010     255  5020.5  258.98    5029  260.83  5060.9  264.71
    5098  267.07  5129.9  269.86  5136.2  271.52  5159.4  273.03  5188.4  274.97
  5225.5  273.95  5291.6  275.06  5396.4  279.88  5462.2  282.93    5507  283.91
#Mann= 9 ,-1 , 0
    4319     .05       0  4334.3      .1       0  4390.2     .05       0
  4421.6     .16       0  4691.1     .12       0  4994.1     .07       0
  5000.1     .12       0  5159.4     .16       0  5396.4      .1       0
Bank Sta=4970.5,5029
XS Rating Curve= 0 ,0
Exp/Cntr=0.3,0.1

Type RM Length L Ch R = 1 ,36566   ,969,969,969
BEGIN DESCRIPTION:
ALLCORN CREEK 39.0
END DESCRIPTION:
XS GIS Cut Line= 3
      3585742.11     10270441.65      3585742.11     10269791.64
      3585543.03     10269302.62
#Sta/Elev= 30
  4395.9  283.45  4450.3   280.9  4485.9  278.75  4505.9  275.82  4565.9  269.56
  4631.4  266.05  4695.9  262.29  4785.9  259.36  4875.9  258.55  4935.9  257.26
  4955.9   257.8  4975.9  259.59  4985.9  257.97  4992.9  254.07  4995.7  253.57
  4998.9  254.07  5005.9  254.48  5015.9  258.17  5025.9  259.02  5108.8  259.07
  5153.9  258.46  5245.2  265.96    5250  266.85  5293.4  271.84  5315.8  273.02
  5337.4   275.1  5366.7  276.24    5467  280.07  5524.6  280.93  5573.9  282.04
#Mann= 8 ,-1 , 0
  4395.9     .16       0  4450.3     .05       0  4631.4     .12       0
  4992.9     .07       0  4998.9     .12       0    5250     .16       0
  5366.7     .05       0  5524.6     .16       0
Bank Sta=4975.9,5025.9
XS Rating Curve= 0 ,0
Exp/Cntr=0.3,0.1

Type RM Length L Ch R = 1 ,35597   ,827,827,827
BEGIN DESCRIPTION:
Mapping XS e6e2f88c
END DESCRIPTION:
XS GIS Cut Line= 3
      3586199.39     10270305.75      3586061.38     10269534.96
      3585722.84     10269337.04
#Sta/Elev= 30
  4487.6  274.24  4512.1  272.33    4537  271.41  4670.2  263.76    4729  261.71
  4745.7  260.39  4787.9  259.66    4827  257.19  4877.8  256.01  4948.9  256.46
  4954.2  257.32  4979.4  256.93  4996.7  249.51  4999.5  249.01  5002.7  249.51
    5008  253.49  5013.1  253.75    5020  257.26  5030.2  257.81  5179.5  257.96
  5192.7  260.21  5202.9  263.46  5213.1  265.32  5238.3  267.53  5287.2  268.62
  5302.9  270.37  5393.7  274.63  5454.9  276.74  5625.4   279.6  5662.8  280.26
#Mann= 7 ,-1 , 0
  4487.6     .05       0    4537     .12       0  4996.7     .07       0
  5002.7     .12       0  5393.7     .16       0  5454.9     .05       0
  5625.4     .16       0
Bank Sta=4979.4,5020
XS Rating Curve= 0 ,0
Exp/Cntr=0.3,0.1

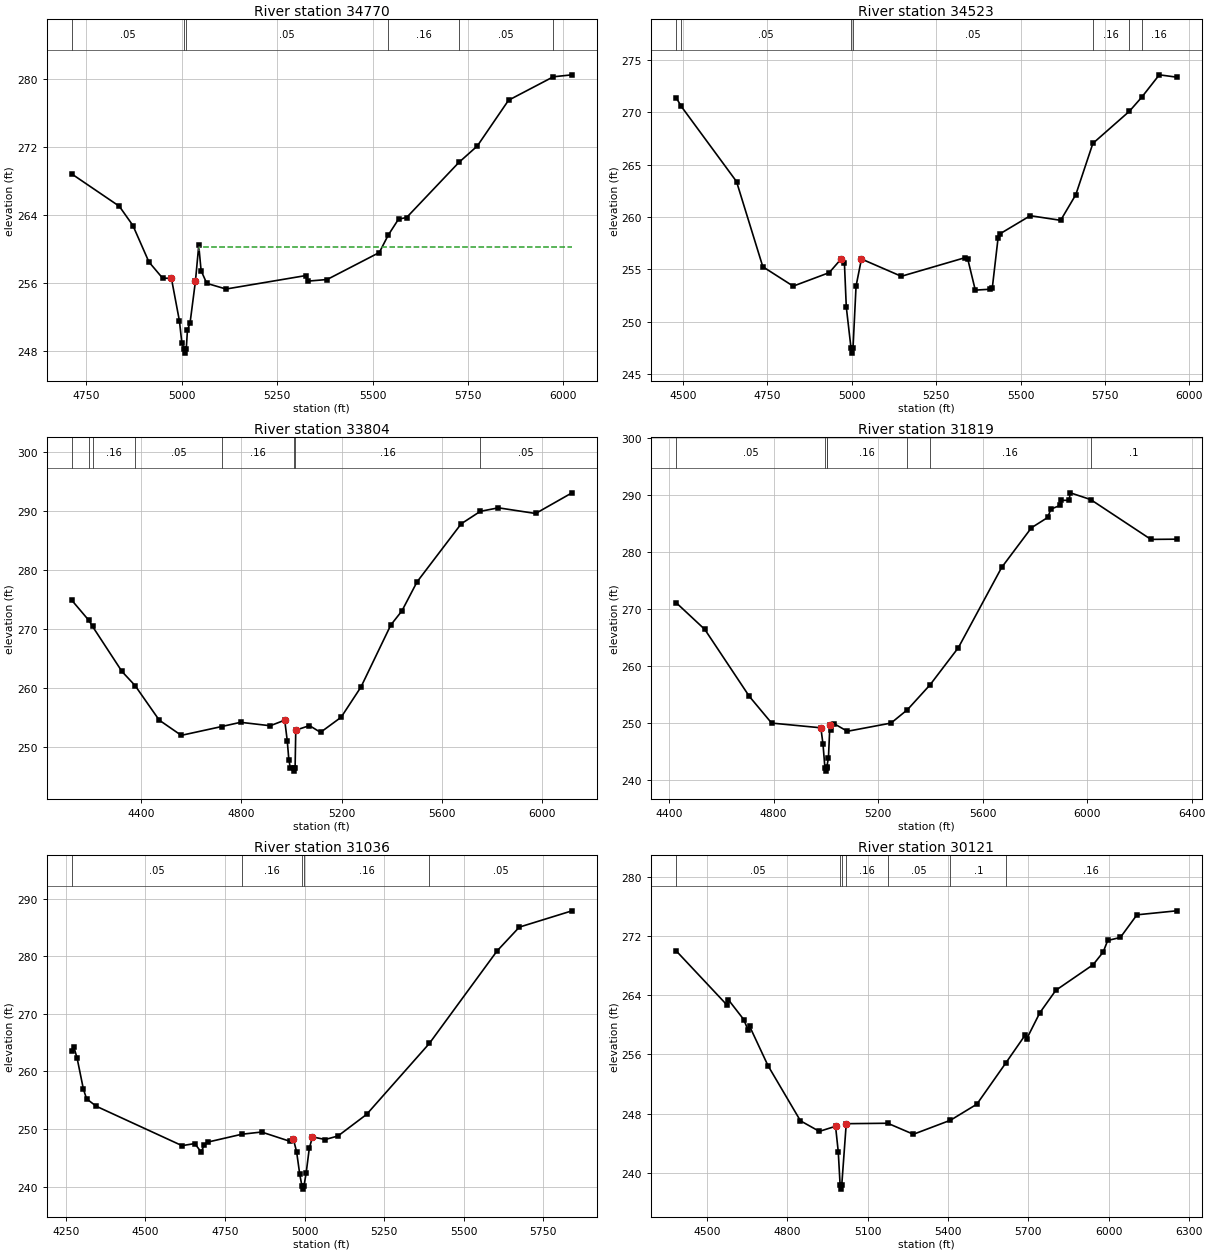
Type RM Length L Ch R = 1 ,34770   ,247,247,247
BEGIN DESCRIPTION:
ALLCORN CREEK 38.0
END DESCRIPTION:
XS GIS Cut Line= 4
      3586834.72     10269984.95      3586792.11     10269891.64
      3586026.56     10269353.87       3585761.8     10269287.04
#Sta/Elev= 30
  4711.3  268.82  4836.1  265.01  4871.8  262.74  4913.7  258.45  4949.4  256.55
  4972.7  256.51  4993.8  251.47  4999.9  248.95  5005.6  248.21  5008.4  247.71
  5011.6  248.21  5014.7  250.41  5021.6  251.29  5035.7  256.21  5044.3  260.39
  5050.5  257.42  5065.3  255.93  5115.8  255.26  5324.1  256.84  5330.2  256.19
  5380.7  256.38  5517.5  259.56  5540.8   261.6    5568   263.5    5589  263.68
    5726  270.17  5774.2   272.1  5856.3   277.5  5973.6  280.26  6022.5  280.49
#Mann= 6 ,-1 , 0
  4711.3     .05       0  5005.6     .03       0  5011.6     .05       0
  5540.8     .16       0    5726     .05       0  5973.6     .16       0
#XS Ineff= 2 , 0
                         5045.71          260.22
Permanent Ineff=
       F       F
Bank Sta=4972.7,5035.7
XS Rating Curve= 0 ,0
Exp/Cntr=0.3,0.1

Type RM Length L Ch R = 1 ,34523   ,719,719,719
BEGIN DESCRIPTION:
ALLCORN CREEK 37.0
END DESCRIPTION:
XS GIS Cut Line= 3
       3587277.4     10269927.64      3587103.94     10269777.16
      3585980.54     10269224.53
#Sta/Elev= 30
  4480.2  271.37  4495.2  270.55  4658.8  263.38  4736.7  255.25  4826.6   253.4
  4933.4  254.69  4968.2  255.98  4978.3  255.64  4983.9   251.4  4997.8  247.51
  5000.5  247.01  5003.8  247.51  5012.8  253.41  5028.8  255.99  5146.8  254.34
    5336  256.12  5343.4  256.01  5365.9  253.02  5410.9  253.11  5416.4  253.27
  5433.3  257.98  5438.9  258.39  5528.8  260.12  5618.7  259.68  5663.6  262.13
  5714.1  267.02  5822.1  270.08  5858.4  271.41  5910.8  273.56  5961.8  273.34
#Mann= 7 ,-1 , 0
  4480.2     .16       0  4495.2     .05       0  4997.8     .03       0
  5003.8     .05       0  5714.1     .16       0  5822.1     .05       0
  5858.4     .16       0
Bank Sta=4968.2,5028.8
XS Rating Curve= 0 ,0
Exp/Cntr=0.3,0.1

Type RM Length L Ch R = 1 ,33804   ,1985,1985,1985
BEGIN DESCRIPTION:
ALLCORN CREEK 36.0
END DESCRIPTION:
XS GIS Cut Line= 2
      3587392.11     10269941.66      3586459.69     10268177.62
#Sta/Elev= 30
  4123.8  274.92  4192.6  271.47  4206.9  270.47  4324.4  262.83  4376.7  260.44
  4472.9  254.59  4560.9  252.01  4721.6   253.5  4797.4  254.22  4915.6  253.64
  4973.4  254.58  4983.5   251.1  4989.8  247.92  4995.5  246.53  5008.8  246.45
  5011.6  245.95  5014.8  246.45  5017.5  252.89  5072.2  253.66  5116.2  252.52
  5198.4  255.08  5277.5   260.2  5396.7  270.72  5440.7  273.09  5501.1  278.01
  5677.2  287.85  5753.4  289.96  5825.6  290.56    5974   289.6  6119.1   293.1
#Mann= 8 ,-1 , 0
  4123.8     .16       0  4192.6     .05       0  4206.9     .16       0
  4376.7     .05       0  4721.6     .16       0  5008.8     .07       0
  5014.8     .16       0  5753.4     .05       0
Bank Sta=4973.4,5017.5
XS Rating Curve= 0 ,0
Exp/Cntr=0.3,0.1

Type RM Length L Ch R = 1 ,31819   ,783,783,783
BEGIN DESCRIPTION:
ALLCORN CREEK 33.0
END DESCRIPTION:
XS GIS Cut Line= 3
      3587933.68     10269682.87      3588043.05     10269490.16
      3587600.59     10267855.67
#Sta/Elev= 30
  4427.2  271.11  4536.6  266.44    4707  254.71  4792.3  250.03  4980.8   249.2
  4989.1  246.32  4996.5  242.11  4999.2  241.61  5002.5  242.11  5003.8  242.42
  5009.8  243.87  5015.5  249.72  5020.7  248.75  5030.6  249.94  5082.4  248.59
  5249.4  250.03  5312.4  252.38  5398.8  256.73  5507.1  263.24  5672.9   277.3
  5786.8  284.25    5849  286.05  5861.2  287.52  5895.9  288.15  5901.1  289.05
  5930.6  289.06  5935.8  290.37  6013.5  289.19  6244.2  282.21  6342.1  282.25
#Mann= 7 ,-1 , 0
  4427.2     .05       0  4996.5    .035       0  5002.5     .05       0
  5003.8     .16       0  5312.4     .05       0  5398.8     .16       0
  6013.5      .1       0
Bank Sta=4980.8,5015.5
XS Rating Curve= 0 ,0
Exp/Cntr=0.3,0.1

Type RM Length L Ch R = 1 ,31036   ,915,915,915
BEGIN DESCRIPTION:
ALLCORN CREEK 32.0
END DESCRIPTION:
XS GIS Cut Line= 2
      3588350.34     10269698.54      3588365.96     10268126.12
#Sta/Elev= 30
  4268.1  263.57    4275   264.2    4285  262.35    4305   256.9    4315  255.24
    4345  253.96    4615   247.1    4655  247.47    4675  245.99    4685  247.25
    4695  247.71  4803.2  249.09    4865  249.47    4955  247.84    4965   248.2
    4975  246.06    4985   242.1    4992  240.05  4994.8  239.55    4998  240.05
    5005  242.32    5015  246.67    5025  248.62    5065  248.17    5105  248.78
    5195  252.53  5392.4  264.87  5605.1  280.93  5675.1  285.07  5840.6   287.9
#Mann= 5 ,-1 , 0
  4268.1     .05       0  4803.2     .16       0    4992     .07       0
    4998     .16       0  5392.4     .05       0
Bank Sta=4965,5025
XS Rating Curve= 0 ,0
Exp/Cntr=0.3,0.1

Type RM Length L Ch R = 1 ,30121   ,796,796,796
BEGIN DESCRIPTION:
ALLCORN CREEK 31.0
END DESCRIPTION:
XS GIS Cut Line= 3
      3588692.11     10269941.62      3588852.12     10268714.93
       3589079.3     10268126.12
#Sta/Elev= 30
  4384.8  270.01  4574.7  262.68  4579.7   263.4  4636.9  260.73  4653.7  259.25
  4658.7  259.83  4727.7  254.48  4848.7  247.03  4919.3   245.6  4979.8  246.29
  4989.9  242.85  4996.9  238.29  4999.7  237.79  5002.9  238.29  5019.7  246.64
  5174.5   246.7  5270.5  245.21    5409  247.11  5507.5  249.28  5616.7  254.91
  5687.8  258.62  5693.2  258.09  5742.4  261.63  5802.3  264.68  5941.5  268.14
  5979.1  269.85    5996  271.42  6043.4  271.83  6105.2  274.89    6253  275.43
#Mann= 7 ,-1 , 0
  4384.8     .05       0  4996.9    .035       0  5002.9     .05       0
  5019.7     .16       0  5174.5     .05       0    5409      .1       0
  5616.7     .16       0
Bank Sta=4979.8,5019.7
XS Rating Curve= 0 ,0
Exp/Cntr=0.3,0.1

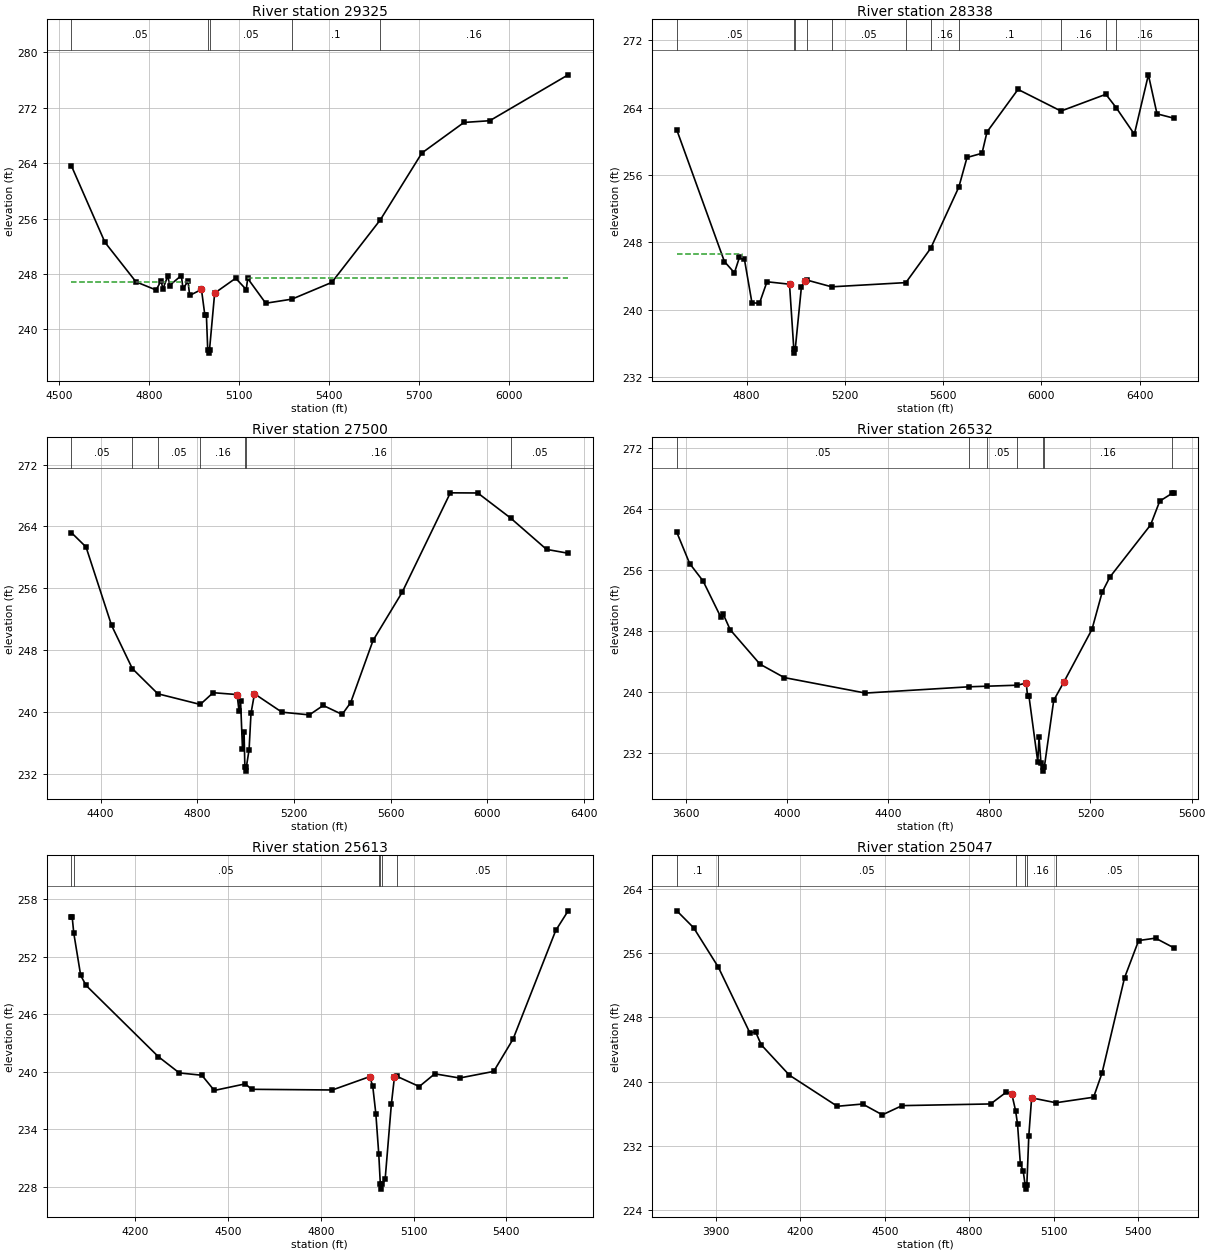
Type RM Length L Ch R = 1 ,29325   ,987,987,987
BEGIN DESCRIPTION:
ALLCORN CREEK 30.0
END DESCRIPTION:
XS GIS Cut Line= 3
      3589142.09     10269791.66      3589342.11     10269391.64
      3589386.73     10268184.81
#Sta/Elev= 30
  4541.5  263.63  4653.3  252.57  4756.7  246.86  4823.8  245.68  4840.6  247.04
  4846.2   245.8    4863  247.75  4868.5  246.33  4907.7  247.77  4913.3   245.9
    4930  246.92  4935.6  244.89  4974.8  245.76  4985.9  242.13  4991.2  242.13
  4995.7  237.06  4998.5  236.56  5001.7  237.06  5018.8  245.23  5088.8  247.38
  5123.9  245.75  5128.9  247.35  5188.9  243.77  5276.2  244.36    5409  246.78
  5570.7  255.82  5709.2  265.48  5849.3  269.89  5935.2  270.14  6196.4  276.77
#Mann= 5 ,-1 , 0
  4541.5     .05       0  4995.7     .03       0  5001.7     .05       0
  5276.2      .1       0  5570.7     .16       0
#XS Ineff= 2 , 0
         4932.12  246.83  5128.6           247.4
Permanent Ineff=
       F       F
Bank Sta=4974.8,5018.8
XS Rating Curve= 0 ,0
Exp/Cntr=0.3,0.1

Type RM Length L Ch R = 1 ,28338   ,838,838,838
BEGIN DESCRIPTION:
ALLCORN CREEK 28.0
END DESCRIPTION:
XS GIS Cut Line= 3
       3589842.1     10269941.69      3589942.11     10269441.64
      3589657.92     10267955.21
#Sta/Elev= 30
  4515.6  261.34  4709.4  245.73  4750.2  244.39  4770.6  246.23    4791  245.99
  4821.6  240.83  4852.2  240.78  4882.8  243.33  4974.6  243.04    4992  235.36
  4994.7  234.86    4998  235.36    5023  242.71  5035.7  243.39  5045.5  243.53
  5146.2  242.73  5448.5  243.23  5549.3  247.29  5664.2  254.57  5697.5  258.08
  5758.6  258.58  5778.9  261.11  5905.2  266.16  6080.2  263.59    6263  265.58
  6304.5  264.01    6379  260.84  6436.2  267.89  6471.3  263.26  6538.9  262.75
#Mann= 11 ,-1 , 0
  4515.6     .05       0    4992    .035       0    4998     .05       0
  5045.5     .16       0  5146.2     .05       0  5448.5      .1       0
  5549.3     .16       0  5664.2      .1       0  6080.2     .16       0
    6263      .1       0  6304.5     .16       0
#XS Ineff= 2 , 0
         4781.41  246.67
Permanent Ineff=
       F       F
Bank Sta=4974.6,5035.7
XS Rating Curve= 0 ,0
Exp/Cntr=0.3,0.1

Type RM Length L Ch R = 1 ,27500   ,968,968,968
BEGIN DESCRIPTION:
ALLCORN CREEK 27.0
END DESCRIPTION:
XS GIS Cut Line= 2
      3589876.36      10270000.6      3591173.28      10268406.8
#Sta/Elev= 30
  4279.1  263.19  4339.7  261.33  4445.4  251.18  4531.2  245.59  4636.7  242.33
  4812.2  240.95  4865.4  242.47  4964.5  242.23  4972.5   240.1  4978.9  241.37
  4986.8  235.22  4993.3  237.44  4996.7  232.82  4999.5  232.32  5002.7  232.82
  5014.1  235.09    5022  239.79  5036.4  242.33  5149.8  239.95  5263.3   239.6
  5320.8  240.82  5399.1  239.66  5434.3  241.19  5526.9  249.24  5646.8  255.44
  5846.5  268.34    5960  268.32  6095.6  265.08  6244.4  261.02  6333.9  260.52
#Mann= 7 ,-1 , 0
  4279.1     .05       0  4531.2     .16       0  4636.7     .05       0
  4812.2     .16       0  4996.7     .07       0  5002.7     .16       0
  6095.6     .05       0
Bank Sta=4964.5,5036.4
XS Rating Curve= 0 ,0
Exp/Cntr=0.3,0.1

Type RM Length L Ch R = 1 ,26532   ,919,919,919
BEGIN DESCRIPTION:
ALLCORN CREEK 25.0
END DESCRIPTION:
XS GIS Cut Line= 3
      3590292.13     10270541.61      3590992.11     10269341.64
      3591063.88     10268771.44
#Sta/Elev= 30
  3564.8  260.92  3615.6  256.83  3668.5  254.55  3738.8   249.8  3748.7  250.16
    3776  248.15  3893.5  243.65  3989.4  241.89  4310.2  239.86  4718.8  240.68
  4791.5  240.76  4910.4  240.89  4946.1  241.17  4951.1  239.54  4956.5  239.54
  4991.7  230.85  4996.7  234.08  5004.4  230.67  5011.5  230.13  5014.2  229.63
  5017.5  230.13  5054.8  238.91  5095.1  241.32    5206  248.21  5246.3  253.08
  5276.5  255.05  5437.8   261.9  5473.8  265.01  5522.5  266.03  5528.7   266.1
#Mann= 7 ,-1 , 0
  3564.8     .05       0  4718.8     .16       0  4791.5     .05       0
  4910.4     .16       0  5011.5     .07       0  5017.5     .16       0
  5522.5     .05       0
Bank Sta=4946.1,5095.1
XS Rating Curve= 0 ,0
Exp/Cntr=0.3,0.1

Type RM Length L Ch R = 1 ,25613   ,566,566,566
BEGIN DESCRIPTION:
ALLCORN CREEK 24.0
END DESCRIPTION:
XS GIS Cut Line= 3
       3591492.1     10270641.63      3591392.11     10269641.64
      3591442.11     10269041.59
#Sta/Elev= 30
  3992.8   256.2  3995.3   256.2  4000.5  254.49  4022.9  250.06  4040.5  249.01
  4274.2  241.57    4342  239.87  4414.9  239.63  4455.1  238.04  4555.6  238.73
  4575.7  238.16    4837  238.09  4957.6  239.48  4967.6  238.52  4977.7  235.62
  4987.1  231.44  4992.3  228.23    4995  227.73  4998.3  228.23  5007.8  228.76
  5027.9  236.59  5037.9  239.44  5046.4  239.51  5118.2  238.45  5168.4  239.78
  5248.6  239.34    5359  240.03  5421.7  243.41  5559.7  254.76  5599.9  256.81
#Mann= 6 ,-1 , 0
  3992.8      .1       0  4000.5     .05       0  4987.1     .16       0
  4992.3     .07       0  4998.3     .16       0  5046.4     .05       0
Bank Sta=4957.6,5037.9
XS Rating Curve= 0 ,0
Exp/Cntr=0.3,0.1

Type RM Length L Ch R = 1 ,25047   ,973,973,973
BEGIN DESCRIPTION:
ALLCORN CREEK 23.0
END DESCRIPTION:
XS GIS Cut Line= 2
      3591874.65     10270781.36      3591846.87     10269017.48
#Sta/Elev= 30
  3761.6   261.3  3821.3  259.19    3909  254.27  4021.3  246.05  4041.4  246.19
  4061.4  244.58  4161.4  240.79  4331.4  236.91  4421.4  237.19  4491.4  235.84
  4561.4  236.99    4876   237.2  4931.5  238.67  4951.5  238.38  4964.5  236.37
  4971.5  234.68  4981.5  229.71  4991.5  228.85  4998.5  227.07  5001.2  226.57
  5004.5  227.07  5011.5  233.22  5021.5  237.96  5107.7  237.35  5241.5  238.04
  5271.5  241.05  5351.5  252.95  5401.5  257.59  5461.5  257.89  5525.7   256.7
#Mann= 6 ,-1 , 0
  3761.6      .1       0    3909     .05       0  4964.5     .16       0
  4998.5     .07       0  5004.5     .16       0  5107.7     .05       0
Bank Sta=4951.5,5021.5
XS Rating Curve= 0 ,0
Exp/Cntr=0.3,0.1

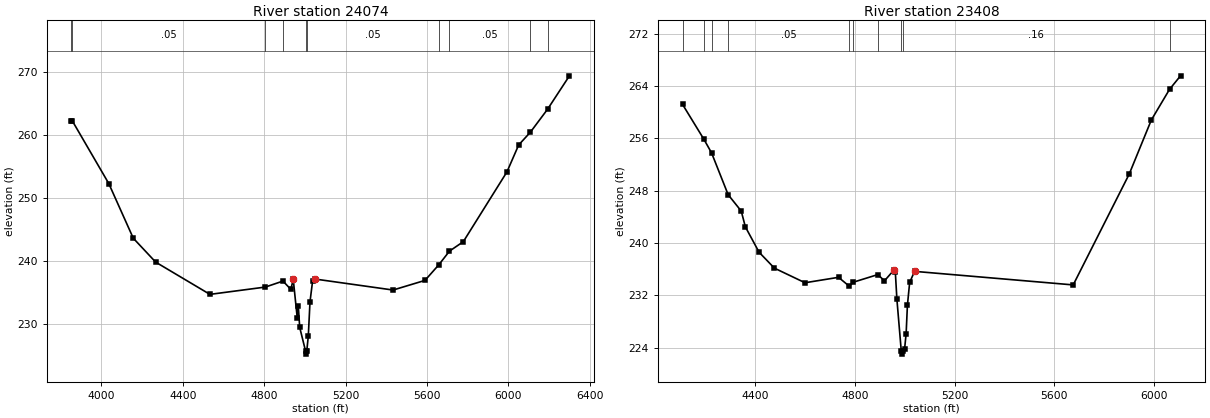
Type RM Length L Ch R = 1 ,24074   ,666,666,666
BEGIN DESCRIPTION:
ALLCORN CREEK 21.0
END DESCRIPTION:
XS GIS Cut Line= 2
      3592039.19     10270813.66      3592826.02     10268496.72
#Sta/Elev= 30
  3852.9  262.22    3858  262.18  4036.4  252.27  4156.7  243.59  4266.9  239.79
  4533.4  234.67  4805.4  235.83  4892.2  236.78  4930.9  235.47  4942.8  237.04
  4962.3  230.97  4967.6  232.82  4974.5  229.43  5003.2  225.68  5005.9  225.18
  5009.2  225.68  5016.7  228.03  5025.1   233.5  5037.9   236.8  5048.4  237.11
  5433.2  235.36  5590.1  236.89  5657.5  239.35  5710.4  241.54  5778.4  243.04
  5992.9  254.13  6050.4   258.4    6108  260.43  6192.5  264.08  6299.8  269.38
#Mann= 10 ,-1 , 0
  3852.9      .1       0    3858     .05       0  4805.4     .16       0
  4892.2     .05       0  5003.2     .03       0  5009.2     .05       0
  5657.5      .1       0  5710.4     .05       0    6108      .1       0
  6192.5     .05       0
Bank Sta=4942.8,5048.4
XS Rating Curve= 0 ,0
Exp/Cntr=0.3,0.1

Type RM Length L Ch R = 1 ,23408   ,611,611,611
BEGIN DESCRIPTION:
ALLCORN CREEK 20.0
END DESCRIPTION:
XS GIS Cut Line= 3
      3592642.11     10270791.64      3592842.11     10269891.64
      3593242.11     10268891.63
#Sta/Elev= 30
  4107.9  261.18  4193.8  255.84  4224.6  253.76    4291  247.39  4343.5  244.89
  4360.2  242.47  4415.2   238.6  4476.7  236.17  4599.6  233.94  4734.1  234.77
  4777.6   233.4  4792.3  234.01  4892.1  235.19  4918.4  234.23  4956.9   235.9
    4962  235.64  4968.4  231.42  4985.9  223.54  4988.6  223.04  4991.9  223.54
  4999.1  223.76  5005.5  226.18  5010.6  230.49  5019.6  233.98  5039.3  235.68
  5676.1  233.61  5900.9  250.53  5989.8   258.8  6062.9  263.48  6106.9  265.54
#Mann= 10 ,-1 , 0
  4107.9      .1       0  4193.8     .05       0  4224.6      .1       0
    4291     .05       0  4777.6      .1       0  4792.3     .12       0
  4892.1     .16       0  4985.9     .03       0  4991.9     .16       0
  6062.9      .1       0
Bank Sta=4956.9,5039.3
XS Rating Curve= 0 ,0
Exp/Cntr=0.3,0.1