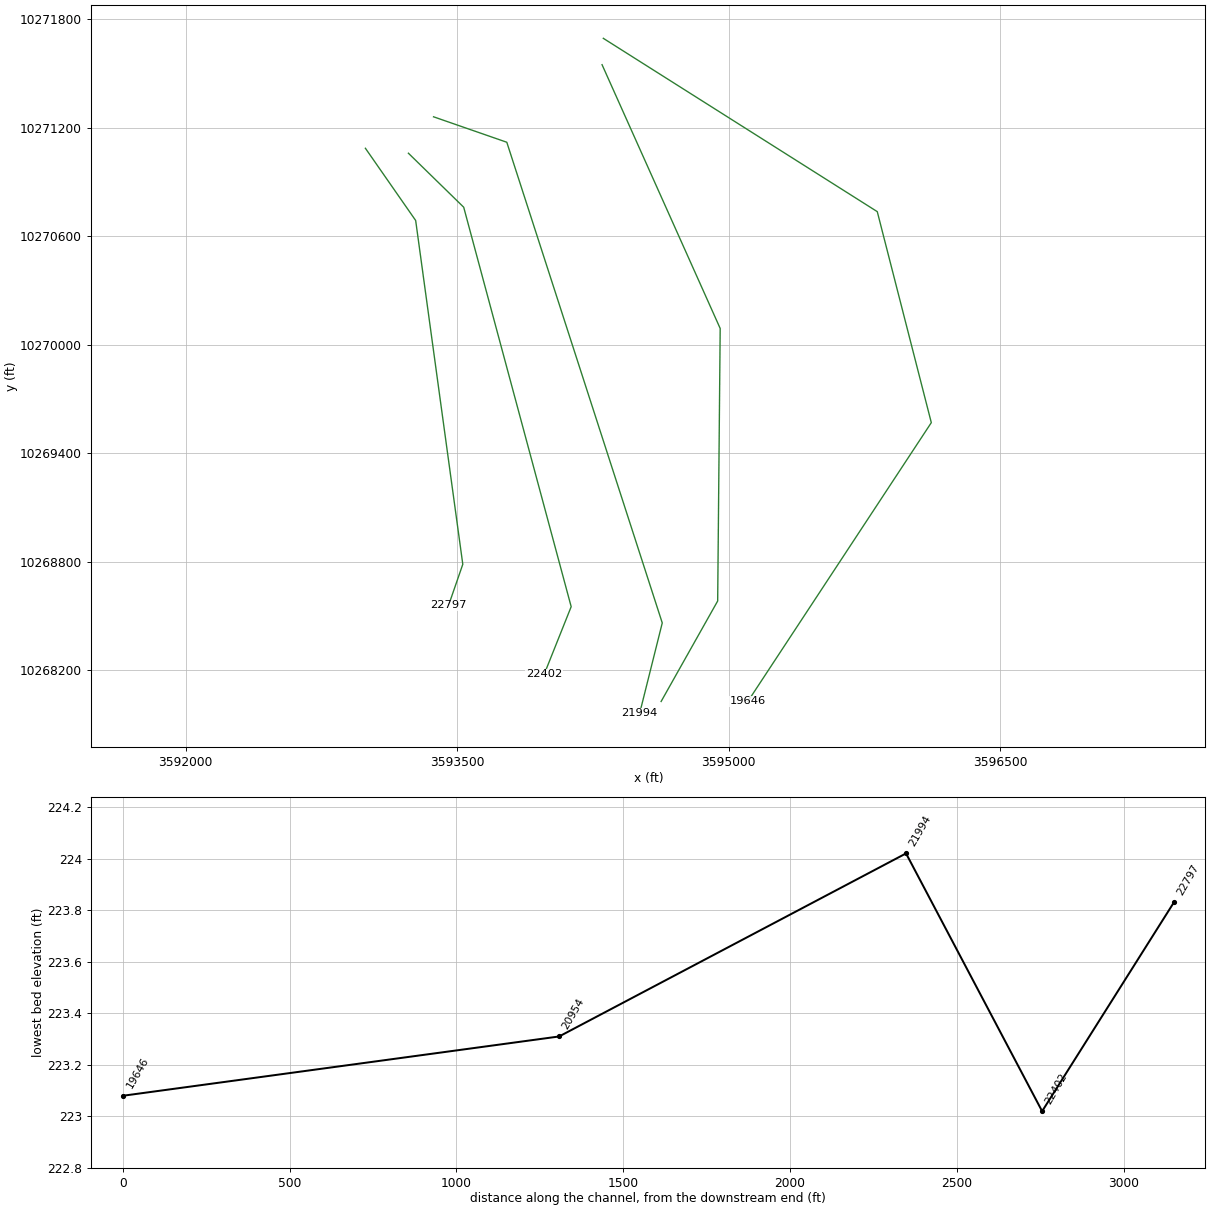
HEC-RAS study ALLCORN CREEK.prj: ALLCORN CREEK Base Level Engineering

--- ALLCORN CREEK.g01 (geometry) --- (continued)

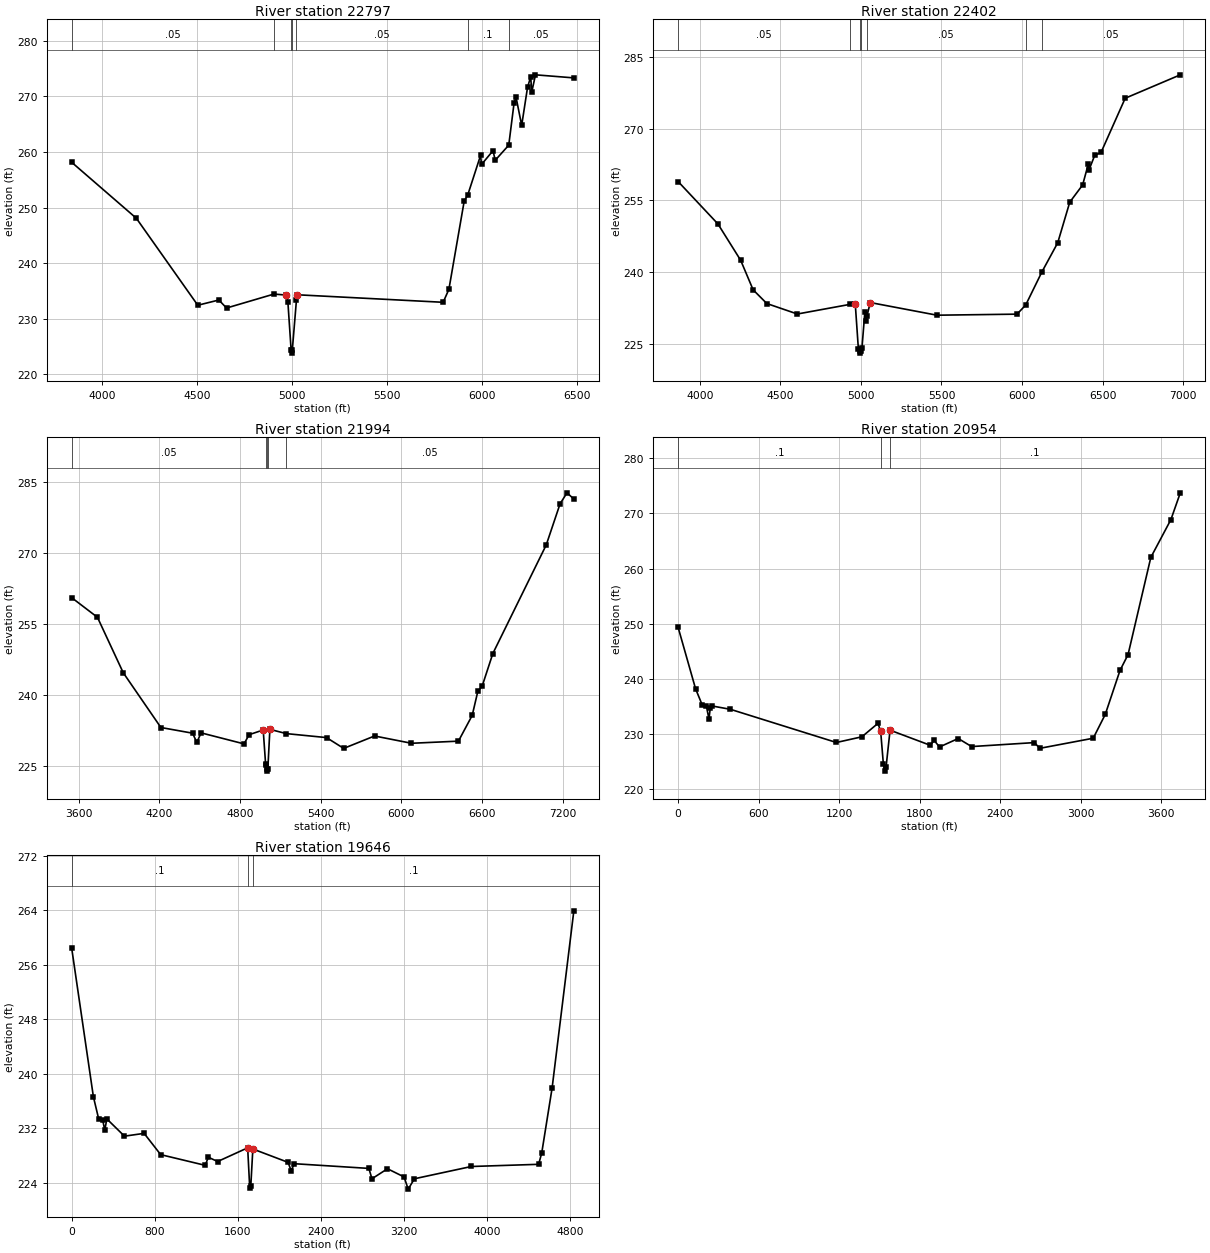
Type RM Length L Ch R = 1 ,22797   ,395,395,395
BEGIN DESCRIPTION:
ALLCORN CREEK 19.0
END DESCRIPTION:
XS GIS Cut Line= 4
      3592993.12     10271086.97      3593270.91     10270687.64
      3593531.33      10268786.6       3593453.2     10268560.89
#Sta/Elev= 30
  3838.7  258.15  4179.3  248.08  4502.8  232.44  4613.8  233.38  4654.2  231.94
    4904  234.45  4967.1  234.27  4977.2  233.02  4994.4  224.33  4997.1  223.83
  5000.4  224.33  5022.1   233.3  5027.6  234.32  5794.7  232.97    5825  235.31
  5905.8  251.22  5923.4  252.18  5991.7  259.38  5996.7  257.75  6057.2  260.23
  6068.9  258.51  6140.1  261.22  6168.2  268.82  6178.3  269.87  6208.2  264.78
  6238.9   271.6  6255.7  273.53    6261  270.75  6280.9  273.87  6482.8  273.32
#Mann= 7 ,-1 , 0
  3838.7     .05       0    4904     .16       0  4994.4     .07       0
  5000.4     .16       0  5022.1     .05       0  5923.4      .1       0
  6140.1     .05       0
Bank Sta=4967.1,5027.6
XS Rating Curve= 0 ,0
Exp/Cntr=0.3,0.1

Type RM Length L Ch R = 1 ,22402   ,408,408,408
BEGIN DESCRIPTION:
ALLCORN CREEK 16.0
END DESCRIPTION:
XS GIS Cut Line= 4
      3593230.82     10271059.59      3593536.36     10270760.99
      3594130.29     10268552.23      3593980.82     10268177.69
#Sta/Elev= 30
  3865.2  258.94  4112.2  250.07  4253.6  242.45  4330.9  236.27    4416   233.4
  4605.5  231.21  4929.5  233.21  4964.8   233.4  4984.4  223.85  4992.9  223.52
  4995.6  223.02  4998.9  223.52  5006.3  224.02  5024.4  231.56  5029.6  229.76
  5037.2  230.75    5058  233.61  5472.2  230.96  5969.3  231.18  6022.9  233.08
  6123.5  240.01  6221.9  246.12  6296.6  254.62  6376.6  258.23  6411.4  262.56
  6416.5  261.42  6451.3   264.4  6491.3  265.07  6640.8  276.38  6982.9  281.28
#Mann= 7 ,-1 , 0
  3865.2     .05       0  4929.5     .16       0  4992.9     .07       0
  4998.9     .16       0  5037.2     .05       0  6022.9     .12       0
  6123.5     .05       0
Bank Sta=4964.8,5058
XS Rating Curve= 0 ,0
Exp/Cntr=0.3,0.1

Type RM Length L Ch R = 1 ,21994   ,1040,1040,1040
BEGIN DESCRIPTION:
ALLCORN CREEK 1.0
END DESCRIPTION:
XS GIS Cut Line= 4
      3593369.68       10271261.      3593774.53     10271120.25
      3594633.59     10268462.38      3594508.58     10267962.34
#Sta/Elev= 30
  3546.7  260.65  3738.6   256.5  3930.5   244.8  4210.8  233.23  4446.8  232.03
  4478.3  230.07  4509.8   232.1  4829.7  229.77  4867.2  231.71  4972.2  232.71
  4989.8  225.63  4993.7  225.33  5000.8  224.52  5003.5  224.02  5006.8  224.52
  5021.9  232.84  5144.4  231.94  5443.4   231.1  5571.3  228.82  5800.9  231.44
  6075.7   229.9  6425.1  230.35  6527.6  235.79  6569.7  240.89  6601.2  241.92
  6681.2  248.85  7078.6  271.78  7181.6  280.47  7233.2  282.78    7284  281.47
#Mann= 5 ,-1 , 0
  3546.7     .05       0  4993.7     .16       0  5000.8     .07       0
  5006.8     .16       0  5144.4     .05       0
Bank Sta=4972.2,5021.9
XS Rating Curve= 0 ,0
Exp/Cntr=0.3,0.1

Type RM Length L Ch R = 1 ,20954   ,1308,1308,1308
XS GIS Cut Line= 4
     3594300.937    10271548.992     3594953.715    10270090.659
     3594939.826    10268583.714     3594627.326    10268028.159
#Sta/Elev= 30
       0  249.36  129.96  238.24  179.95  235.28  209.94  235.18  229.93  232.75
  239.93  234.82  249.93  235.13  389.89  234.51 1179.65   228.5  1369.6  229.53
 1489.56  231.97 1509.55  230.51 1529.55  224.62 1539.55  223.31 1549.54  223.99
 1579.53  230.73 1878.52     228  1908.4  228.86 1948.24  227.69 2087.67  229.22
 2187.27  227.76 2655.39  228.48 2695.23  227.44 3093.62  229.27 3183.37  233.59
 3293.22  241.56 3353.14  244.42 3522.92  262.04 3672.72   268.9 3742.62  273.74
#Mann= 3 , 0 , 0
       0      .1       0 1509.55     .05       0 1579.53      .1       0
Bank Sta=1509.55,1579.53
XS Rating Curve= 0 ,0
Exp/Cntr=0.3,0.1

Type RM Length L Ch R = 1 ,19646   ,0,0,0
XS GIS Cut Line= 4
     3594307.881    10271694.825      3595821.77    10270736.492
     3596120.381    10269569.825     3595106.492    10268028.214
#Sta/Elev= 30
       0  258.47  209.51  236.63   259.4  233.44  299.31  233.17  319.26  231.75
  339.21  233.38  508.82  230.85  698.38  231.26  858.01  228.14 1287.01  226.57
 1316.94  227.76 1406.74  227.13 1696.07  229.14 1716.02  223.22    1726  223.48
 1745.95  228.97 2085.28  227.01 2115.22  225.78 2145.16  226.81 2863.76  226.12
 2893.71   224.6 3043.39  226.07    3203  224.87  3242.9  223.08 3302.76   224.6
 3851.42   226.4 4499.85  226.72 4529.77   228.4 4629.53  237.91 4839.02  263.91
#Mann= 3 , 0 , 0
       0      .1       0 1696.07     .05       0 1745.95      .1       0
Bank Sta=1696.07,1745.95
XS Rating Curve= 0 ,0
Exp/Cntr=0.3,0.1

Chan Stop Cuts=-1
Use User Specified Reach Order=0
Composite Channel Slope=5