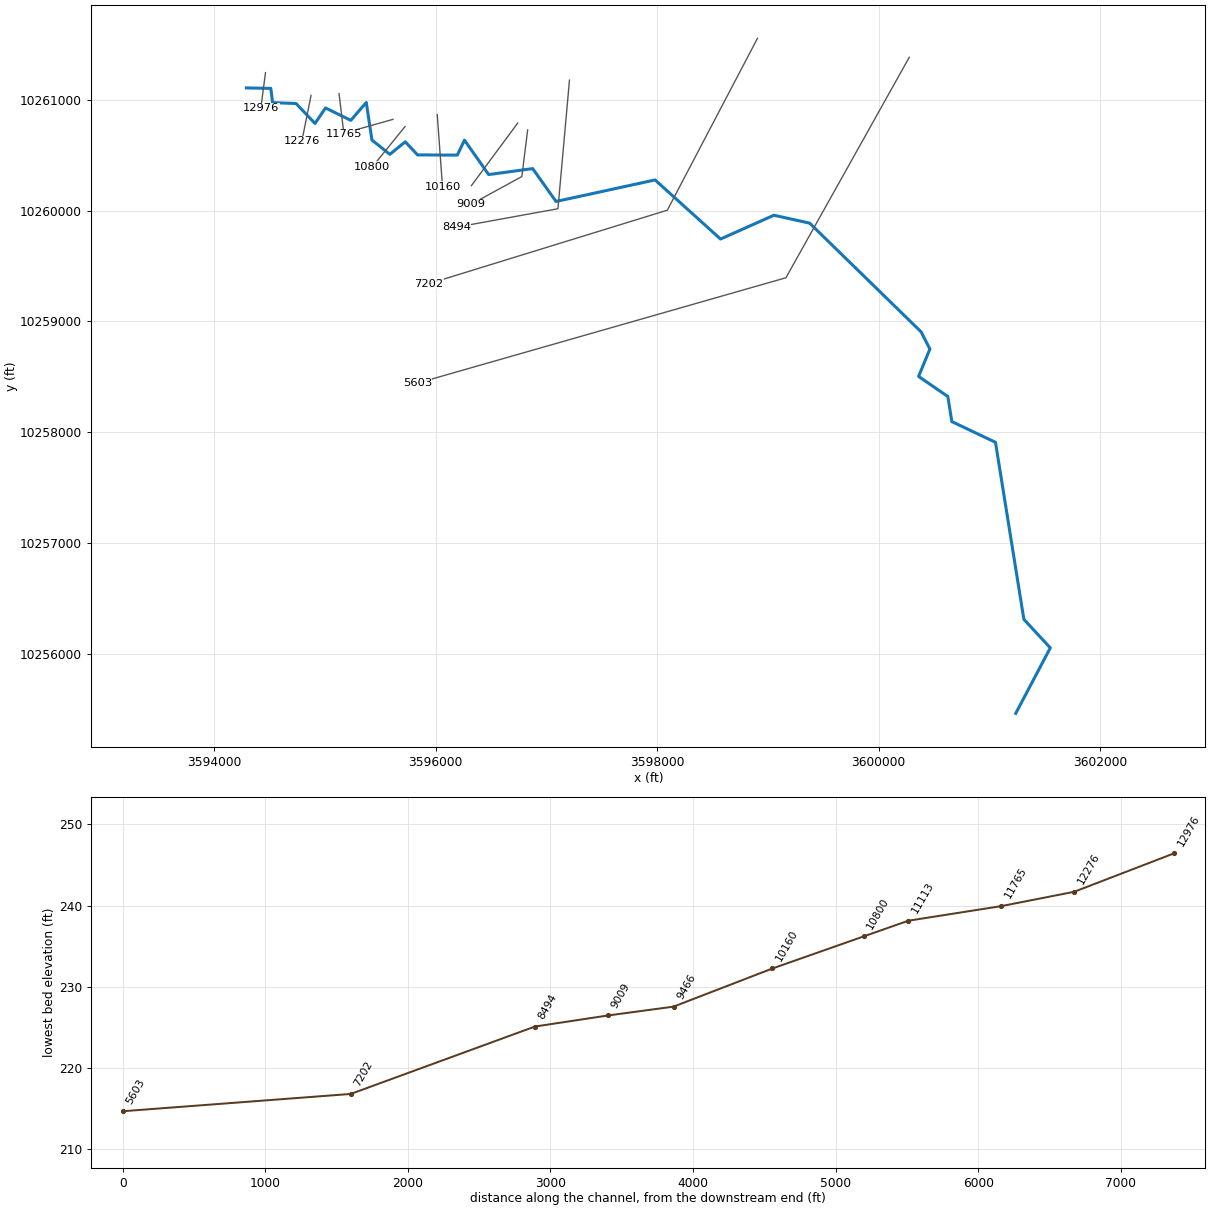
--- BOWMAN CREEK TRIB 1.prj (project) ---

Proj Title=BOWMAN CREEK TRIB 1 Base Level Engineering
Current Plan=p01
Default Exp/Contr=0.3,0.1
English Units
Geom File=g01
Flow File=f01
Plan File=p01
BEGIN DESCRIPTION:
BOWMAN CREEK TRIB 1
END DESCRIPTION:

--- BOWMAN CREEK TRIB 1.p01 (plan) ---

Plan Title=Multiple Run
Short Identifier=Multiple
Geom File=g01
Flow File=f01
Subcritical Flow
K Sum by GR= 0
Std Step Tol= 0.01
Critical Tol= 0.01
Num of Std Step Trials= 20
Max Error Tol= 0.3
Flow Tol Ratio= 0.001
Split Flow NTrial= 30
Split Flow Tol= 0.02
Split Flow Ratio= 0.02
Log Output Level= 0
Friction Slope Method= 1
Unsteady Friction Slope Method= 2
Unsteady Bridges Friction Slope Method= 1
Parabolic Critical Depth
Global Vel Dist=  1 , 1 , 1
Global Log Level= 0
CheckData=True
Encroach Param= -1, 0, 0, 0
BEGIN DESCRIPTION:
Multiple Run
END DESCRIPTION:

--- BOWMAN CREEK TRIB 1.f01 (steady flow) ---

Flow Title=Multiple
Number of Profiles=7
Profile Names=10-year,25-year,50-year,1pct_min,100-year,1pct_plu,500-year
River Rch & RM= BOWMAN CREEK TRI,Reach-1,12976
     881    1202    1466    1308    1769    2392    2581
Boundary for River Rch & Prof#=BOWMAN CREEK TRI,Reach-1,1
Up Type=0
Dn Type=3
Dn Slope=0.005
Boundary for River Rch & Prof#=BOWMAN CREEK TRI,Reach-1,2
Up Type=0
Dn Type=3
Dn Slope=0.005
Boundary for River Rch & Prof#=BOWMAN CREEK TRI,Reach-1,3
Up Type=0
Dn Type=3
Dn Slope=0.005
Boundary for River Rch & Prof#=BOWMAN CREEK TRI,Reach-1,4
Up Type=0
Dn Type=3
Dn Slope=0.005
Boundary for River Rch & Prof#=BOWMAN CREEK TRI,Reach-1,5
Up Type=0
Dn Type=3
Dn Slope=0.005
Boundary for River Rch & Prof#=BOWMAN CREEK TRI,Reach-1,6
Up Type=0
Dn Type=3
Dn Slope=0.005
Boundary for River Rch & Prof#=BOWMAN CREEK TRI,Reach-1,7
Up Type=0
Dn Type=3
Dn Slope=0.005

--- BOWMAN CREEK TRIB 1.g01 (geometry) ---

Geom Title=Existing Conditions

River Reach=BOWMAN CREEK TRI,Reach-1
Reach XY= 30
      3594293.11     10261108.84      3594513.75     10261104.75
      3594529.01     10260976.16      3594741.47     10260968.11
      3594912.31     10260787.75      3595007.10     10260928.15
      3595235.25     10260816.04      3595375.02     10260977.52
      3595426.07     10260638.56      3595587.46     10260508.93
      3595726.99     10260622.26      3595838.02     10260503.72
      3596196.87     10260502.34      3596261.42     10260637.22
      3596479.45     10260326.44      3596877.13     10260380.26
      3597087.76     10260083.32      3597981.58     10260277.88
      3598572.60     10259744.08      3599053.99     10259958.98
      3599376.88     10259887.56      3600382.97     10258905.70
      3600462.18     10258750.54      3600360.18     10258503.14
      3600624.28     10258321.83      3600660.20     10258095.33
      3601054.20     10257908.21      3601310.53     10256309.51
      3601549.07     10256051.70      3601237.19     10255459.98

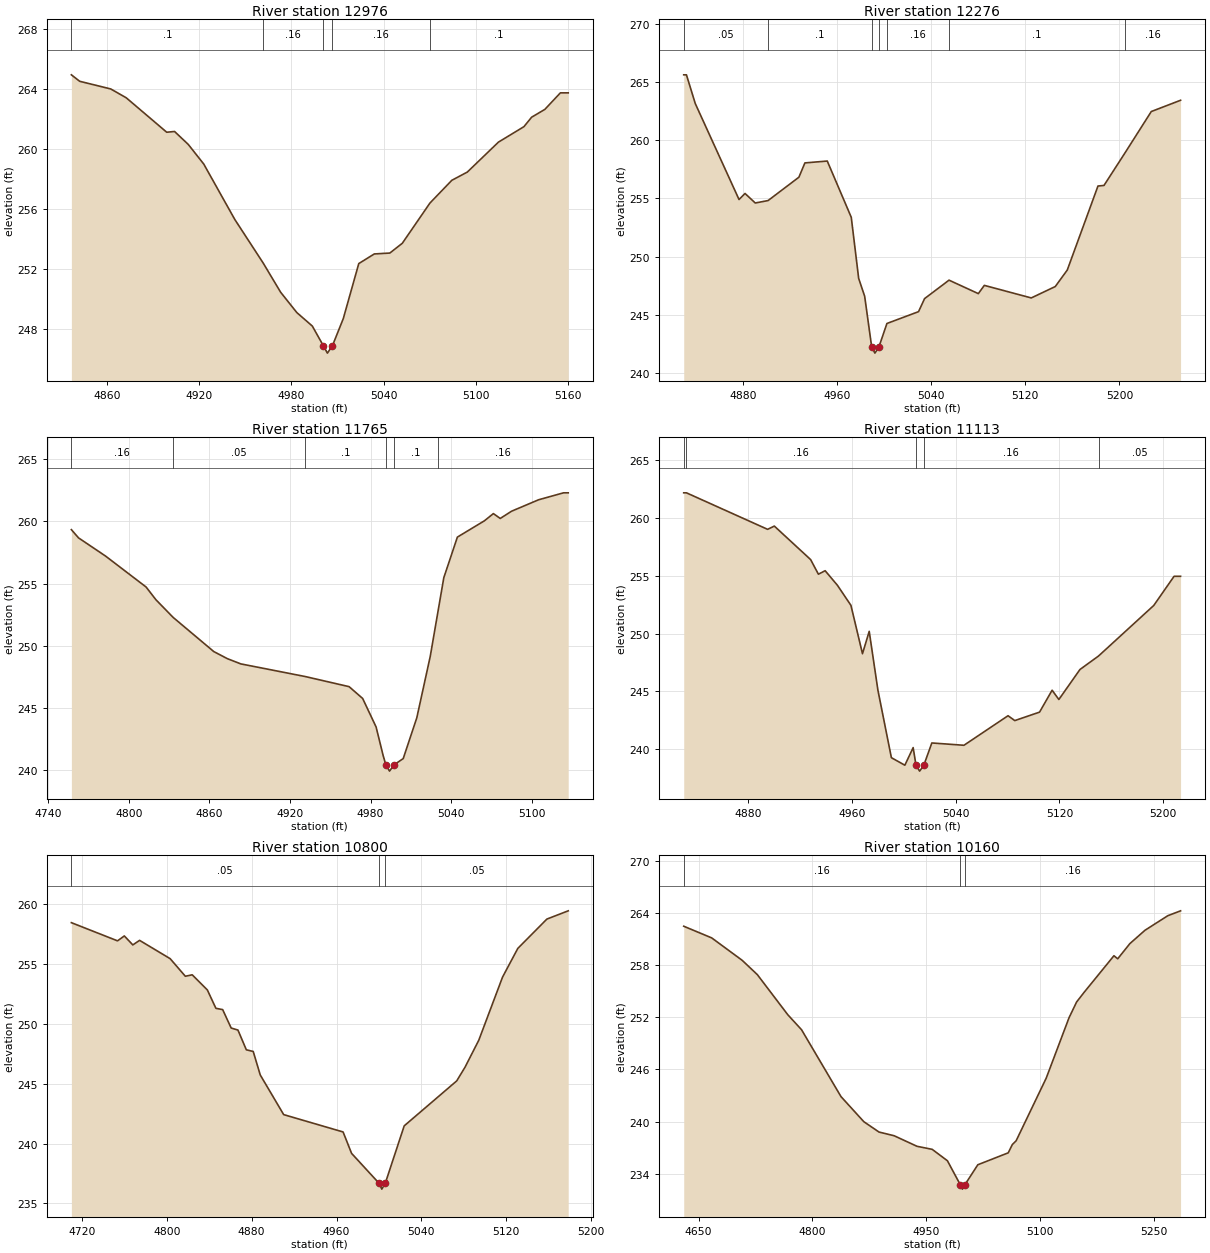
Type RM Length L Ch R = 1,12976,700,700,700
BEGIN DESCRIPTION:
BOWMAN CREEK TRIB 1 15.0
END DESCRIPTION:
XS GIS Cut Line= 2
      3594465.25     10261247.01      3594423.57     10260926.61
#Sta/Elev= 30
  4836.9  264.94  4842.3  264.51  4862.5  264.00  4872.6  263.41  4898.9  261.12
  4904.0  261.17  4912.9  260.31  4923.0  259.00  4943.2  255.31  4961.6  252.42
  4973.0  250.47  4983.5  249.12  4993.6  248.22  5000.7  246.92  5003.4  246.42
  5006.7  246.92  5013.7  248.71  5023.8  252.38  5033.9  253.02  5044.0  253.08
  5052.1  253.73  5070.1  256.41  5084.3  257.92  5094.4  258.47  5114.6  260.46
  5131.2  261.49  5136.2  262.12  5144.8  262.64  5154.9  263.74  5160.0  263.74
#Mann=5,-1,0
  4836.9     0.1       0  4961.6    0.16       0  5000.7    0.07       0
  5006.7    0.16       0  5070.1     0.1       0
Bank Sta=5000.7,5006.7
Exp/Cntr=0.3,0.1

Type RM Length L Ch R = 1,12276,511,511,511
BEGIN DESCRIPTION:
BOWMAN CREEK TRIB 1 14.0
END DESCRIPTION:
XS GIS Cut Line= 2
      3594876.69     10261041.20      3594793.37     10260627.20
#Sta/Elev= 30
  4829.7  265.64  4832.0  265.64  4839.5  263.17  4876.7  254.91  4881.8  255.43
  4890.5  254.61  4901.4  254.82  4927.6  256.83  4932.7  258.06  4951.7  258.22
  4972.1  253.38  4978.4  248.12  4983.5  246.58  4989.5  242.19  4992.2  241.69
  4995.5  242.19  5002.4  244.24  5029.3  245.26  5034.4  246.38  5055.2  247.97
  5080.1  246.81  5085.2  247.52  5125.1  246.44  5145.5  247.42  5155.7  248.84
  5181.8  256.07  5186.9  256.12  5204.5  258.88  5227.1  262.48  5252.0  263.45
#Mann=7,-1,0
  4829.7    0.05       0  4901.4     0.1       0  4989.5    0.07       0
  4995.5     0.1       0  5002.4    0.16       0  5055.2     0.1       0
  5204.5    0.16       0
Bank Sta=4989.5,4995.5
Exp/Cntr=0.3,0.1

Type RM Length L Ch R = 1,11765,652,652,652
BEGIN DESCRIPTION:
BOWMAN CREEK TRIB 1 13.0
END DESCRIPTION:
XS GIS Cut Line= 2
      3595129.31     10261056.86      3595173.57     10260689.72
#Sta/Elev= 30
  4757.3  259.34  4762.6  258.68  4782.7  257.22  4812.9  254.73  4820.2  253.71
  4833.0  252.29  4863.3  249.54  4873.4  248.97  4883.4  248.55  4931.5  247.53
  4964.0  246.72  4974.1  245.77  4984.1  243.48  4989.4  241.16  4991.4  240.43
  4994.1  239.93  4997.4  240.43  5004.3  240.94  5014.4  244.22  5024.4  249.15
  5030.0  252.66  5034.5  255.48  5044.6  258.74  5064.7  260.05  5071.4  260.63
  5076.5  260.24  5084.9  260.82  5105.0  261.74  5123.6  262.30  5127.1  262.30
#Mann=6,-1,0
  4757.3    0.16       0  4833.0    0.05       0  4931.5     0.1       0
  4991.4    0.07       0  4997.4     0.1       0  5030.0    0.16       0
Bank Sta=4991.4,4997.4
Exp/Cntr=0.3,0.1

Type RM Length L Ch R = 1,11113,313,313,313
BEGIN DESCRIPTION:
BOWMAN CREEK TRIB 1 12.0
END DESCRIPTION:
XS GIS Cut Line= 2
      3595616.28     10260825.09      3595247.40     10260720.93
#Sta/Elev= 30
  4830.2  262.14  4832.3  262.14  4894.9  258.99  4900.1  259.27  4928.1  256.38
  4934.1  255.12  4939.3  255.42  4948.8  254.16  4959.2  252.43  4968.1  248.26
  4973.3  250.19  4980.0  245.12  4990.4  239.29  5000.8  238.64  5007.2  240.16
  5009.4  238.63  5012.2  238.13  5015.4  238.63  5021.6  240.56  5046.4  240.36
  5080.4  242.91  5085.6  242.49  5104.7  243.22  5114.4  245.11  5119.6  244.31
  5135.9  246.90  5150.2  248.06  5192.8  252.42  5208.5  254.94  5213.5  254.94
#Mann=5,-1,0
  4830.2    0.05       0  4832.3    0.16       0  5009.4    0.07       0
  5015.4    0.16       0  5150.2    0.05       0
Bank Sta=5009.4,5015.4
Exp/Cntr=0.3,0.1

Type RM Length L Ch R = 1,10800,640,640,640
BEGIN DESCRIPTION:
BOWMAN CREEK TRIB 1 11.0
END DESCRIPTION:
XS GIS Cut Line= 2
      3595724.81     10260760.01      3595430.16     10260396.02
#Sta/Elev= 30
  4710.1  258.48  4753.6  256.96  4760.0  257.37  4768.0  256.62  4774.4  257.00
  4803.2  255.47  4817.5  254.00  4824.0  254.12  4838.3  252.85  4846.3  251.32
  4852.7  251.21  4860.7  249.67  4867.1  249.50  4875.0  247.85  4881.5  247.71
  4888.1  245.75  4910.2  242.43  4966.2  240.98  4974.2  239.19  5000.0  236.70
  5002.7  236.20  5006.0  236.70  5023.8  241.49  5073.3  245.25  5081.1  246.39
  5094.1  248.65  5116.5  253.93  5130.9  256.33  5158.3  258.78  5178.4  259.47
#Mann=3,-1,0
  4710.1    0.05       0  5000.0    0.03       0  5006.0    0.05       0
Bank Sta=5000,5006
Exp/Cntr=0.3,0.1

Type RM Length L Ch R = 1,10160,694,694,694
BEGIN DESCRIPTION:
BOWMAN CREEK TRIB 1 10.0
END DESCRIPTION:
XS GIS Cut Line= 2
      3596015.59     10260868.48      3596063.20     10260214.91
#Sta/Elev= 30
  4630.4  262.45  4667.3  261.11  4707.4  258.54  4727.5  256.89  4767.6  252.29
  4785.8  250.56  4837.8  242.88  4867.9  240.00  4887.9  238.81  4908.0  238.38
  4938.1  237.17  4958.1  236.82  4978.2  235.51  4995.2  232.75  4998.0  232.25
  5001.2  232.75  5018.3  235.05  5058.4  236.42  5063.8  237.37  5068.8  237.80
  5108.5  245.00  5138.6  251.94  5148.6  253.75  5158.6  254.87  5197.8  259.06
  5202.8  258.71  5218.8  260.45  5238.8  261.99  5268.9  263.66  5285.7  264.22
#Mann=3,-1,0
  4630.4    0.16       0  4995.2    0.07       0  5001.2    0.16       0
Bank Sta=4995.2,5001.2
Exp/Cntr=0.3,0.1

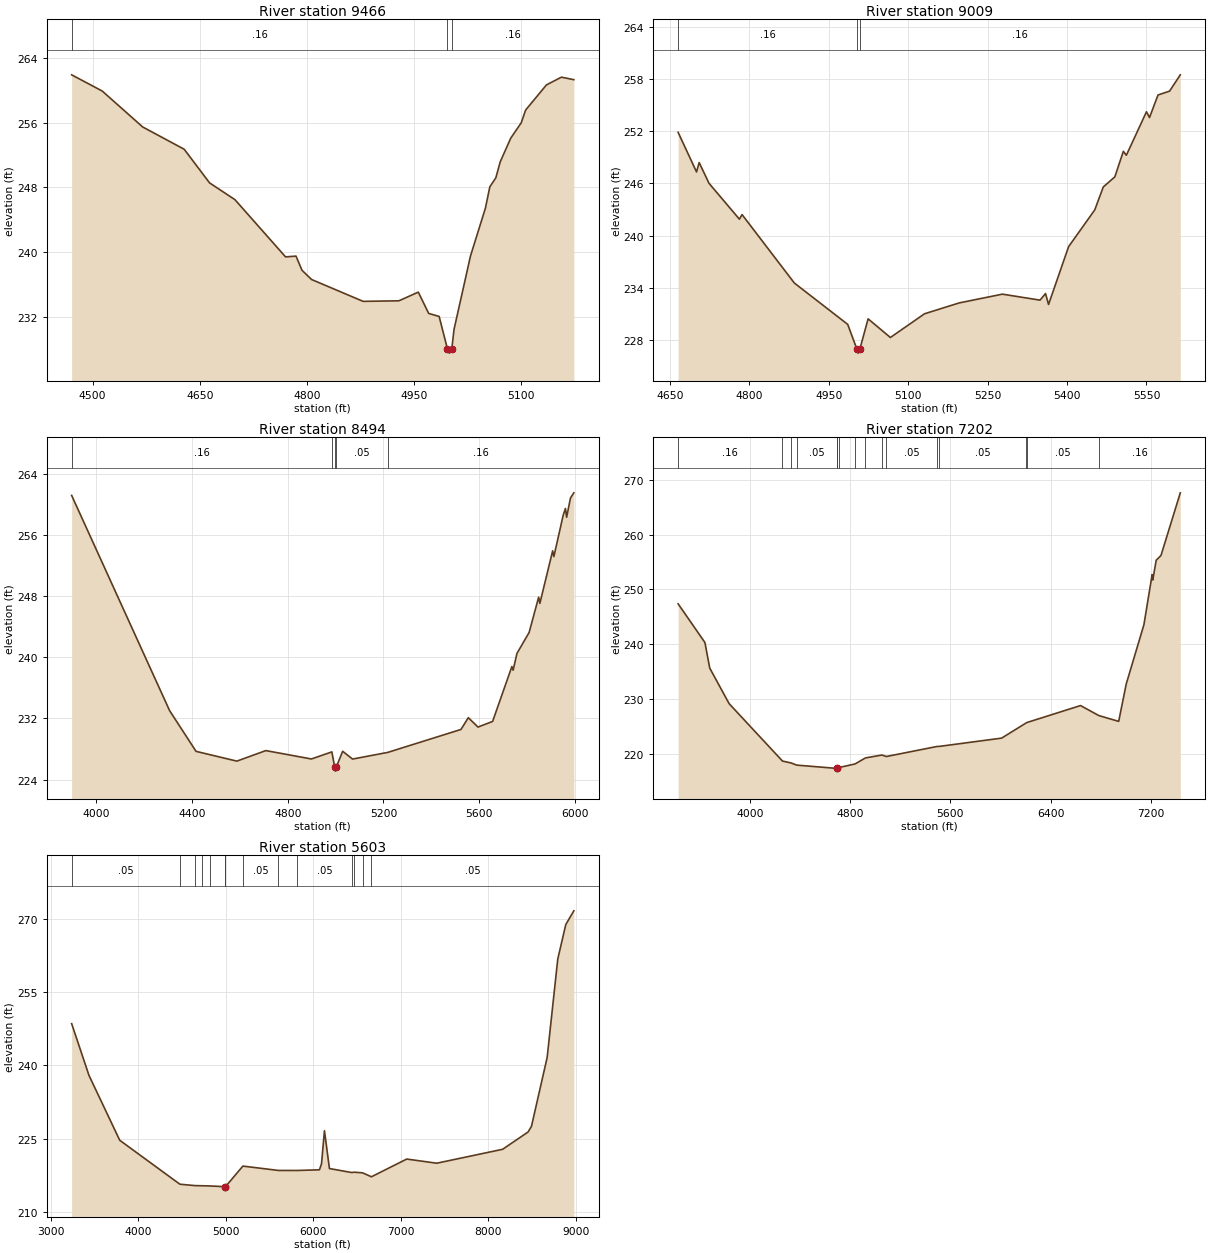
Type RM Length L Ch R = 1,9466,457,457,457
BEGIN DESCRIPTION:
BOWMAN CREEK TRIB 1 9.0
END DESCRIPTION:
XS GIS Cut Line= 2
      3596742.11     10260791.65      3596323.96     10260226.41
#Sta/Elev= 30
  4470.7  261.91  4513.5  259.91  4570.2  255.47  4628.3  252.72  4663.8  248.57
  4699.3  246.50  4770.2  239.43  4784.8  239.53  4793.2  237.78  4806.6  236.64
  4878.8  233.94  4928.9  234.01  4956.0  235.08  4970.6  232.45  4985.2  232.08
  4996.9  228.05  4999.6  227.55  5002.9  228.05  5006.1  230.49  5029.1  239.54
  5050.0  245.45  5056.2  248.08  5064.6  249.20  5070.8  251.18  5085.4  254.08
  5100.1  255.98  5106.3  257.56  5135.5  260.67  5156.4  261.62  5173.8  261.31
#Mann=3,-1,0
  4470.7    0.16       0  4996.9    0.07       0  5002.9    0.16       0
Bank Sta=4996.9,5002.9
Exp/Cntr=0.3,0.1

Type RM Length L Ch R = 1,9009,515,515,515
BEGIN DESCRIPTION:
BOWMAN CREEK TRIB 1 8.0
END DESCRIPTION:
XS GIS Cut Line= 3
      3596831.56     10260729.61      3596779.48     10260308.60
      3596319.38     10260056.84
#Sta/Elev= 30
  4665.2  251.89  4700.0  247.33  4705.0  248.41  4723.6  246.02  4781.0  241.89
  4786.0  242.42  4884.8  234.54  4985.6  229.78  5002.7  226.97  5005.5  226.47
  5008.7  226.97  5024.1  230.42  5066.2  228.27  5130.7  231.00  5196.2  232.25
  5277.8  233.26  5348.9  232.57  5359.3  233.33  5365.0  232.07  5402.9  238.73
  5452.3  242.96  5468.4  245.60  5490.2  246.76  5506.3  249.70  5512.0  249.25
  5550.0  254.26  5555.7  253.59  5571.8  256.19  5593.6  256.63  5613.9  258.51
#Mann=3,-1,0
  4665.2    0.16       0  5002.7    0.07       0  5008.7    0.16       0
Bank Sta=5002.7,5008.7
Exp/Cntr=0.3,0.1

Type RM Length L Ch R = 1,8494,1292,1292,1292
BEGIN DESCRIPTION:
BOWMAN CREEK TRIB 1 7.0
END DESCRIPTION:
XS GIS Cut Line= 3
      3597209.17     10261179.30      3597105.00     10260017.80
      3596188.30     10259851.12
#Sta/Elev= 30
  3897.4  261.21  4306.7  233.02  4417.1  227.69  4587.5  226.41  4708.7  227.79
  4899.1  226.69  4984.4  227.62  4996.5  225.60  4999.2  225.10  5002.5  225.60
  5029.6  227.70  5070.8  226.68  5217.7  227.55  5523.9  230.56  5554.4  232.10
  5595.0  230.87  5656.0  231.61  5736.5  238.80  5741.6  238.32  5757.7  240.52
  5808.5  243.26  5848.3  247.88  5853.4  247.07  5906.8  253.95  5911.9  253.20
  5950.8  258.61  5960.2  259.50  5965.2  258.35  5981.3  260.87  5995.3  261.55
#Mann=5,-1,0
  3897.4    0.16       0  4984.4    0.05       0  4996.5   0.035       0
  5002.5    0.05       0  5217.7    0.16       0
Bank Sta=4996.5,5002.5
Exp/Cntr=0.3,0.1

Type RM Length L Ch R = 1,7202,1599,1599,1599
BEGIN DESCRIPTION:
BOWMAN CREEK TRIB 1 6.0
END DESCRIPTION:
XS GIS Cut Line= 3
      3598905.93     10261556.77      3598092.37     10260004.58
      3595940.78     10259340.90
#Sta/Elev= 30
  3429.0  247.37  3642.8  240.30  3681.2  235.62  3835.7  229.13  4261.1  218.64
  4329.0  218.30  4374.4  217.90  4692.5  217.30  4695.3  216.80  4698.5  217.30
  4714.1  217.47  4839.5  218.11  4922.6  219.21  5053.8  219.74  5089.5  219.47
  5494.6  221.31  5512.5  221.32  6008.5  222.83  6205.2  225.62  6210.0  225.68
  6637.5  228.78  6783.6  226.95  6941.9  225.89  7002.0  232.72  7143.1  243.56
  7208.4  252.70  7213.6  251.72  7241.1  255.34  7279.0  256.20  7433.1  267.65
#Mann=16,-1,0
  3429.0    0.16       0  4261.1    0.05       0  4329.0    0.16       0
  4374.4    0.05       0  4692.5   0.035       0  4698.5    0.05       0
  4714.1    0.07       0  4839.5    0.16       0  4922.6    0.05       0
  5053.8    0.16       0  5089.5    0.05       0  5494.6    0.16       0
  5512.5    0.05       0  6205.2     0.1       0  6210.0    0.05       0
  6783.6    0.16       0
Bank Sta=4692.5,4698.5
Exp/Cntr=0.3,0.1

Type RM Length L Ch R = 1,5603,0,0,0
BEGIN DESCRIPTION:
BOWMAN CREEK TRIB 1 1.0
END DESCRIPTION:
XS GIS Cut Line= 3
      3600276.12     10261385.49      3599162.83     10259394.42
      3595835.38     10258442.19
#Sta/Elev= 30
  3238.1  248.58  3436.3  237.97  3788.0  224.68  4475.4  215.68  4647.9  215.39
  4729.0  215.36  4817.9  215.32  4991.0  215.17  4993.7  214.67  4997.0  215.17
  5196.0  219.39  5601.2  218.50  5814.7  218.49  6071.3  218.63  6095.0  219.84
  6128.8  226.64  6185.7  218.89  6443.7  218.06  6462.8  218.14  6564.4  218.01
  6665.9  217.20  7069.4  220.83  7413.1  219.98  8165.8  222.83  8456.8  226.37
  8495.8  227.53  8675.1  241.63  8796.5  261.80  8888.2  268.88  8980.3  271.69
#Mann=14,-1,0
  3238.1    0.05       0  4475.4    0.07       0  4647.9    0.12       0
  4729.0    0.07       0  4817.9    0.12       0  4991.0    0.07       0
  4997.0    0.12       0  5196.0    0.05       0  5601.2    0.07       0
  5814.7    0.05       0  6443.7    0.16       0  6462.8    0.05       0
  6564.4    0.16       0  6665.9    0.05       0
Bank Sta=4991,4997
Exp/Cntr=0.3,0.1

Chan Stop Cuts=-1