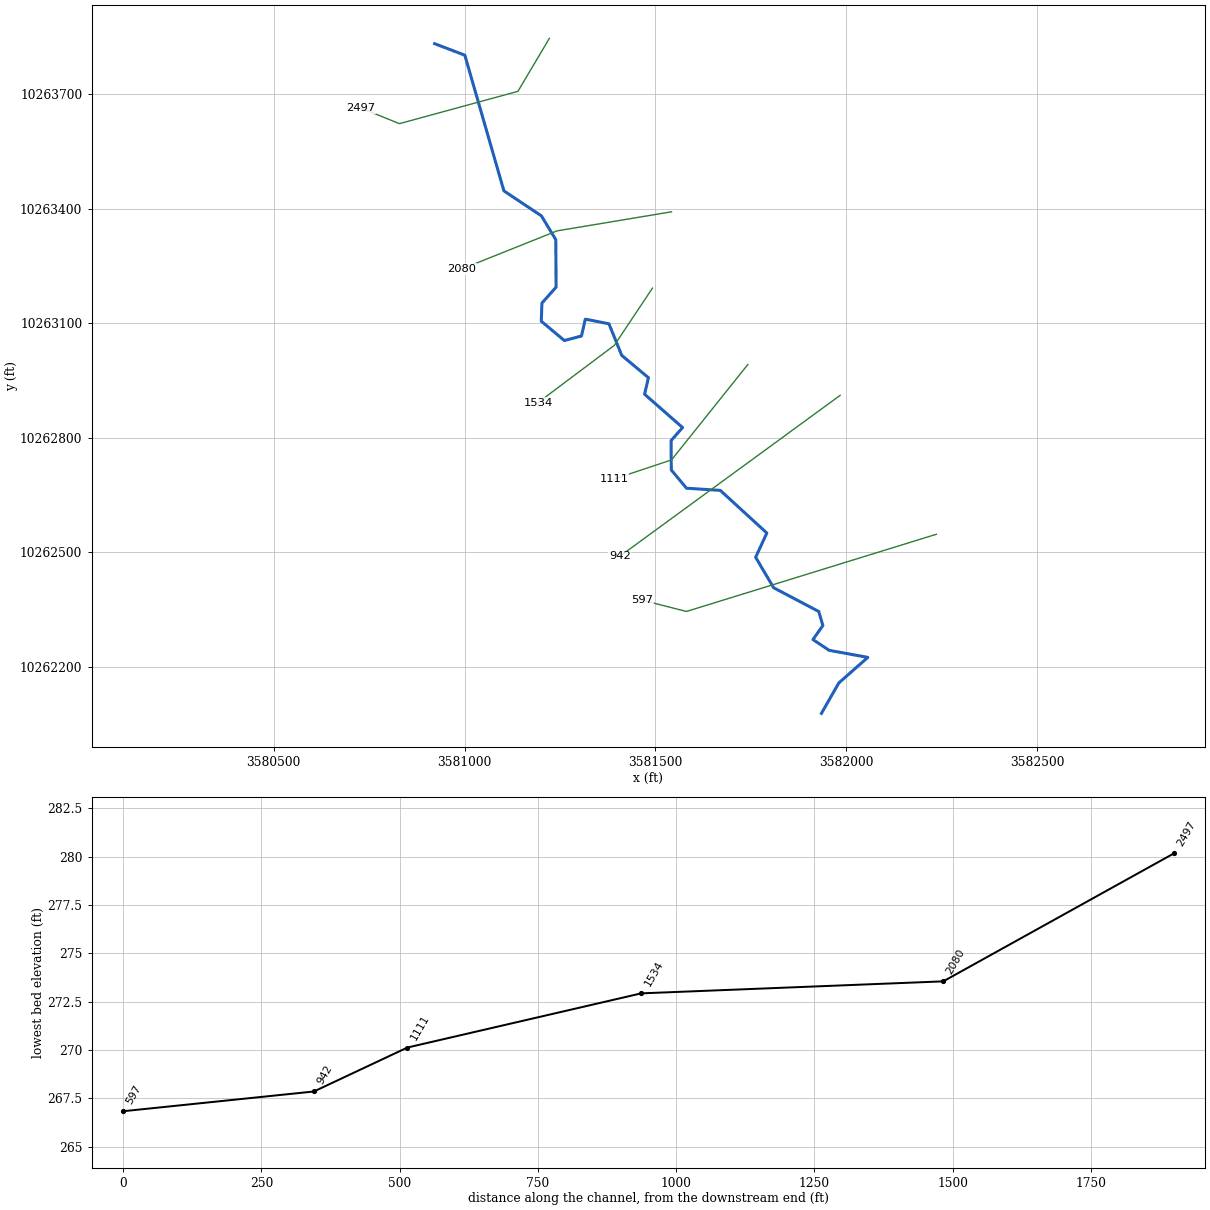
--- BOWMANCRTRIB11.prj (project) ---

Proj Title=BOWMAN CREEK TRIB 11
Current Plan=p01
Default Exp/Contr=0.3,0.1
English Units
Geom File=g01
Flow File=f01
Plan File=p01
Y Axis Title=Elevation
X Axis Title(PF)=Main Channel Distance
X Axis Title(XS)=Station
BEGIN DESCRIPTION:
UNT04962 IN WICK
END DESCRIPTION:
DSS Export Rating Curves= 0
DSS Export Rating Curve Sorted= 0
DSS Export Volume Flow Curves= 0
DXF OffsetX= 0
DXF OffsetY= 0
DXF ScaleX= 1
DXF ScaleY= 10

--- BOWMANCRTRIB11.p01 (plan) ---

Plan Title=Multiple Run
Short Identifier=Multiple
Geom File=g01
Flow File=f01
Subcritical Flow
K Sum by GR= 0
Std Step Tol= 0.01
Critical Tol= 0.01
Num of Std Step Trials= 20
Max Error Tol= 0.3
Flow Tol Ratio= 0.001
Split Flow NTrial= 30
Split Flow Tol= 0.02
Split Flow Ratio= 0.02
Log Output Level= 0
Friction Slope Method= 1
Unsteady Friction Slope Method= 2
Unsteady Bridges Friction Slope Method= 1
Parabolic Critical Depth
Global Vel Dist=  1 , 1 , 1
Global Log Level= 0
CheckData=True
Encroach Param= -1, 0, 0, 0
BEGIN DESCRIPTION:
Multiple Run
END DESCRIPTION:

--- BOWMANCRTRIB11.f01 (steady flow) ---

Flow Title=Multiple
Program Version=4.10
Number of Profiles= 7
Profile Names=10-year,25-year,50-year,1pct_min,100-year,1pct_plu,500-year
River Rch & RM=UNT04962 IN WICK,Reach-1         ,2497
     422     554     658     573     775    1049    1078
River Rch & RM=BOWMANCRTRIB11,Reach-1         ,2497
     422     554     658     573     775    1049    1078
Boundary for River Rch & Prof#=BOWMANCRTRIB11,Reach-1         , 1
Up Type= 0
Dn Type= 3
Dn Slope=0.005
Boundary for River Rch & Prof#=BOWMANCRTRIB11,Reach-1         , 2
Up Type= 0
Dn Type= 3
Dn Slope=0.005
Boundary for River Rch & Prof#=BOWMANCRTRIB11,Reach-1         , 3
Up Type= 0
Dn Type= 3
Dn Slope=0.005
Boundary for River Rch & Prof#=BOWMANCRTRIB11,Reach-1         , 4
Up Type= 0
Dn Type= 3
Dn Slope=0.005
Boundary for River Rch & Prof#=BOWMANCRTRIB11,Reach-1         , 5
Up Type= 0
Dn Type= 3
Dn Slope=0.005
Boundary for River Rch & Prof#=BOWMANCRTRIB11,Reach-1         , 6
Up Type= 0
Dn Type= 3
Dn Slope=0.005
Boundary for River Rch & Prof#=BOWMANCRTRIB11,Reach-1         , 7
Up Type= 0
Dn Type= 3
Dn Slope=0.005
DSS Import GetInterval= 0
DSS Import GetPeak= 0
DSS Import FillOption= 0

--- BOWMANCRTRIB11.g01 (geometry) ---

Geom Title=Existing Conditions
Program Version=4.10

River Reach=BOWMANCRTRIB11  ,Reach-1
Reach XY= 30
      3580921.59     10263832.07       3581000.6     10263801.96
      3581102.93     10263446.47      3581201.36     10263380.92
      3581238.86     10263318.77      3581239.71     10263194.19
       3581202.6     10263152.53      3581200.86       10263105.
      3581261.19     10263054.44      3581306.11     10263066.16
      3581316.31     10263110.43      3581378.16     10263098.27
      3581411.58     10263015.59      3581481.68       10262957.
      3581471.48     10262913.81      3581571.09     10262826.35
      3581541.14      10262792.5      3581541.36     10262715.46
      3581581.29      10262667.5      3581669.83     10262661.86
      3581791.79      10262550.1      3581762.49     10262486.51
      3581809.63     10262406.73      3581927.82     10262344.48
      3581938.61     10262307.82      3581912.67     10262271.02
      3581954.82     10262242.87      3582056.36     10262224.28
      3581980.39     10262157.34      3581934.84      10262077.6

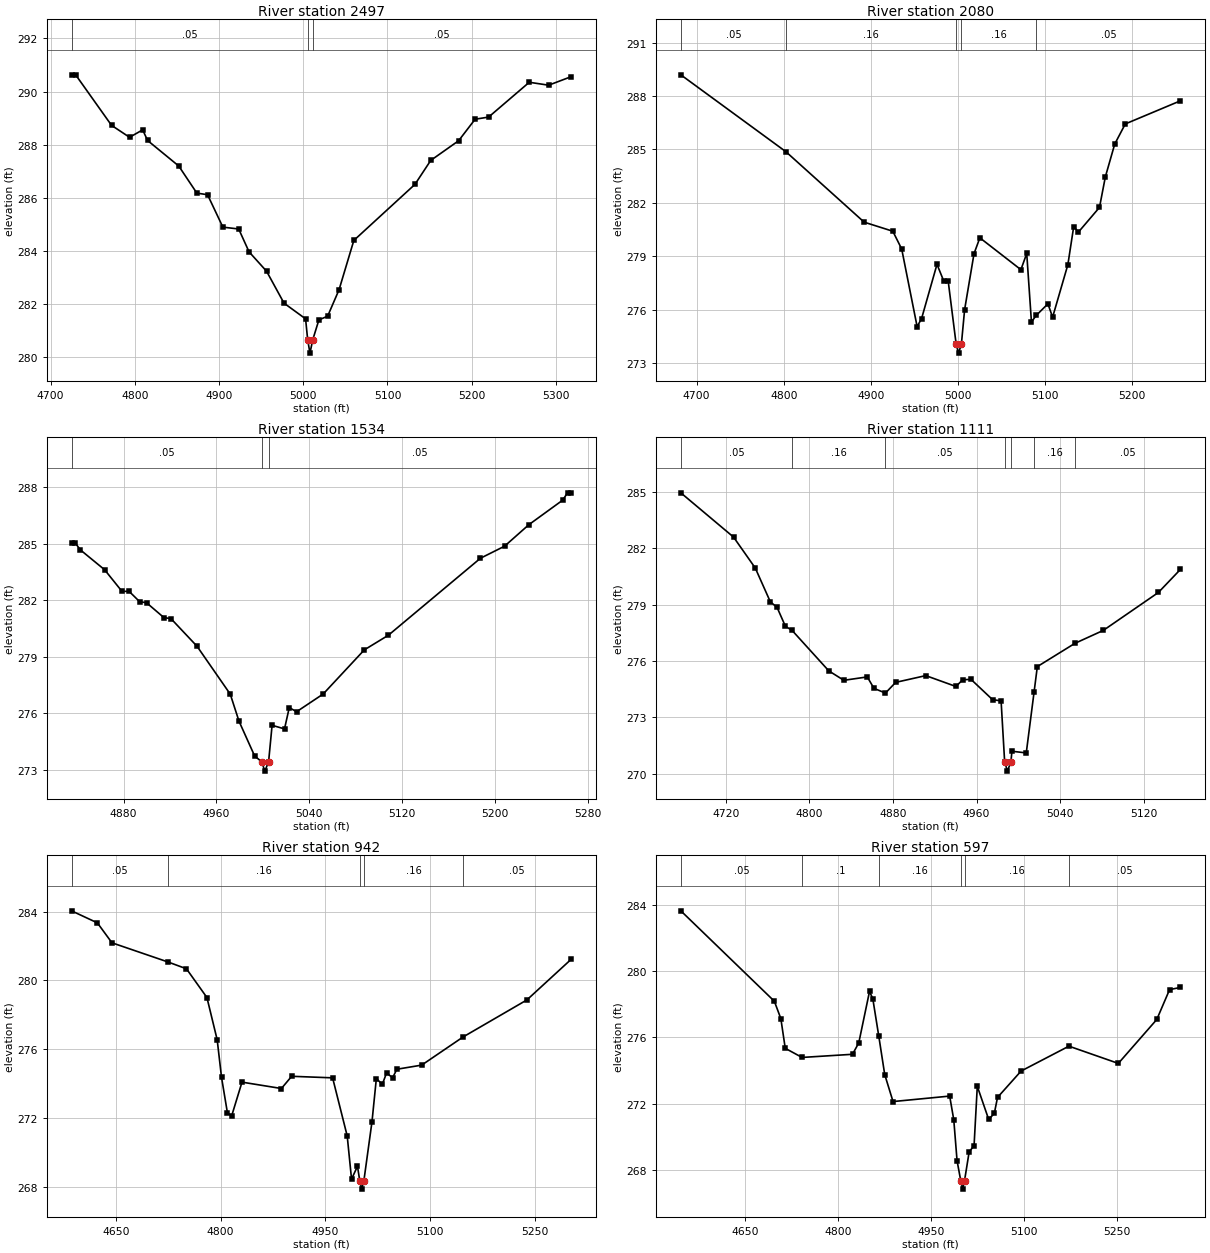
Type RM Length L Ch R = 1 ,2497    ,417,417,417
BEGIN DESCRIPTION:
UNT04962 IN WICK 5.0
END DESCRIPTION:
XS GIS Cut Line= 4
      3581222.13     10263846.11      3581139.65      10263707.2
      3580829.32     10263622.57      3580727.35     10263663.79
#Sta/Elev= 30
  4724.9  290.63  4729.8  290.63  4772.4  288.73  4793.8  288.28  4809.4  288.56
  4815.2  288.16  4852.2   287.2  4873.7  286.18  4886.4  286.12  4904.6   284.9
  4923.4  284.83  4935.7  283.97  4956.5  283.24  4977.2  282.04  5002.8  281.45
  5005.3  280.66    5008  280.16  5011.3  280.66  5018.6  281.41    5029  281.55
  5042.6  282.55  5060.1   284.4  5132.7  286.51  5151.4  287.41  5184.5  288.15
  5204.1  288.96  5220.1  289.04  5268.4  290.35  5291.4  290.24  5318.1  290.56
#Mann= 3 ,-1 , 0
  4724.9     .05       0  5005.3     .03       0  5011.3     .05       0
Bank Sta=5005.3,5011.3
XS Rating Curve= 0 ,0
Exp/Cntr=0.3,0.1

Type RM Length L Ch R = 1 ,2080    ,546,546,546
BEGIN DESCRIPTION:
UNT04962 IN WICK 4.0
END DESCRIPTION:
XS GIS Cut Line= 3
      3581542.12     10263391.64      3581242.11     10263341.64
      3580992.11     10263241.65
#Sta/Elev= 30
  4681.9  289.19  4802.5  284.87  4892.3  280.91  4925.2   280.4  4935.4   279.4
  4953.1  275.04  4958.2  275.49  4975.9  278.54  4983.5  277.62  4988.7  277.62
  4997.9  274.05  5000.6  273.55  5003.9  274.05  5007.6  275.99  5018.4  279.14
  5025.1  280.03  5072.2  278.24  5078.9  279.15  5084.3   275.3  5089.8  275.67
  5103.2  276.32  5108.6  275.57  5126.1  278.52  5132.8  280.66  5138.2  280.35
  5162.4  281.74  5169.1  283.45  5179.9   285.3    5192  286.43  5255.3  287.73
#Mann= 5 ,-1 , 0
  4681.9     .05       0  4802.5     .16       0  4997.9     .07       0
  5003.9     .16       0  5089.8     .05       0
Bank Sta=4997.9,5003.9
XS Rating Curve= 0 ,0
Exp/Cntr=0.3,0.1

Type RM Length L Ch R = 1 ,1534    ,423,423,423
BEGIN DESCRIPTION:
UNT04962 IN WICK 3.0
END DESCRIPTION:
XS GIS Cut Line= 3
      3581492.08     10263191.61      3581392.11     10263041.64
      3581192.14     10262891.67
#Sta/Elev= 30
  4835.2  285.05  4838.2  285.05  4842.7  284.67  4863.7  283.61  4878.7  282.46
  4884.7  282.47  4893.8  281.92  4899.8  281.86  4914.8  281.07  4920.8  281.02
  4943.3  279.55  4971.9  277.01  4979.4  275.58  4992.9  273.73  4998.9  273.43
  5001.7  272.93  5004.9  273.43  5007.9  275.36  5018.6  275.17  5022.7   276.3
    5029  276.08  5051.9  277.02  5087.3  279.36  5108.1  280.14  5187.3  284.22
  5208.1  284.86    5229     286  5258.1   287.3  5262.3  287.69  5265.4  287.69
#Mann= 3 ,-1 , 0
  4835.2     .05       0  4998.9     .03       0  5004.9     .05       0
Bank Sta=4998.9,5004.9
XS Rating Curve= 0 ,0
Exp/Cntr=0.3,0.1

Type RM Length L Ch R = 1 ,1111    ,169,169,169
BEGIN DESCRIPTION:
UNT04962 IN WICK 2.0
END DESCRIPTION:
XS GIS Cut Line= 3
      3581742.13     10262991.67      3581542.11     10262741.64
      3581392.11     10262691.64
#Sta/Elev= 30
  4676.9  284.96  4727.4   282.6  4748.2  280.95  4762.6  279.15    4769  278.86
    4777  277.85  4783.4  277.63  4818.6  275.47    4833  274.97  4855.4  275.15
  4861.8  274.54  4872.8  274.29  4882.6  274.86  4911.4  275.22  4940.3  274.64
  4946.7     275  4954.7  275.02  4975.5  273.93  4983.5  273.88  4986.9  270.63
  4989.6  270.13  4992.9  270.63  4993.9  271.19  5007.6   271.1  5015.1  274.35
  5018.2   275.7  5054.2  276.94  5081.4  277.63  5134.1  279.65  5155.2  280.88
#Mann= 7 ,-1 , 0
  4676.9     .05       0  4783.4     .16       0  4872.8     .05       0
  4986.9     .03       0  4992.9     .05       0  5015.1     .16       0
  5054.2     .05       0
Bank Sta=4986.9,4992.9
XS Rating Curve= 0 ,0
Exp/Cntr=0.3,0.1

Type RM Length L Ch R = 1 ,942     ,345,345,345
BEGIN DESCRIPTION:
Mapping XS 7fd8c737
END DESCRIPTION:
XS GIS Cut Line= 2
      3581983.86     10262910.78       3581406.4     10262488.99
#Sta/Elev= 30
  4586.7  284.04  4623.7  283.34  4644.6  282.18  4725.2  281.06  4751.2  280.67
  4780.5     279  4795.2  276.54  4801.4  274.36  4809.9  272.28    4816  272.13
  4830.7  274.08  4887.1  273.71  4901.8  274.42  4960.4  274.33  4981.3  270.95
  4987.5  268.44    4996  269.19  4999.2  268.36  5001.9  267.86  5005.2  268.36
  5016.8  271.79    5023  274.29  5031.5  273.95  5037.7  274.62  5046.2  274.33
  5052.4  274.83  5087.9  275.07  5147.3  276.71  5238.5  278.86  5301.8  281.22
#Mann= 5 ,-1 , 0
  4586.7     .05       0  4725.2     .16       0  4999.2     .07       0
  5005.2     .16       0  5147.3     .05       0
Bank Sta=4999.2,5005.2
XS Rating Curve= 0 ,0
Exp/Cntr=0.3,0.1

Type RM Length L Ch R = 1 ,597     ,0,0,0
BEGIN DESCRIPTION:
UNT04962 IN WICK 1.0
END DESCRIPTION:
XS GIS Cut Line= 3
       3582236.1     10262546.89      3581581.28     10262344.61
      3581465.16     10262374.26
#Sta/Elev= 30
  4546.7  283.62  4697.4  278.17  4707.9  277.12    4715  275.33  4742.1  274.78
  4823.4  274.97  4833.5  275.66  4850.8  278.76  4856.1  278.32  4865.8  276.05
  4875.3  273.75  4888.7  272.12    4980  272.45  4986.6  271.02  4991.9  268.55
  4997.9  267.34  5000.7  266.84  5003.9  267.34  5011.4  269.09  5019.3  269.46
  5024.5  273.04  5042.8  271.05  5051.9   271.4  5057.1  272.37  5095.1  273.96
  5172.2  275.46  5251.8  274.42  5313.8  277.07  5334.4  278.87  5351.9     279
#Mann= 6 ,-1 , 0
  4546.7     .05       0  4742.1      .1       0  4865.8     .16       0
  4997.9     .07       0  5003.9     .16       0  5172.2     .05       0
Bank Sta=4997.9,5003.9
XS Rating Curve= 0 ,0
Exp/Cntr=0.3,0.1

Chan Stop Cuts=-1
Use User Specified Reach Order=0
Composite Channel Slope=5