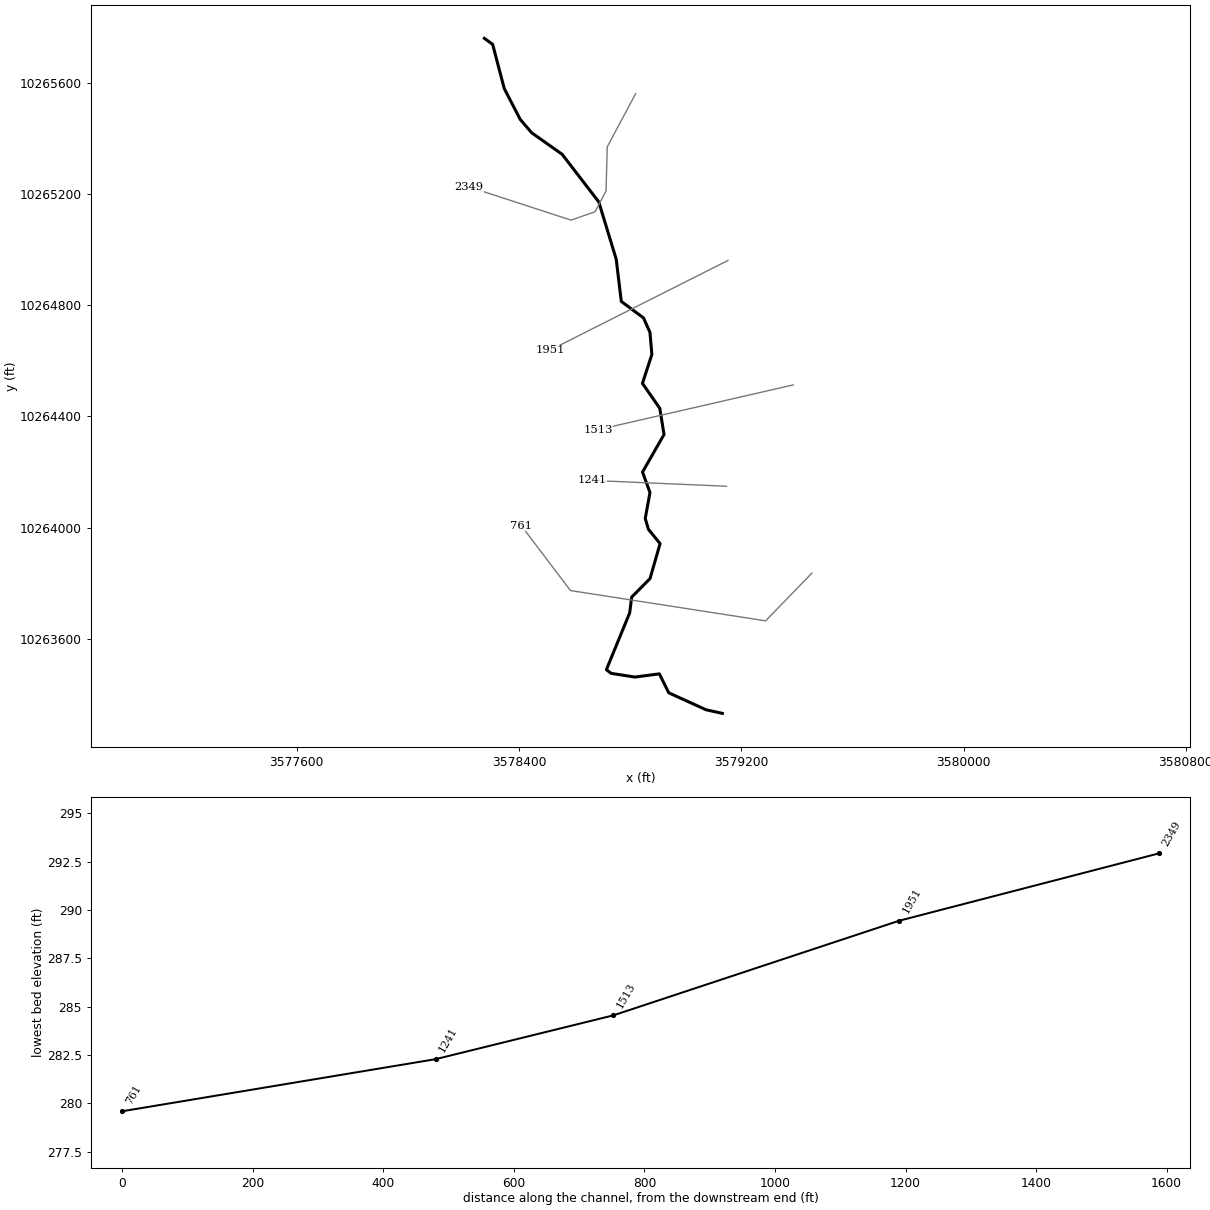
--- BOWMANCREEKTRIB1.prj (project) ---

Proj Title=BOWMAN CREEK TRIB 12
Current Plan=p01
Default Exp/Contr=0.3,0.1
English Units
Geom File=g01
Flow File=f01
Plan File=p01
Y Axis Title=Elevation
X Axis Title(PF)=Main Channel Distance
X Axis Title(XS)=Station
BEGIN DESCRIPTION:
UNT106 IN WICK
END DESCRIPTION:
DSS Export Rating Curves= 0
DSS Export Rating Curve Sorted= 0
DSS Export Volume Flow Curves= 0
DXF Filename=UNT106 IN WICK.
DXF OffsetX= 0
DXF OffsetY= 0
DXF ScaleX= 1
DXF ScaleY= 10

--- BOWMANCREEKTRIB1.p01 (plan) ---

Plan Title=Multiple Run
Short Identifier=Multiple
Geom File=g01
Flow File=f01
Subcritical Flow
K Sum by GR= 0
Std Step Tol= 0.01
Critical Tol= 0.01
Num of Std Step Trials= 20
Max Error Tol= 0.3
Flow Tol Ratio= 0.001
Split Flow NTrial= 30
Split Flow Tol= 0.02
Split Flow Ratio= 0.02
Log Output Level= 0
Friction Slope Method= 1
Unsteady Friction Slope Method= 2
Unsteady Bridges Friction Slope Method= 1
Parabolic Critical Depth
Global Vel Dist=  1 , 1 , 1
Global Log Level= 0
CheckData=True
Encroach Param= -1, 0, 0, 0
BEGIN DESCRIPTION:
Multiple Run
END DESCRIPTION:

--- BOWMANCREEKTRIB1.f01 (steady flow) ---

Flow Title=Multiple
Program Version=4.10
Number of Profiles= 7
Profile Names=10-year,25-year,50-year,1pct_min,100-year,1pct_plu,500-year
River Rch & RM=BOWMANCRTRIB12,Reach-1         ,2349
     168     208     238     200     271     366     351
Boundary for River Rch & Prof#=BOWMANCRTRIB12,Reach-1         , 1
Up Type= 0
Dn Type= 3
Dn Slope=0.005
Boundary for River Rch & Prof#=BOWMANCRTRIB12,Reach-1         , 2
Up Type= 0
Dn Type= 3
Dn Slope=0.005
Boundary for River Rch & Prof#=BOWMANCRTRIB12,Reach-1         , 3
Up Type= 0
Dn Type= 3
Dn Slope=0.005
Boundary for River Rch & Prof#=BOWMANCRTRIB12,Reach-1         , 4
Up Type= 0
Dn Type= 3
Dn Slope=0.005
Boundary for River Rch & Prof#=BOWMANCRTRIB12,Reach-1         , 5
Up Type= 0
Dn Type= 3
Dn Slope=0.005
Boundary for River Rch & Prof#=BOWMANCRTRIB12,Reach-1         , 6
Up Type= 0
Dn Type= 3
Dn Slope=0.005
Boundary for River Rch & Prof#=BOWMANCRTRIB12,Reach-1         , 7
Up Type= 0
Dn Type= 3
Dn Slope=0.005
DSS Import GetInterval= 0
DSS Import GetPeak= 0
DSS Import FillOption= 0

--- BOWMANCREEKTRIB1.g01 (geometry) ---

Geom Title=Existing Conditions
Program Version=4.10

River Reach=BOWMANCRTRIB12  ,Reach-1
Reach XY= 30
       3578275.8     10265760.73      3578305.49     10265739.17
      3578347.17     10265580.48      3578404.59     10265469.22
      3578445.79     10265421.07      3578555.48     10265343.55
      3578687.46     10265172.11       3578750.2     10264965.85
      3578768.45     10264814.04      3578848.45     10264754.64
      3578871.59     10264702.81       3578878.5     10264623.29
       3578844.6     10264519.12      3578907.02     10264429.44
      3578922.22     10264334.99      3578844.84     10264199.98
      3578871.62     10264126.36      3578854.65     10264032.67
      3578866.16     10263993.95      3578908.02     10263942.44
      3578871.87     10263816.67       3578805.9     10263750.12
      3578798.57     10263692.99      3578714.73     10263488.85
      3578732.14     10263475.68      3578817.38     10263462.29
      3578905.41     10263473.87      3578939.23     10263405.68
      3579073.36     10263344.66      3579132.11     10263331.64

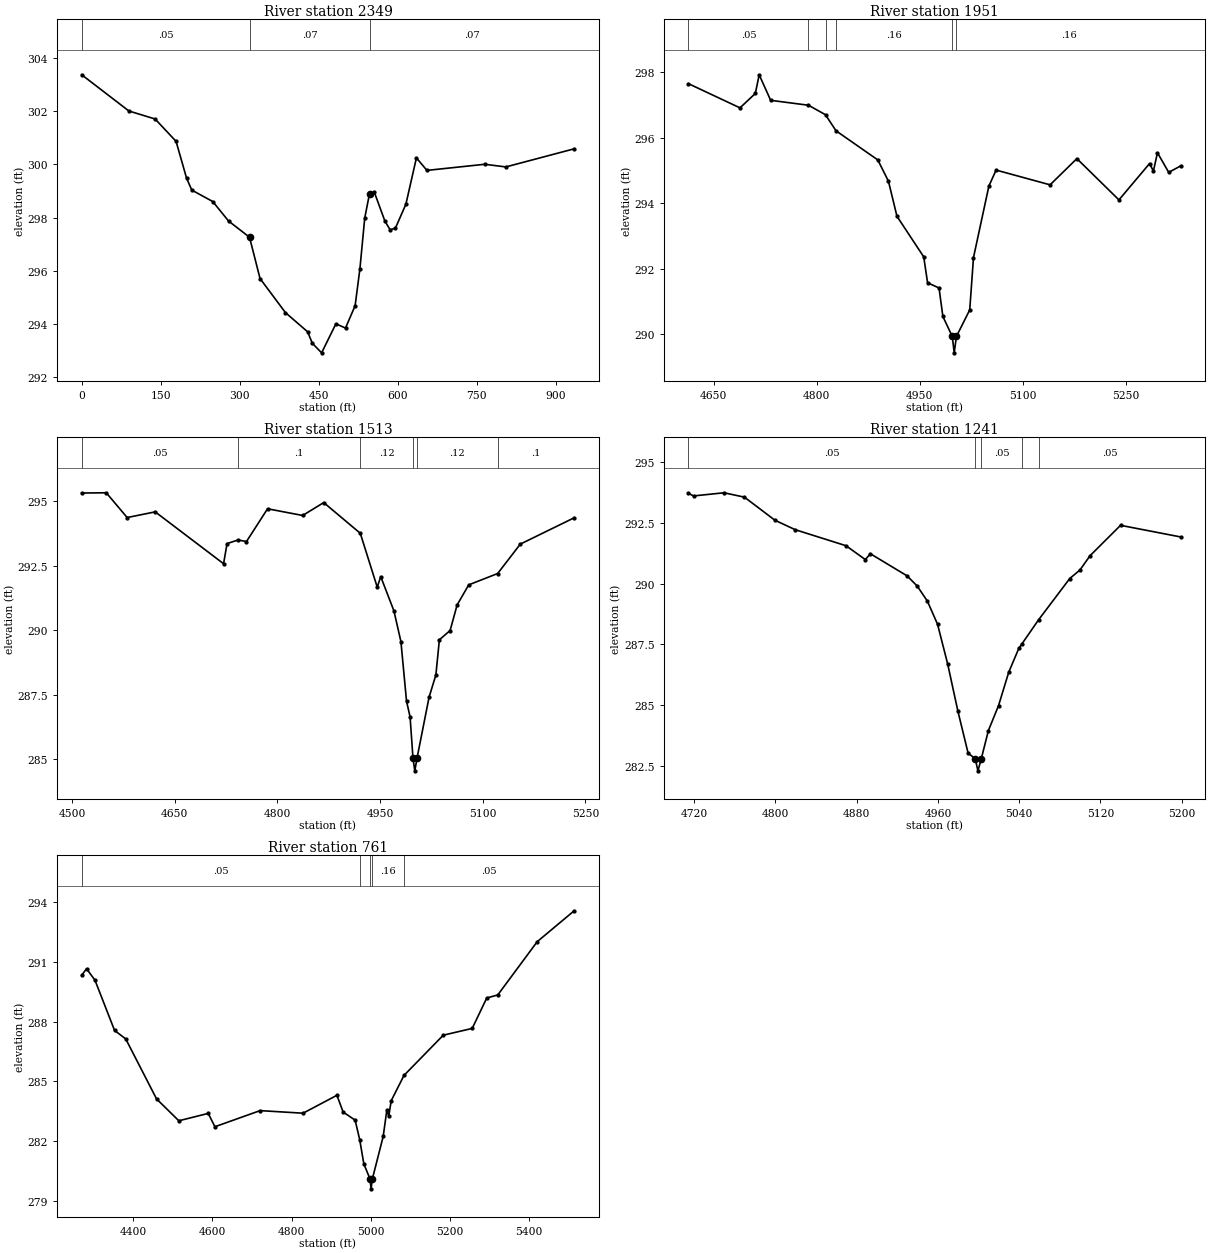
Type RM Length L Ch R = 1 ,2349    ,398,398,398
XS GIS Cut Line= 6
     3578819.901    10265561.189     3578717.904    10265370.216
     3578713.564    10265211.796     3578674.502    10265136.926
     3578587.696    10265106.545     3578220.943    10265225.902
#Sta/Elev= 30
       0  303.36   89.59     302  139.37   301.7  179.19  300.86   199.1  299.48
  209.05  299.03  248.92   298.6  278.83  297.87  318.71  297.26  338.65  295.71
  386.95  294.43  429.06  293.71  437.92  293.28  455.63  292.92  482.74  294.01
     501  293.85  519.25  294.69  528.38  296.08  537.51  297.98  546.64   298.9
  555.76  298.95  575.74  297.87  585.73  297.54  595.71   297.6  615.69   298.5
  635.66  300.24  655.64  299.77   765.5     300  805.45   299.9  935.29  300.58
#Mann= 3 ,-1 , 0
       0     .05       0  318.71     .07       0  546.64     .07       0
Bank Sta=318.71,546.64
XS Rating Curve= 0 ,0
Exp/Cntr=0.3,0.1

Type RM Length L Ch R = 1 ,1951    ,438,438,438
BEGIN DESCRIPTION:
UNT106 IN WICK 4.0
END DESCRIPTION:
XS GIS Cut Line= 2
      3579152.38     10264961.48      3578511.77     10264638.57
#Sta/Elev= 30
    4613  297.66  4688.2  296.92  4710.6  297.36  4716.2  297.93  4732.9  297.15
    4788     297  4812.8  296.71  4828.1  296.22    4889  295.33  4904.5  294.68
  4916.9  293.61  4955.9  292.37  4961.5  291.58  4978.2  291.42  4983.8  290.55
  4997.5  289.94  5000.3  289.44  5003.5  289.94  5022.9  290.75  5028.4  292.35
  5050.8  294.53  5061.3  295.02    5140  294.57    5179  295.37  5240.3  294.11
  5284.9  295.22  5290.5  294.99  5296.4  295.55  5312.8  294.95  5330.4  295.15
#Mann= 6 ,-1 , 0
    4613     .05       0    4788     .16       0  4812.8     .05       0
  4828.1     .16       0  4997.5     .07       0  5003.5     .16       0
Bank Sta=4997.5,5003.5
XS Rating Curve= 0 ,0
Exp/Cntr=0.3,0.1

Type RM Length L Ch R = 1 ,1513    ,272,272,272
BEGIN DESCRIPTION:
UNT106 IN WICK 3.0
END DESCRIPTION:
XS GIS Cut Line= 2
       3579386.8     10264513.58      3578685.36     10264352.51
#Sta/Elev= 30
  4513.9  295.32  4549.8  295.33  4580.3  294.37  4621.3  294.59  4721.2  292.58
  4726.3  293.36  4742.3   293.5  4754.7  293.44  4785.5  294.71  4836.8  294.45
  4867.6  294.95    4921  293.76  4945.8  291.67  4950.9  292.08  4970.2  290.75
  4980.4  289.56  4988.6  287.25  4993.8  286.64    4998  285.05  5000.7  284.55
    5004  285.05  5021.5   287.4  5031.5  288.27  5036.6  289.63  5052.3  289.99
  5062.5  290.98  5079.5  291.76  5121.8   292.2  5154.9  293.34  5233.6  294.36
#Mann= 6 ,-1 , 0
  4513.9     .05       0  4742.3      .1       0    4921     .12       0
    4998     .07       0    5004     .12       0  5121.8      .1       0
Bank Sta=4998,5004
XS Rating Curve= 0 ,0
Exp/Cntr=0.3,0.1

Type RM Length L Ch R = 1 ,1241    ,480,480,480
BEGIN DESCRIPTION:
UNT106 IN WICK 2.0
END DESCRIPTION:
XS GIS Cut Line= 2
      3579147.21     10264148.99      3578662.86     10264169.82
#Sta/Elev= 30
  4714.3  293.72  4719.4  293.61  4749.4  293.74  4769.5  293.56  4799.5  292.61
  4819.5  292.22  4869.5  291.56  4888.5  290.99  4893.5  291.23  4929.6  290.32
  4939.6   289.9  4949.6  289.28  4959.6  288.33  4969.6  286.69  4979.7  284.74
  4989.7  283.02  4996.7  282.79  4999.4  282.29  5002.7  282.79  5009.7  283.95
  5019.7  284.98  5029.7  286.35  5039.7  287.34  5042.4   287.5  5059.1  288.51
  5089.8  290.21  5099.8  290.56  5109.8  291.15  5139.8   292.4  5199.1  291.92
#Mann= 5 ,-1 , 0
  4714.3     .05       0  4996.7     .03       0  5002.7     .05       0
  5042.4     .16       0  5059.1     .05       0
Bank Sta=4996.7,5002.7
XS Rating Curve= 0 ,0
Exp/Cntr=0.3,0.1

Type RM Length L Ch R = 1 ,761     ,0,0,0
BEGIN DESCRIPTION:
UNT106 IN WICK 1.0
END DESCRIPTION:
XS GIS Cut Line= 4
       3579454.5      10263836.5      3579287.82     10263664.61
      3578585.65     10263773.57      3578408.26     10264007.51
#Sta/Elev= 30
  4270.2  290.33  4282.4  290.66  4303.7  290.08  4353.1  287.56  4381.4  287.13
  4459.1  284.12  4515.4  283.02  4589.7  283.39  4606.5  282.72  4720.7  283.53
  4829.1   283.4  4914.7   284.3  4930.3  283.46  4960.7  283.05  4972.2  282.07
  4982.7  280.85  4998.2   280.1  5000.9   279.6  5004.2   280.1  5031.5  282.23
  5040.6  283.54  5045.6  283.26  5051.8  284.03  5084.1   285.3  5183.3  287.32
  5256.3  287.66  5293.1  289.19  5320.8  289.34  5420.6  292.02  5513.8  293.57
#Mann= 5 ,-1 , 0
  4270.2     .05       0  4972.2     .16       0  4998.2     .07       0
  5004.2     .16       0  5084.1     .05       0
Bank Sta=4998.2,5004.2
XS Rating Curve= 0 ,0
Exp/Cntr=0.3,0.1

Chan Stop Cuts=-1
Use User Specified Reach Order=0
Composite Channel Slope=5