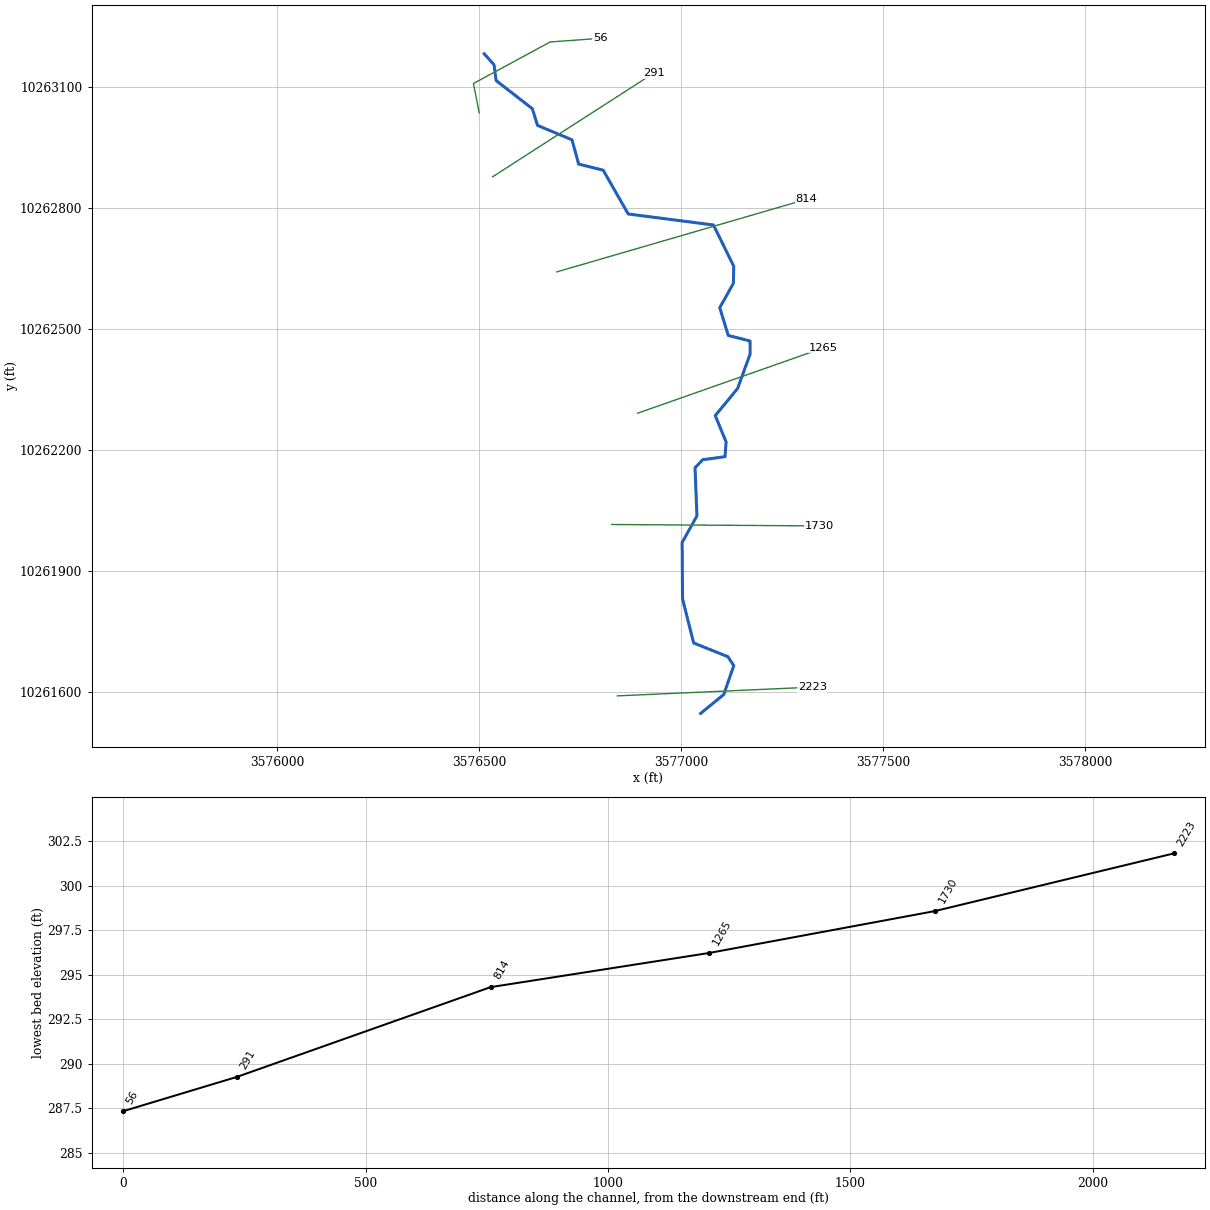
--- BOWMAN CREEK TRIB 13 1 1.prj (project) ---

Proj Title=BOWMAN CREEK TRIB 13 1 1 Base Level Engineering
Current Plan=p01
Default Exp/Contr=0.3,0.1
English Units
Geom File=g01
Flow File=f01
Plan File=p01
Y Axis Title=Elevation
X Axis Title(PF)=Main Channel Distance
X Axis Title(XS)=Station
BEGIN DESCRIPTION:
BOWMAN CREEK TRIB 13 1 1
END DESCRIPTION:
DSS Export Rating Curves= 0
DSS Export Rating Curve Sorted= 0
DSS Export Volume Flow Curves= 0
DXF OffsetX= 0
DXF OffsetY= 0
DXF ScaleX= 1
DXF ScaleY= 10

--- BOWMAN CREEK TRIB 13 1 1.p01 (plan) ---

Plan Title=Multiple Run
Short Identifier=Multiple
Geom File=g01
Flow File=f01
Subcritical Flow
K Sum by GR= 0
Std Step Tol= 0.01
Critical Tol= 0.01
Num of Std Step Trials= 20
Max Error Tol= 0.3
Flow Tol Ratio= 0.001
Split Flow NTrial= 30
Split Flow Tol= 0.02
Split Flow Ratio= 0.02
Log Output Level= 0
Friction Slope Method= 1
Unsteady Friction Slope Method= 2
Unsteady Bridges Friction Slope Method= 1
Parabolic Critical Depth
Global Vel Dist=  1 , 1 , 1
Global Log Level= 0
CheckData=True
Encroach Param= -1, 0, 0, 0
BEGIN DESCRIPTION:
Multiple Run
END DESCRIPTION:

--- BOWMAN CREEK TRIB 13 1 1.f01 (steady flow) ---

Flow Title=Multiple
Program Version=4.10
Number of Profiles= 7
Profile Names=10-year,25-year,50-year,1pct_min,100-year,1pct_plu,500-year
River Rch & RM=BOWMAN CREEK TRI,Reach-1         ,2223
     179     224     258     219     296     400     390
Boundary for River Rch & Prof#=BOWMAN CREEK TRI,Reach-1         , 1
Up Type= 0
Dn Type= 3
Dn Slope=0.008
Boundary for River Rch & Prof#=BOWMAN CREEK TRI,Reach-1         , 2
Up Type= 0
Dn Type= 3
Dn Slope=0.008
Boundary for River Rch & Prof#=BOWMAN CREEK TRI,Reach-1         , 3
Up Type= 0
Dn Type= 3
Dn Slope=0.008
Boundary for River Rch & Prof#=BOWMAN CREEK TRI,Reach-1         , 4
Up Type= 0
Dn Type= 3
Dn Slope=0.008
Boundary for River Rch & Prof#=BOWMAN CREEK TRI,Reach-1         , 5
Up Type= 0
Dn Type= 3
Dn Slope=0.008
Boundary for River Rch & Prof#=BOWMAN CREEK TRI,Reach-1         , 6
Up Type= 0
Dn Type= 3
Dn Slope=0.008
Boundary for River Rch & Prof#=BOWMAN CREEK TRI,Reach-1         , 7
Up Type= 0
Dn Type= 3
Dn Slope=0.008
DSS Import GetInterval= 0
DSS Import GetPeak= 0
DSS Import FillOption= 0

--- BOWMAN CREEK TRIB 13 1 1.g01 (geometry) ---

Geom Title=Existing Conditions

River Reach=BOWMAN CREEK TRI,Reach-1
Reach XY= 30
      3577048.15     10261548.27      3577105.25     10261594.93
      3577130.08     10261666.32      3577115.66     10261688.59
      3577030.74     10261722.57      3577003.18     10261832.04
      3577002.30     10261971.59      3577038.90     10262037.32
      3577034.18     10262156.41      3577053.09     10262176.46
      3577108.42     10262183.91      3577111.08     10262220.49
      3577084.26     10262285.71      3577139.52     10262352.72
      3577170.51     10262437.85      3577170.32     10262470.49
      3577116.46     10262484.20      3577095.38     10262552.86
      3577129.15     10262613.26      3577130.07     10262655.46
      3577079.85     10262757.72      3576868.74     10262785.00
      3576806.78     10262893.41      3576745.99     10262908.49
      3576729.44     10262968.73      3576644.05     10263004.34
      3576631.29     10263045.66      3576541.58     10263115.47
      3576536.42     10263154.53      3576512.11     10263181.64

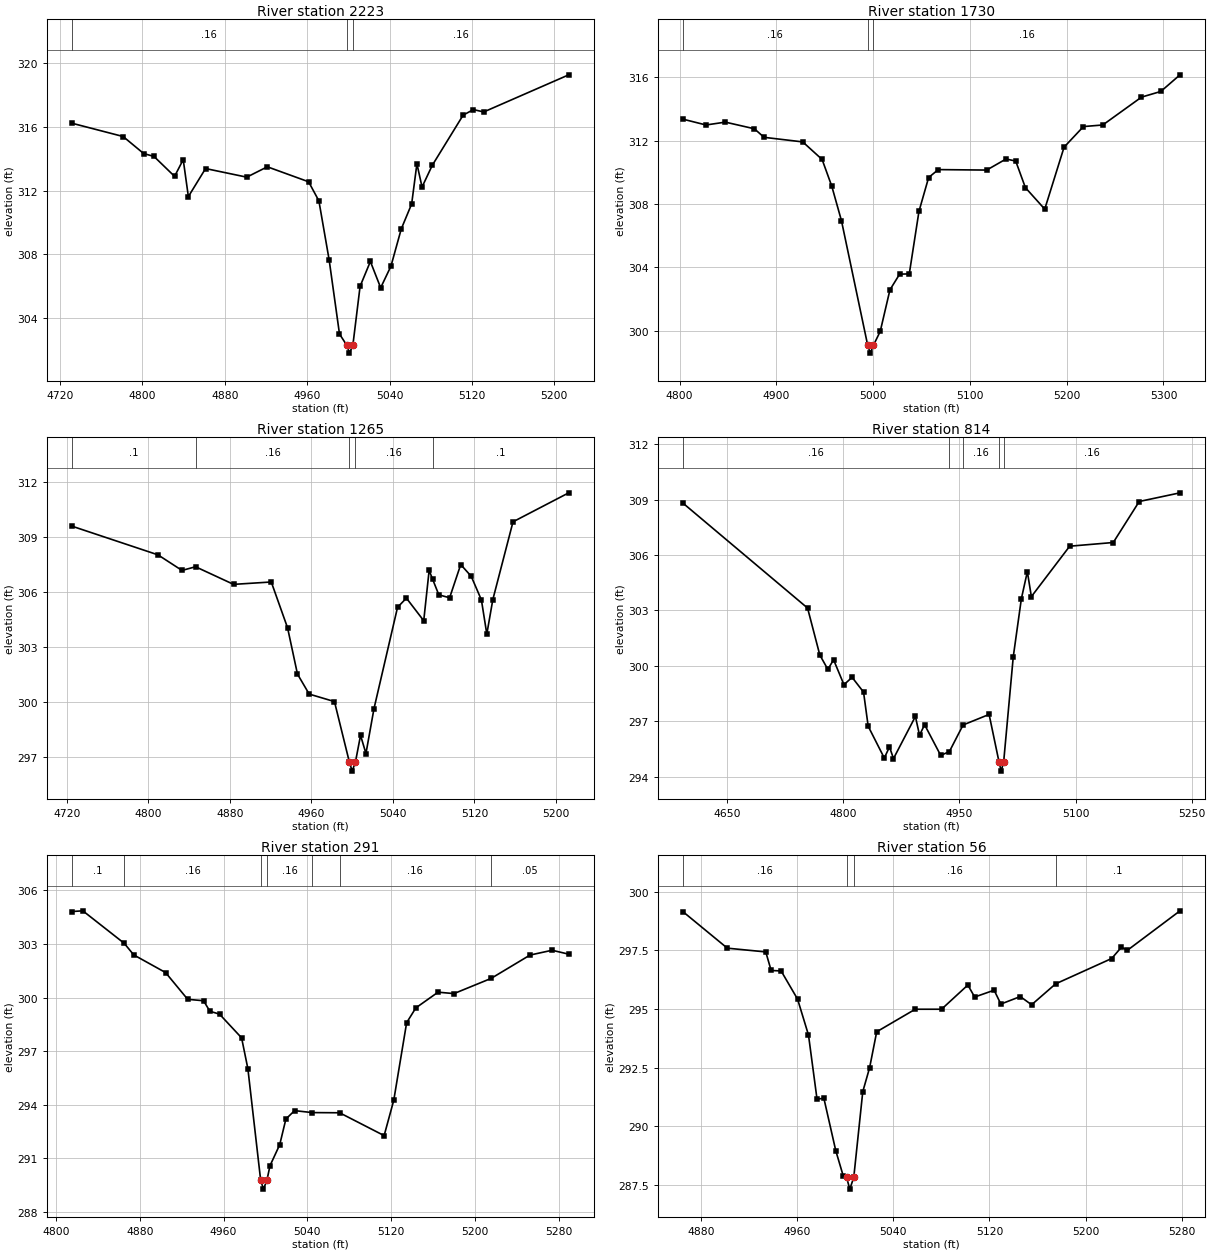
Type RM Length L Ch R = 1,2223,493,493,493
BEGIN DESCRIPTION:
UNT111 IN WICK 8.0
END DESCRIPTION:
XS GIS Cut Line= 2
      3576842.08     10261591.64      3577324.60     10261613.22
#Sta/Elev= 30
  4731.1  316.24  4781.2  315.40  4801.2  314.33  4811.2  314.15  4831.2  312.90
  4839.6  313.95  4844.6  311.63  4861.3  313.39  4901.3  312.85  4921.3  313.50
  4961.4  312.56  4971.4  311.36  4981.4  307.64  4991.4  303.01  4998.4  302.31
  5001.1  301.81  5004.4  302.31  5011.4  306.00  5021.4  307.56  5031.4  305.91
  5041.4  307.27  5051.4  309.60  5061.5  311.17  5066.6  313.69  5071.6  312.23
  5081.5  313.59  5111.5  316.74  5121.5  317.09  5131.5  316.94  5214.1  319.27
#Mann=3,-1,0
  4731.1    0.16       0  4998.4    0.07       0  5004.4    0.16       0
Bank Sta=4998.4,5004.4
Exp/Cntr=0.3,0.1

Type RM Length L Ch R = 1,1730,465,465,465
BEGIN DESCRIPTION:
UNT111 IN WICK 7.0
END DESCRIPTION:
XS GIS Cut Line= 2
      3576828.06     10262016.00      3577341.95     10262012.53
#Sta/Elev= 30
  4803.2  313.36  4827.2  312.99  4847.2  313.17  4877.2  312.75  4887.2  312.21
  4927.2  311.92  4947.2  310.81  4957.2  309.12  4967.2  306.94  4994.3  299.07
  4997.0  298.57  5000.3  299.07  5007.3  299.95  5017.3  302.57  5027.3  303.56
  5037.3  303.58  5047.3  307.53  5057.3  309.67  5067.3  310.17  5117.3  310.14
  5137.3  310.84  5147.3  310.71  5157.3  309.03  5177.3  307.67  5197.3  311.59
  5217.3  312.89  5237.3  312.99  5277.3  314.75  5297.3  315.11  5317.1  316.16
#Mann=3,-1,0
  4803.2    0.16       0  4994.3    0.07       0  5000.3    0.16       0
Bank Sta=4994.3,5000.3
Exp/Cntr=0.3,0.1

Type RM Length L Ch R = 1,1265,451,451,451
BEGIN DESCRIPTION:
UNT111 IN WICK 6.0
END DESCRIPTION:
XS GIS Cut Line= 2
      3576892.10     10262291.64      3577352.37     10262453.49
#Sta/Elev= 30
  4724.6  309.58  4809.4  308.01  4833.0  307.16  4846.3  307.36  4883.6  306.40
  4920.6  306.53  4936.6  304.03  4946.3  301.51  4957.8  300.42  4982.6  300.01
  4997.2  296.72  5000.0  296.22  5003.2  296.72  5008.2  298.17  5013.5  297.18
  5021.4  299.63  5044.5  305.15  5053.2  305.65  5070.2  304.42  5075.5  307.16
  5079.0  306.67  5085.0  305.83  5095.6  305.67  5106.5  307.48  5116.8  306.84
  5126.8  305.55  5132.1  303.69  5138.0  305.57  5157.8  309.81  5212.5  311.39
#Mann=5,-1,0
  4724.6     0.1       0  4846.3    0.16       0  4997.2    0.07       0
  5003.2    0.16       0  5079.0     0.1       0
Bank Sta=4997.2,5003.2
Exp/Cntr=0.3,0.1

Type RM Length L Ch R = 1,814,523,523,523
BEGIN DESCRIPTION:
UNT111 IN WICK 5.0
END DESCRIPTION:
XS GIS Cut Line= 2
      3576692.15     10262641.66      3577308.90     10262821.02
#Sta/Elev= 30
  4592.6  308.82  4753.8  303.13  4769.6  300.59  4780.0  299.81  4787.4  300.33
  4800.8  298.98  4811.3  299.38  4826.1  298.58  4832.1  296.73  4852.9  295.01
  4859.6  295.61  4864.8  294.98  4893.1  297.26  4898.4  296.25  4905.0  296.81
  4925.8  295.15  4937.0  295.36  4954.7  296.80  4988.3  297.37  5001.1  294.80
  5003.9  294.30  5007.1  294.80  5019.5  300.49  5030.0  303.64  5037.7  305.10
  5042.9  303.75  5092.4  306.48  5148.7  306.68  5182.2  308.90  5234.9  309.37
#Mann=5,-1,0
  4592.6    0.16       0  4937.0     0.1       0  4954.7    0.16       0
  5001.1    0.07       0  5007.1    0.16       0
Bank Sta=5001.1,5007.1
Exp/Cntr=0.3,0.1

Type RM Length L Ch R = 1,291,235,235,235
BEGIN DESCRIPTION:
UNT111 IN WICK 5.0.a
END DESCRIPTION:
XS GIS Cut Line= 2
      3576533.00     10262877.14      3576932.28     10263134.07
#Sta/Elev= 30
  4814.8  304.82  4825.6  304.86  4865.1  303.04  4874.2  302.39  4904.6  301.40
  4925.7  299.90  4940.9  299.82  4946.9  299.23  4956.1  299.07  4977.2  297.74
  4983.2  296.01  4995.4  289.76  4998.1  289.26  5001.4  289.76  5004.3  290.57
  5013.6  291.75  5019.5  293.19  5027.8  293.66  5044.7  293.55  5070.8  293.54
  5113.3  292.26  5122.5  294.24  5134.8  298.59  5143.6  299.42  5164.8  300.30
  5180.0  300.22  5215.4  301.07  5252.6  302.38  5273.7  302.65  5289.6  302.43
#Mann=7,-1,0
  4814.8     0.1       0  4865.1    0.16       0  4995.4    0.07       0
  5001.4    0.16       0  5044.7     0.1       0  5070.8    0.16       0
  5215.4    0.05       0
Bank Sta=4995.4,5001.4
Exp/Cntr=0.3,0.1

Type RM Length L Ch R = 1,56,0,0,0
BEGIN DESCRIPTION:
UNT111 IN WICK 4.0
END DESCRIPTION:
XS GIS Cut Line= 4
      3576499.71     10263035.20      3576485.39     10263108.11
      3576675.49     10263210.98      3576798.81     10263219.97
#Sta/Elev= 30
  4864.6  299.15  4901.7  297.59  4933.7  297.43  4938.2  296.64  4946.5  296.62
  4960.2  295.42  4969.3  293.89  4976.4  291.16  4982.1  291.20  4992.0  288.97
  4998.3  287.88  5001.0  287.83  5003.7  287.33  5007.0  287.83  5014.5  291.48
  5020.2  292.50  5026.1  294.03  5058.2  294.99  5080.1  294.99  5102.0  296.02
  5107.7  295.51  5123.9  295.80  5129.5  295.21  5145.7  295.53  5155.1  295.18
  5175.1  296.07  5221.8  297.15  5229.9  297.63  5234.9  297.50  5278.7  299.18
#Mann=4,-1,0
  4864.6    0.16       0  5001.0    0.07       0  5007.0    0.16       0
  5175.1     0.1       0
Bank Sta=5001,5007
Exp/Cntr=0.3,0.1

Chan Stop Cuts=-1