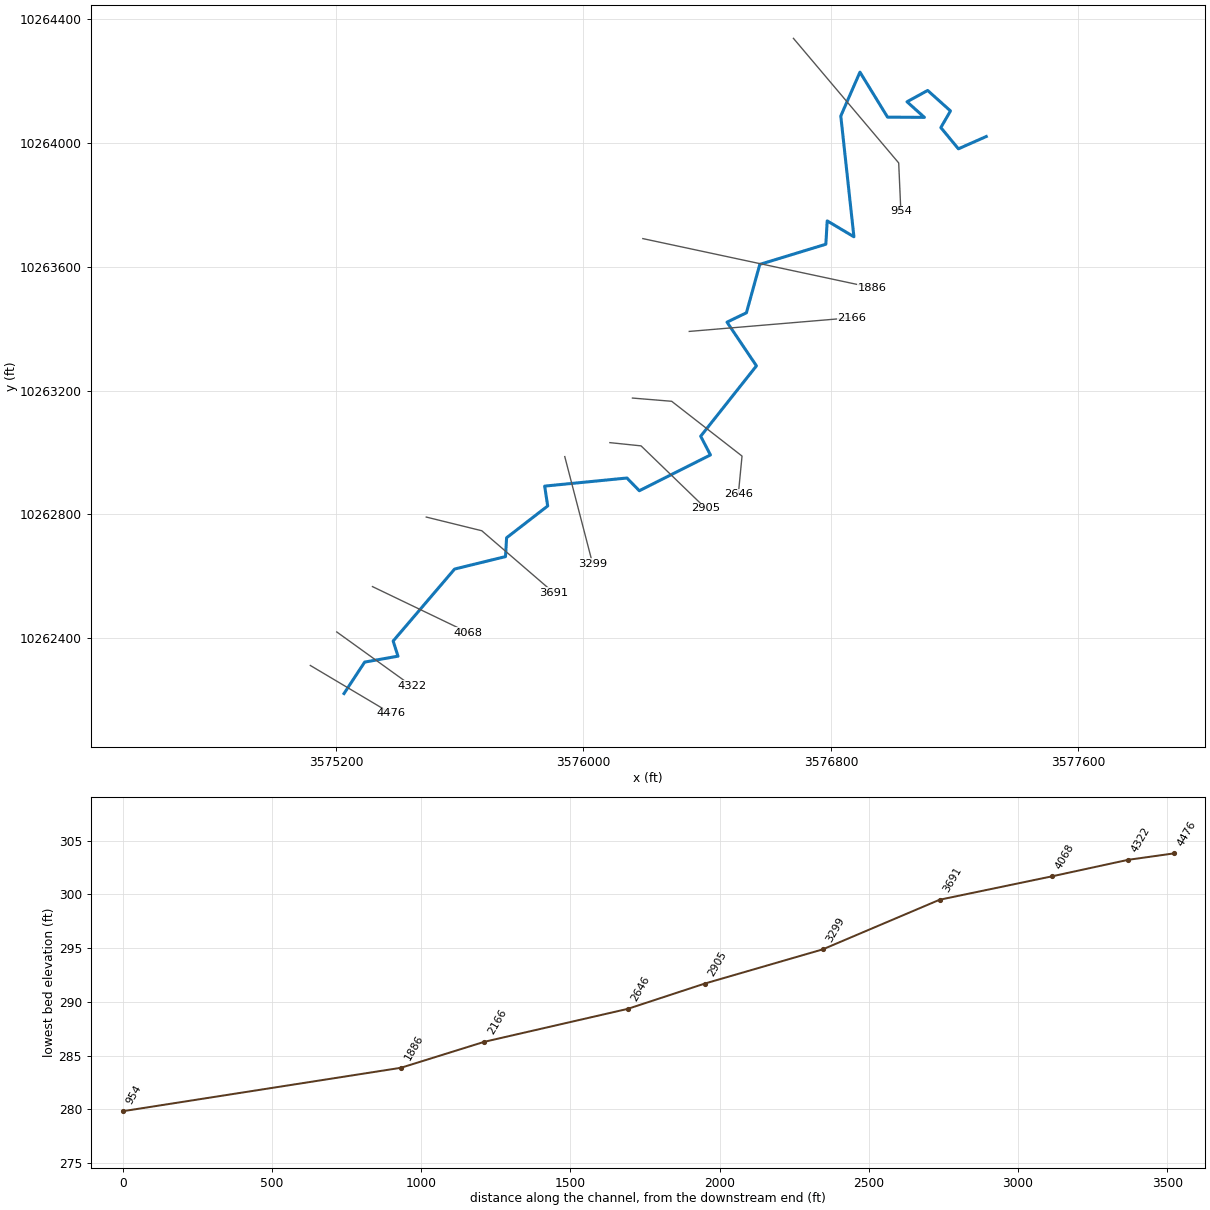
--- BOWMANCRTRIB131.prj (project) ---

Proj Title=BOWMAN CREEK TRIB 13 1
Current Plan=p01
Default Exp/Contr=0.3,0.1
English Units
Geom File=g01
Flow File=f01
Plan File=p01
Y Axis Title=Elevation
X Axis Title(PF)=Main Channel Distance
X Axis Title(XS)=Station
BEGIN DESCRIPTION:
UNT111 IN WICK
END DESCRIPTION:
DSS Export Rating Curves= 0
DSS Export Rating Curve Sorted= 0
DSS Export Volume Flow Curves= 0
DXF OffsetX= 0
DXF OffsetY= 0
DXF ScaleX= 1
DXF ScaleY= 10

--- BOWMANCRTRIB131.p01 (plan) ---

Plan Title=Multiple Run
Short Identifier=Multiple
Geom File=g01
Flow File=f01
Subcritical Flow
K Sum by GR= 0
Std Step Tol= 0.01
Critical Tol= 0.01
Num of Std Step Trials= 20
Max Error Tol= 0.3
Flow Tol Ratio= 0.001
Split Flow NTrial= 30
Split Flow Tol= 0.02
Split Flow Ratio= 0.02
Log Output Level= 0
Friction Slope Method= 1
Unsteady Friction Slope Method= 2
Unsteady Bridges Friction Slope Method= 1
Parabolic Critical Depth
Global Vel Dist=  1 , 1 , 1
Global Log Level= 0
CheckData=True
Encroach Param= -1, 0, 0, 0
BEGIN DESCRIPTION:
Multiple Run
END DESCRIPTION:

--- BOWMANCRTRIB131.f01 (steady flow) ---

Flow Title=Multiple
Program Version=4.10
Number of Profiles= 7
Profile Names=10-year,25-year,50-year,1pct_min,100-year,1pct_plu,500-year
River Rch & RM=BOWMANCRTRIB131,Reach-1         ,4476
     136     167     190     160     216     292     278
River Rch & RM=BOWMANCRTRIB131,Reach-1         ,2166
     265     340     398     344     465     629     632
River Rch & RM=BOWMANCRTRIB131,Reach-1         ,954
     429     567     677     594     803    1086    1130
Boundary for River Rch & Prof#=BOWMANCRTRIB131,Reach-1         , 1
Up Type= 0
Dn Type= 3
Dn Slope=0.005
Boundary for River Rch & Prof#=BOWMANCRTRIB131,Reach-1         , 2
Up Type= 0
Dn Type= 3
Dn Slope=0.005
Boundary for River Rch & Prof#=BOWMANCRTRIB131,Reach-1         , 3
Up Type= 0
Dn Type= 3
Dn Slope=0.005
Boundary for River Rch & Prof#=BOWMANCRTRIB131,Reach-1         , 4
Up Type= 0
Dn Type= 3
Dn Slope=0.005
Boundary for River Rch & Prof#=BOWMANCRTRIB131,Reach-1         , 5
Up Type= 0
Dn Type= 3
Dn Slope=0.005
Boundary for River Rch & Prof#=BOWMANCRTRIB131,Reach-1         , 6
Up Type= 0
Dn Type= 3
Dn Slope=0.005
Boundary for River Rch & Prof#=BOWMANCRTRIB131,Reach-1         , 7
Up Type= 0
Dn Type= 3
Dn Slope=0.005
DSS Import GetInterval= 0
DSS Import GetPeak= 0
DSS Import FillOption= 0

--- BOWMANCRTRIB131.g01 (geometry) ---

Geom Title=Existing Conditions
Program Version=4.10

River Reach=BOWMANCRTRIB131 ,Reach-1
Reach XY= 30
      3575226.29     10262221.23      3575293.08     10262322.92
      3575400.72     10262342.02       3575385.1     10262390.98
      3575583.71     10262623.62      3575748.29     10262663.89
      3575751.76     10262724.66      3575884.58     10262827.51
      3575874.79     10262891.68      3576140.64     10262917.85
      3576180.76     10262876.76      3576410.61     10262992.41
      3576379.06     10263052.88      3576559.29     10263280.36
      3576464.18      10263421.6      3576526.92     10263451.89
       3576570.1     10263608.27       3576783.6     10263673.44
      3576787.98     10263748.96      3576874.31     10263697.55
       3576831.9     10264087.89      3576893.84     10264229.67
      3576983.08     10264084.18      3577102.18     10264083.49
      3577045.93     10264133.84      3577112.67     10264170.48
      3577186.41     10264104.33       3577155.3      10264050.5
        3577212.     10263981.78      3577302.11     10264021.64

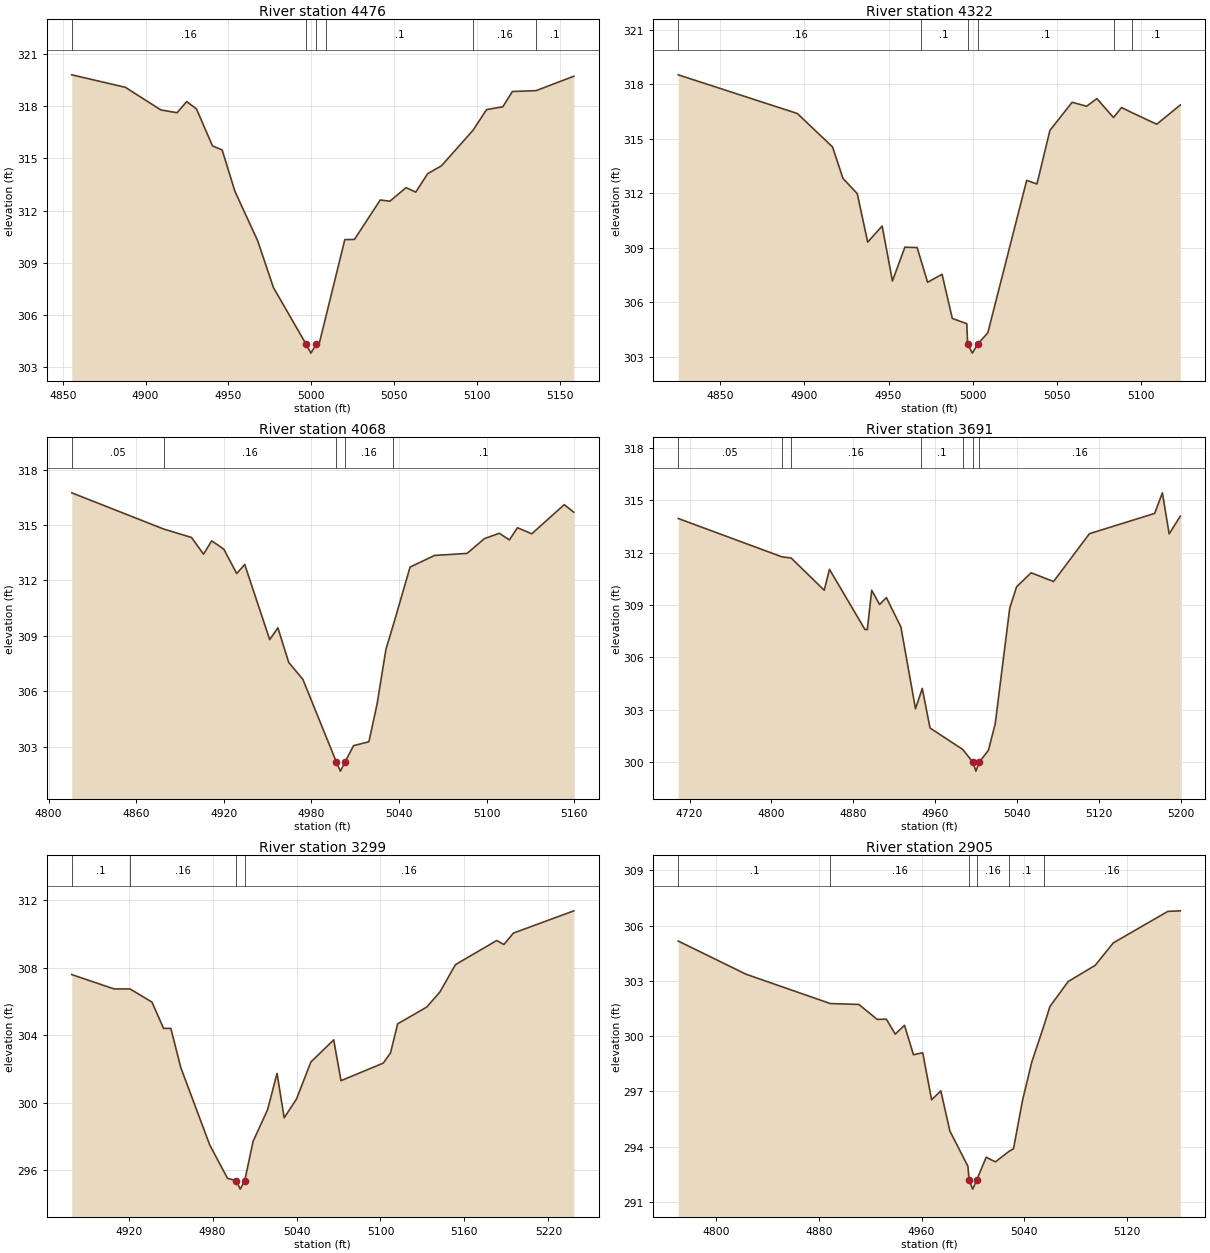
Type RM Length L Ch R = 1 ,4476    ,154,154,154
BEGIN DESCRIPTION:
UNT108 IN WICK 3.0
END DESCRIPTION:
XS GIS Cut Line= 2
      3575117.36     10262312.03      3575378.02     10262157.15
#Sta/Elev= 30
  4855.4  319.81  4887.8  319.09  4909.2  317.79    4919  317.63  4924.8  318.27
  4930.7  317.85  4940.4  315.72  4946.2  315.49    4954  313.09  4967.6  310.28
  4977.2  307.57    4997   304.3  4999.8   303.8    5003   304.3  5004.7   304.3
  5008.7  305.84  5020.3  310.33  5026.1  310.34  5041.7  312.61  5047.5  312.54
  5057.3  313.32  5063.1  313.06  5070.3  314.12  5078.7  314.58  5097.7  316.62
  5105.9  317.81  5115.7  317.97  5121.5  318.85  5135.8   318.9  5158.6  319.73
#Mann= 6 ,-1 , 0
  4855.4     .16       0    4997     .07       0    5003     .16       0
  5008.7      .1       0  5097.7     .16       0  5135.8      .1       0
Bank Sta=4997,5003
XS Rating Curve= 0 ,0
Exp/Cntr=0.3,0.1

Type RM Length L Ch R = 1 ,4322    ,254,254,254
BEGIN DESCRIPTION:
Mapping XS eaeb313e
END DESCRIPTION:
XS GIS Cut Line= 2
      3575202.82     10262420.34      3575444.98     10262245.98
#Sta/Elev= 30
    4825  318.52  4895.8  316.39  4916.7  314.55  4922.9  312.82  4931.4  311.98
  4937.6  309.31  4946.2   310.2  4952.3  307.17  4959.7  309.03    4967  309.01
  4969.2  308.33  4973.2   307.1  4981.8  307.54  4987.9  305.11  4996.5  304.82
    4997   303.7  4999.8   303.2    5003   303.7    5009  304.32  5032.1  312.71
  5038.2  312.51  5045.9  315.46  5059.1  317.01  5067.7  316.79  5073.8  317.21
  5083.7  316.17  5088.5  316.72  5094.4  316.45  5109.4   315.8  5123.4  316.86
#Mann= 6 ,-1 , 0
    4825     .16       0  4969.2      .1       0    4997     .07       0
    5003      .1       0  5083.7     .16       0  5094.4      .1       0
Bank Sta=4997,5003
XS Rating Curve= 0 ,0
Exp/Cntr=0.3,0.1

Type RM Length L Ch R = 1 ,4068    ,377,377,377
BEGIN DESCRIPTION:
Mapping XS 8a9d8c5f
END DESCRIPTION:
XS GIS Cut Line= 2
      3575318.24     10262566.91      3575628.03     10262418.07
#Sta/Elev= 30
  4815.9  316.74  4878.8  314.78  4897.9  314.32  4906.1  313.42  4911.7  314.14
    4920  313.69  4928.8  312.37  4934.3  312.86  4951.4  308.79    4957  309.43
  4964.4  307.56  4974.1  306.64    4997  302.17  4999.8  301.67    5003  302.17
  5008.8  303.05  5019.3  303.26  5024.9   305.3    5031  308.28  5036.1  309.61
  5047.5  312.72  5064.3  313.35  5086.5  313.46  5098.4  314.26  5108.6  314.55
  5115.5  314.19    5121  314.85  5130.8  314.52    5153   316.1  5159.6  315.69
#Mann= 5 ,-1 , 0
  4815.9     .05       0  4878.8     .16       0    4997     .07       0
    5003     .16       0  5036.1      .1       0
Bank Sta=4997,5003
XS Rating Curve= 0 ,0
Exp/Cntr=0.3,0.1

Type RM Length L Ch R = 1 ,3691    ,392,392,392
BEGIN DESCRIPTION:
UNT108 IN WICK 2.0
END DESCRIPTION:
XS GIS Cut Line= 3
      3575492.09     10262791.65      3575671.55     10262747.43
      3575903.31     10262547.82
#Sta/Elev= 30
  4708.9  313.96  4810.4  311.76  4819.2   311.7  4851.6  309.85  4856.7  311.05
  4891.4   307.6  4893.7   307.6    4898  309.85  4905.7  309.03  4912.3  309.43
  4926.5  307.75  4940.8  303.06  4945.9  303.96  4947.4  304.23    4955  301.96
    4987  300.73    4997  299.99  4999.8  299.49    5003  299.99  5012.1  300.69
  5018.7   302.2  5032.9  308.83  5039.6  310.05  5053.8  310.85  5075.7  310.35
  5110.8  313.09  5174.5  314.25  5182.1  315.43  5188.7  313.08  5199.6  314.09
#Mann= 7 ,-1 , 0
  4708.9     .05       0  4810.4      .1       0  4819.2     .16       0
  4945.9      .1       0    4987     .16       0    4997     .07       0
    5003     .16       0
Bank Sta=4997,5003
XS Rating Curve= 0 ,0
Exp/Cntr=0.3,0.1

Type RM Length L Ch R = 1 ,3299    ,394,394,394
BEGIN DESCRIPTION:
Mapping XS b23211dd
END DESCRIPTION:
XS GIS Cut Line= 2
      3575939.79     10262987.05      3576030.08      10262639.8
#Sta/Elev= 30
  4879.4  307.59  4909.6  306.74    4921  306.74  4936.7  305.96    4945   304.4
  4950.2   304.4  4957.3  302.08    4978  297.49  4990.7  295.51    4997  295.37
  4999.8  294.87    5003  295.37    5009  297.71  5019.3  299.57  5026.1  301.73
  5031.2   299.1    5040  300.21  5050.3  302.41  5066.6  303.72  5071.8   301.3
    5102  302.34  5107.2  302.95  5112.3  304.67    5133  305.66  5142.5  306.56
  5153.6  308.18  5183.1  309.61  5188.2  309.37    5195  310.05  5238.2  311.37
#Mann= 4 ,-1 , 0
  4879.4      .1       0    4921     .16       0    4997     .07       0
    5003     .16       0
Bank Sta=4997,5003
XS Rating Curve= 0 ,0
Exp/Cntr=0.3,0.1

Type RM Length L Ch R = 1 ,2905    ,259,259,259
BEGIN DESCRIPTION:
Mapping XS dc70626a
END DESCRIPTION:
XS GIS Cut Line= 3
       3576085.6     10263032.18      3576186.32     10263021.76
      3576394.65     10262820.38
#Sta/Elev= 30
  4770.5  305.16  4823.3  303.36  4888.9  301.77  4911.2  301.72  4925.4  300.91
  4932.6  300.92  4939.5  300.11  4946.7  300.59  4953.7  298.99  4960.9   299.1
  4967.8  296.55    4975  297.03    4982  294.86  4996.1  292.94    4997   292.2
  4999.8   291.7    5003   292.2  5010.3  293.43  5017.5  293.18  5028.1  293.75
  5031.6  293.89  5038.6  296.51  5045.8  298.59  5055.3  300.57  5059.9   301.6
  5074.1  302.96  5095.2  303.84  5109.3  305.06  5151.8  306.77  5161.5   306.8
#Mann= 6 ,-1 , 0
  4770.5      .1       0  4888.9     .16       0    4997     .07       0
    5003     .16       0  5028.1      .1       0  5055.3     .16       0
Bank Sta=4997,5003
XS Rating Curve= 0 ,0
Exp/Cntr=0.3,0.1

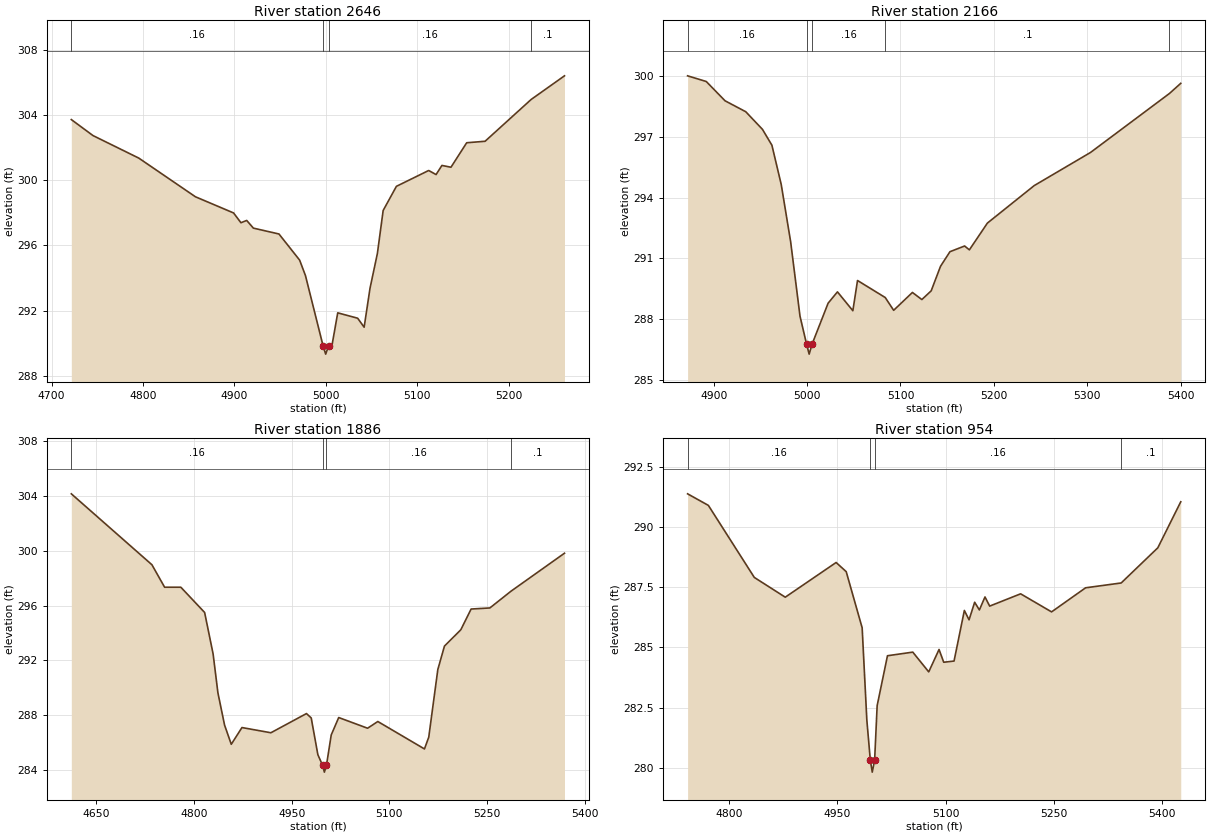
Type RM Length L Ch R = 1 ,2646    ,480,480,480
BEGIN DESCRIPTION:
UNT108 IN WICK 1.0
END DESCRIPTION:
XS GIS Cut Line= 4
      3576158.52     10263176.27      3576285.28     10263165.85
      3576512.71     10262988.77       3576500.7     10262865.18
#Sta/Elev= 30
  4721.5  303.71  4745.2  302.73  4795.3  301.35  4857.3  298.98    4899  297.99
  4907.1  297.39  4913.4  297.53  4920.7  297.06  4948.7   296.7  4971.3   295.1
  4977.7  294.15    4997  289.84  4999.8  289.34    5003  289.84  5006.6  289.84
    5013  291.87  5034.8  291.54  5041.9  290.99  5048.3  293.37  5056.4  295.51
  5062.7  298.14  5077.2  299.62  5112.5  300.59  5120.6  300.34    5127   300.9
  5136.9  300.79  5154.1  302.29  5174.2  302.38  5224.6  304.94  5261.1  306.39
#Mann= 4 ,-1 , 0
  4721.5     .16       0    4997     .07       0    5003     .16       0
  5224.6      .1       0
Bank Sta=4997,5003
XS Rating Curve= 0 ,0
Exp/Cntr=0.3,0.1

Type RM Length L Ch R = 1 ,2166    ,280,280,280
BEGIN DESCRIPTION:
UNT111 IN WICK 3.0
END DESCRIPTION:
XS GIS Cut Line= 2
      3576342.14     10263391.65      3576868.47     10263436.03
#Sta/Elev= 30
    4872     300    4892  299.72  4912.1  298.77  4934.3  298.23  4952.2  297.36
  4962.3  296.58  4972.3  294.64  4982.4  291.81  4992.4  288.15  4999.4  286.78
  5002.2  286.28  5005.4  286.78  5022.5  288.79  5032.5  289.35    5049  288.42
    5054  289.91  5083.7  289.07  5092.7  288.44  5112.8  289.32  5122.9  288.97
  5132.9   289.4  5142.9  290.61    5153  291.33  5168.7  291.61  5173.8  291.42
  5193.1  292.74  5243.3  294.59  5303.5  296.22  5388.1  299.13  5400.2  299.63
#Mann= 5 ,-1 , 0
    4872     .16       0  4999.4     .07       0  5005.4     .16       0
  5083.7      .1       0  5388.1     .16       0
Bank Sta=4999.4,5005.4
XS Rating Curve= 0 ,0
Exp/Cntr=0.3,0.1

Type RM Length L Ch R = 1 ,1886    ,932,932,932
BEGIN DESCRIPTION:
UNT111 IN WICK 2.0
END DESCRIPTION:
XS GIS Cut Line= 2
      3576192.07     10263691.65      3576932.23     10263533.37
#Sta/Elev= 30
  4611.8  304.15  4735.5  298.98    4755  297.34  4779.9  297.34  4816.4   295.5
  4829.4  292.48  4836.8  289.64    4847  287.29  4857.3  285.89  4873.7  287.11
  4918.1  286.73  4972.7  288.13    4980  287.81  4990.2  285.13  4997.4  284.36
  5000.2  283.86  5003.4  284.36  5010.7  286.57  5022.2  287.84  5066.5  287.06
  5082.2  287.55  5153.8  285.55  5160.4  286.41  5174.3  291.34  5184.5  293.05
  5209.6  294.24  5225.4  295.75  5254.2  295.83  5286.6  297.05  5368.7  299.82
#Mann= 4 ,-1 , 0
  4611.8     .16       0  4997.4     .07       0  5003.4     .16       0
  5286.6      .1       0
Bank Sta=4997.4,5003.4
XS Rating Curve= 0 ,0
Exp/Cntr=0.3,0.1

Type RM Length L Ch R = 1 ,954     ,0,0,0
BEGIN DESCRIPTION:
UNT111 IN WICK 1.0
END DESCRIPTION:
XS GIS Cut Line= 3
      3576678.79     10264338.92      3577019.07     10263936.14
      3577026.01     10263779.87
#Sta/Elev= 30
  4742.2  291.37    4771  290.89  4834.7   287.9  4877.6  287.08  4948.1  288.52
  4962.1  288.14  4984.2  285.81  4990.7  281.98  4995.5  280.32  4998.2  279.82
  5001.5  280.32    5005  282.58  5019.3  284.65  5054.4   284.8  5076.5  283.98
  5090.8  284.91  5097.3  284.38  5111.6  284.43  5125.9  286.53  5132.4  286.14
  5140.2  286.87  5146.7  286.55  5154.5  287.09    5161  286.71  5203.9  287.22
  5246.8  286.47    5294  287.47  5343.3  287.67  5394.1  289.13  5425.9  291.04
#Mann= 4 ,-1 , 0
  4742.2     .16       0  4995.5     .07       0  5001.5     .16       0
  5343.3      .1       0
Bank Sta=4995.5,5001.5
XS Rating Curve= 0 ,0
Exp/Cntr=0.3,0.1

Chan Stop Cuts=-1
Use User Specified Reach Order=0
Composite Channel Slope=5