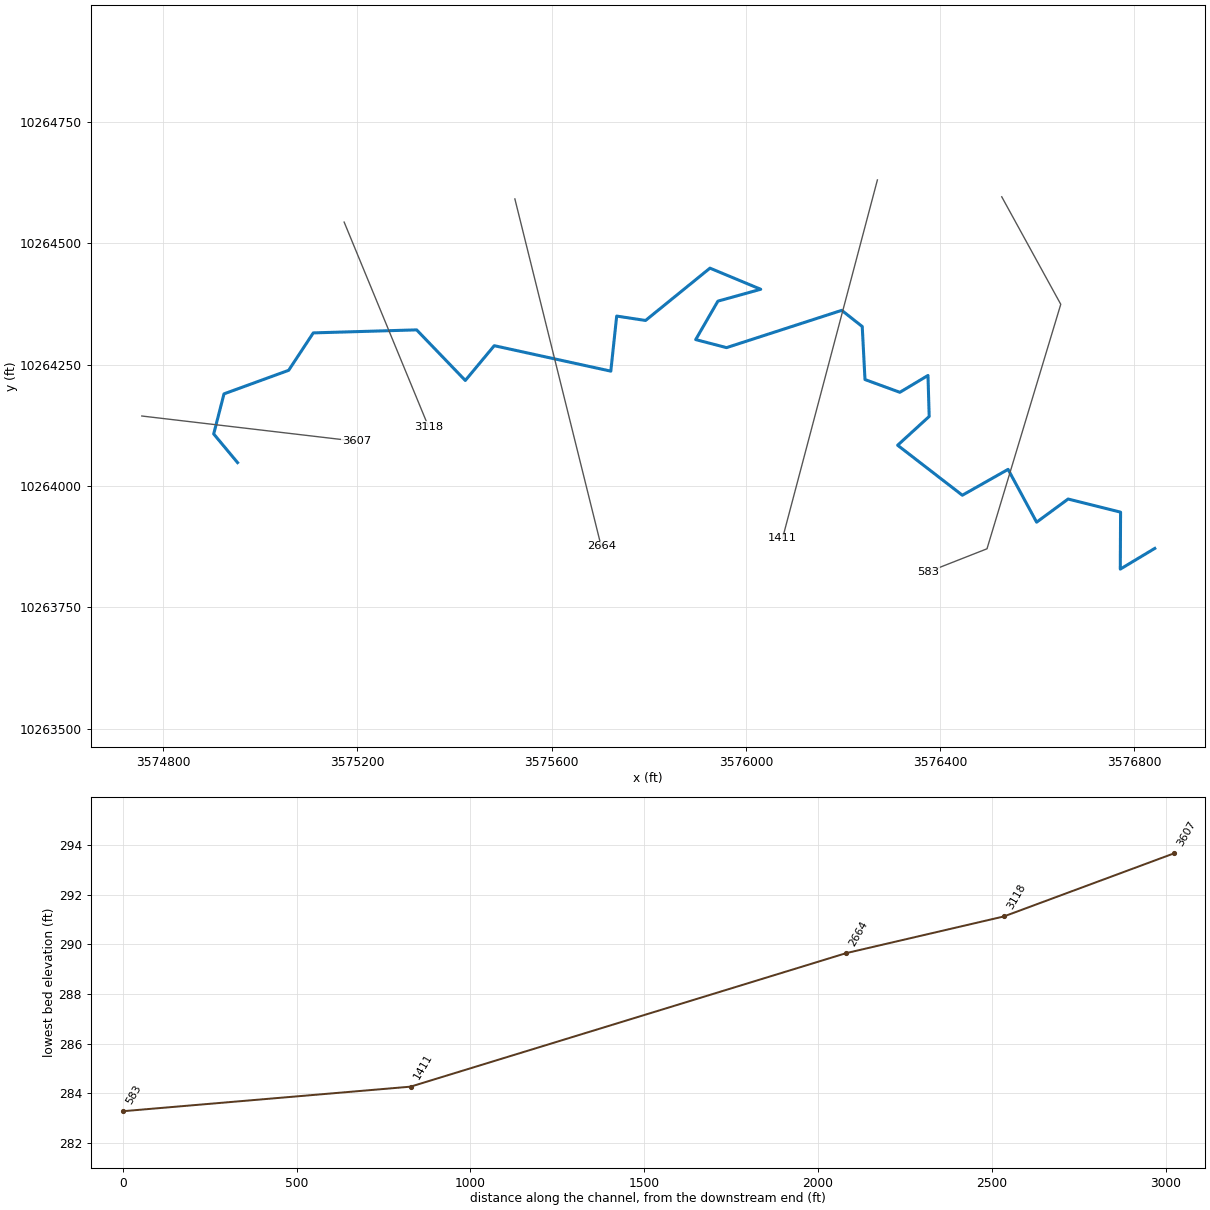
--- BOWMANCRTRIB13.prj (project) ---

Proj Title=BOWMAN CREEK TRIB 13
Current Plan=p01
Default Exp/Contr=0.3,0.1
English Units
Geom File=g01
Flow File=f01
Plan File=p01
Y Axis Title=Elevation
X Axis Title(PF)=Main Channel Distance
X Axis Title(XS)=Station
BEGIN DESCRIPTION:
UNT110 IN WICK
END DESCRIPTION:
DSS Export Rating Curves= 0
DSS Export Rating Curve Sorted= 0
DSS Export Volume Flow Curves= 0
DXF OffsetX= 0
DXF OffsetY= 0
DXF ScaleX= 1
DXF ScaleY= 10

--- BOWMANCRTRIB13.p01 (plan) ---

Plan Title=Multiple Run
Short Identifier=Multiple
Geom File=g01
Flow File=f01
Subcritical Flow
K Sum by GR= 0
Std Step Tol= 0.01
Critical Tol= 0.01
Num of Std Step Trials= 20
Max Error Tol= 0.3
Flow Tol Ratio= 0.001
Split Flow NTrial= 30
Split Flow Tol= 0.02
Split Flow Ratio= 0.02
Log Output Level= 0
Friction Slope Method= 1
Unsteady Friction Slope Method= 2
Unsteady Bridges Friction Slope Method= 1
Parabolic Critical Depth
Global Vel Dist=  1 , 1 , 1
Global Log Level= 0
CheckData=True
Encroach Param= -1, 0, 0, 0
BEGIN DESCRIPTION:
Multiple Run
END DESCRIPTION:

--- BOWMANCRTRIB13.f01 (steady flow) ---

Flow Title=Multiple
Program Version=4.10
Number of Profiles= 7
Profile Names=10-year,25-year,50-year,1pct_min,100-year,1pct_plu,500-year
River Rch & RM=UNT110 IN WICK,Reach-1         ,3607
     244     311     362     310     419     567     562
River Rch & RM=BOWMANCRTRIB13,Reach-1         ,3607
     244     311     362     310     419     567     562
Boundary for River Rch & Prof#=BOWMANCRTRIB13,Reach-1         , 1
Up Type= 0
Dn Type= 3
Dn Slope=0.005
Boundary for River Rch & Prof#=BOWMANCRTRIB13,Reach-1         , 2
Up Type= 0
Dn Type= 3
Dn Slope=0.005
Boundary for River Rch & Prof#=BOWMANCRTRIB13,Reach-1         , 3
Up Type= 0
Dn Type= 3
Dn Slope=0.005
Boundary for River Rch & Prof#=BOWMANCRTRIB13,Reach-1         , 4
Up Type= 0
Dn Type= 3
Dn Slope=0.005
Boundary for River Rch & Prof#=BOWMANCRTRIB13,Reach-1         , 5
Up Type= 0
Dn Type= 3
Dn Slope=0.005
Boundary for River Rch & Prof#=BOWMANCRTRIB13,Reach-1         , 6
Up Type= 0
Dn Type= 3
Dn Slope=0.005
Boundary for River Rch & Prof#=BOWMANCRTRIB13,Reach-1         , 7
Up Type= 0
Dn Type= 3
Dn Slope=0.005
DSS Import GetInterval= 0
DSS Import GetPeak= 0
DSS Import FillOption= 0

--- BOWMANCRTRIB13.g01 (geometry) ---

Geom Title=Existing Conditions
Program Version=4.10

River Reach=BOWMANCRTRIB13  ,Reach-1
Reach XY= 30
      3574953.33     10264048.33       3574904.2      10264107.3
      3574925.42     10264189.88      3575058.56     10264238.36
       3575109.3     10264315.44      3575322.11     10264321.64
      3575422.32     10264217.48      3575481.95     10264289.08
      3575721.96     10264236.65      3575734.06     10264350.05
      3575793.52     10264341.03      3575926.17     10264448.76
      3576030.67     10264405.26      3575942.46     10264380.79
      3575896.78     10264301.64      3575960.28     10264285.08
      3576197.51     10264361.86       3576239.7     10264328.53
      3576245.37     10264219.34      3576317.16      10264193.1
      3576375.11     10264227.83      3576377.58     10264143.35
      3576312.61     10264084.08      3576445.87     10263981.11
      3576540.01     10264034.38      3576598.81     10263925.66
      3576663.66     10263973.32      3576771.71     10263946.26
      3576771.11       10263829.      3576842.11     10263871.64

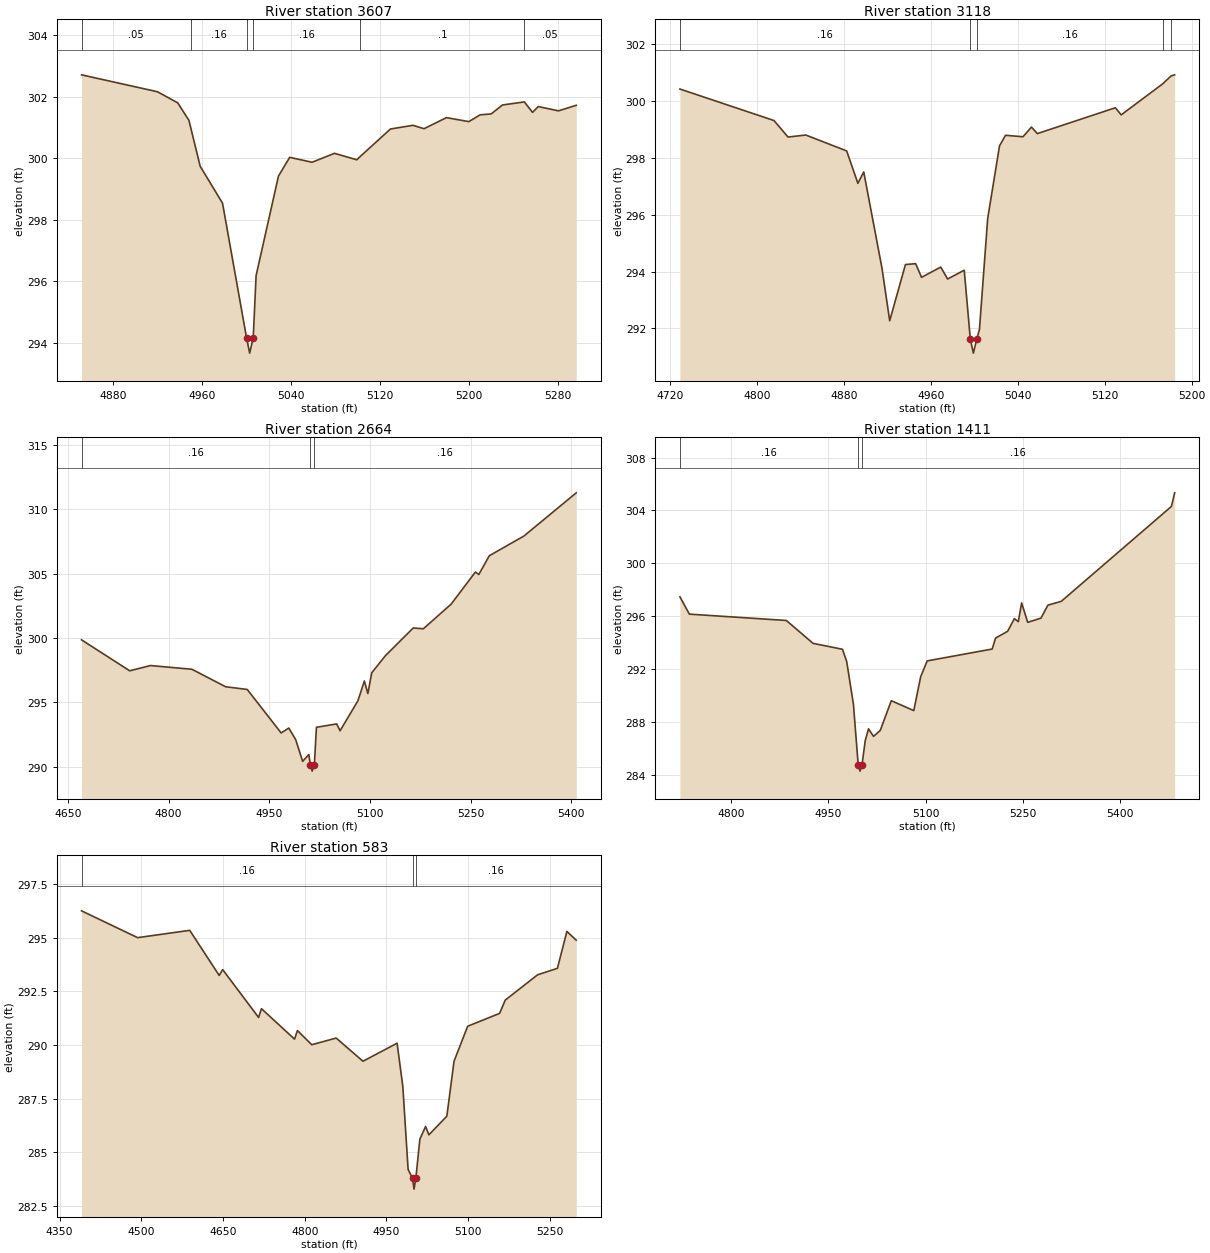
Type RM Length L Ch R = 1 ,3607    ,489,489,489
BEGIN DESCRIPTION:
UNT110 IN WICK 4.0
END DESCRIPTION:
XS GIS Cut Line= 2
      3574756.18     10264144.27      3575198.04     10264092.28
#Sta/Elev= 30
  4851.3  302.71  4919.6  302.16  4937.8   301.8  4947.9  301.23  4949.8  300.95
    4958  299.74  4978.1  298.54  4999.7  294.17  5002.5  293.67  5005.7  294.17
  5008.3  296.19  5028.4  299.42  5038.5  300.03  5058.6  299.87  5078.8  300.16
  5098.9  299.95    5102  300.06  5129.1  300.95  5149.3  301.07  5159.3  300.96
  5179.5  301.32  5199.6  301.19  5209.7  301.41  5219.7  301.44  5229.8  301.73
  5249.5  301.83  5256.9  301.49    5262  301.68  5280.2  301.54  5296.2  301.72
#Mann= 6 ,-1 , 0
  4851.3     .05       0  4949.8     .16       0  4999.7     .07       0
  5005.7     .16       0    5102      .1       0  5249.5     .05       0
Bank Sta=4999.7,5005.7
XS Rating Curve= 0 ,0
Exp/Cntr=0.3,0.1

Type RM Length L Ch R = 1 ,3118    ,454,454,454
BEGIN DESCRIPTION:
Mapping XS c0e5a67f
END DESCRIPTION:
XS GIS Cut Line= 2
      3575172.83     10264543.59      3575346.45     10264122.58
#Sta/Elev= 30
  4728.9  300.43  4815.5  299.32  4828.4  298.74  4844.8  298.81  4882.4  298.25
  4892.7  297.11  4898.1  297.51  4914.9  294.12    4922  292.27  4936.5  294.25
  4945.9  294.28  4951.3   293.8    4969  294.16  4975.3  293.74  4990.6  294.05
  4996.2  291.63    4999  291.13  5002.2  291.63  5004.6  291.96  5012.2  295.87
  5023.1  298.43  5028.6   298.8  5044.7  298.75  5052.5  299.09  5057.9  298.86
  5129.7  299.77  5135.1  299.52  5173.2  300.61    5181  300.89  5184.3  300.93
#Mann= 5 ,-1 , 0
  4728.9     .16       0  4996.2     .07       0  5002.2     .16       0
  5173.2      .1       0    5181     .05       0
Bank Sta=4996.2,5002.2
XS Rating Curve= 0 ,0
Exp/Cntr=0.3,0.1

Type RM Length L Ch R = 1 ,2664    ,1253,1253,1253
BEGIN DESCRIPTION:
UNT110 IN WICK 3.0
END DESCRIPTION:
XS GIS Cut Line= 2
      3575524.41      10264591.3      3575702.16     10263875.95
#Sta/Elev= 30
  4670.3  299.86  4742.1  297.45    4773  297.86  4834.8  297.57    4885  296.21
  4917.2     296  4967.7  292.62  4979.1     293  4989.4   292.1  4999.7  290.41
    5009  290.94  5011.2  290.15  5013.9  289.65  5017.2  290.15  5020.3  293.06
  5050.4  293.32  5055.5  292.79  5082.1  295.12  5091.7  296.66  5096.9  295.68
  5102.7   297.3  5123.3  298.64  5164.5  300.78  5179.6  300.72  5220.9  302.63
  5257.1  305.13  5262.2  304.94  5277.9   306.4  5329.4  307.93  5407.4  311.29
#Mann= 3 ,-1 , 0
  4670.3     .16       0  5011.2     .07       0  5017.2     .16       0
Bank Sta=5011.2,5017.2
XS Rating Curve= 0 ,0
Exp/Cntr=0.3,0.1

Type RM Length L Ch R = 1 ,1411    ,828,828,828
BEGIN DESCRIPTION:
UNT110 IN WICK 2.0
END DESCRIPTION:
XS GIS Cut Line= 2
      3576270.94     10264630.42      3576075.62     10263892.53
#Sta/Elev= 30
  4721.1  297.46  4735.7  296.15  4885.3  295.67  4926.5  293.94  4971.9  293.49
  4978.4  292.57  4988.8  289.33  4996.1  284.77  4998.9  284.27  5002.1  284.77
    5007  286.58  5012.1  287.47  5019.8   286.9  5030.2  287.35  5047.2   289.6
  5081.9  288.85  5092.6  291.42  5102.6  292.61  5202.9  293.51  5208.1  294.34
  5226.7  294.85  5237.1  295.81  5243.2  295.58  5248.3     297  5257.7  295.53
  5278.2  295.85  5288.8  296.83  5309.5  297.12  5479.4   304.3  5484.4  305.33
#Mann= 3 ,-1 , 0
  4721.1     .16       0  4996.1     .07       0  5002.1     .16       0
Bank Sta=4996.1,5002.1
XS Rating Curve= 0 ,0
Exp/Cntr=0.3,0.1

Type RM Length L Ch R = 1 ,583     ,0,0,0
BEGIN DESCRIPTION:
UNT110 IN WICK 1.0
END DESCRIPTION:
XS GIS Cut Line= 4
      3576526.99     10264595.69      3576648.53      10264374.3
      3576496.62     10263870.83      3576376.14      10263823.5
#Sta/Elev= 30
  4390.4  296.25  4493.3     295    4589  295.34    4643  293.24  4649.4  293.51
  4715.4  291.28  4720.6  291.69  4781.3  290.27  4786.6  290.67  4812.9  290.01
  4857.7  290.32  4906.9  289.24  4969.5  290.08    4980  288.07  4989.7   284.2
  4997.9  283.78  5000.6  283.28  5003.9  283.78  5011.3  285.61  5021.8   286.2
  5027.8  285.81  5060.8  286.68    5074  289.24    5099  290.87  5157.6  291.47
    5168  292.09  5227.4  293.27  5263.7  293.57  5281.1  295.29  5298.3  294.88
#Mann= 3 ,-1 , 0
  4390.4     .16       0  4997.9     .07       0  5003.9     .16       0
Bank Sta=4997.9,5003.9
XS Rating Curve= 0 ,0
Exp/Cntr=0.3,0.1

Chan Stop Cuts=-1
Use User Specified Reach Order=0
Composite Channel Slope=5