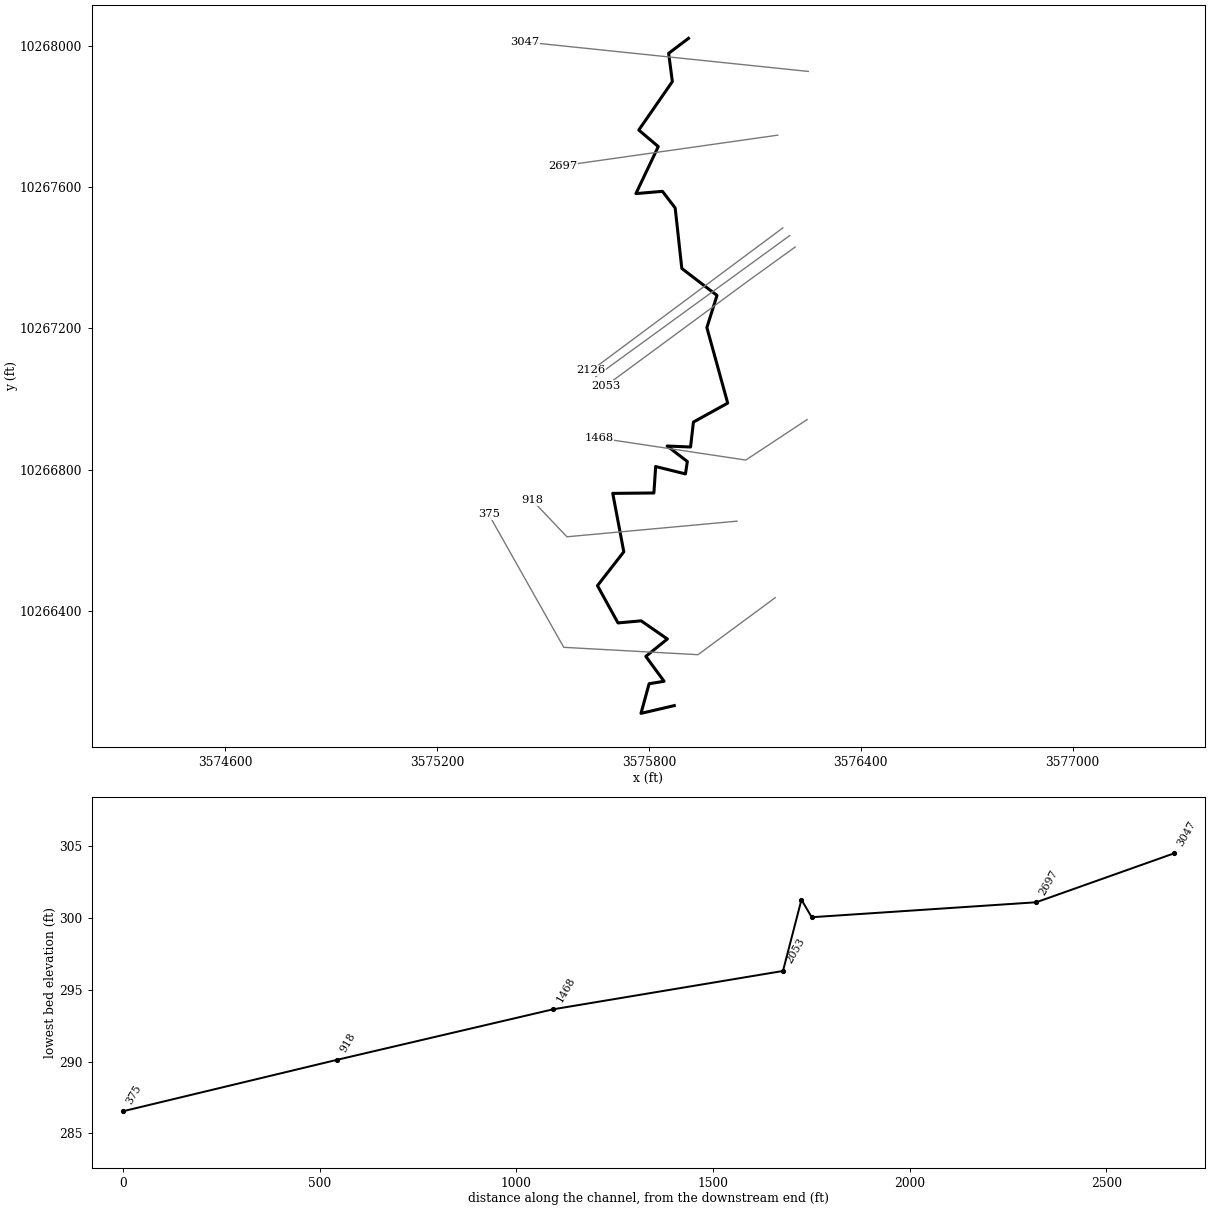
--- BOWMANCRTRIB14.prj (project) ---

Proj Title=BOWMAN CREEK TRIB 14
Current Plan=p01
Default Exp/Contr=0.3,0.1
English Units
Geom File=g01
Flow File=f01
Plan File=p01
Y Axis Title=Elevation
X Axis Title(PF)=Main Channel Distance
X Axis Title(XS)=Station
BEGIN DESCRIPTION:
UNT04953 IN WICK
END DESCRIPTION:
DSS Export Rating Curves= 0
DSS Export Rating Curve Sorted= 0
DSS Export Volume Flow Curves= 0
DXF OffsetX= 0
DXF OffsetY= 0
DXF ScaleX= 1
DXF ScaleY= 10

--- BOWMANCRTRIB14.p01 (plan) ---

Plan Title=Multiple Run
Short Identifier=Multiple
Geom File=g01
Flow File=f01
Subcritical Flow
K Sum by GR= 0
Std Step Tol= 0.01
Critical Tol= 0.01
Num of Std Step Trials= 20
Max Error Tol= 0.3
Flow Tol Ratio= 0.001
Split Flow NTrial= 30
Split Flow Tol= 0.02
Split Flow Ratio= 0.02
Log Output Level= 0
Friction Slope Method= 1
Unsteady Friction Slope Method= 2
Unsteady Bridges Friction Slope Method= 1
Parabolic Critical Depth
Global Vel Dist=  1 , 1 , 1
Global Log Level= 0
CheckData=True
Encroach Param= -1, 0, 0, 0
BEGIN DESCRIPTION:
Multiple Run
END DESCRIPTION:

--- BOWMANCRTRIB14.f01 (steady flow) ---

Flow Title=Multiple
Program Version=4.10
Number of Profiles= 7
Profile Names=10-year,25-year,50-year,1pct_min,100-year,1pct_plu,500-year
River Rch & RM=UNT04953 IN WICK,Reach-1         ,3047
     234     297     346     295     399     540     534
River Rch & RM=BOWMANCRTRIB14,Reach-1         ,3047
     234     297     346     295     399     540     534
Boundary for River Rch & Prof#=BOWMANCRTRIB14,Reach-1         , 1
Up Type= 0
Dn Type= 3
Dn Slope=0.005
Boundary for River Rch & Prof#=BOWMANCRTRIB14,Reach-1         , 2
Up Type= 0
Dn Type= 3
Dn Slope=0.005
Boundary for River Rch & Prof#=BOWMANCRTRIB14,Reach-1         , 3
Up Type= 0
Dn Type= 3
Dn Slope=0.005
Boundary for River Rch & Prof#=BOWMANCRTRIB14,Reach-1         , 4
Up Type= 0
Dn Type= 3
Dn Slope=0.005
Boundary for River Rch & Prof#=BOWMANCRTRIB14,Reach-1         , 5
Up Type= 0
Dn Type= 3
Dn Slope=0.005
Boundary for River Rch & Prof#=BOWMANCRTRIB14,Reach-1         , 6
Up Type= 0
Dn Type= 3
Dn Slope=0.005
Boundary for River Rch & Prof#=BOWMANCRTRIB14,Reach-1         , 7
Up Type= 0
Dn Type= 3
Dn Slope=0.005
DSS Import GetInterval= 0
DSS Import GetPeak= 0
DSS Import FillOption= 0

--- BOWMANCRTRIB14.g01 (geometry) ---

Geom Title=Existing Conditions
Program Version=4.10

River Reach=BOWMANCRTRIB14  ,Reach-1
Reach XY= 30
       3575912.4     10268021.52      3575856.16     10267979.05
      3575866.63     10267899.04      3575771.51     10267761.81
      3575826.72     10267714.94      3575763.38     10267581.75
      3575838.52      10267588.2      3575874.63     10267540.98
      3575893.38      10267369.8      3575993.04     10267293.41
      3575964.36     10267202.34      3576023.36     10266988.37
      3575926.32     10266934.72      3575918.15     10266864.07
      3575851.83     10266866.85      3575909.05     10266822.94
      3575903.72     10266787.83      3575819.34     10266808.75
      3575814.33     10266733.86      3575697.78     10266732.71
       3575729.1     10266567.25      3575654.49      10266471.4
       3575712.6      10266365.8      3575778.22     10266371.71
      3575852.53     10266320.32      3575791.42     10266271.01
      3575843.15     10266200.53      3575800.79     10266193.58
      3575777.75     10266109.62      3575872.11     10266131.64

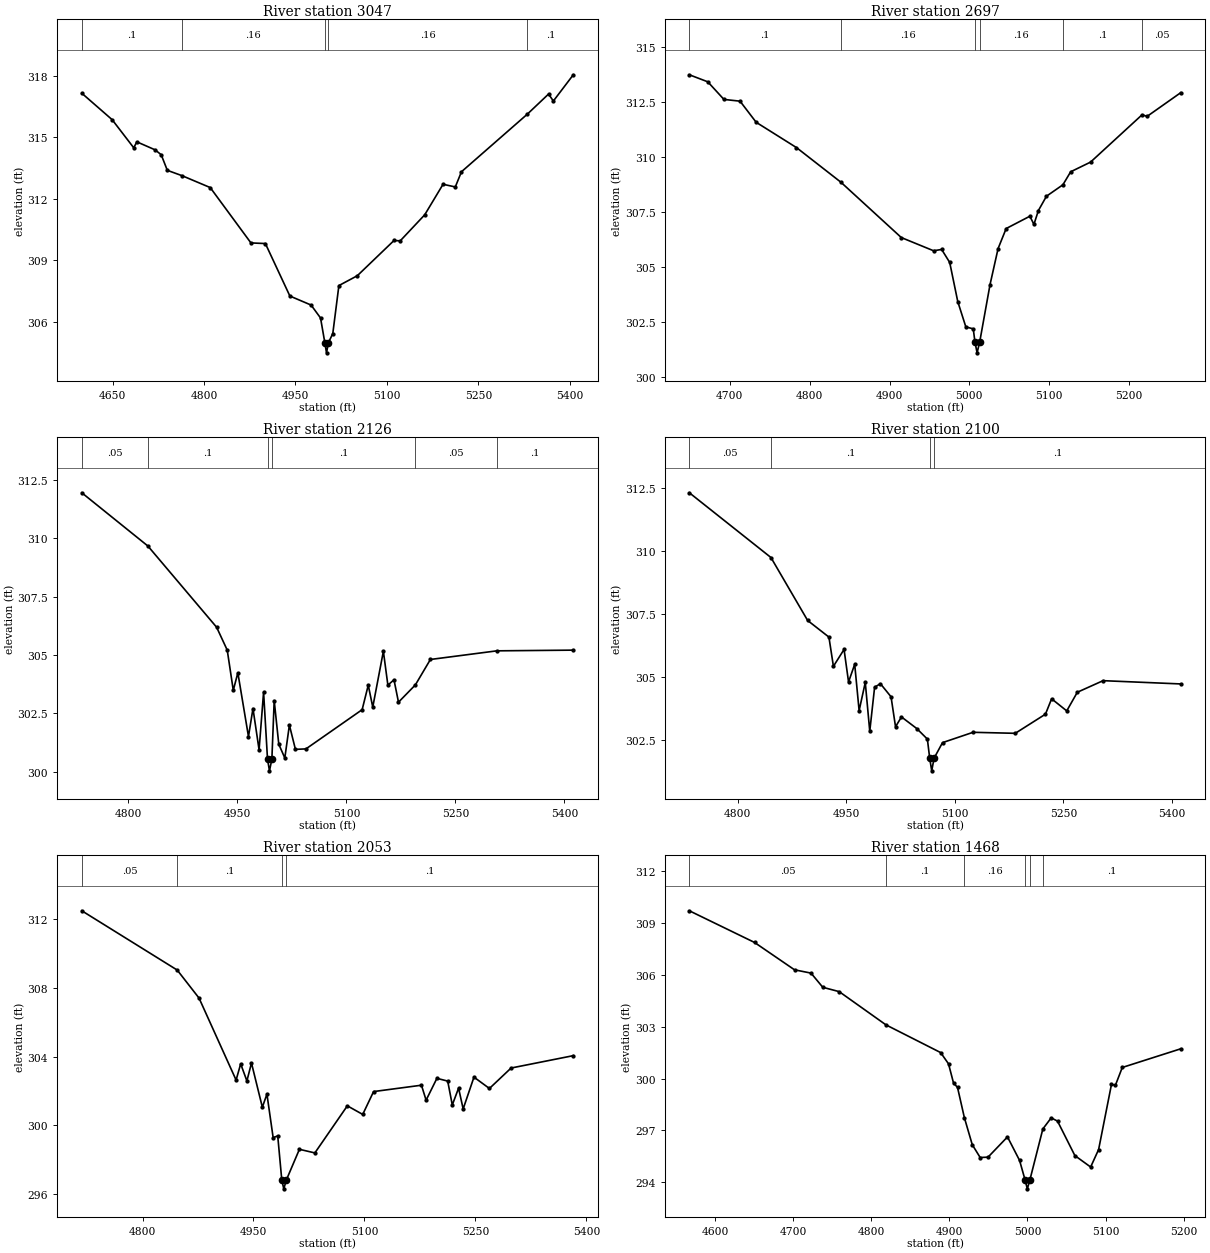
Type RM Length L Ch R = 1 ,3047    ,350,350,350
BEGIN DESCRIPTION:
UNT04953 IN WICK 5.0
END DESCRIPTION:
XS GIS Cut Line= 2
      3576251.67     10267927.81      3575449.59     10268011.15
#Sta/Elev= 30
  4599.4  317.14  4649.2  315.85  4684.6  314.48  4689.7  314.77  4719.6  314.38
  4729.7  314.14  4739.7  313.38  4763.8  313.12  4810.1  312.54  4876.9  309.84
  4900.6  309.81  4940.8  307.25  4975.6  306.81  4991.1  306.18  4998.1  304.98
  5000.9  304.48  5004.1  304.98  5011.2  305.42  5021.2  307.76  5051.4  308.24
  5111.7  309.96  5121.8  309.94    5162  311.21  5192.1   312.7  5212.2  312.57
  5222.3  313.31  5330.4  316.12  5365.2   317.1  5373.1  316.76  5405.8  318.04
#Mann= 5 ,-1 , 0
  4599.4      .1       0  4763.8     .16       0  4998.1     .07       0
  5004.1     .16       0  5330.4      .1       0
Bank Sta=4998.1,5004.1
XS Rating Curve= 0 ,0
Exp/Cntr=0.3,0.1

Type RM Length L Ch R = 1 ,2697    ,571,571,571
BEGIN DESCRIPTION:
UNT04953 IN WICK 4.0
END DESCRIPTION:
XS GIS Cut Line= 2
      3576164.95     10267747.26      3575555.47     10267660.69
#Sta/Elev= 30
  4649.3  313.72  4672.4   313.4  4692.6   312.6  4712.8  312.52    4733  311.56
  4783.5  310.41    4839  308.84  4914.8  306.32  4955.2  305.72  4965.3  305.78
  4975.4  305.19  4985.5  303.41  4995.6  302.26  5004.9  302.17    5007  301.58
  5009.7  301.08    5013  301.58  5025.9  304.18    5036  305.82  5046.1  306.73
  5075.8  307.29  5080.9  306.92  5086.5  307.55  5096.6   308.2  5117.2  308.72
  5126.9  309.31  5151.8  309.75  5216.3   311.9  5222.7  311.83  5264.9  312.91
#Mann= 6 ,-1 , 0
  4649.3      .1       0    4839     .16       0    5007     .07       0
    5013     .16       0  5117.2      .1       0  5216.3     .05       0
Bank Sta=5007,5013
XS Rating Curve= 0 ,0
Exp/Cntr=0.3,0.1

Type RM Length L Ch R = 1 ,2126    ,26,26,26
BEGIN DESCRIPTION:
Mapping XS db13860f
END DESCRIPTION:
XS GIS Cut Line= 2
      3576179.55     10267484.62      3575637.04     10267080.99
#Sta/Elev= 30
    4736  311.95  4826.9  309.67  4921.5  306.19  4936.1  305.21  4944.4  303.49
  4950.7  304.24  4965.3  301.51  4971.5  302.71  4979.9  300.94  4986.1  303.41
  4991.5  300.54  4994.2  300.04  4997.5  300.54  5000.7  303.05    5007  301.18
  5015.3  300.59  5021.6     302  5029.9  300.96  5044.4  300.98  5121.7  302.66
  5130.1  303.71  5136.3  302.77  5150.9  305.16  5157.1  303.71  5165.5  303.94
  5171.7  302.98  5194.9  303.72  5215.6  304.81  5307.1  305.18  5412.2  305.21
#Mann= 6 ,-1 , 0
    4736     .05       0  4826.9      .1       0  4991.5     .07       0
  4997.5      .1       0  5194.9     .05       0  5307.1      .1       0
Bank Sta=4991.5,4997.5
XS Rating Curve= 0 ,0
Exp/Cntr=0.3,0.1

Type RM Length L Ch R = 1 ,2100    ,47,47,47
BEGIN DESCRIPTION:
Mapping XS 709ca1cf
END DESCRIPTION:
XS GIS Cut Line= 2
      3576199.09     10267462.92      3575650.04     10267063.61
#Sta/Elev= 30
  4733.4   312.3  4846.1  309.73  4896.8  307.23  4926.2  306.57  4932.4  305.41
  4947.1  306.08  4953.3  304.79  4961.8  305.49  4967.9  303.65  4976.4  304.77
  4982.6  302.83  4989.3  304.58  4997.3  304.72    5012   304.2  5018.2  303.01
  5026.4   303.4  5047.5  302.94  5062.2  302.52  5065.4  301.76  5068.2  301.26
  5071.4  301.76  5083.1  302.38  5125.3  302.79  5183.6  302.75  5225.3  303.51
  5233.8  304.12  5254.7  303.64  5269.3  304.38  5304.9  304.84  5412.3  304.71
#Mann= 4 ,-1 , 0
  4733.4     .05       0  4846.1      .1       0  5065.4     .07       0
  5071.4      .1       0
Bank Sta=5065.4,5071.4
XS Rating Curve= 0 ,0
Exp/Cntr=0.3,0.1

Type RM Length L Ch R = 1 ,2053    ,585,585,585
BEGIN DESCRIPTION:
UNT04953 IN WICK 3.0
END DESCRIPTION:
XS GIS Cut Line= 3
      3576214.23     10267430.33      3576081.89     10267334.87
      3575678.24     10267037.56
#Sta/Elev= 30
  4717.9  312.48  4846.9  309.03  4876.4   307.4  4926.5  302.63  4932.7  303.57
  4941.1  302.58  4947.3  303.62    4962  301.05  4968.2  301.81  4976.6  299.28
  4982.8  299.38  4988.3   296.8    4991   296.3  4994.3   296.8  5012.1   298.6
    5033  298.39  5076.9  301.13  5097.7  300.63  5112.4  301.96  5177.1  302.33
  5183.4  301.46    5198  302.73  5212.6  302.57  5218.8  301.18  5227.3  302.16
  5233.5  300.95  5248.1   302.8    5269  302.14  5298.3  303.33  5382.4  304.05
#Mann= 4 ,-1 , 0
  4717.9     .05       0  4846.9      .1       0  4988.3     .07       0
  4994.3      .1       0
Bank Sta=4988.3,4994.3
XS Rating Curve= 0 ,0
Exp/Cntr=0.3,0.1

Type RM Length L Ch R = 1 ,1468    ,550,550,550
BEGIN DESCRIPTION:
UNT04953 IN WICK 2.0
END DESCRIPTION:
XS GIS Cut Line= 3
      3576248.25     10266941.71      3576074.62     10266827.11
      3575657.92     10266889.62
#Sta/Elev= 30
    4567  309.69  4650.5  307.86  4701.7  306.28  4722.8  306.09  4737.9  305.27
  4758.9  305.02  4818.8   303.1  4888.8   301.5  4898.9  300.85  4905.3  299.74
  4910.4  299.49  4919.2  297.74  4929.3  296.18  4939.4  295.44  4949.5  295.46
  4974.4  296.63  4989.9  295.27    4997  294.13  4999.8  293.63    5003  294.13
  5019.7  297.09  5030.4  297.73  5038.5  297.54  5060.7  295.55  5080.9  294.89
  5091.1   295.9  5107.6  299.67  5112.6  299.61  5121.4  300.64  5196.4  301.72
#Mann= 6 ,-1 , 0
    4567     .05       0  4818.8      .1       0  4919.2     .16       0
    4997     .07       0    5003     .16       0  5019.7      .1       0
Bank Sta=4997,5003
XS Rating Curve= 0 ,0
Exp/Cntr=0.3,0.1

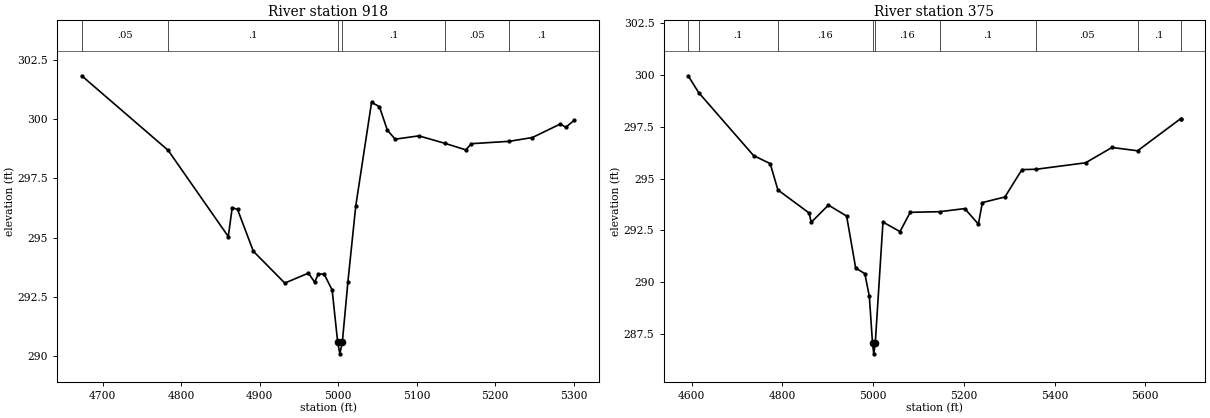
Type RM Length L Ch R = 1 ,918     ,543,543,543
BEGIN DESCRIPTION:
Mapping XS 70a26701
END DESCRIPTION:
XS GIS Cut Line= 3
      3576049.74     10266654.03      3575567.99     10266609.76
        3575469.     10266713.96
#Sta/Elev= 30
  4673.4  301.82  4783.5  298.68  4860.1  295.05  4865.1  296.27  4871.9  296.19
    4892  294.43  4932.1  293.09  4962.2  293.51    4970  293.13    4975  293.48
  4982.3  293.46  4992.4   292.8  4999.4  290.61  5002.2  290.11  5005.4  290.61
  5012.5  293.15  5022.5  296.34  5042.6   300.7  5052.6  300.52  5062.7  299.53
  5072.7  299.15  5102.8  299.29  5136.6  298.97  5162.6   298.7  5169.8  298.96
    5218  299.06  5247.5  299.22  5283.1  299.79    5290  299.65  5300.9  299.95
#Mann= 6 ,-1 , 0
  4673.4     .05       0  4783.5      .1       0  4999.4     .07       0
  5005.4      .1       0  5136.6     .05       0    5218      .1       0
Bank Sta=4999.4,5005.4
XS Rating Curve= 0 ,0
Exp/Cntr=0.3,0.1

Type RM Length L Ch R = 1 ,375     ,0,0,0
BEGIN DESCRIPTION:
UNT04953 IN WICK 1.0
END DESCRIPTION:
XS GIS Cut Line= 4
      3576157.95      10266437.3      3575939.21     10266275.85
        3575559.     10266296.68       3575346.3     10266673.66
#Sta/Elev= 30
  4592.6  299.96  4615.6  299.15  4736.6  296.11  4773.3  295.72  4790.3  294.45
  4858.9  293.34  4863.8  292.89  4901.6  293.72  4941.7  293.19  4961.7  290.68
  4981.8  290.41  4991.8  289.31  4998.8  287.04  5001.5  286.54  5004.8  287.04
  5021.8   292.9  5059.3  292.44  5081.9  293.37  5146.4   293.4  5202.1  293.55
  5232.1   292.8  5240.8  293.84  5290.5  294.11    5328  295.43    5360  295.45
  5468.2  295.76  5526.5   296.5  5582.9  296.34  5677.8  297.89  5678.1  297.89
#Mann= 9 ,-1 , 0
  4592.6     .05       0  4615.6      .1       0  4790.3     .16       0
  4998.8     .07       0  5004.8     .16       0  5146.4      .1       0
    5360     .05       0  5582.9      .1       0  5677.8     .05       0
Bank Sta=4998.8,5004.8
XS Rating Curve= 0 ,0
Exp/Cntr=0.3,0.1

Chan Stop Cuts=-1
Use User Specified Reach Order=0
Composite Channel Slope=5