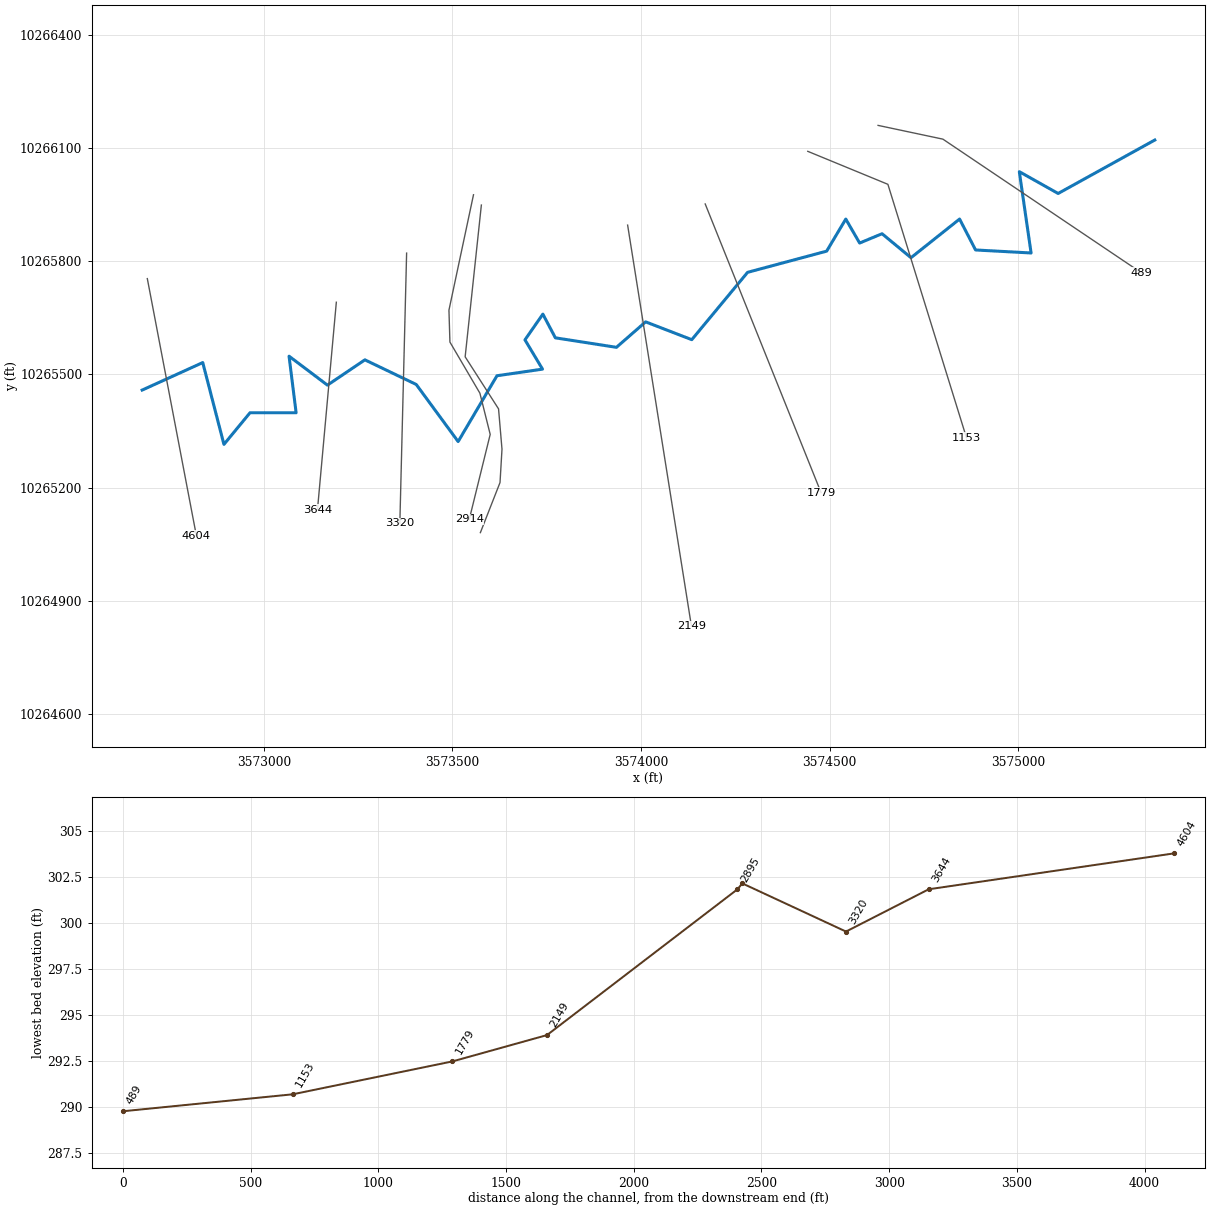
--- BOWMANCRTRIB15.prj (project) ---

Proj Title=BOWMAN CREEK TRIB 15
Current Plan=p01
Default Exp/Contr=0.3,0.1
English Units
Geom File=g01
Flow File=f01
Plan File=p01
Y Axis Title=Elevation
X Axis Title(PF)=Main Channel Distance
X Axis Title(XS)=Station
BEGIN DESCRIPTION:
UNT04952 IN WICK
END DESCRIPTION:
DSS Export Rating Curves= 0
DSS Export Rating Curve Sorted= 0
DSS Export Volume Flow Curves= 0
DXF OffsetX= 0
DXF OffsetY= 0
DXF ScaleX= 1
DXF ScaleY= 10

--- BOWMANCRTRIB15.p01 (plan) ---

Plan Title=Multiple Run
Short Identifier=Multiple
Geom File=g01
Flow File=f01
Subcritical Flow
K Sum by GR= 0
Std Step Tol= 0.01
Critical Tol= 0.01
Num of Std Step Trials= 20
Max Error Tol= 0.3
Flow Tol Ratio= 0.001
Split Flow NTrial= 30
Split Flow Tol= 0.02
Split Flow Ratio= 0.02
Log Output Level= 0
Friction Slope Method= 1
Unsteady Friction Slope Method= 2
Unsteady Bridges Friction Slope Method= 1
Parabolic Critical Depth
Global Vel Dist=  1 , 1 , 1
Global Log Level= 0
CheckData=True
Encroach Param= -1, 0, 0, 0
BEGIN DESCRIPTION:
Multiple Run
END DESCRIPTION:

--- BOWMANCRTRIB15.f01 (steady flow) ---

Flow Title=Multiple
Program Version=4.10
Number of Profiles= 7
Profile Names=10-year,25-year,50-year,1pct_min,100-year,1pct_plu,500-year
River Rch & RM=UNT04952 IN WICK,Reach-1         ,4604
     317     409     480     413     559     756     759
River Rch & RM=BOWMANCRTRIB15,Reach-1         ,4604
     317     409     480     413     559     756     759
Boundary for River Rch & Prof#=BOWMANCRTRIB15,Reach-1         , 1
Up Type= 0
Dn Type= 3
Dn Slope=0.005
Boundary for River Rch & Prof#=BOWMANCRTRIB15,Reach-1         , 2
Up Type= 0
Dn Type= 3
Dn Slope=0.005
Boundary for River Rch & Prof#=BOWMANCRTRIB15,Reach-1         , 3
Up Type= 0
Dn Type= 3
Dn Slope=0.005
Boundary for River Rch & Prof#=BOWMANCRTRIB15,Reach-1         , 4
Up Type= 0
Dn Type= 3
Dn Slope=0.005
Boundary for River Rch & Prof#=BOWMANCRTRIB15,Reach-1         , 5
Up Type= 0
Dn Type= 3
Dn Slope=0.005
Boundary for River Rch & Prof#=BOWMANCRTRIB15,Reach-1         , 6
Up Type= 0
Dn Type= 3
Dn Slope=0.005
Boundary for River Rch & Prof#=BOWMANCRTRIB15,Reach-1         , 7
Up Type= 0
Dn Type= 3
Dn Slope=0.005
DSS Import GetInterval= 0
DSS Import GetPeak= 0
DSS Import FillOption= 0

--- BOWMANCRTRIB15.g01 (geometry) ---

Geom Title=Existing Conditions
Program Version=4.10

River Reach=BOWMANCRTRIB15  ,Reach-1
Reach XY= 30
       3572677.3     10265458.69      3572837.92     10265531.59
      3572894.08     10265314.68      3572963.25     10265398.55
      3573085.47     10265398.55      3573066.72     10265548.55
      3573168.52     10265471.81      3573267.83     10265538.83
      3573403.94     10265473.55      3573515.05     10265322.16
      3573617.95     10265496.65      3573738.72     10265514.16
      3573692.18     10265591.82       3573739.7     10265660.01
      3573772.84     10265597.19      3573934.75     10265572.03
      3574012.15     10265639.53       3574134.5      10265592.3
      3574282.49     10265770.83      3574492.13     10265827.02
      3574542.83     10265912.09      3574579.57     10265848.47
      3574639.01      10265873.2      3574715.75     10265809.66
      3574844.56     10265912.09      3574886.93     10265830.15
      3575034.15     10265822.16       3575002.9     10266037.78
      3575105.86     10265979.92      3575362.11     10266121.64

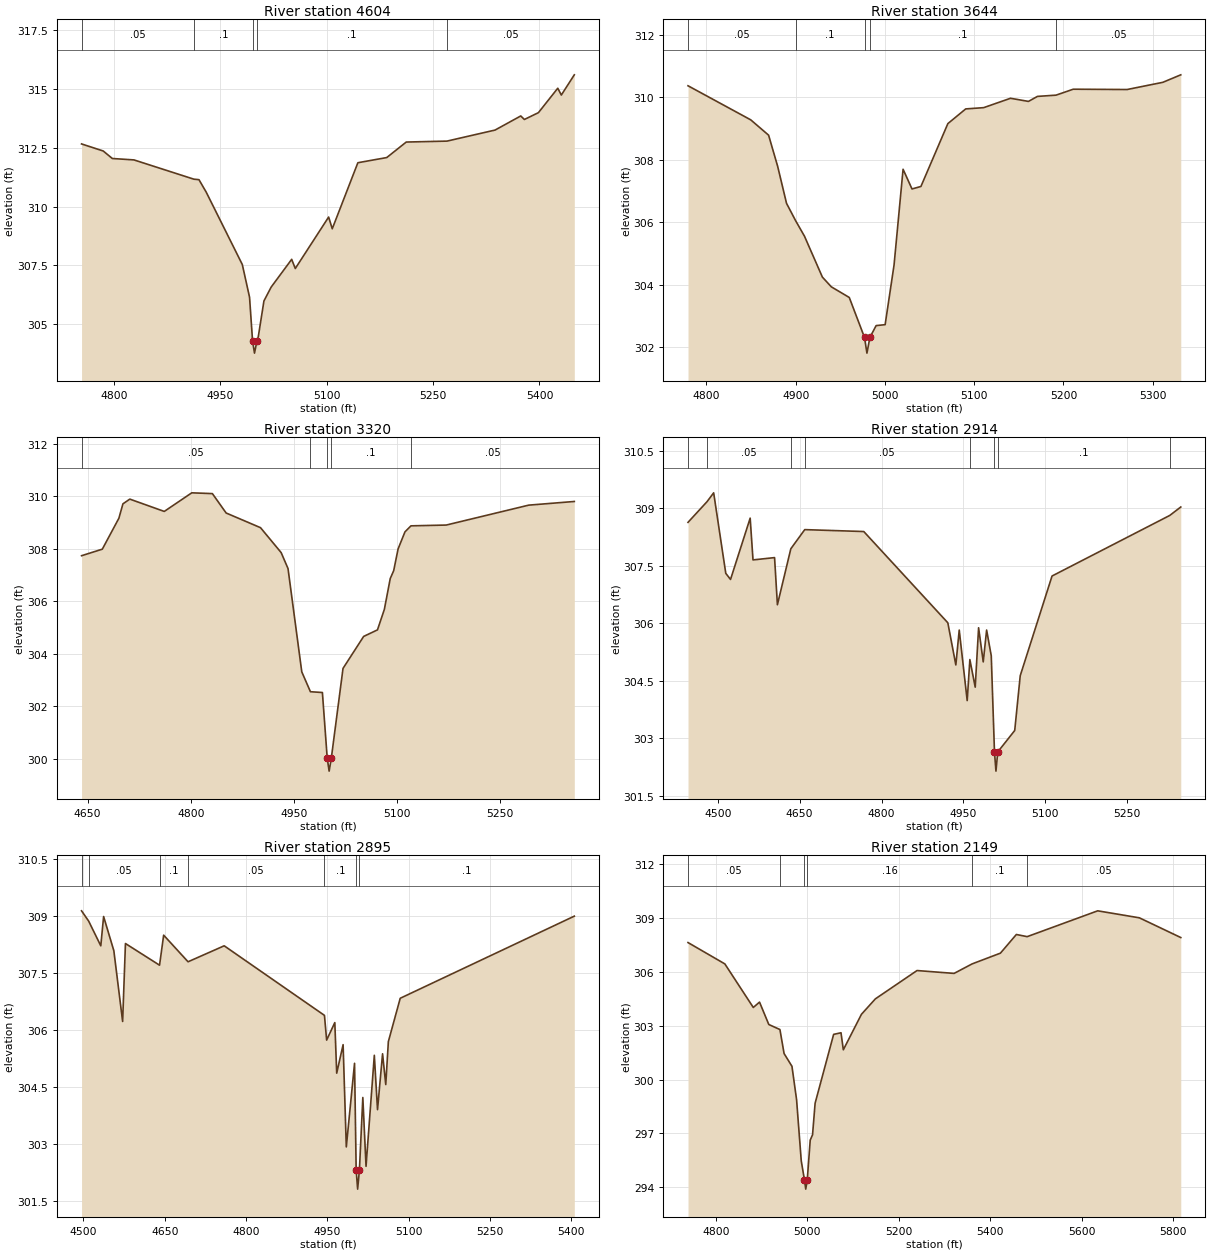
Type RM Length L Ch R = 1 ,4604    ,960,960,960
BEGIN DESCRIPTION:
UNT04952 IN WICK 7.0
END DESCRIPTION:
XS GIS Cut Line= 2
      3572690.94     10265754.23      3572821.14     10265071.95
#Sta/Elev= 30
  4754.5  312.67    4785  312.37  4797.9  312.05  4828.4  311.99  4912.9  311.17
    4920  311.15  4930.2  310.62  4981.1  307.54  4991.3  306.15  4995.6  304.27
  4998.3  303.77  5001.6  304.27  5003.7  304.48  5011.6  305.99  5021.8  306.58
  5050.7  307.76  5055.8  307.37  5102.8  309.56  5107.9  309.06    5144  311.87
  5184.7  312.09  5212.2  312.75  5269.6  312.79  5337.4  313.26  5373.6  313.86
  5378.7  313.71  5398.5     314  5425.8  315.04  5430.8  314.75  5449.1  315.61
#Mann= 5 ,-1 , 0
  4754.5     .05       0  4912.9      .1       0  4995.6     .07       0
  5001.6      .1       0  5269.6     .05       0
Bank Sta=4995.6,5001.6
XS Rating Curve= 0 ,0
Exp/Cntr=0.3,0.1

Type RM Length L Ch R = 1 ,3644    ,324,324,324
BEGIN DESCRIPTION:
UNT04952 IN WICK 6.0
END DESCRIPTION:
XS GIS Cut Line= 2
       3573192.1     10265691.61      3573142.11     10265141.67
#Sta/Elev= 30
  4779.3  310.37  4849.6  309.28  4869.6  308.79  4879.7   307.8  4889.7  306.61
  4899.8  306.06  4909.8  305.56  4929.9  304.25  4939.9  303.94    4960   303.6
  4977.1  302.32  4979.8  301.82  4983.1  302.32  4990.1   302.7  5000.2  302.73
  5010.2  304.64  5020.3   307.7  5030.3  307.07  5040.3  307.15  5070.5  309.16
  5090.5  309.63  5110.6  309.67  5140.7  309.97  5160.8  309.87  5170.9  310.03
  5191.7  310.07    5211  310.26  5271.3  310.25  5311.4  310.48  5331.5  310.72
#Mann= 5 ,-1 , 0
  4779.3     .05       0  4899.8      .1       0  4977.1     .07       0
  4983.1      .1       0  5191.7     .05       0
Bank Sta=4977.1,4983.1
XS Rating Curve= 0 ,0
Exp/Cntr=0.3,0.1

Type RM Length L Ch R = 1 ,3320    ,406,406,406
BEGIN DESCRIPTION:
UNT04952 IN WICK 5.0
END DESCRIPTION:
XS GIS Cut Line= 2
      3573378.44     10265821.86      3573360.49     10265105.39
#Sta/Elev= 30
  4641.1  307.74  4671.3  307.99  4695.4  309.17  4701.3  309.72  4711.3   309.9
  4761.4  309.43  4801.4  310.14  4831.4  310.11  4851.4  309.37  4901.4  308.81
  4931.4  307.86  4941.4  307.25  4961.4  303.31    4974  302.55  4991.4  302.52
  4998.4  300.02  5001.2  299.52  5004.4  300.02  5021.4  303.44  5051.4  304.66
  5071.5  304.91  5081.5  305.69  5090.1  306.87  5095.1  307.17  5101.5     308
  5111.5  308.65  5120.2  308.88  5171.5  308.91  5291.5  309.67  5357.8  309.81
#Mann= 5 ,-1 , 0
  4641.1     .05       0    4974      .1       0  4998.4     .07       0
  5004.4      .1       0  5120.2     .05       0
Bank Sta=4998.4,5004.4
XS Rating Curve= 0 ,0
Exp/Cntr=0.3,0.1

Type RM Length L Ch R = 1 ,2914    ,19,19,19
BEGIN DESCRIPTION:
Mapping XS 81e34cc8
END DESCRIPTION:
XS GIS Cut Line= 6
      3573555.77     10265976.53      3573490.67     10265670.56
      3573493.27     10265585.92       3573572.7      10265450.5
      3573600.05     10265341.13      3573544.48     10265115.64
#Sta/Elev= 30
  4445.4  308.63  4480.3  309.17  4492.4   309.4  4514.6   307.3  4523.3  307.14
  4559.3  308.74  4564.5  307.65    4604  307.71  4609.2  306.48  4633.8  307.94
  4659.3  308.44  4767.5  308.39  4921.5  306.01  4936.2  304.91  4942.4  305.82
    4957  303.98  4961.9  305.05  4971.7  304.33  4977.9  305.88  4986.4  304.99
  4992.6  305.82  5001.1  305.15    5007  302.64  5009.7  302.14    5013  302.64
  5044.1   303.2  5054.2  304.63  5112.5  307.23  5328.2  308.81  5348.4  309.03
#Mann= 8 ,-1 , 0
  4445.4      .1       0  4480.3     .05       0  4633.8      .1       0
  4659.3     .05       0  4961.9      .1       0    5007     .07       0
    5013      .1       0  5328.2     .05       0
Bank Sta=5007,5013
XS Rating Curve= 0 ,0
Exp/Cntr=0.3,0.1

Type RM Length L Ch R = 1 ,2895    ,746,746,746
BEGIN DESCRIPTION:
Mapping XS 8a9adad7
END DESCRIPTION:
XS GIS Cut Line= 6
      3573576.62     10265949.25      3573533.64     10265546.86
      3573622.18     10265408.84       3573631.3     10265302.07
      3573626.09     10265213.52      3573574.01     10265080.72
#Sta/Elev= 30
  4496.5  309.14  4509.6  308.87    4532  308.22  4537.2  308.99  4556.1  308.09
  4572.3  306.23  4577.5  308.28  4640.4  307.71    4648   308.5    4693   307.8
  4759.7  308.22  4944.7  306.39  4948.7  305.74  4963.8   306.2  4967.3  304.87
  4979.1  305.62    4985  302.93  5000.2  305.13  5003.2  302.32  5005.9  301.82
  5009.2  302.32  5015.5  304.23  5021.4  302.42  5036.7  305.34  5042.6  303.91
  5051.9  305.38  5057.8  304.57  5062.6   305.7  5084.5  306.84  5405.7     309
#Mann= 7 ,-1 , 0
  4496.5      .1       0  4509.6     .05       0  4640.4      .1       0
    4693     .05       0  4944.7      .1       0  5003.2     .07       0
  5009.2      .1       0
Bank Sta=5003.2,5009.2
XS Rating Curve= 0 ,0
Exp/Cntr=0.3,0.1

Type RM Length L Ch R = 1 ,2149    ,370,370,370
BEGIN DESCRIPTION:
UNT04952 IN WICK 4.0
END DESCRIPTION:
XS GIS Cut Line= 2
      3573964.43     10265896.04      3574133.65     10264832.31
#Sta/Elev= 30
  4739.3  307.64  4819.8  306.45    4882  304.02  4895.6  304.32  4915.9  303.07
  4940.2  302.79  4949.3  301.45  4966.5  300.74  4976.6  298.88  4986.8  295.47
  4993.9  294.39  4996.6  293.89  4999.9  294.39  5006.4  296.62  5011.5  296.92
  5017.1  298.68  5057.6  302.52  5073.7  302.61  5078.8  301.66  5118.4  303.64
  5148.8   304.5  5239.9  306.08  5320.9  305.92  5360.3  306.45  5422.2  307.05
    5457  308.09  5480.7  307.97  5634.8  309.41  5725.9  309.02  5816.4  307.92
#Mann= 6 ,-1 , 0
  4739.3     .05       0  4940.2     .16       0  4993.9     .07       0
  4999.9     .16       0  5360.3      .1       0  5480.7     .05       0
Bank Sta=4993.9,4999.9
XS Rating Curve= 0 ,0
Exp/Cntr=0.3,0.1

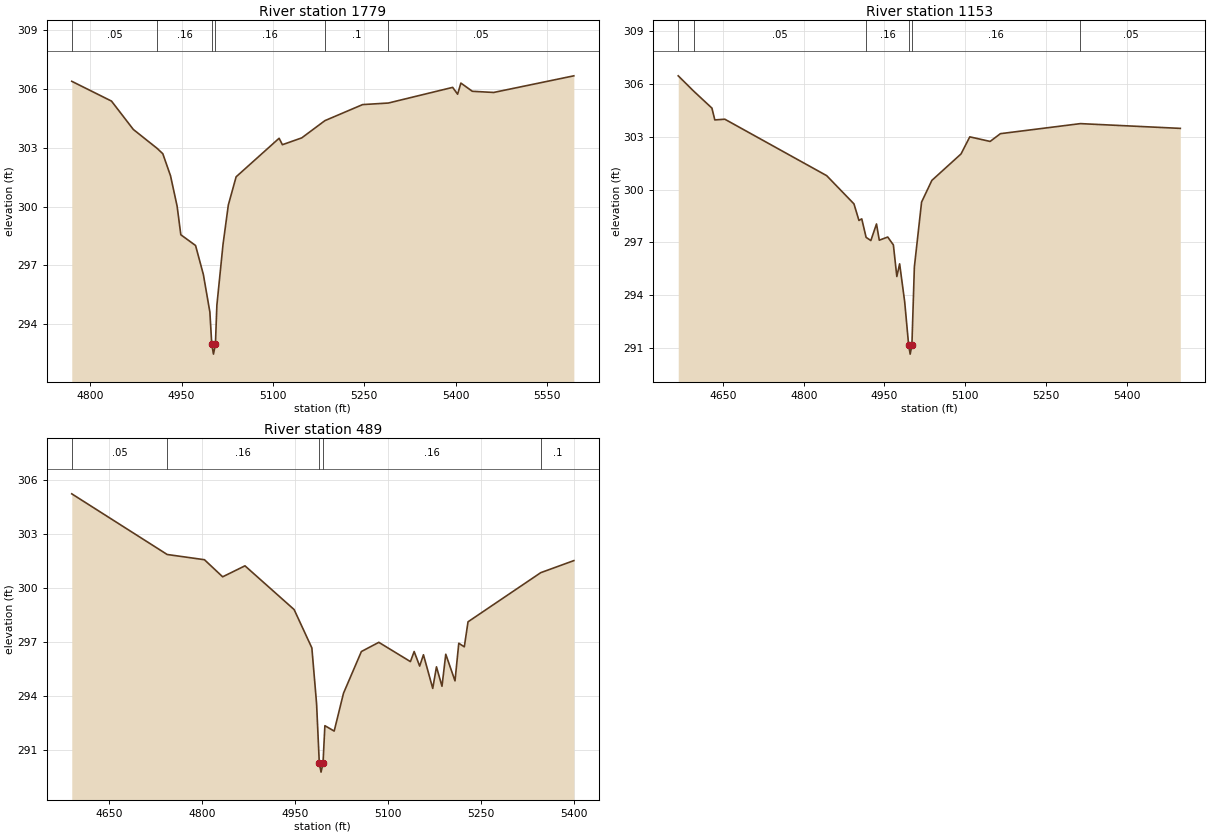
Type RM Length L Ch R = 1 ,1779    ,626,626,626
BEGIN DESCRIPTION:
UNT04952 IN WICK 3.0
END DESCRIPTION:
XS GIS Cut Line= 2
       3574170.1     10265952.15      3574477.21     10265186.98
#Sta/Elev= 30
  4769.6   306.4  4834.8  305.39  4870.7  303.94  4909.9  302.97  4919.1   302.7
  4931.8  301.57  4942.6  300.02  4948.7  298.56  4972.9  298.01  4985.7  296.53
  4996.4  294.61  4999.5  292.96  5002.3  292.46  5005.5  292.96  5007.9  294.96
    5018  298.07  5026.7  300.08  5039.5  301.52  5110.1  303.49  5115.5  303.16
  5147.3  303.51  5185.3  304.39  5247.2  305.21  5289.5  305.29  5395.1  306.09
  5403.2  305.74  5408.6  306.31  5427.4  305.89  5462.4  305.83  5594.1  306.68
#Mann= 6 ,-1 , 0
  4769.6     .05       0  4909.9     .16       0  4999.5     .07       0
  5005.5     .16       0  5185.3      .1       0  5289.5     .05       0
Bank Sta=4999.5,5005.5
XS Rating Curve= 0 ,0
Exp/Cntr=0.3,0.1

Type RM Length L Ch R = 1 ,1153    ,664,664,664
BEGIN DESCRIPTION:
UNT04952 IN WICK 2.0
END DESCRIPTION:
XS GIS Cut Line= 3
      3574442.06     10266091.66      3574654.49      10266004.2
      3574862.83     10265332.28
#Sta/Elev= 30
  4566.8  306.45  4595.9  305.57  4629.4  304.62  4634.8  303.95  4653.4  303.99
  4842.7  300.79  4893.4  299.19  4902.7  298.25  4907.9  298.34    4916  297.29
  4924.8  297.11  4935.3  298.05  4940.5  297.13  4956.2  297.31  4966.7  296.86
  4973.1  295.07  4978.3  295.79  4987.7  293.64  4995.1  291.17  4997.9  290.67
  5001.1  291.17  5005.7  295.61  5019.1  299.29  5038.2  300.52  5092.4  302.02
  5108.7  302.99  5146.5  302.73  5165.6  303.17  5314.3  303.74    5500  303.47
#Mann= 6 ,-1 , 0
  4566.8      .1       0  4595.9     .05       0    4916     .16       0
  4995.1     .07       0  5001.1     .16       0  5314.3     .05       0
Bank Sta=4995.1,5001.1
XS Rating Curve= 0 ,0
Exp/Cntr=0.3,0.1

Type RM Length L Ch R = 1 ,489     ,0,0,0
BEGIN DESCRIPTION:
UNT04952 IN WICK 1.0
END DESCRIPTION:
XS GIS Cut Line= 3
      3574628.43     10266160.45      3574800.32     10266123.99
      3575326.39      10265769.8
#Sta/Elev= 30
  4589.4  305.21  4743.3  301.84  4803.4  301.55  4832.8   300.6  4868.8  301.21
  4948.1  298.78  4976.7  296.65  4984.3  293.56  4988.7  290.25  4991.5  289.75
  4994.7  290.25  4997.7  292.33  5012.7  292.03  5027.7  294.13  5056.6  296.45
  5084.7  296.96  5135.7  295.89  5141.7  296.45  5150.6  295.64  5156.7  296.27
  5171.7   294.4  5177.7   295.6  5186.6  294.52  5192.7   296.3  5207.6  294.82
  5213.7  296.91  5222.6  296.71  5228.6   298.1  5345.9  300.83  5399.3   301.5
#Mann= 5 ,-1 , 0
  4589.4     .05       0  4743.3     .16       0  4988.7     .07       0
  4994.7     .16       0  5345.9      .1       0
Bank Sta=4988.7,4994.7
XS Rating Curve= 0 ,0
Exp/Cntr=0.3,0.1

Chan Stop Cuts=-1
Use User Specified Reach Order=0
Composite Channel Slope=5