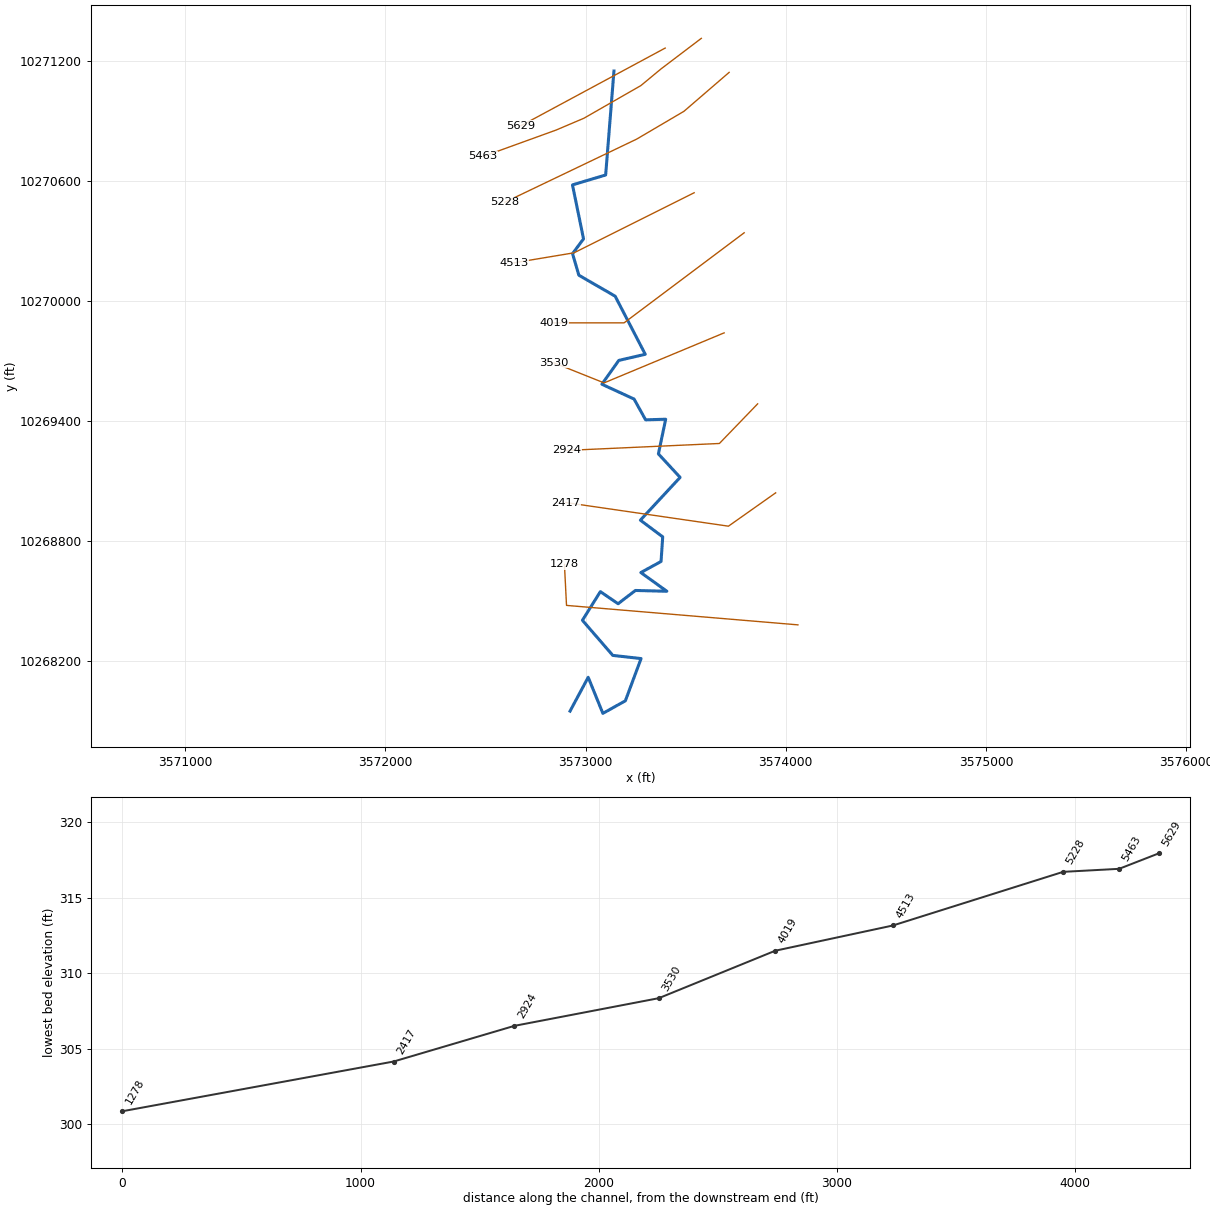
--- BOWMANCRTRIB16.prj (project) ---

Proj Title=BOWMAN CREEK TRIB 16
Current Plan=p01
Default Exp/Contr=0.3,0.1
English Units
Geom File=g01
Flow File=f01
Plan File=p01
Y Axis Title=Elevation
X Axis Title(PF)=Main Channel Distance
X Axis Title(XS)=Station
BEGIN DESCRIPTION:
UNT1484 IN WICK
END DESCRIPTION:
DSS Export Rating Curves= 0
DSS Export Rating Curve Sorted= 0
DSS Export Volume Flow Curves= 0
DXF Filename=UNT1484 IN WICK.
DXF OffsetX= 0
DXF OffsetY= 0
DXF ScaleX= 1
DXF ScaleY= 10

--- BOWMANCRTRIB16.p01 (plan) ---

Plan Title=Multiple Run
Short Identifier=Multiple
Geom File=g01
Flow File=f01
Subcritical Flow
K Sum by GR= 0
Std Step Tol= 0.01
Critical Tol= 0.01
Num of Std Step Trials= 20
Max Error Tol= 0.3
Flow Tol Ratio= 0.001
Split Flow NTrial= 30
Split Flow Tol= 0.02
Split Flow Ratio= 0.02
Log Output Level= 0
Friction Slope Method= 1
Unsteady Friction Slope Method= 2
Unsteady Bridges Friction Slope Method= 1
Parabolic Critical Depth
Global Vel Dist=  1 , 1 , 1
Global Log Level= 0
CheckData=True
Encroach Param= -1, 0, 0, 0
BEGIN DESCRIPTION:
Multiple Run
END DESCRIPTION:

--- BOWMANCRTRIB16.f01 (steady flow) ---

Flow Title=Multiple
Program Version=4.10
Number of Profiles= 7
Profile Names=10-year,25-year,50-year,1pct_min,100-year,1pct_plu,500-year
River Rch & RM=UNT1484 IN WICK,Reach-1         ,5629
     276     353     413     355     480     649     649
River Rch & RM=UNT1484 IN WICK,Reach-1         ,5228
     335     434     511     442     598     808     818
River Rch & RM=BOWMANCRTRIB16,Reach-1         ,5629
     276     353     413     355     480     649     649
River Rch & RM=BOWMANCRTRIB16,Reach-1         ,5228
     335     434     511     442     598     808     818
Boundary for River Rch & Prof#=BOWMANCRTRIB16,Reach-1         , 1
Up Type= 0
Dn Type= 3
Dn Slope=0.005
Boundary for River Rch & Prof#=BOWMANCRTRIB16,Reach-1         , 2
Up Type= 0
Dn Type= 3
Dn Slope=0.005
Boundary for River Rch & Prof#=BOWMANCRTRIB16,Reach-1         , 3
Up Type= 0
Dn Type= 3
Dn Slope=0.005
Boundary for River Rch & Prof#=BOWMANCRTRIB16,Reach-1         , 4
Up Type= 0
Dn Type= 3
Dn Slope=0.005
Boundary for River Rch & Prof#=BOWMANCRTRIB16,Reach-1         , 5
Up Type= 0
Dn Type= 3
Dn Slope=0.005
Boundary for River Rch & Prof#=BOWMANCRTRIB16,Reach-1         , 6
Up Type= 0
Dn Type= 3
Dn Slope=0.005
Boundary for River Rch & Prof#=BOWMANCRTRIB16,Reach-1         , 7
Up Type= 0
Dn Type= 3
Dn Slope=0.005
DSS Import GetInterval= 0
DSS Import GetPeak= 0
DSS Import FillOption= 0

--- BOWMANCRTRIB16.g01 (geometry) ---

Geom Title=Existing Conditions
Program Version=4.10

River Reach=BOWMANCRTRIB16  ,Reach-1
Reach XY= 30
      3573141.49     10271149.81      3573100.02      10270630.4
      3572934.24     10270580.93      3572989.51     10270311.27
      3572934.59     10270237.37      3572966.16     10270129.59
      3573147.58     10270024.78      3573297.97     10269734.52
      3573165.66     10269703.91      3573081.12      10269584.9
      3573241.92     10269510.95      3573299.78     10269406.93
      3573399.98     10269410.16      3573363.63     10269236.89
      3573472.03     10269119.54      3573273.52     10268905.75
      3573385.16     10268822.37       3573376.8     10268699.31
       3573275.9     10268644.03      3573405.67     10268550.51
       3573248.6     10268554.52      3573162.13     10268488.17
      3573073.53     10268548.61      3572983.98     10268405.45
       3573135.7     10268230.05      3573277.05      10268214.2
      3573198.41      10268003.1      3573086.16     10267940.39
      3573012.83      10268120.7      3572922.11     10267951.64

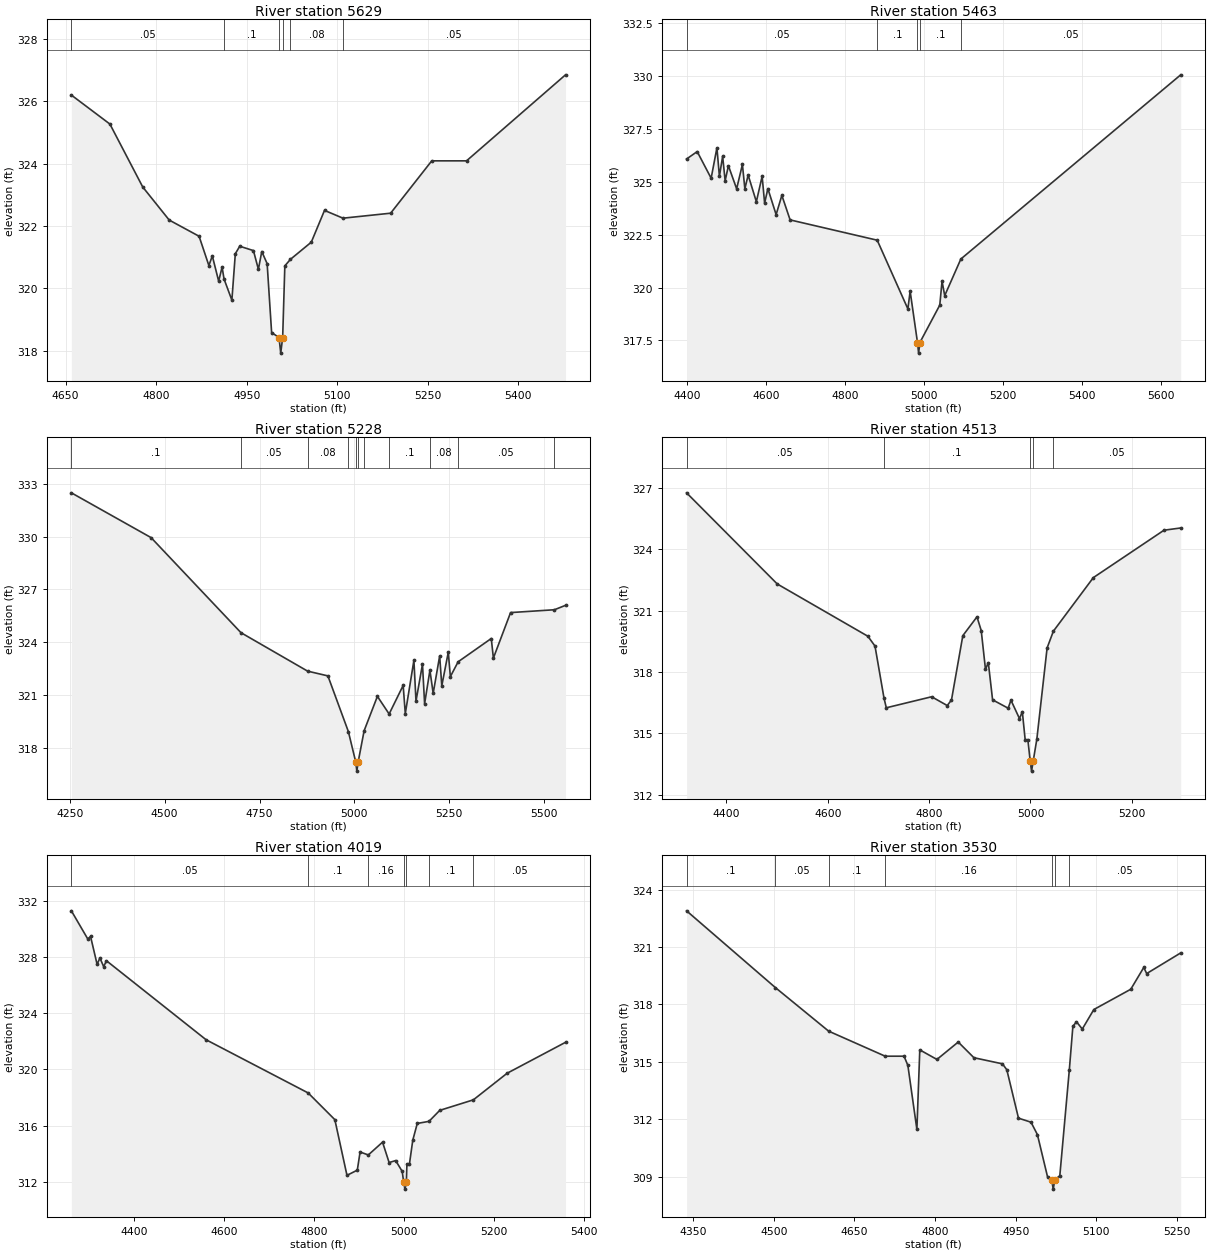
Type RM Length L Ch R = 1 ,5629    ,166,166,166
BEGIN DESCRIPTION:
UNT1484 IN WICK 8.0
END DESCRIPTION:
XS GIS Cut Line= 2
      3573397.56     10271264.63      3572677.07     10270876.67
#Sta/Elev= 30
  4659.7   326.2  4723.5  325.27  4777.9  323.25  4821.7  322.19  4871.2  321.67
  4887.4  320.73  4893.1  321.04  4903.6  320.23  4909.3  320.68  4912.5   320.3
  4925.5  319.62  4931.2  321.11  4938.5  321.35  4961.2  321.21  4969.4  320.61
    4975  321.18  4983.9  320.79  4991.3  318.58  5003.6  318.42  5006.4  317.92
  5009.6  318.42  5013.2  320.72  5022.5  320.93    5057  321.48  5078.9   322.5
  5109.5  322.25  5188.4  322.41  5256.5  324.09  5314.1  324.09    5478  326.85
#Mann= 6 ,-1 , 0
  4659.7     .05       0  4912.5      .1       0  5003.6     .07       0
  5009.6      .1       0  5022.5     .08       0  5109.5     .05       0
Bank Sta=5003.6,5009.6
XS Rating Curve= 0 ,0
Exp/Cntr=0.3,0.1

Type RM Length L Ch R = 1 ,5463    ,235,235,235
BEGIN DESCRIPTION:
Mapping XS 27f307ef
END DESCRIPTION:
XS GIS Cut Line= 6
      3573578.07     10271313.21      3573376.71     10271160.45
      3573276.01     10271077.11      3572991.29     10270913.92
       3572852.4     10270854.89      3572487.79     10270722.94
#Sta/Elev= 30
  4399.2  326.08  4426.1  326.43  4461.4  325.17    4476  326.61  4482.3  325.26
  4490.5  326.21  4496.8  325.05  4505.1  325.76  4525.9  324.67  4540.5  325.82
  4546.7  324.67    4555  325.32  4575.8  324.06  4590.4  325.26  4596.7  323.99
  4604.9  324.68  4625.8  323.45  4640.3  324.36  4661.2   323.2  4881.6  322.24
  4959.2  318.99  4964.9  319.83  4983.5   317.4  4986.3   316.9  4989.5   317.4
  5039.9  319.17  5045.6   320.3  5052.4  319.62  5093.2  321.35  5649.5  330.06
#Mann= 5 ,-1 , 0
  4399.2     .05       0  4881.6      .1       0  4983.5     .07       0
  4989.5      .1       0  5093.2     .05       0
Bank Sta=4983.5,4989.5
XS Rating Curve= 0 ,0
Exp/Cntr=0.3,0.1

Type RM Length L Ch R = 1 ,5228    ,715,715,715
BEGIN DESCRIPTION:
UNT1484 IN WICK 7.0
END DESCRIPTION:
XS GIS Cut Line= 4
        3573717.      10271143.1      3573491.29     10270948.64
      3573255.18     10270809.75       3572596.3     10270494.19
#Sta/Elev= 30
  4254.1  332.48  4464.2  329.94  4701.1  324.55  4876.7  322.37  4930.2   322.1
  4984.2  318.94  5003.8   317.2  5006.5   316.7  5009.8   317.2  5025.7  318.99
  5060.7  320.94  5091.6  319.94  5128.6  321.56  5134.2  319.96  5156.9  322.98
  5162.4  320.67  5179.5  322.76  5185.1  320.52  5199.1  322.42  5207.7  321.11
  5224.8  323.23  5230.4  321.54  5247.5  323.44    5253  322.06  5273.5   322.9
  5360.8  324.22  5366.4  323.11  5411.7  325.69  5527.1  325.85  5556.5   326.1
#Mann= 11 ,-1 , 0
  4254.1      .1       0  4701.1     .05       0  4876.7     .08       0
  4984.2      .1       0  5003.8     .07       0  5009.8      .1       0
  5025.7     .08       0  5091.6      .1       0  5199.1     .08       0
  5273.5     .05       0  5527.1      .1       0
Bank Sta=5003.8,5009.8
XS Rating Curve= 0 ,0
Exp/Cntr=0.3,0.1

Type RM Length L Ch R = 1 ,4513    ,494,494,494
BEGIN DESCRIPTION:
UNT1484 IN WICK 6.0
END DESCRIPTION:
XS GIS Cut Line= 3
      3573542.13     10270541.66      3572942.11     10270241.64
       3572642.1     10270191.64
#Sta/Elev= 30
  4321.4  326.77  4500.3  322.31  4679.2  319.75  4693.2  319.27    4711  316.72
  4715.5  316.25    4805  316.79  4835.7  316.36  4844.1  316.63  4866.5  319.78
  4894.4   320.7  4902.8  320.03  4911.2  318.13  4916.8  318.46  4925.2  316.64
  4955.9  316.23  4961.5  316.62  4978.3  315.72  4983.9  316.06  4989.5  314.69
  4994.8  314.69  4999.4  313.65  5002.1  313.15  5005.4  313.65  5012.5  314.71
  5032.8  319.18  5045.2     320    5124  322.62  5263.4  324.94  5296.4  325.05
#Mann= 5 ,-1 , 0
  4321.4     .05       0    4711      .1       0  4999.4     .07       0
  5005.4      .1       0  5045.2     .05       0
Bank Sta=4999.4,5005.4
XS Rating Curve= 0 ,0
Exp/Cntr=0.3,0.1

Type RM Length L Ch R = 1 ,4019    ,489,489,489
BEGIN DESCRIPTION:
UNT1484 IN WICK 5.0
END DESCRIPTION:
XS GIS Cut Line= 3
       3573792.1     10270341.64      3573192.11     10269891.64
       3572842.1     10269891.64
#Sta/Elev= 30
  4259.6  331.27  4296.1  329.27  4302.3  329.45  4316.9  327.46  4323.1  327.92
  4331.5   327.3  4337.7  327.72  4559.6   322.1  4786.7  318.32  4846.1  316.42
  4873.1  312.46  4896.1  312.83  4902.3  314.12  4920.6  313.91  4952.3  314.82
  4966.9  313.37  4981.5  313.51  4996.1  312.74  4999.3  311.98  5002.1  311.48
  5005.3  311.98  5006.5  313.25  5012.1  313.25  5019.6  314.96  5029.6  316.15
  5055.7   316.3  5079.6  317.08  5154.5  317.83  5229.6  319.72  5359.6  321.92
#Mann= 7 ,-1 , 0
  4259.6     .05       0  4786.7      .1       0  4920.6     .16       0
  4999.3     .07       0  5005.3     .16       0  5055.7      .1       0
  5154.5     .05       0
Bank Sta=4999.3,5005.3
XS Rating Curve= 0 ,0
Exp/Cntr=0.3,0.1

Type RM Length L Ch R = 1 ,3530    ,606,606,606
BEGIN DESCRIPTION:
UNT1484 IN WICK 4.0
END DESCRIPTION:
XS GIS Cut Line= 3
       3573692.1     10269841.64      3573092.11     10269591.64
      3572842.06     10269691.66
#Sta/Elev= 30
  4337.7  322.89  4502.8  318.88    4602   316.6  4707.2  315.29  4742.3  315.29
  4749.4  314.81  4766.2  311.46  4771.6  315.62  4803.5  315.12  4843.1  316.03
  4872.3  315.21  4925.4  314.89  4933.5  314.58  4955.2  312.05  4978.5  311.84
  4990.4  311.19  5009.2  308.99    5017  308.84  5019.8  308.34    5023  308.84
  5032.1  309.04  5049.8  314.58  5056.4  316.85  5063.1  317.09  5073.9  316.71
  5095.4  317.73  5164.1  318.79  5188.3  319.93  5193.7  319.61    5257  320.69
#Mann= 7 ,-1 , 0
  4337.7      .1       0  4502.8     .05       0    4602      .1       0
  4707.2     .16       0    5017     .07       0    5023     .16       0
  5049.8     .05       0
Bank Sta=5017,5023
XS Rating Curve= 0 ,0
Exp/Cntr=0.3,0.1

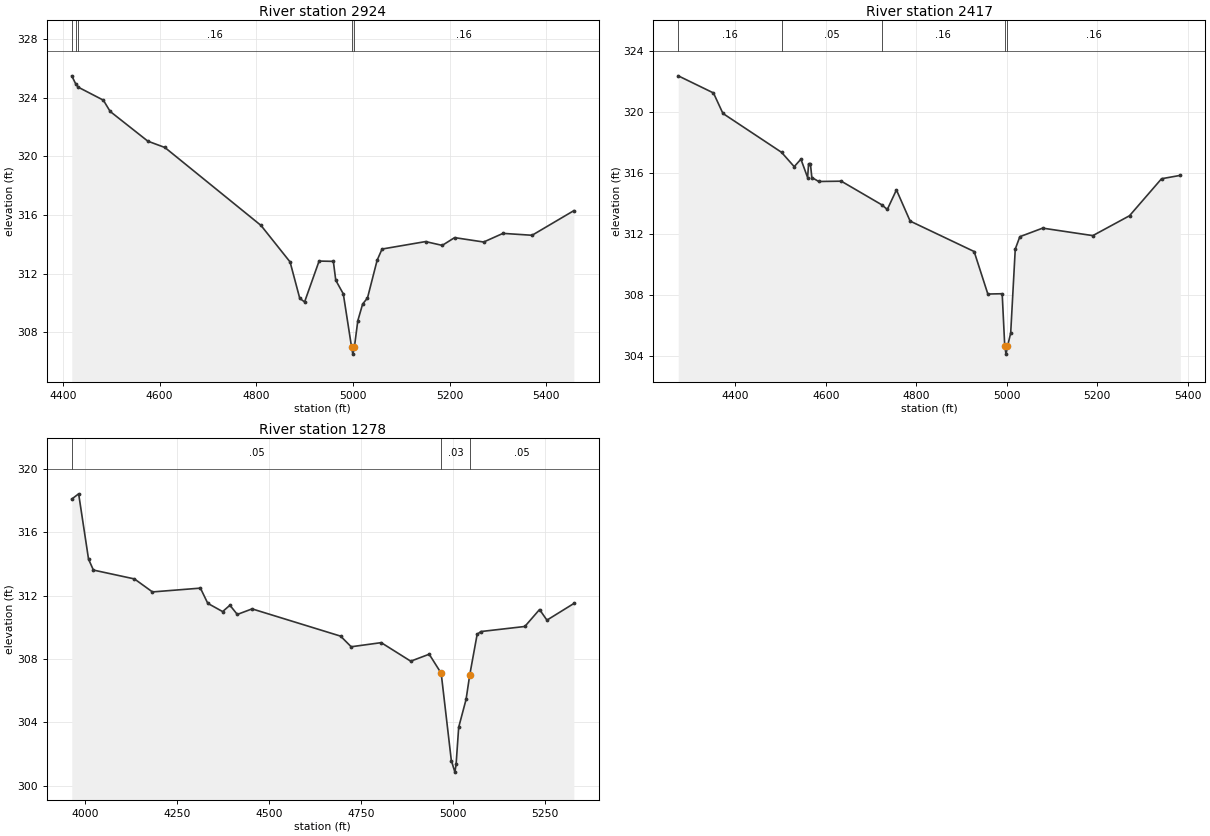
Type RM Length L Ch R = 1 ,2924    ,507,507,507
BEGIN DESCRIPTION:
UNT1484 IN WICK 3.0
END DESCRIPTION:
XS GIS Cut Line= 3
      3573859.33     10269486.82      3573668.37     10269288.92
      3572905.77     10269254.26
#Sta/Elev= 30
  4418.3   325.5  4426.9  324.92    4432  324.72  4483.6  323.84  4497.7  323.07
  4575.7  321.04  4610.9  320.61  4809.7  315.29  4869.8   312.8  4889.8  310.32
  4899.8  310.07  4929.8  312.86  4959.3  312.84  4964.3  311.55  4979.9  310.62
  4996.9  307.01  4999.6  306.51  5002.9  307.01  5009.9  308.79  5019.9  309.93
  5029.9  310.34  5049.9  312.92    5060  313.68    5150  314.19  5184.5  313.93
  5210.1  314.46  5270.2  314.16  5310.2  314.75  5370.3  314.62  5456.7   316.3
#Mann= 5 ,-1 , 0
  4418.3     .05       0  4426.9      .1       0    4432     .16       0
  4996.9     .07       0  5002.9     .16       0
Bank Sta=4996.9,5002.9
XS Rating Curve= 0 ,0
Exp/Cntr=0.3,0.1

Type RM Length L Ch R = 1 ,2417    ,1139,1139,1139
BEGIN DESCRIPTION:
UNT1484 IN WICK 2.0
END DESCRIPTION:
XS GIS Cut Line= 3
      3573949.59     10269042.37      3573713.51     10268875.73
      3572901.01     10268993.78
#Sta/Elev= 30
  4273.8  322.35  4351.7  321.23  4372.6  319.89  4502.1  317.35  4530.2  316.41
    4545   316.9  4559.8   315.7    4562   316.6    4566   316.6  4569.2   315.7
  4584.4  315.44  4634.3  315.46  4724.1  313.91    4736  313.61  4756.2  314.89
  4786.5  312.85    4928  310.86  4958.3  308.08    4990   308.1  4995.7  304.65
  4998.5  304.15  5001.7  304.65  5008.8  305.53  5018.9  311.02    5029  311.83
  5079.5  312.39  5190.4   311.9  5271.5   313.2  5342.3  315.62  5383.8  315.84
#Mann= 5 ,-1 , 0
  4273.8     .16       0  4502.1     .05       0  4724.1     .16       0
  4995.7     .07       0  5001.7     .16       0
Bank Sta=4995.7,5001.7
XS Rating Curve= 0 ,0
Exp/Cntr=0.3,0.1

Type RM Length L Ch R = 1 ,1278    ,0,0,0
BEGIN DESCRIPTION:
UNT1484 IN WICK 1.0
END DESCRIPTION:
XS GIS Cut Line= 3
      3574060.74     10268382.67      3572904.49     10268479.89
      3572894.07     10268684.79
#Sta/Elev= 30
    3964  318.09  3982.7  318.42  4009.6   314.3  4022.8  313.61  4134.5  313.05
  4183.4  312.23  4313.9  312.47  4333.9  311.51  4374.3  310.99  4394.1  311.39
  4414.2  310.81  4454.4  311.16  4695.2  309.44  4723.9  308.77  4805.6  309.03
  4885.9  307.86  4936.1   308.3  4968.7   307.1  4996.3  301.59    5006  300.86
  5009.3  301.36  5016.3  303.69  5036.4  305.45  5046.4     307  5066.5  309.55
  5076.5  309.73  5196.2  310.05  5236.2  311.12  5256.3  310.45  5329.5   311.5
#Mann= 3 , 0 , 0
    3964     .05       0  4968.7     .03       0  5046.4     .05       0
Bank Sta=4968.7,5046.4
XS Rating Curve= 0 ,0
Exp/Cntr=0.3,0.1

Chan Stop Cuts=-1
Use User Specified Reach Order=0
Composite Channel Slope=5