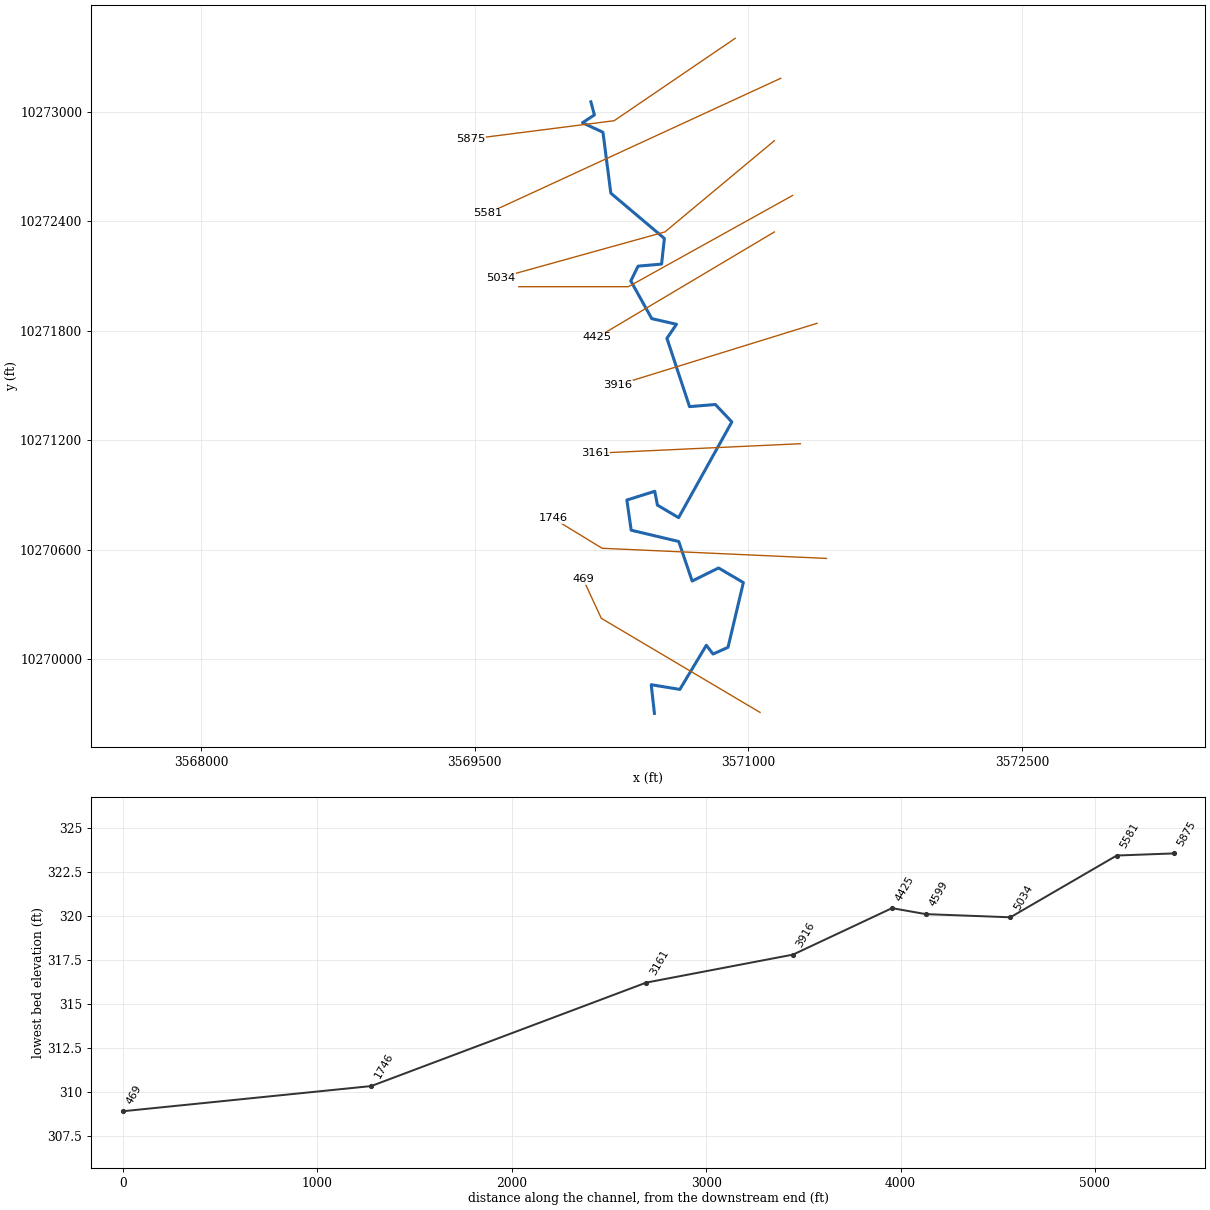
--- BOWMANCRTRIB17.prj (project) ---

Proj Title=BOWMAN CREEK TRIB 17
Current Plan=p01
Default Exp/Contr=0.3,0.1
English Units
Geom File=g01
Flow File=f01
Plan File=p01
Y Axis Title=Elevation
X Axis Title(PF)=Main Channel Distance
X Axis Title(XS)=Station
BEGIN DESCRIPTION:
UNT1483 IN WICK
END DESCRIPTION:
DSS Export Rating Curves= 0
DSS Export Rating Curve Sorted= 0
DSS Export Volume Flow Curves= 0
DXF OffsetX= 0
DXF OffsetY= 0
DXF ScaleX= 1
DXF ScaleY= 10

--- BOWMANCRTRIB17.p01 (plan) ---

Plan Title=Multiple Run
Short Identifier=Multiple
Geom File=g01
Flow File=f01
Subcritical Flow
K Sum by GR= 0
Std Step Tol= 0.01
Critical Tol= 0.01
Num of Std Step Trials= 20
Max Error Tol= 0.3
Flow Tol Ratio= 0.001
Split Flow NTrial= 30
Split Flow Tol= 0.02
Split Flow Ratio= 0.02
Log Output Level= 0
Friction Slope Method= 1
Unsteady Friction Slope Method= 2
Unsteady Bridges Friction Slope Method= 1
Parabolic Critical Depth
Global Vel Dist=  1 , 1 , 1
Global Log Level= 0
CheckData=True
Encroach Param= -1, 0, 0, 0
BEGIN DESCRIPTION:
Multiple Run
END DESCRIPTION:

--- BOWMANCRTRIB17.f01 (steady flow) ---

Flow Title=Multiple
Program Version=4.10
Number of Profiles= 7
Profile Names=10-year,25-year,50-year,1pct_min,100-year,1pct_plu,500-year
River Rch & RM=UNT1483 IN WICK,Reach-1         ,5875
     358     466     551     477     645     873     888
River Rch & RM=BOWMANCRTRIB17,Reach-1         ,5875
     358     466     551     477     645     873     888
Boundary for River Rch & Prof#=BOWMANCRTRIB17,Reach-1         , 1
Up Type= 0
Dn Type= 3
Dn Slope=0.005
Boundary for River Rch & Prof#=BOWMANCRTRIB17,Reach-1         , 2
Up Type= 0
Dn Type= 3
Dn Slope=0.005
Boundary for River Rch & Prof#=BOWMANCRTRIB17,Reach-1         , 3
Up Type= 0
Dn Type= 3
Dn Slope=0.005
Boundary for River Rch & Prof#=BOWMANCRTRIB17,Reach-1         , 4
Up Type= 0
Dn Type= 3
Dn Slope=0.005
Boundary for River Rch & Prof#=BOWMANCRTRIB17,Reach-1         , 5
Up Type= 0
Dn Type= 3
Dn Slope=0.005
Boundary for River Rch & Prof#=BOWMANCRTRIB17,Reach-1         , 6
Up Type= 0
Dn Type= 3
Dn Slope=0.005
Boundary for River Rch & Prof#=BOWMANCRTRIB17,Reach-1         , 7
Up Type= 0
Dn Type= 3
Dn Slope=0.005
DSS Import GetInterval= 0
DSS Import GetPeak= 0
DSS Import FillOption= 0

--- BOWMANCRTRIB17.g01 (geometry) ---

Geom Title=Existing Conditions
Program Version=4.10

River Reach=BOWMANCRTRIB17  ,Reach-1
Reach XY= 30
      3570136.83     10273054.34      3570155.88     10272982.75
      3570090.78     10272939.78      3570202.76      10272887.7
      3570246.01     10272553.98      3570539.37     10272306.13
      3570524.09     10272165.48      3570395.29     10272154.31
      3570355.39     10272073.19      3570470.27     10271866.68
      3570605.72      10271835.7      3570553.28     10271758.75
      3570677.33     10271384.52      3570818.82     10271396.24
       3570909.1     10271300.75      3570617.23     10270776.22
      3570501.26     10270844.97      3570486.67     10270920.66
      3570333.89     10270872.74      3570357.51     10270707.47
      3570617.92     10270645.66      3570691.53     10270428.99
      3570835.98     10270500.52      3570972.09     10270420.66
      3570888.06      10270065.8      3570806.12     10270028.99
      3570769.31     10270076.91      3570624.17     10269835.24
      3570467.23     10269860.94       3570484.8     10269703.88

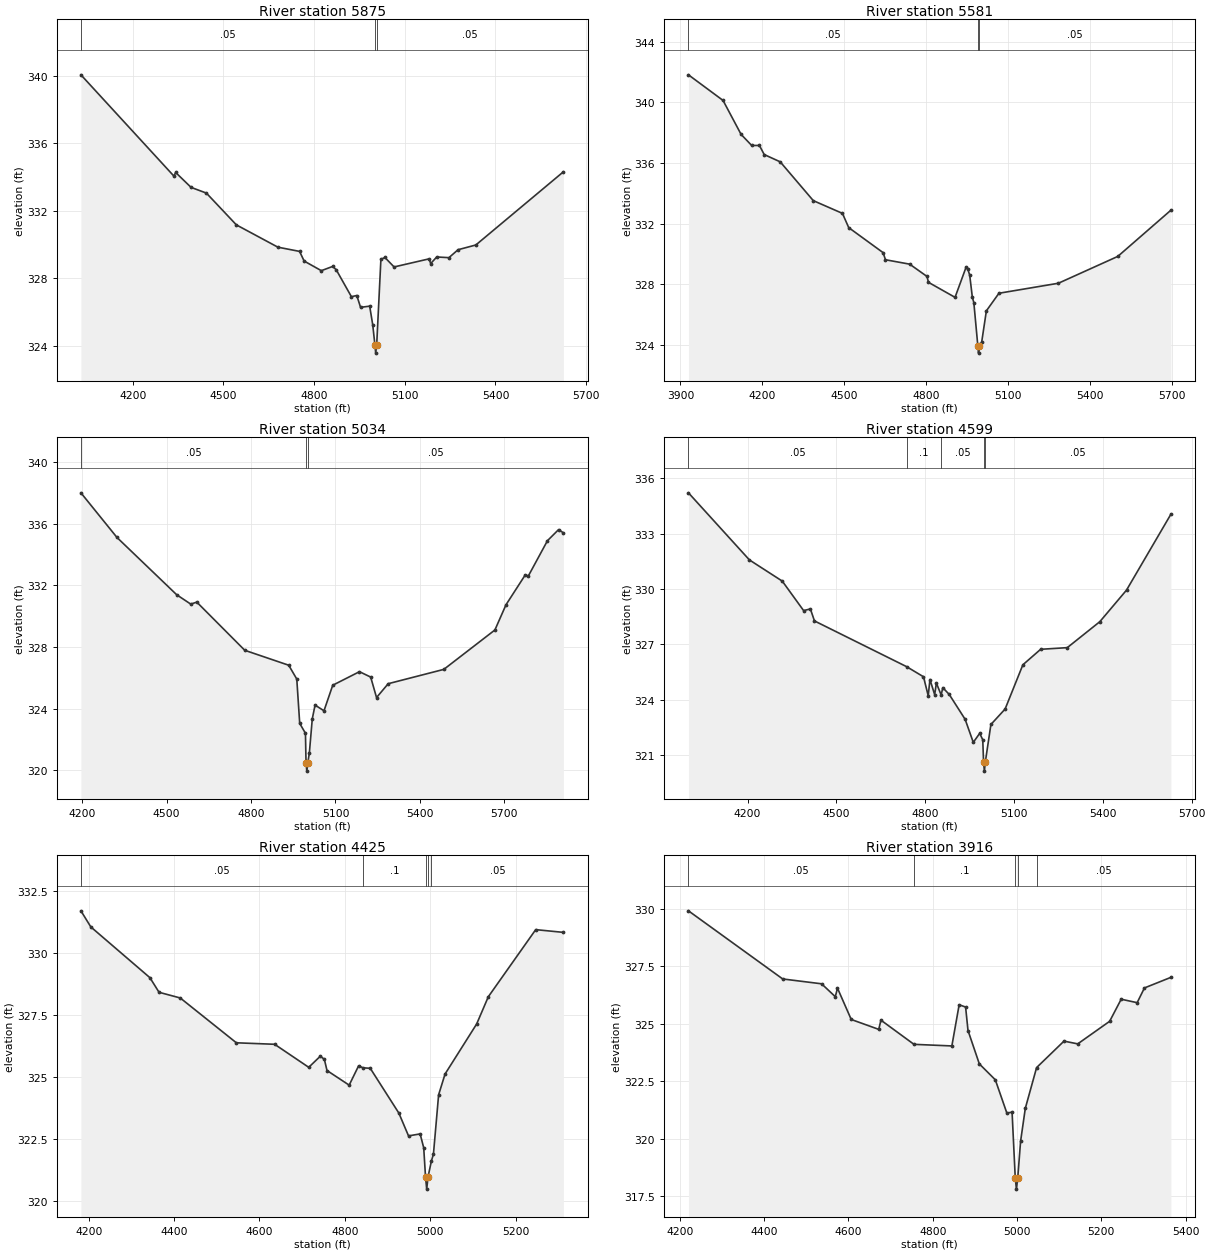
Type RM Length L Ch R = 1 ,5875    ,294,294,294
BEGIN DESCRIPTION:
UNT1483 IN WICK 6.0
END DESCRIPTION:
XS GIS Cut Line= 3
      3570927.24     10273402.38      3570264.03     10272950.98
      3569476.48     10272850.37
#Sta/Elev= 30
  4028.5  340.04    4336  334.05    4342  334.26  4392.9  333.38  4443.7  333.04
  4542.8  331.16  4680.2  329.84    4752  329.59    4767  329.02  4823.9  328.45
  4861.4   328.7    4873  328.51  4923.4  326.91  4941.2  326.98  4953.7  326.28
  4983.9  326.35    4994  325.24  5001.1  324.07  5003.8  323.57  5007.1  324.07
    5021  329.12  5034.3  329.23  5064.6  328.67  5180.6  329.15  5185.6  328.87
  5205.7  329.26    5246  329.22  5276.3  329.69  5335.1  329.97  5624.7   334.3
#Mann= 3 ,-1 , 0
  4028.5     .05       0  5001.1     .03       0  5007.1     .05       0
Bank Sta=5001.1,5007.1
XS Rating Curve= 0 ,0
Exp/Cntr=0.3,0.1

Type RM Length L Ch R = 1 ,5581    ,547,547,547
BEGIN DESCRIPTION:
Mapping XS 1a5874a5
END DESCRIPTION:
XS GIS Cut Line= 2
       3571177.2     10273183.61      3569573.08     10272444.04
#Sta/Elev= 30
  3929.5  341.81  4056.2  340.12  4122.3  337.88    4161  337.15  4189.4  337.15
  4206.9  336.55  4265.5  336.07  4386.6  333.51  4493.3  332.67  4516.3  331.73
  4642.1  330.08  4650.9  329.61  4739.4  329.32  4802.8  328.51  4808.3  328.12
  4905.6  327.13    4946  329.12  4951.5  329.03  4959.2   328.6  4968.9  327.14
  4974.4  326.78  4988.9  323.95  4991.6  323.45  4994.9  323.95  5003.2  324.19
  5020.3  326.24  5066.3   327.4  5283.9  328.06  5501.4  329.83  5695.9  332.88
#Mann= 3 ,-1 , 0
  3929.5     .05       0  4988.9     .03       0  4994.9     .05       0
Bank Sta=4988.9,4994.9
XS Rating Curve= 0 ,0
Exp/Cntr=0.3,0.1

Type RM Length L Ch R = 1 ,5034    ,435,435,435
BEGIN DESCRIPTION:
UNT1483 IN WICK 5.0
END DESCRIPTION:
XS GIS Cut Line= 3
      3571142.11     10272841.64      3570542.11     10272341.64
      3569642.11     10272091.64
#Sta/Elev= 30
  4195.2  338.02  4323.4  335.12  4535.6   331.4  4585.7  330.79  4607.2  330.92
  4777.7  327.79  4933.9  326.82  4962.6  325.92    4973  323.04  4993.4   322.4
  4995.5  320.44  4998.3  319.94  5001.5  320.44  5007.4  321.14  5017.7  323.34
  5027.6  324.23  5059.3  323.86  5090.4  325.52  5185.4   326.4  5225.3  326.05
  5246.1  324.72  5287.6  325.62  5485.3  326.55  5666.9  329.11  5706.4  330.75
  5774.9  332.69  5785.8  332.62  5853.7  334.91  5893.2  335.63  5910.3  335.42
#Mann= 3 ,-1 , 0
  4195.2     .05       0  4995.5     .03       0  5001.5     .05       0
Bank Sta=4995.5,5001.5
XS Rating Curve= 0 ,0
Exp/Cntr=0.3,0.1

Type RM Length L Ch R = 1 ,4599    ,174,174,174
BEGIN DESCRIPTION:
UNT1483 IN WICK 4.0
END DESCRIPTION:
XS GIS Cut Line= 3
      3571242.13     10272541.66      3570342.11     10272041.64
       3569742.1     10272041.64
#Sta/Elev= 30
  4000.3  335.22  4206.2  331.58  4317.2  330.43  4389.3  328.83  4412.2  328.92
  4425.9  328.27    4737  325.79  4794.2  325.24  4810.2  324.21    4816  325.09
    4832  324.27  4837.7   324.9  4853.9  324.25  4859.4  324.65  4881.2  324.28
  4934.9  322.93  4962.4  321.68  4984.1  322.17  4994.4  321.82  4997.1  320.62
  4999.9  320.12  5003.1  320.62  5021.9  322.65  5069.9  323.49  5129.9  325.89
  5189.9  326.73  5279.9  326.82  5389.9  328.23  5479.9  329.94  5629.9  334.06
#Mann= 5 ,-1 , 0
  4000.3     .05       0    4737      .1       0  4853.9     .05       0
  4997.1     .03       0  5003.1     .05       0
Bank Sta=4997.1,5003.1
XS Rating Curve= 0 ,0
Exp/Cntr=0.3,0.1

Type RM Length L Ch R = 1 ,4425    ,509,509,509
BEGIN DESCRIPTION:
UNT1483 IN WICK 3.0
END DESCRIPTION:
XS GIS Cut Line= 2
      3571142.07     10272341.62        3570171.     10271763.76
#Sta/Elev= 30
  4181.8   331.7    4205  331.05  4343.4     329  4364.8  328.41  4414.5  328.18
  4545.9  326.37  4635.5  326.31  4715.4  325.38  4742.6  325.83    4752   325.7
  4758.2  325.25  4810.1  324.66  4832.2  325.44  4842.5  325.36  4859.5  325.34
  4926.5  323.53  4949.1  322.61  4976.3  322.69  4984.7  322.13  4988.9  320.96
  4991.7  320.46  4994.9  320.96  5002.6  321.59  5007.5  321.88  5019.6  324.27
  5034.7  325.11  5108.7  327.13    5136  328.23    5247  330.94  5311.8  330.83
#Mann= 5 ,-1 , 0
  4181.8     .05       0  4842.5      .1       0  4988.9     .07       0
  4994.9      .1       0  5002.6     .05       0
Bank Sta=4988.9,4994.9
XS Rating Curve= 0 ,0
Exp/Cntr=0.3,0.1

Type RM Length L Ch R = 1 ,3916    ,755,755,755
BEGIN DESCRIPTION:
Mapping XS df4b6374
END DESCRIPTION:
XS GIS Cut Line= 2
       3571375.8     10271840.99      3570282.09     10271502.46
#Sta/Elev= 30
  4220.3  329.91    4444  326.95  4536.2  326.74  4568.8  326.18    4574  326.55
  4606.6  325.19  4671.9  324.76  4677.1  325.16  4755.5  324.11  4845.4  324.04
  4862.7  325.83    4878  325.73  4883.7  324.71  4910.6  323.26  4948.5  322.57
  4975.8  321.13  4988.3  321.16  4995.8  318.32  4998.6  317.82  5001.8  318.32
  5008.5   319.9  5019.7  321.33  5046.5   323.1  5111.5  324.25  5144.1  324.13
  5219.8  325.11  5247.2  326.07  5285.1  325.92  5302.4  326.56  5365.2  327.02
#Mann= 5 ,-1 , 0
  4220.3     .05       0  4755.5      .1       0  4995.8     .07       0
  5001.8      .1       0  5046.5     .05       0
Bank Sta=4995.8,5001.8
XS Rating Curve= 0 ,0
Exp/Cntr=0.3,0.1

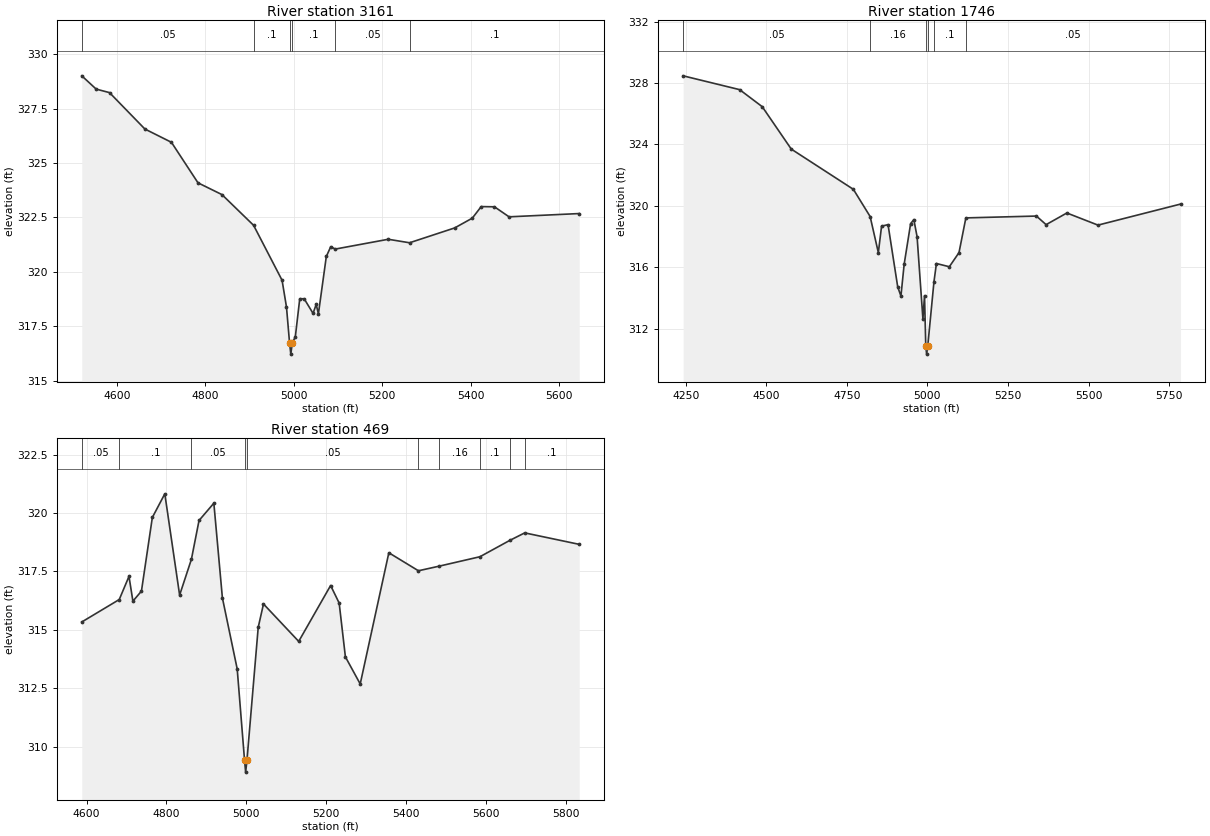
Type RM Length L Ch R = 1 ,3161    ,1415,1415,1415
BEGIN DESCRIPTION:
UNT1483 IN WICK 2.0
END DESCRIPTION:
XS GIS Cut Line= 2
       3571284.7     10271181.28      3570160.61      10271129.2
#Sta/Elev= 30
  4520.4     329    4553  328.39  4583.1  328.23  4663.1  326.56  4723.2  325.95
  4783.3  324.09  4837.5  323.55  4909.1  322.14  4973.5  319.62  4983.5  318.39
  4990.5  316.73  4993.3  316.23  4996.5  316.73  5003.5  317.03  5013.5  318.77
  5023.5  318.77  5043.6   318.1  5050.7  318.51  5055.7  318.08  5073.6  320.71
  5083.6  321.16  5093.8  321.05  5213.7   321.5  5261.9  321.34  5363.9  322.02
  5403.9  322.47    5424     323    5454  322.99    5487  322.53  5645.7  322.68
#Mann= 6 ,-1 , 0
  4520.4     .05       0  4909.1      .1       0  4990.5     .07       0
  4996.5      .1       0  5093.8     .05       0  5261.9      .1       0
Bank Sta=4990.5,4996.5
XS Rating Curve= 0 ,0
Exp/Cntr=0.3,0.1

Type RM Length L Ch R = 1 ,1746    ,1277,1277,1277
BEGIN DESCRIPTION:
Mapping XS 98ae5a7e
END DESCRIPTION:
XS GIS Cut Line= 3
      3571427.32      10270552.9      3570198.17     10270608.46
      3569930.84     10270771.63
#Sta/Elev= 30
    4242  328.47  4417.4  327.57  4487.5  326.46  4577.6   323.7  4770.3  321.08
  4822.3  319.31  4847.8  316.96  4857.8  318.68  4877.9  318.78  4907.9  314.73
  4917.9  314.13  4927.9   316.2  4947.9  318.84  4957.9  319.11    4968     318
  4986.1  312.64  4991.1  314.16    4995  310.85  4997.7  310.35    5001  310.85
  5020.4  315.06    5028  316.25  5068.1  316.04  5098.1  316.96  5119.4  319.22
  5338.3  319.34  5368.4  318.78  5432.8  319.54  5529.4  318.75  5785.6  320.12
#Mann= 6 ,-1 , 0
    4242     .05       0  4822.3     .16       0    4995     .07       0
    5001     .16       0  5020.4      .1       0  5119.4     .05       0
Bank Sta=4995,5001
XS Rating Curve= 0 ,0
Exp/Cntr=0.3,0.1

Type RM Length L Ch R = 1 ,469     ,0,0,0
BEGIN DESCRIPTION:
UNT1483 IN WICK 1.0
END DESCRIPTION:
XS GIS Cut Line= 3
      3571063.51     10269709.16       3570193.7      10270224.8
      3570095.12      10270437.5
#Sta/Elev= 30
  4588.2  315.34    4682   316.3  4706.4  317.29  4716.2  316.23  4737.6  316.66
  4764.9  319.81  4796.1  320.82  4833.2  316.49  4862.7  318.02  4881.8  319.68
  4918.9  320.42  4940.3  316.37  4977.4  313.33  4995.8  309.42  4998.5  308.92
  5001.8  309.42    5030  315.11  5043.2  316.11  5131.4  314.51  5211.3   316.9
  5232.7  316.15  5248.3  313.85  5285.4  312.69  5357.1   318.3  5431.2  317.53
  5483.9  317.73  5585.2  318.13  5660.1  318.83  5697.4  319.15  5833.8  318.66
#Mann= 10 ,-1 , 0
  4588.2     .05       0    4682      .1       0  4862.7     .05       0
  4995.8     .07       0  5001.8     .05       0  5431.2     .05       0
  5483.9     .16       0  5585.2      .1       0  5660.1     .16       0
  5697.4      .1       0
Bank Sta=4995.8,5001.8
XS Rating Curve= 0 ,0
Exp/Cntr=0.3,0.1

Chan Stop Cuts=-1
Use User Specified Reach Order=0
Composite Channel Slope=5