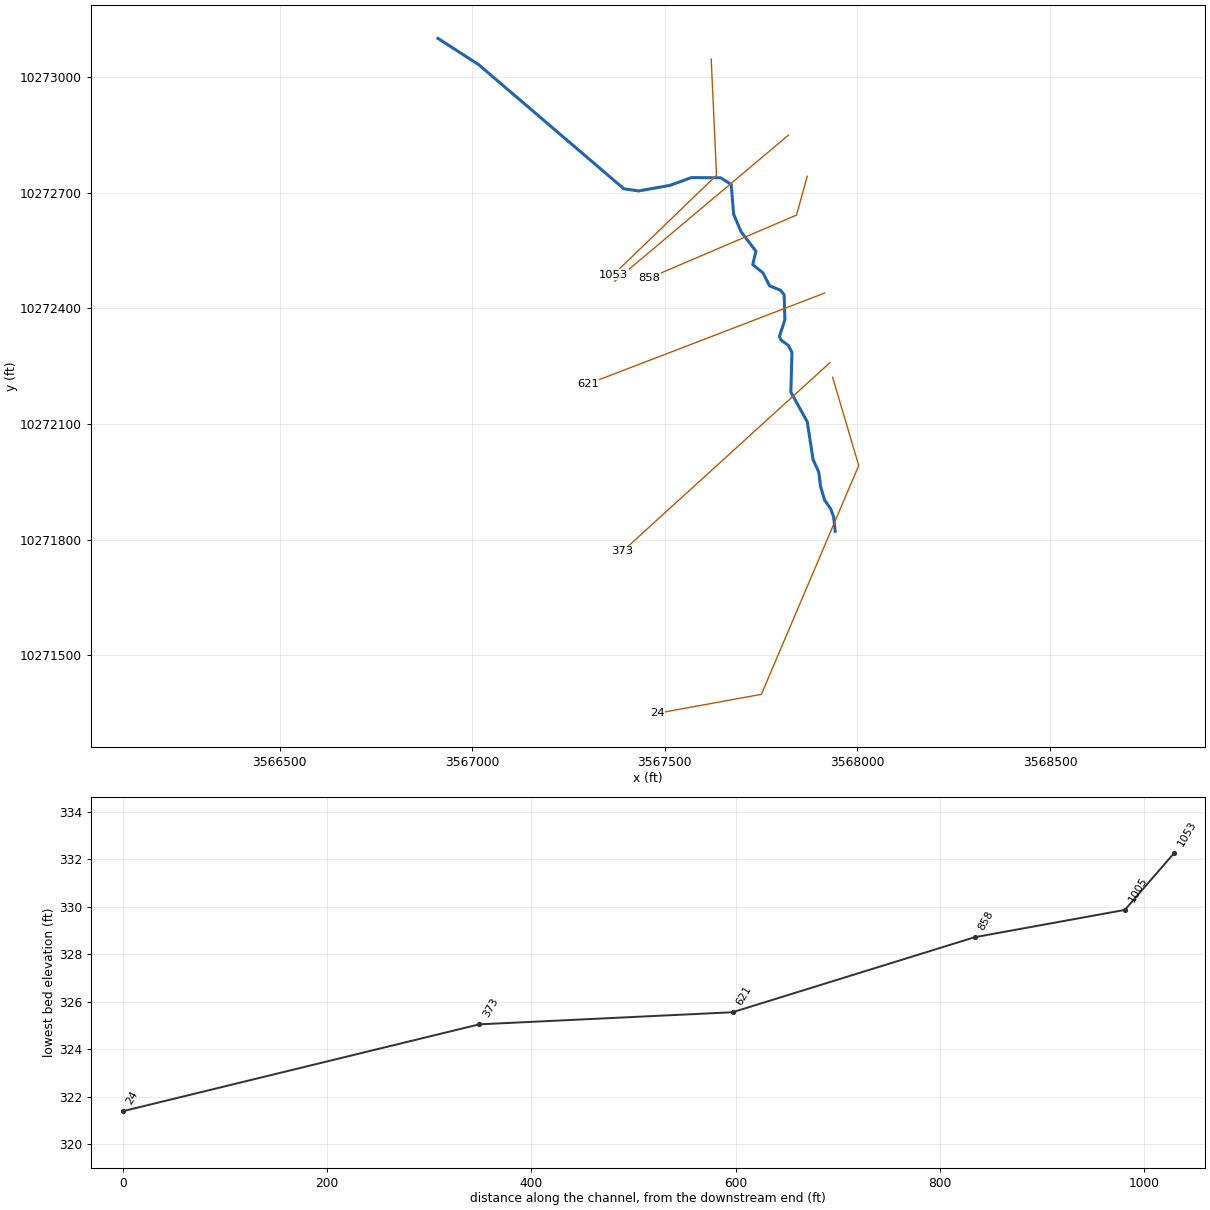
--- BOWMANCRTRIB18.prj (project) ---

Proj Title=BOWMAN CREEK TRIB 18
Current Plan=p01
Default Exp/Contr=0.3,0.1
English Units
Geom File=g01
Flow File=f01
Plan File=p01
Y Axis Title=Elevation
X Axis Title(PF)=Main Channel Distance
X Axis Title(XS)=Station
BEGIN DESCRIPTION:
UNT04949 IN WICK
END DESCRIPTION:
DSS Export Rating Curves= 0
DSS Export Rating Curve Sorted= 0
DSS Export Volume Flow Curves= 0
DXF Filename=UNT04949 IN WICK.
DXF OffsetX= 0
DXF OffsetY= 0
DXF ScaleX= 1
DXF ScaleY= 10

--- BOWMANCRTRIB18.p01 (plan) ---

Plan Title=Multiple Run
Short Identifier=Multiple
Geom File=g01
Flow File=f01
Subcritical Flow
K Sum by GR= 0
Std Step Tol= 0.01
Critical Tol= 0.01
Num of Std Step Trials= 20
Max Error Tol= 0.3
Flow Tol Ratio= 0.001
Split Flow NTrial= 30
Split Flow Tol= 0.02
Split Flow Ratio= 0.02
Log Output Level= 0
Friction Slope Method= 1
Unsteady Friction Slope Method= 2
Unsteady Bridges Friction Slope Method= 1
Parabolic Critical Depth
Global Vel Dist=  1 , 1 , 1
Global Log Level= 0
CheckData=True
Encroach Param= -1, 0, 0, 0
BEGIN DESCRIPTION:
Multiple Run
END DESCRIPTION:

--- BOWMANCRTRIB18.f01 (steady flow) ---

Flow Title=Multiple
Program Version=4.10
Number of Profiles= 7
Profile Names=10-year,25-year,50-year,1pct_min,100-year,1pct_plu,500-year
River Rch & RM=BOWMANCRTRIB18,Reach-1         ,1053
     156     193     221     186     251     340     325
River Rch & RM=BOWMANCRTRIB18,Reach-1         ,24
     488     646     771     675     913    1234    1281
Boundary for River Rch & Prof#=BOWMANCRTRIB18,Reach-1         , 1
Up Type= 0
Dn Type= 3
Dn Slope=0.005
Boundary for River Rch & Prof#=BOWMANCRTRIB18,Reach-1         , 2
Up Type= 0
Dn Type= 3
Dn Slope=0.005
Boundary for River Rch & Prof#=BOWMANCRTRIB18,Reach-1         , 3
Up Type= 0
Dn Type= 3
Dn Slope=0.005
Boundary for River Rch & Prof#=BOWMANCRTRIB18,Reach-1         , 4
Up Type= 0
Dn Type= 3
Dn Slope=0.005
Boundary for River Rch & Prof#=BOWMANCRTRIB18,Reach-1         , 5
Up Type= 0
Dn Type= 3
Dn Slope=0.005
Boundary for River Rch & Prof#=BOWMANCRTRIB18,Reach-1         , 6
Up Type= 0
Dn Type= 3
Dn Slope=0.005
Boundary for River Rch & Prof#=BOWMANCRTRIB18,Reach-1         , 7
Up Type= 0
Dn Type= 3
Dn Slope=0.005
DSS Import GetInterval= 0
DSS Import GetPeak= 0
DSS Import FillOption= 0

--- BOWMANCRTRIB18.g01 (geometry) ---

Geom Title=Existing Conditions
Program Version=4.10

River Reach=BOWMANCRTRIB18  ,Reach-1
Reach XY= 30
        3566911.      10273100.9       3567016.8     10273032.66
      3567393.82     10272710.45      3567432.01     10272704.89
      3567513.91     10272719.44      3567569.08     10272739.52
       3567644.6       10272739.       3567672.2     10272721.82
      3567678.58     10272644.65      3567697.75     10272599.19
      3567736.48      10272548.4      3567728.22      10272513.7
      3567754.87     10272492.07      3567771.86     10272458.62
      3567799.75     10272447.41      3567809.64     10272435.43
      3567811.54     10272370.74      3567797.33     10272327.12
      3567801.67     10272317.75      3567820.43     10272304.09
      3567829.94     10272285.77      3567827.09     10272182.72
      3567869.57     10272106.07      3567884.72     10272007.73
      3567899.43     10271975.53       3567904.2     10271937.51
      3567914.65     10271902.69      3567930.59     10271879.46
      3567938.15     10271858.62      3567942.11     10271821.64

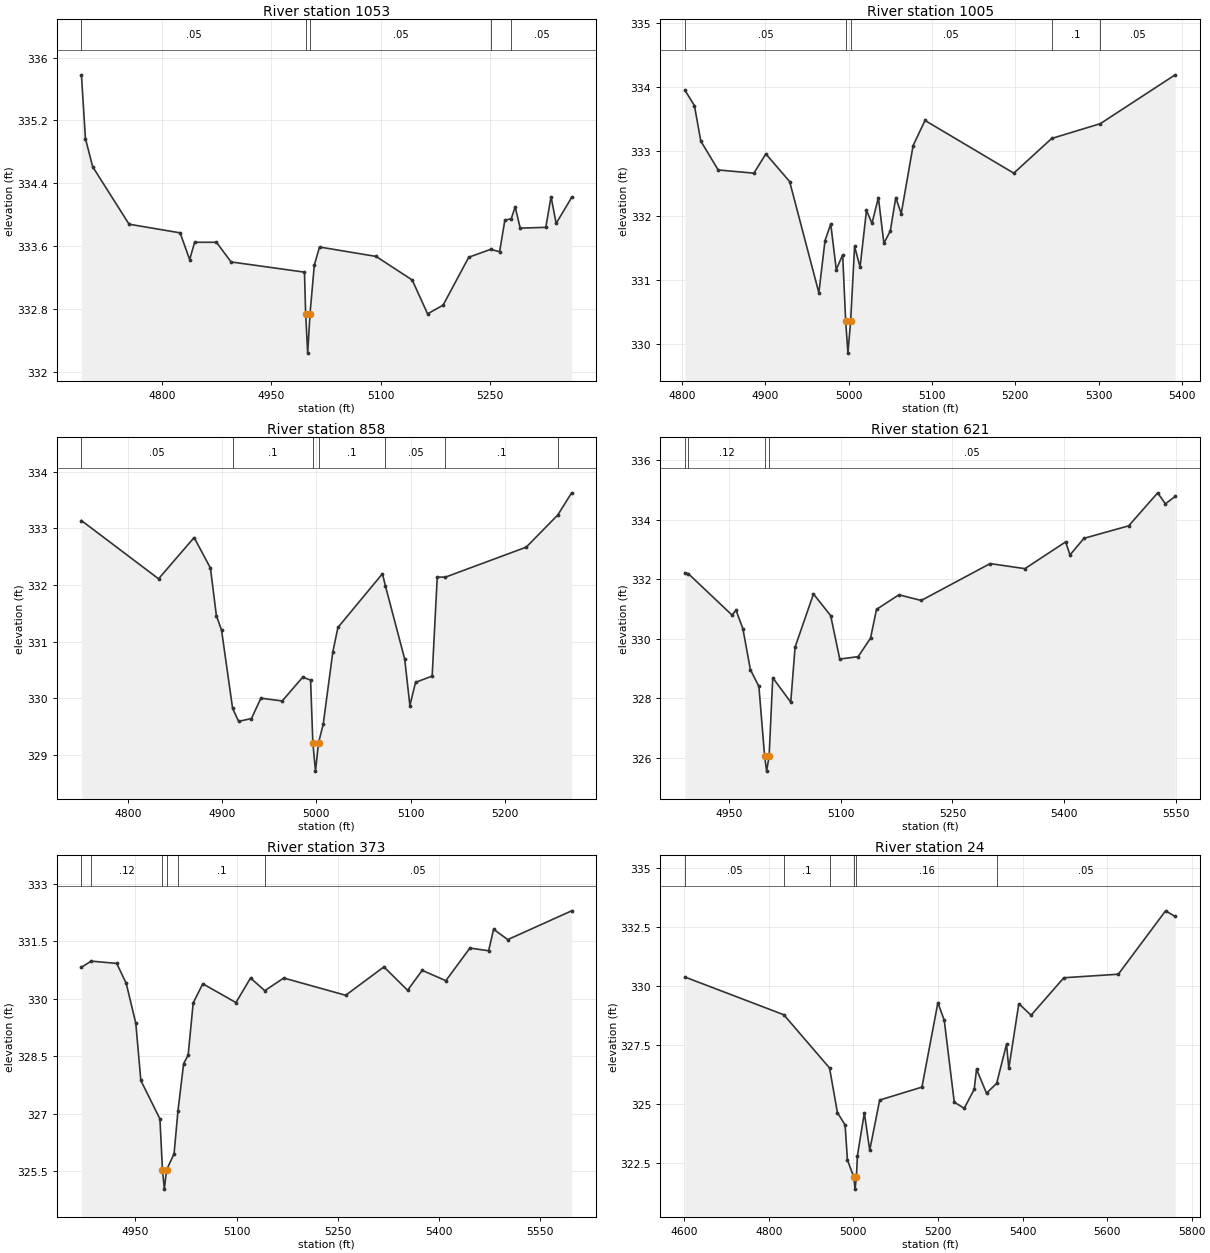
Type RM Length L Ch R = 1 ,1053    ,48,48,48
BEGIN DESCRIPTION:
Mapping XS d15d54cd
END DESCRIPTION:
XS GIS Cut Line= 3
      3567620.34     10273047.09      3567634.23     10272745.73
      3567366.39      10272487.4
#Sta/Elev= 30
  4688.8  335.78  4694.3  334.97  4704.3  334.61  4754.3  333.88  4824.4  333.77
  4837.6  333.43  4844.4  333.65  4874.4  333.65  4894.5   333.4  4995.4  333.27
    4997  332.74  4999.8  332.24    5003  332.74  5008.9  333.36  5016.1  333.59
  5093.8  333.47  5143.5  333.17  5164.6  332.74  5185.9  332.85  5221.2  333.46
  5251.3  333.56  5263.6  333.53  5270.8  333.93  5279.6  333.95    5285   334.1
  5291.9  333.83  5327.1  333.84  5334.3  334.23  5341.3  333.89  5362.6  334.22
#Mann= 5 ,-1 , 0
  4688.8     .05       0    4997     .03       0    5003     .05       0
  5251.3      .1       0  5279.6     .05       0
Bank Sta=4997,5003
XS Rating Curve= 0 ,0
Exp/Cntr=0.3,0.1

Type RM Length L Ch R = 1 ,1005    ,147,147,147
BEGIN DESCRIPTION:
Mapping XS b93262df
END DESCRIPTION:
XS GIS Cut Line= 2
      3567820.83     10272849.62      3567370.33     10272470.65
#Sta/Elev= 30
  4803.3  333.95  4814.7  333.71  4822.3  333.16  4843.2  332.71  4886.1  332.66
  4900.4  332.96    4929  332.53  4964.1   330.8  4971.5  331.61  4978.4  331.87
    4985  331.16  4992.7  331.39  4996.3  330.36    4999  329.86  5002.3  330.36
    5007  331.52  5013.6   331.2  5021.3  332.08  5027.9  331.88  5035.6  332.28
  5042.2  331.57  5049.9  331.76  5056.5  332.28    5063  332.03  5077.3  333.09
  5091.6  333.48  5198.2  332.66  5243.7   333.2  5302.1  333.43    5392  334.19
#Mann= 5 ,-1 , 0
  4803.3     .05       0  4996.3     .03       0  5002.3     .05       0
  5243.7      .1       0  5302.1     .05       0
Bank Sta=4996.3,5002.3
XS Rating Curve= 0 ,0
Exp/Cntr=0.3,0.1

Type RM Length L Ch R = 1 ,858     ,237,237,237
BEGIN DESCRIPTION:
Mapping XS 31cb205d
END DESCRIPTION:
XS GIS Cut Line= 3
       3567869.6     10272742.91      3567841.82      10272642.2
      3567459.89     10272479.01
#Sta/Elev= 30
  4750.9  333.14  4832.7  332.11  4870.4  332.84  4887.7   332.3    4894  331.46
  4899.5   331.2  4911.2  329.82  4917.6  329.59  4931.2  329.64  4941.2     330
  4963.8  329.95  4985.5  330.37  4993.9  330.32  4996.3  329.21  4999.1  328.71
  5002.3  329.21  5007.3  329.54  5017.5  330.82  5022.9  331.25  5070.1   332.2
  5073.3  331.98  5093.7  330.69  5099.2  329.87  5105.2  330.28  5122.8  330.39
  5128.2  332.14  5136.9  332.14  5222.6  332.67  5256.1  333.24  5270.7  333.63
#Mann= 7 ,-1 , 0
  4750.9     .05       0  4911.2      .1       0  4996.3     .07       0
  5002.3      .1       0  5073.3     .05       0  5136.9      .1       0
  5256.1     .05       0
Bank Sta=4996.3,5002.3
XS Rating Curve= 0 ,0
Exp/Cntr=0.3,0.1

Type RM Length L Ch R = 1 ,621     ,248,248,248
BEGIN DESCRIPTION:
Mapping XS 1a344e96
END DESCRIPTION:
XS GIS Cut Line= 2
      3567914.76     10272439.85      3567300.16     10272203.73
#Sta/Elev= 30
  4890.7  332.22  4895.2  332.19  4953.9   330.8  4959.3  330.96  4968.5  330.34
  4978.6  328.96    4990   328.4  4997.7  326.05  5000.4  325.55  5003.7  326.05
  5008.6  328.69  5032.8  327.87  5038.6  329.72  5063.3  331.51  5086.4  330.78
  5098.6  329.32  5123.3   329.4  5139.9  330.02    5148  330.99    5178  331.48
    5208  331.29  5300.6  332.53  5347.3  332.36    5402  333.26  5407.8  332.82
  5426.6  333.38  5486.7   333.8  5525.6  334.91    5536  334.54  5549.1  334.79
#Mann= 4 ,-1 , 0
  4890.7     .05       0  4895.2     .12       0  4997.7     .03       0
  5003.7     .05       0
Bank Sta=4997.7,5003.7
XS Rating Curve= 0 ,0
Exp/Cntr=0.3,0.1

Type RM Length L Ch R = 1 ,373     ,349,349,349
BEGIN DESCRIPTION:
Mapping XS a3ac994d
END DESCRIPTION:
XS GIS Cut Line= 2
      3567928.66     10272259.31      3567390.43      10271769.7
#Sta/Elev= 30
  4869.8  330.82  4884.2  330.98  4922.2  330.92  4936.3   330.4  4950.5  329.36
    4958  327.87  4986.3  326.87  4990.1  325.54  4992.9  325.04  4996.1  325.54
  5007.3  325.96  5013.1  327.08  5021.5  328.31  5028.2  328.53  5035.7  329.89
  5049.9  330.39  5099.2   329.9  5120.8  330.54  5141.9  330.21  5170.1  330.54
    5262  330.09  5318.8  330.83  5353.9  330.22  5375.6  330.74  5410.7  330.47
  5446.4  331.32  5474.2  331.25  5481.6  331.81  5502.6  331.54  5597.4  332.29
#Mann= 6 ,-1 , 0
  4869.8     .05       0  4884.2     .12       0  4990.1     .07       0
  4996.1     .12       0  5013.1      .1       0  5141.9     .05       0
Bank Sta=4990.1,4996.1
XS Rating Curve= 0 ,0
Exp/Cntr=0.3,0.1

Type RM Length L Ch R = 1 ,24      ,0,0,0
BEGIN DESCRIPTION:
UNT04949 IN WICK 1.0
END DESCRIPTION:
XS GIS Cut Line= 4
      3567935.51     10272221.38      3568003.21     10271992.23
      3567750.61     10271398.48      3567479.78       10271349.
#Sta/Elev= 30
  4601.5  330.38  4835.3  328.78  4943.5  326.52  4962.1  324.63  4980.3   324.1
  4985.8  322.62    5001  321.88  5003.7  321.38    5007  321.88  5009.4  322.79
  5025.8  324.62  5038.5  323.03  5062.1  325.16  5162.1  325.71  5199.7  329.29
  5214.8  328.55  5238.5  325.07  5262.1  324.81  5285.7  325.62  5291.2  326.47
  5314.8  325.45  5338.8  325.87  5362.1  327.53  5367.5   326.5  5391.2  329.25
  5420.2  328.76  5497.7  330.35  5626.5   330.5  5738.3  333.19    5761  332.95
#Mann= 6 ,-1 , 0
  4601.5     .05       0  4835.3      .1       0  4943.5     .16       0
    5001     .07       0    5007     .16       0  5338.8     .05       0
Bank Sta=5001,5007
XS Rating Curve= 0 ,0
Exp/Cntr=0.3,0.1

Chan Stop Cuts=-1
Use User Specified Reach Order=0
Composite Channel Slope=5