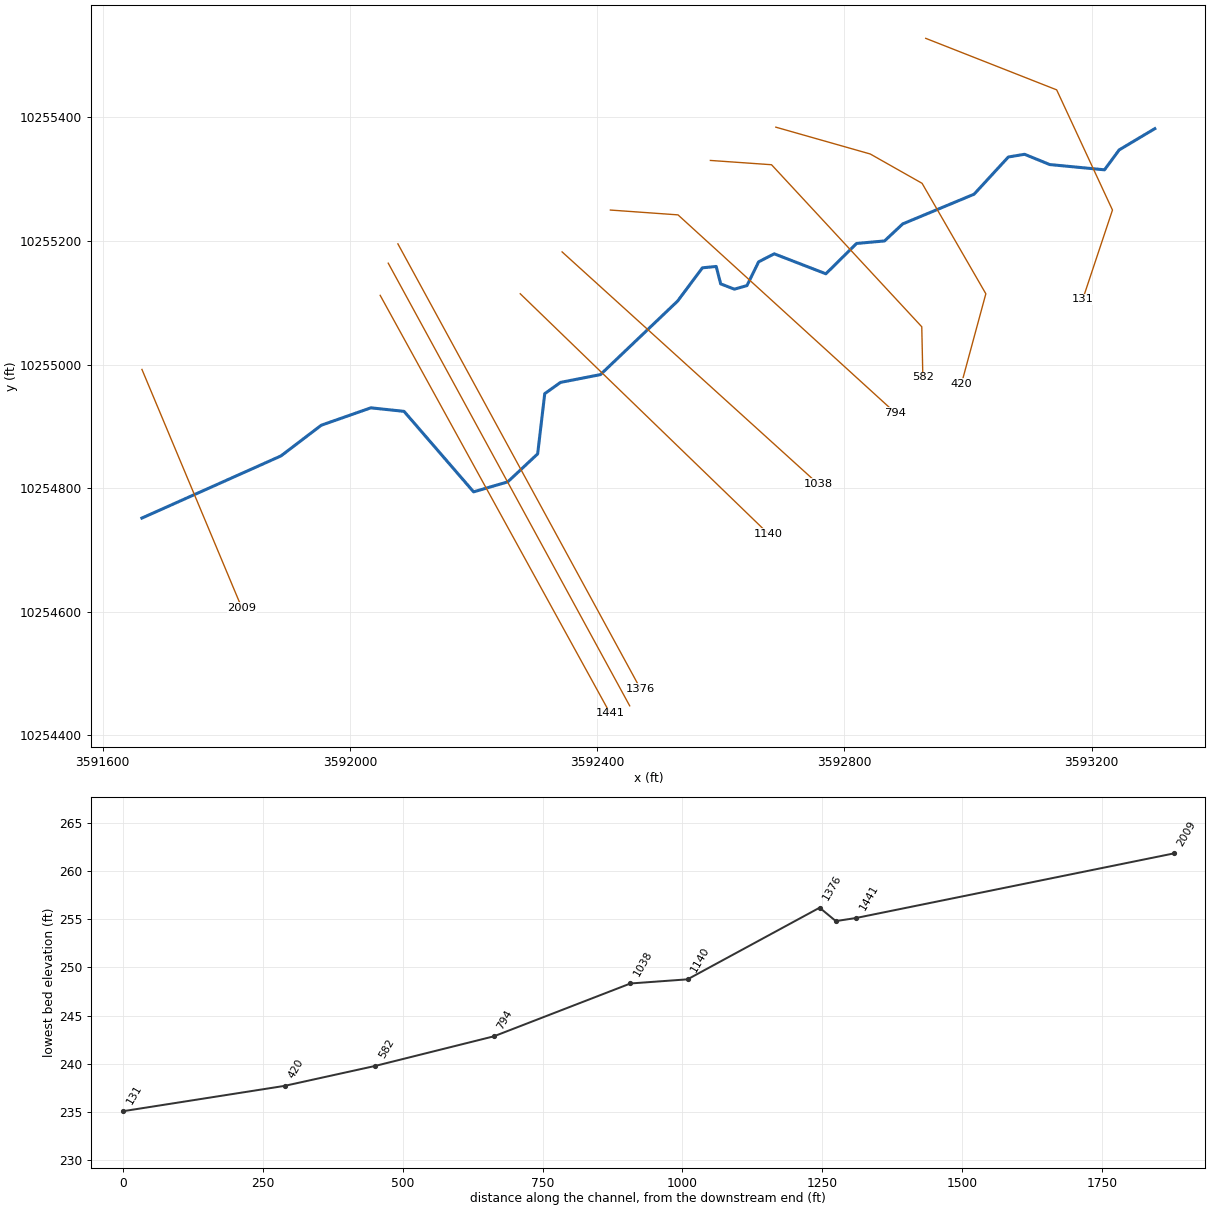
--- BOWMANCRTRIB21.prj (project) ---

Proj Title=BOWMAN CREEK TRIB 2 1
Current Plan=p01
Default Exp/Contr=0.3,0.1
English Units
Geom File=g01
Flow File=f01
Plan File=p01
Y Axis Title=Elevation
X Axis Title(PF)=Main Channel Distance
X Axis Title(XS)=Station
BEGIN DESCRIPTION:
UNT04977 IN WICK
END DESCRIPTION:
DSS Export Rating Curves= 0
DSS Export Rating Curve Sorted= 0
DSS Export Volume Flow Curves= 0
DXF Filename=UNT04977 IN WICK.
DXF OffsetX= 0
DXF OffsetY= 0
DXF ScaleX= 1
DXF ScaleY= 10

--- BOWMANCRTRIB21.p01 (plan) ---

Plan Title=Multiple Run
Short Identifier=Multiple
Geom File=g01
Flow File=f01
Subcritical Flow
K Sum by GR= 0
Std Step Tol= 0.01
Critical Tol= 0.01
Num of Std Step Trials= 20
Max Error Tol= 0.3
Flow Tol Ratio= 0.001
Split Flow NTrial= 30
Split Flow Tol= 0.02
Split Flow Ratio= 0.02
Log Output Level= 0
Friction Slope Method= 1
Unsteady Friction Slope Method= 2
Unsteady Bridges Friction Slope Method= 1
Parabolic Critical Depth
Global Vel Dist=  1 , 1 , 1
Global Log Level= 0
CheckData=True
Encroach Param= -1, 0, 0, 0
BEGIN DESCRIPTION:
Multiple Run
END DESCRIPTION:

--- BOWMANCRTRIB21.f01 (steady flow) ---

Flow Title=Multiple
Program Version=4.10
Number of Profiles= 7
Profile Names=10-year,25-year,50-year,1pct_min,100-year,1pct_plu,500-year
River Rch & RM=UNT04977 IN WICK,Reach-1         ,2009
     140     173     197     166     225     304     291
River Rch & RM=BOWMANCRTRIB21,Reach-1         ,2009
     140     173     197     166     225     304     291
Boundary for River Rch & Prof#=BOWMANCRTRIB21,Reach-1         , 1
Up Type= 0
Dn Type= 3
Dn Slope=0.005
Boundary for River Rch & Prof#=BOWMANCRTRIB21,Reach-1         , 2
Up Type= 0
Dn Type= 3
Dn Slope=0.005
Boundary for River Rch & Prof#=BOWMANCRTRIB21,Reach-1         , 3
Up Type= 0
Dn Type= 3
Dn Slope=0.005
Boundary for River Rch & Prof#=BOWMANCRTRIB21,Reach-1         , 4
Up Type= 0
Dn Type= 3
Dn Slope=0.005
Boundary for River Rch & Prof#=BOWMANCRTRIB21,Reach-1         , 5
Up Type= 0
Dn Type= 3
Dn Slope=0.005
Boundary for River Rch & Prof#=BOWMANCRTRIB21,Reach-1         , 6
Up Type= 0
Dn Type= 3
Dn Slope=0.005
Boundary for River Rch & Prof#=BOWMANCRTRIB21,Reach-1         , 7
Up Type= 0
Dn Type= 3
Dn Slope=0.005
DSS Import GetInterval= 0
DSS Import GetPeak= 0
DSS Import FillOption= 0

--- BOWMANCRTRIB21.g01 (geometry) ---

Geom Title=Existing Conditions
Program Version=4.10

River Reach=BOWMANCRTRIB21  ,Reach-1
Reach XY= 30
      3591663.48     10254751.62      3591888.54     10254852.21
      3591953.72     10254901.86      3592033.93     10254929.98
      3592087.58     10254924.26      3592200.08     10254794.05
      3592255.29     10254810.19      3592303.72     10254855.51
      3592315.18      10254952.9       3592340.7     10254971.13
      3592405.37     10254983.75      3592530.15     10255102.72
      3592570.25     10255156.49      3592592.54     10255158.69
       3592599.8      10255130.5      3592621.97     10255121.95
       3592642.3     10255127.74      3592661.19     10255166.16
      3592686.45     10255179.13      3592769.97     10255146.82
      3592819.64     10255195.89      3592864.86     10255199.96
      3592894.31     10255227.52      3593009.71     10255275.54
      3593065.16     10255335.77      3593091.41     10255340.13
      3593132.12     10255323.54      3593220.73     10255315.02
      3593244.41     10255347.19      3593302.11     10255381.64

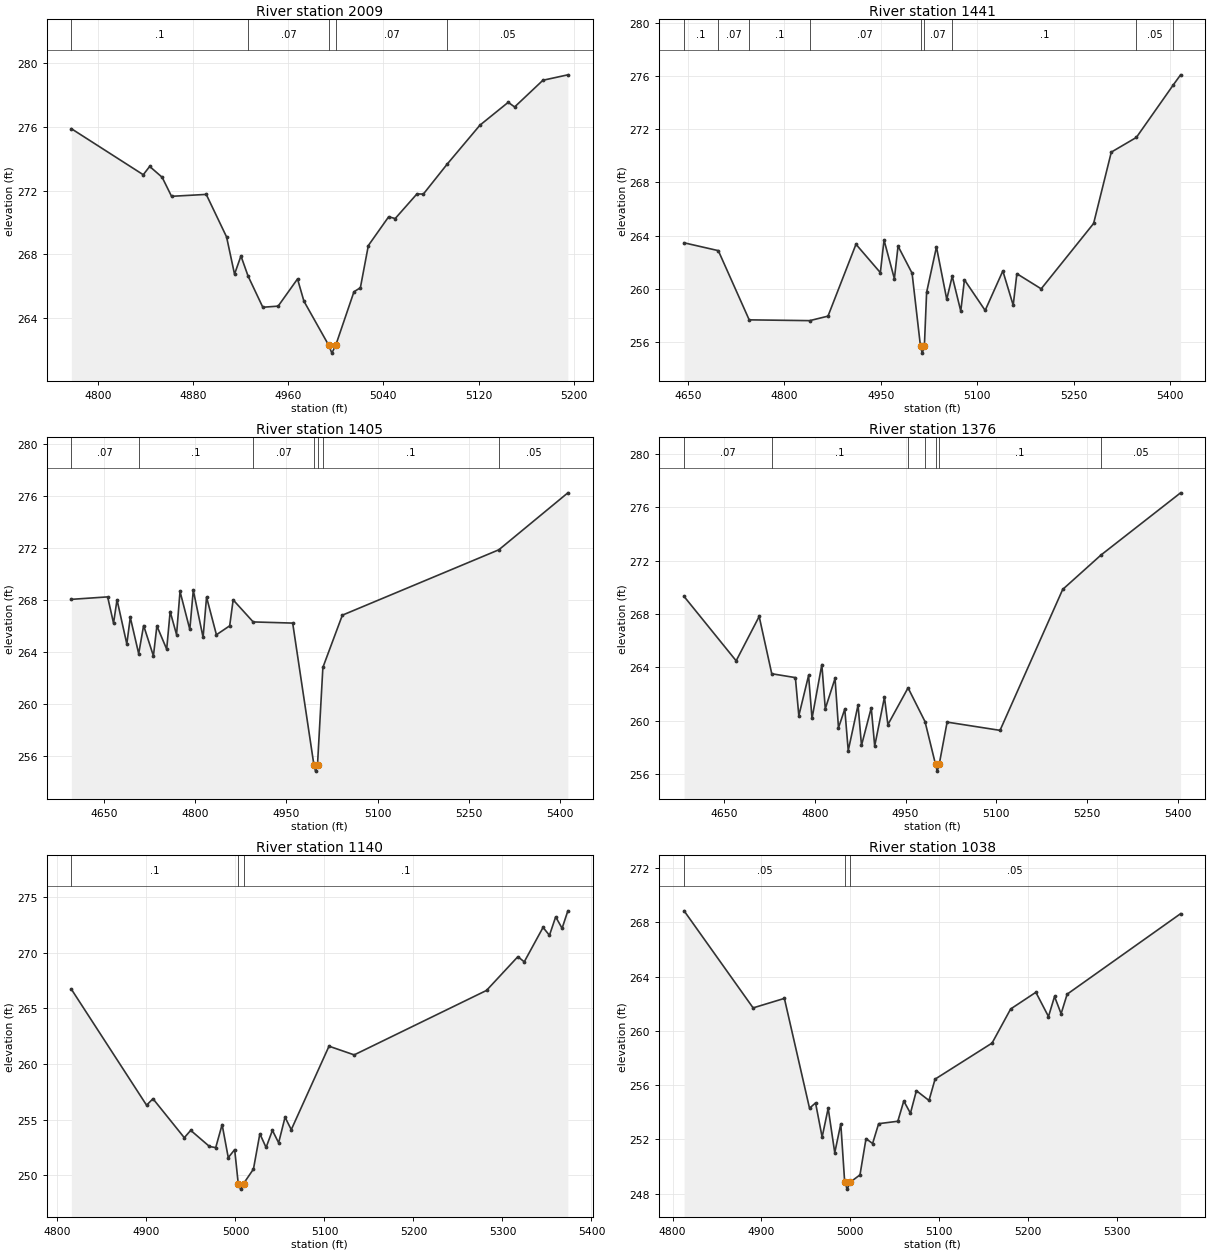
Type RM Length L Ch R = 1 ,2009    ,568,568,568
BEGIN DESCRIPTION:
UNT04977 IN WICK 4.0
END DESCRIPTION:
XS GIS Cut Line= 2
      3591663.58      10254992.1      3591825.01     10254606.75
#Sta/Elev= 30
  4777.4  275.87  4837.9  272.99  4843.3  273.51  4853.8  272.83  4861.7  271.64
  4890.9  271.76    4908   269.1  4914.7  266.77  4920.1  267.91  4926.1  266.65
  4938.5   264.7  4951.4  264.77  4967.7  266.47  4973.1  265.08  4993.9  262.33
  4996.6  261.83  4999.9  262.33  5015.2  265.67  5020.6  265.92  5027.3  268.56
  5044.4  270.36  5049.9  270.25  5068.2  271.79  5073.6  271.78  5093.6  273.65
  5121.2  276.09    5145  277.52  5150.4  277.23  5174.2   278.9  5195.2  279.24
#Mann= 5 ,-1 , 0
  4777.4      .1       0  4926.1     .07       0  4993.9     .07       0
  4999.9     .07       0  5093.6     .05       0
Bank Sta=4993.9,4999.9
XS Rating Curve= 0 ,0
Exp/Cntr=0.3,0.1

Type RM Length L Ch R = 1 ,1441    ,36,36,36
BEGIN DESCRIPTION:
UNT04977 IN WICK 3.0
END DESCRIPTION:
XS GIS Cut Line= 2
      3592048.96     10255111.96      3592420.91      10254435.7
#Sta/Elev= 30
    4644  263.45  4697.2  262.86  4745.2  257.64  4839.3  257.58  4867.7  257.92
  4911.2  263.34  4949.1   261.2  4954.8  263.66  4970.9  260.74  4976.6   263.2
  4998.4  261.16  5011.5  255.63  5014.2  255.13  5017.5  255.63    5021  259.71
  5036.3  263.14  5052.3  259.19  5060.8  260.93  5074.1   258.3  5079.8  260.66
    5112  258.35  5139.5  261.33  5155.6  258.74  5161.3  261.12  5199.1  259.98
  5280.6  264.91  5308.1  270.29  5347.1   271.4  5404.6  275.37  5415.8  276.12
#Mann= 9 ,-1 , 0
    4644      .1       0  4697.2     .07       0  4745.2      .1       0
  4839.3     .07       0  5011.5     .07       0  5017.5     .07       0
  5060.8      .1       0  5347.1     .05       0  5404.6      .1       0
Bank Sta=5011.5,5017.5
XS Rating Curve= 0 ,0
Exp/Cntr=0.3,0.1

Type RM Length L Ch R = 1 ,1405    ,29,29,29
BEGIN DESCRIPTION:
Mapping XS c6631c06
END DESCRIPTION:
XS GIS Cut Line= 2
      3592062.01       10255164.      3592452.61      10254447.9
#Sta/Elev= 30
  4596.9  268.05  4656.5  268.24  4666.2  266.21  4671.9  268.02    4688  264.61
  4693.7  266.66  4707.5  263.86  4715.6  266.03  4731.7  263.69  4737.4     266
  4753.5  264.21  4759.2  267.11  4769.7  265.33  4775.4  268.66  4791.5  265.73
  4797.2  268.75  4813.3  265.12    4819  268.22  4835.2  265.32    4857  266.01
  4862.7  268.01  4895.6  266.31  4960.5  266.22  4995.3  255.31    4998  254.81
  5001.3  255.31  5010.1   262.8  5042.1  266.83  5299.2  271.87  5412.6  276.26
#Mann= 7 ,-1 , 0
  4596.9     .07       0  4707.5      .1       0  4895.6     .07       0
  4995.3     .07       0  5001.3     .07       0  5010.1      .1       0
  5299.2     .05       0
Bank Sta=4995.3,5001.3
XS Rating Curve= 0 ,0
Exp/Cntr=0.3,0.1

Type RM Length L Ch R = 1 ,1376    ,236,236,236
BEGIN DESCRIPTION:
Mapping XS f33ab422
END DESCRIPTION:
XS GIS Cut Line= 2
      3592077.63     10255195.25      3592470.11     10254475.28
#Sta/Elev= 30
  4584.2  269.31  4670.2  264.48  4708.2  267.81    4729  263.51    4768  263.22
  4773.7  260.36  4789.8  263.38  4795.5  260.16  4811.7   264.2  4817.4  260.88
  4833.5  263.16  4839.2  259.45  4849.6  260.86  4855.3  257.74  4871.5  261.16
  4877.2  258.13  4893.3  260.95    4899  258.08  4915.1  261.75  4920.8  259.69
  4954.1  262.45  4982.1  259.92  4999.5   256.7  5002.2   256.2  5005.5   256.7
  5018.6  259.88    5106  259.26  5209.5  269.84  5272.7  272.42  5404.2  277.09
#Mann= 7 ,-1 , 0
  4584.2     .07       0    4729      .1       0  4954.1     .07       0
  4982.1      .1       0  4999.5     .07       0  5005.5      .1       0
  5272.7     .05       0
Bank Sta=4999.5,5005.5
XS Rating Curve= 0 ,0
Exp/Cntr=0.3,0.1

Type RM Length L Ch R = 1 ,1140    ,102,102,102
BEGIN DESCRIPTION:
Mapping XS 33850514
END DESCRIPTION:
XS GIS Cut Line= 2
      3592275.53     10255114.54      3592676.48     10254726.61
#Sta/Elev= 30
  4815.6  266.73  4900.1  256.31  4907.3  256.89  4942.5  253.39  4949.7  254.05
  4970.8   252.6  4977.8   252.5    4985  254.57  4991.9   251.6  4999.1  252.32
  5003.1  249.27  5005.8  248.77  5009.1  249.27  5020.2  250.57  5027.4  253.74
  5034.4  252.51  5041.5  254.05  5048.5  252.93  5055.7  255.23  5062.7  254.11
  5105.1  261.61  5133.4  260.83  5282.1  266.62  5317.3  269.65  5324.5  269.19
  5345.6  272.28  5352.8  271.57  5359.8  273.23    5367   272.2  5373.5  273.77
#Mann= 3 ,-1 , 0
  4815.6      .1       0  5003.1     .07       0  5009.1      .1       0
Bank Sta=5003.1,5009.1
XS Rating Curve= 0 ,0
Exp/Cntr=0.3,0.1

Type RM Length L Ch R = 1 ,1038    ,244,244,244
BEGIN DESCRIPTION:
Mapping XS 62a4c6ca
END DESCRIPTION:
XS GIS Cut Line= 2
      3592343.26     10255182.22       3592757.4     10254806.91
#Sta/Elev= 30
    4813  268.84  4890.7  261.69  4925.9  262.39  4954.2   254.3    4961  254.69
  4968.4  252.17  4975.2   254.3  4982.6  251.02  4989.4  253.15  4993.8  248.84
  4996.6  248.34  4999.8  248.84    5011  249.39  5017.8  252.06  5025.2   251.7
    5032  253.16  5053.6  253.34  5060.3  254.83  5067.8  253.93  5074.5  255.59
  5088.7  254.87  5095.5  256.44  5159.7   259.1  5180.6  261.61    5209  262.84
  5223.2  261.05    5230  262.53  5237.4  261.26  5244.2   262.7  5371.9  268.63
#Mann= 3 ,-1 , 0
    4813     .05       0  4993.8     .04       0  4999.8     .05       0
Bank Sta=4993.8,4999.8
XS Rating Curve= 0 ,0
Exp/Cntr=0.3,0.1

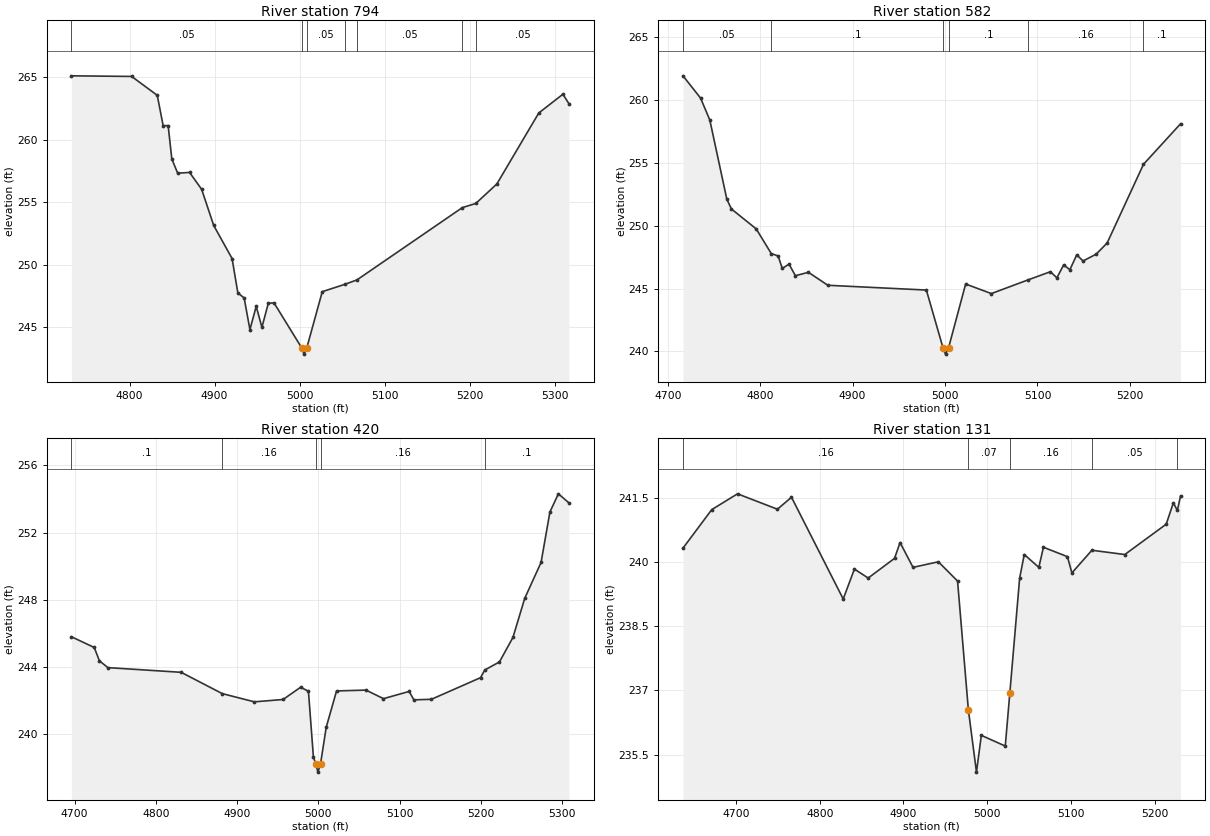
Type RM Length L Ch R = 1 ,794     ,212,212,212
BEGIN DESCRIPTION:
UNT04977 IN WICK 2.0
END DESCRIPTION:
XS GIS Cut Line= 3
      3592421.34     10255249.94      3592530.76     10255242.13
      3592882.33     10254921.81
#Sta/Elev= 30
  4731.6   265.1  4802.5  265.05  4832.6  263.54  4839.5  261.12  4845.4  261.12
  4849.7  258.46  4856.6  257.32  4870.6  257.38  4884.8  256.03    4899  253.14
  4920.6   250.5  4927.4  247.75  4934.8  247.35  4941.6  244.82    4949  246.68
  4955.7     245  4963.2  246.92  4969.9  246.96  5002.5  243.36  5005.2  242.86
  5008.5  243.36  5026.7  247.85  5052.9  248.43  5067.5  248.79  5191.5  254.57
  5207.3   254.9  5232.1  256.46  5281.4  262.13  5309.8  263.63  5316.9  262.87
#Mann= 7 ,-1 , 0
  4731.6     .05       0  5002.5     .04       0  5008.5     .05       0
  5052.9      .1       0  5067.5     .05       0  5191.5     .16       0
  5207.3     .05       0
Bank Sta=5002.5,5008.5
XS Rating Curve= 0 ,0
Exp/Cntr=0.3,0.1

Type RM Length L Ch R = 1 ,582     ,162,162,162
BEGIN DESCRIPTION:
Mapping XS 62c8efae
END DESCRIPTION:
XS GIS Cut Line= 4
      3592583.14     10255330.19      3592682.06     10255323.25
      3592925.11      10255061.1      3592926.85     10254979.47
#Sta/Elev= 30
  4716.5   261.9  4735.5  260.13  4745.5  258.39  4763.9   252.1  4768.9  251.32
  4795.7  249.74    4812  247.78  4819.4  247.59  4823.9   246.6  4831.2  246.94
  4838.1  246.02  4852.2  246.29  4873.2  245.26  4979.8  244.88  4997.8  240.29
  5000.5  239.79  5003.8  240.29  5022.3  245.36  5050.1   244.6  5089.9  245.69
  5114.1  246.34    5121  245.85  5128.3  246.87  5135.1   246.5  5142.5  247.68
  5149.3  247.19  5163.5  247.73  5175.4  248.62  5214.7  254.87  5254.8  258.09
#Mann= 6 ,-1 , 0
  4716.5     .05       0    4812      .1       0  4997.8     .07       0
  5003.8      .1       0  5089.9     .16       0  5214.7      .1       0
Bank Sta=4997.8,5003.8
XS Rating Curve= 0 ,0
Exp/Cntr=0.3,0.1

Type RM Length L Ch R = 1 ,420     ,289,289,289
BEGIN DESCRIPTION:
Mapping XS b36c3270
END DESCRIPTION:
XS GIS Cut Line= 5
        3592689.     10255384.02      3592841.78     10255340.61
      3592925.58      10255293.2      3593028.75      10255114.5
      3592989.35      10254969.1
#Sta/Elev= 30
  4696.1  245.79  4724.2  245.15  4730.5  244.36  4740.9  243.95  4831.1  243.67
  4881.7   242.4  4921.2  241.91  4956.5  242.05  4978.1  242.78  4987.7  242.54
  4993.8  238.63  4996.6  238.22  4999.4  237.72  5002.6  238.22  5009.6   240.4
  5022.3  242.56  5058.5  242.61    5080   242.1  5111.6  242.53  5117.4  242.03
  5138.9  242.06  5199.4  243.35  5204.7  243.81  5222.7  244.29  5239.3  245.75
  5253.8  248.08  5273.9  250.22  5284.8  253.23  5295.2  254.31  5308.2  253.77
#Mann= 5 ,-1 , 0
  4696.1      .1       0  4881.7     .16       0  4996.6     .07       0
  5002.6     .16       0  5204.7      .1       0
Bank Sta=4996.6,5002.6
XS Rating Curve= 0 ,0
Exp/Cntr=0.3,0.1

Type RM Length L Ch R = 1 ,131     ,0,0,0
BEGIN DESCRIPTION:
UNT04977 IN WICK 1.0
END DESCRIPTION:
XS GIS Cut Line= 4
      3592931.48     10255527.72      3593143.33     10255444.37
      3593233.61     10255249.92      3593185.43     10255105.38
#Sta/Elev= 30
  4636.7  240.33    4671  241.23  4701.8   241.6  4749.5  241.24  4766.3  241.52
  4828.1  239.14  4841.5  239.84  4857.9  239.63  4889.4  240.09    4896  240.46
  4911.5  239.88  4941.8  240.01  4964.7  239.56  4977.6  236.55  4987.3  235.09
  4993.1  235.95  5021.7   235.7 5027.16  236.94  5038.9  239.63  5044.4  240.18
  5061.8  239.88  5067.3  240.35    5096  240.13  5101.3  239.75  5125.2  240.28
  5164.5  240.18    5214  240.89  5222.5  241.39  5227.3  241.21  5231.1  241.55
#Mann= 5 ,-1 , 0
  4636.7     .16       0  4977.6     .07       0 5027.16     .16       0
  5125.2     .05       0  5227.3     .16       0
Bank Sta=4977.6,5027.16
XS Rating Curve= 0 ,0
Exp/Cntr=0.3,0.1

Chan Stop Cuts=-1
Use User Specified Reach Order=0
Composite Channel Slope=5